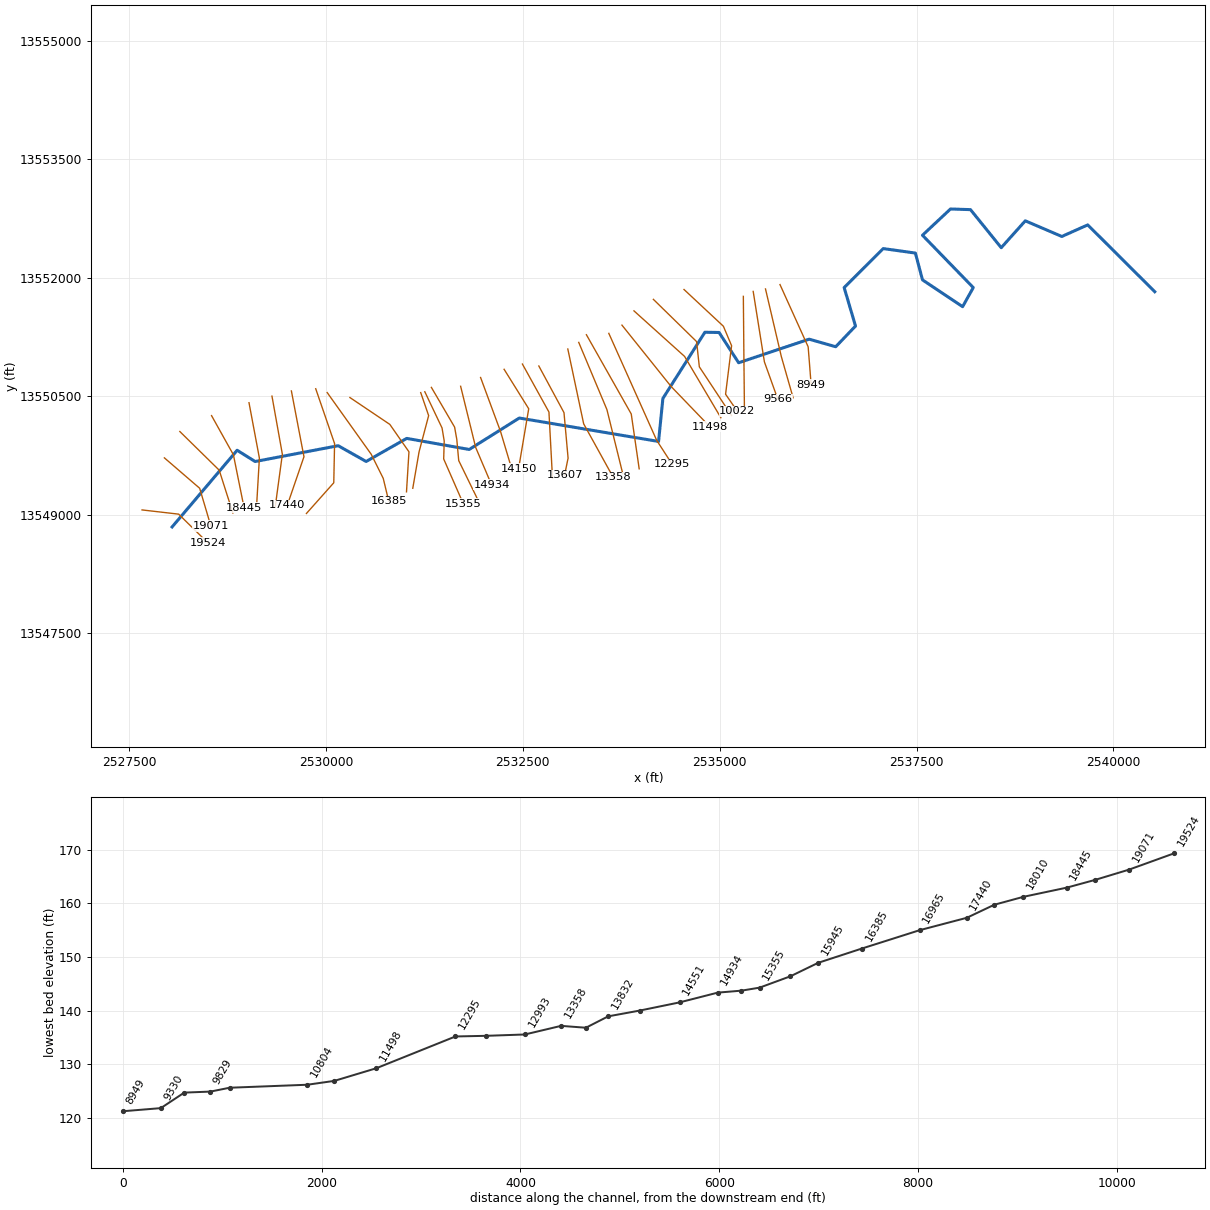
--- CARLISLE CREEK.prj (project) ---

Proj Title=CARLISLE CREEK Base Level Engineering
Current Plan=p01
Default Exp/Contr=0.3,0.1
English Units
Geom File=g01
Flow File=f01
Plan File=p01
Y Axis Title=Elevation
X Axis Title(PF)=Main Channel Distance
X Axis Title(XS)=Station
BEGIN DESCRIPTION:
CARLISLE CREEK
END DESCRIPTION:
DSS Export Rating Curves= 0
DSS Export Rating Curve Sorted= 0
DSS Export Volume Flow Curves= 0
DXF OffsetX= 0
DXF OffsetY= 0
DXF ScaleX= 1
DXF ScaleY= 10

--- CARLISLE CREEK.p01 (plan) ---

Plan Title=Multiple Run
Short Identifier=Multiple
Geom File=g01
Flow File=f01
Subcritical Flow
K Sum by GR= 0
Std Step Tol= 0.01
Critical Tol= 0.01
Num of Std Step Trials= 20
Max Error Tol= 0.3
Flow Tol Ratio= 0.001
Split Flow NTrial= 30
Split Flow Tol= 0.02
Split Flow Ratio= 0.02
Log Output Level= 0
Friction Slope Method= 1
Unsteady Friction Slope Method= 2
Unsteady Bridges Friction Slope Method= 1
Parabolic Critical Depth
Global Vel Dist=  1 , 1 , 1
Global Log Level= 0
CheckData=True
Encroach Param= -1, 0, 0, 0
BEGIN DESCRIPTION:
Multiple Run
END DESCRIPTION:

--- CARLISLE CREEK.f01 (steady flow) ---

Flow Title=Multiple
Number of Profiles=7
Profile Names=10-year,25-year,50-year,1pct_min,100-year,1pct_plu,500-year
River Rch & RM= CARLISLE CREEK,Reach-1,19524
     535     849    1128     727    1450    2892    2366
River Rch & RM= CARLISLE CREEK,Reach-1,19071
     836    1363    1844    1207    2409    4806    4066
River Rch & RM= CARLISLE CREEK,Reach-1,17440
     867    1416    1918    1257    2508    5004    4241
River Rch & RM= CARLISLE CREEK,Reach-1,16385
    1058    1747    2385    1574    3141    6266    5389
River Rch & RM= CARLISLE CREEK,Reach-1,15665
    2113    3605    5027    3381    6746   13459   12025
River Rch & RM= CARLISLE CREEK,Reach-1,11076
    2211    3776    5269    3545    7074   14114   12625
River Rch & RM= CARLISLE CREEK,Reach-1,9330
    2033    3458    4812    3231    6448   12865   11473
River Rch & RM= CARLISLE CREEK,Reach-1,6616
    2373    4055    5659    3806    7594   15152   13542
River Rch & RM= CARLISLE CREEK,Reach-1,3209
    3302    5728    8079    5490   10954   21855   19961
Boundary for River Rch & Prof#=CARLISLE CREEK,Reach-1,1
Up Type=0
Dn Type=3
Dn Slope=0.005
Boundary for River Rch & Prof#=CARLISLE CREEK,Reach-1,2
Up Type=0
Dn Type=3
Dn Slope=0.005
Boundary for River Rch & Prof#=CARLISLE CREEK,Reach-1,3
Up Type=0
Dn Type=3
Dn Slope=0.005
Boundary for River Rch & Prof#=CARLISLE CREEK,Reach-1,4
Up Type=0
Dn Type=3
Dn Slope=0.005
Boundary for River Rch & Prof#=CARLISLE CREEK,Reach-1,5
Up Type=0
Dn Type=3
Dn Slope=0.005
Boundary for River Rch & Prof#=CARLISLE CREEK,Reach-1,6
Up Type=0
Dn Type=3
Dn Slope=0.005
Boundary for River Rch & Prof#=CARLISLE CREEK,Reach-1,7
Up Type=0
Dn Type=3
Dn Slope=0.005

--- CARLISLE CREEK.g01 (geometry) ---

Geom Title=Existing Conditions

River Reach=CARLISLE CREEK,Reach-1
Reach XY= 30
      2528045.56     13548845.56      2528871.59     13549817.23
      2529099.81     13549674.51      2530154.97     13549874.94
      2530509.95     13549675.12      2531025.00     13549967.44
      2531819.07     13549827.24      2532454.86     13550225.40
      2534223.55     13549928.53      2534278.54     13550473.54
      2534811.68     13551311.63      2534992.24     13551308.76
      2535240.21     13550925.51      2536135.54     13551223.92
      2536473.50     13551128.47      2536724.63     13551390.27
      2536580.35     13551877.70      2537076.46     13552371.46
      2537485.12     13552314.37      2537575.00     13551975.00
      2538084.81     13551635.43      2538219.91     13551877.30
      2537574.89     13552540.36      2537930.88     13552872.88
      2538184.82     13552864.53      2538575.00     13552382.50
      2538880.67     13552723.02      2539345.10     13552524.88
      2539673.44     13552671.26      2540525.00     13551825.00

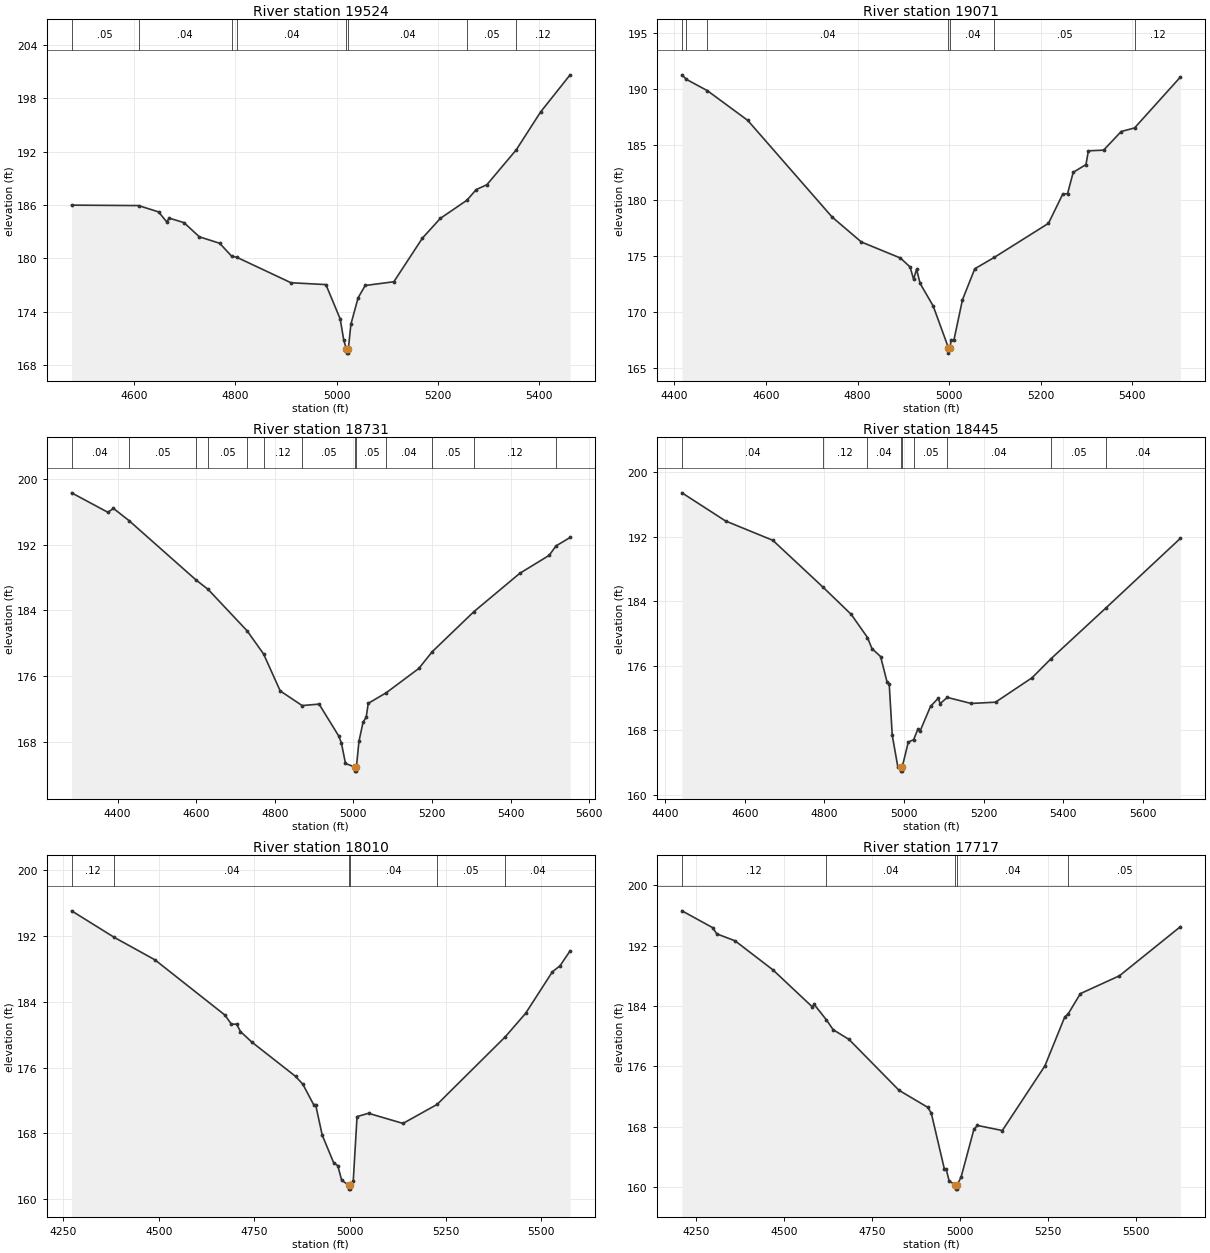
Type RM Length L Ch R = 1,19524,453,453,453
BEGIN DESCRIPTION:
LGII3443
END DESCRIPTION:
XS GIS Cut Line= 3
      2527664.22     13549061.54      2528129.13     13549008.19
      2528498.80     13548646.13
#Sta/Elev= 30
  4476.1  186.00  4608.4  185.95  4648.0  185.24  4664.1  184.12  4669.1  184.54
  4698.3  184.03  4728.5  182.44  4768.8  181.71  4792.4  180.26  4803.2  180.12
  4909.7  177.27  4978.8  177.06  5007.1  173.18  5014.1  170.80  5019.2  169.85
  5019.5  169.35  5023.0  169.35  5023.2  169.85  5028.2  172.60  5042.4  175.57
  5056.5  176.96  5113.1  177.38  5169.7  182.30  5205.0  184.51  5257.5  186.55
  5275.7  187.74  5297.0  188.30  5355.0  192.22  5403.0  196.47  5461.5  200.66
#Mann=8,-1,0
  4476.1    0.05       0  4608.4    0.04       0  4792.4    0.05       0
  4803.2    0.04       0  5019.2    0.04       0  5023.2    0.04       0
  5257.5    0.05       0  5355.0    0.12       0
Bank Sta=5019.2,5023.2
Exp/Cntr=0.3,0.1

Type RM Length L Ch R = 1,19071,340,340,340
BEGIN DESCRIPTION:
CARLISLE CREEK 35.0
END DESCRIPTION:
XS GIS Cut Line= 3
      2527947.88     13549720.87      2528395.88     13549335.92
      2528537.72     13548858.62
#Sta/Elev= 30
  4416.5  191.25  4426.0  190.85  4472.0  189.83  4560.1  187.17  4744.5  178.50
  4808.2  176.27  4893.7  174.83  4914.6  174.03  4922.3  172.93  4928.8  173.83
  4936.5  172.56  4965.0  170.54  4998.2  166.81  4998.4  166.31  5002.2  166.81
  5004.0  167.47  5010.3  167.47  5029.0  171.09  5055.9  173.87  5098.9  174.90
  5216.8  177.94  5248.1  180.57  5258.5  180.60  5270.8  182.51  5298.7  183.21
  5304.0  184.44  5337.2  184.50  5375.6  186.17  5404.8  186.49  5505.1  191.06
#Mann=7,-1,0
  4416.5    0.04       0  4426.0    0.05       0  4472.0    0.04       0
  4998.2    0.04       0  5002.2    0.04       0  5098.9    0.05       0
  5404.8    0.12       0
Bank Sta=4998.2,5002.2
Exp/Cntr=0.3,0.1

Type RM Length L Ch R = 1,18731,286,286,286
BEGIN DESCRIPTION:
Mapping XS cf108506
END DESCRIPTION:
XS GIS Cut Line= 3
      2528143.96     13550054.54      2528643.94     13549564.97
      2528817.57     13549023.27
#Sta/Elev= 30
  4283.1  198.32  4375.4  195.95  4389.6  196.42  4429.1  194.94  4600.2  187.68
  4630.3  186.56  4729.8  181.50  4771.8  178.67  4813.9  174.18  4869.8  172.39
  4912.9  172.57  4962.4  168.72  4969.5  167.87  4980.1  165.33  5003.9  164.90
  5004.1  164.40  5007.6  164.40  5007.9  164.90  5014.3  168.02  5024.8  170.35
  5032.8  170.98  5038.0  172.66  5084.0  173.96  5166.6  176.91  5200.9  178.96
  5306.2  183.81  5423.6  188.51  5498.4  190.70  5515.8  191.85  5551.7  192.88
#Mann=13,-1,0
  4283.1    0.04       0  4429.1    0.05       0  4600.2    0.04       0
  4630.3    0.05       0  4729.8    0.04       0  4771.8    0.12       0
  4869.8    0.05       0  5003.9    0.05       0  5007.9    0.05       0
  5084.0    0.04       0  5200.9    0.05       0  5306.2    0.12       0
  5515.8    0.04       0
Bank Sta=5003.9,5007.9
Exp/Cntr=0.3,0.1

Type RM Length L Ch R = 1,18445,435,435,435
BEGIN DESCRIPTION:
Mapping XS 7cd668a4
END DESCRIPTION:
XS GIS Cut Line= 3
      2528546.71     13550255.96      2528824.50     13549759.42
      2528959.85     13549089.62
#Sta/Elev= 30
  4442.4  197.46  4551.9  193.97  4670.7  191.57  4797.2  185.74  4867.5  182.39
  4908.4  179.52  4919.6  178.15  4941.3  177.16  4957.3  174.06  4963.0  173.76
  4970.6  167.41  4984.7  163.47  4991.5  163.45  4991.8  162.95  4995.3  162.95
  4995.6  163.45  5011.0  166.56  5024.2  166.84  5035.2  168.17  5040.3  167.89
  5066.9  170.99  5085.9  171.97  5091.0  171.33  5109.0  172.09  5168.9  171.34
  5230.1  171.50  5321.9  174.53  5369.5  176.89  5507.3  183.18  5694.7  191.83
#Mann=9,-1,0
  4442.4    0.04       0  4797.2    0.12       0  4908.4    0.04       0
  4991.5    0.04       0  4995.6    0.04       0  5024.2    0.05       0
  5109.0    0.04       0  5369.5    0.05       0  5507.3    0.04       0
Bank Sta=4991.5,4995.6
Exp/Cntr=0.3,0.1

Type RM Length L Ch R = 1,18010,293,293,293
BEGIN DESCRIPTION:
Mapping XS 0a14c5b3
END DESCRIPTION:
XS GIS Cut Line= 3
      2529022.42     13550419.13      2529154.36     13549717.75
      2529119.71     13549128.75
#Sta/Elev= 30
  4271.9  195.04  4383.7  191.81  4489.8  189.09  4672.9  182.38  4689.9  181.27
  4703.5  181.28  4713.6  180.38  4742.4  179.13  4857.5  174.94  4876.5  173.99
  4904.9  171.50  4910.0  171.51  4927.3  167.80  4957.4  164.43  4968.0  164.09
  4978.2  162.31  4996.3  161.74  4996.6  161.24  5000.2  161.24  5000.4  161.74
  5008.4  162.18  5018.4  170.05  5048.4  170.45  5138.6  169.22  5227.8  171.53
  5405.8  179.73  5459.2  182.59  5529.3  187.64  5549.3  188.37  5575.6  190.18
#Mann=6,-1,0
  4271.9    0.12       0  4383.7    0.04       0  4996.3    0.04       0
  5000.4    0.04       0  5227.8    0.05       0  5405.8    0.04       0
Bank Sta=4996.3,5000.4
Exp/Cntr=0.3,0.1

Type RM Length L Ch R = 1,17717,277,277,277
BEGIN DESCRIPTION:
Mapping XS cf9e43d9
END DESCRIPTION:
XS GIS Cut Line= 3
      2529314.08     13550502.49      2529446.03     13549766.36
      2529355.74     13549103.13
#Sta/Elev= 30
  4210.4  196.61  4297.4  194.39  4309.4  193.56  4361.3  192.64  4468.8  188.80
  4581.3  183.88  4586.4  184.21  4621.1  182.17  4640.2  180.87  4685.3  179.58
  4827.6  172.84  4908.8  170.60  4919.0  169.85  4956.4  162.42  4961.5  162.42
  4969.7  160.88  4987.9  160.26  4988.1  159.76  4991.7  159.76  4992.0  160.26
  5004.0  161.36  5040.4  167.69  5050.5  168.19  5121.1  167.52  5242.2  176.08
  5298.6  182.56  5308.2  182.96  5343.1  185.65  5454.1  188.01  5627.6  194.52
#Mann=5,-1,0
  4210.4    0.12       0  4621.1    0.04       0  4987.9    0.04       0
  4992.0    0.04       0  5308.2    0.05       0
Bank Sta=4987.9,4992
Exp/Cntr=0.3,0.1

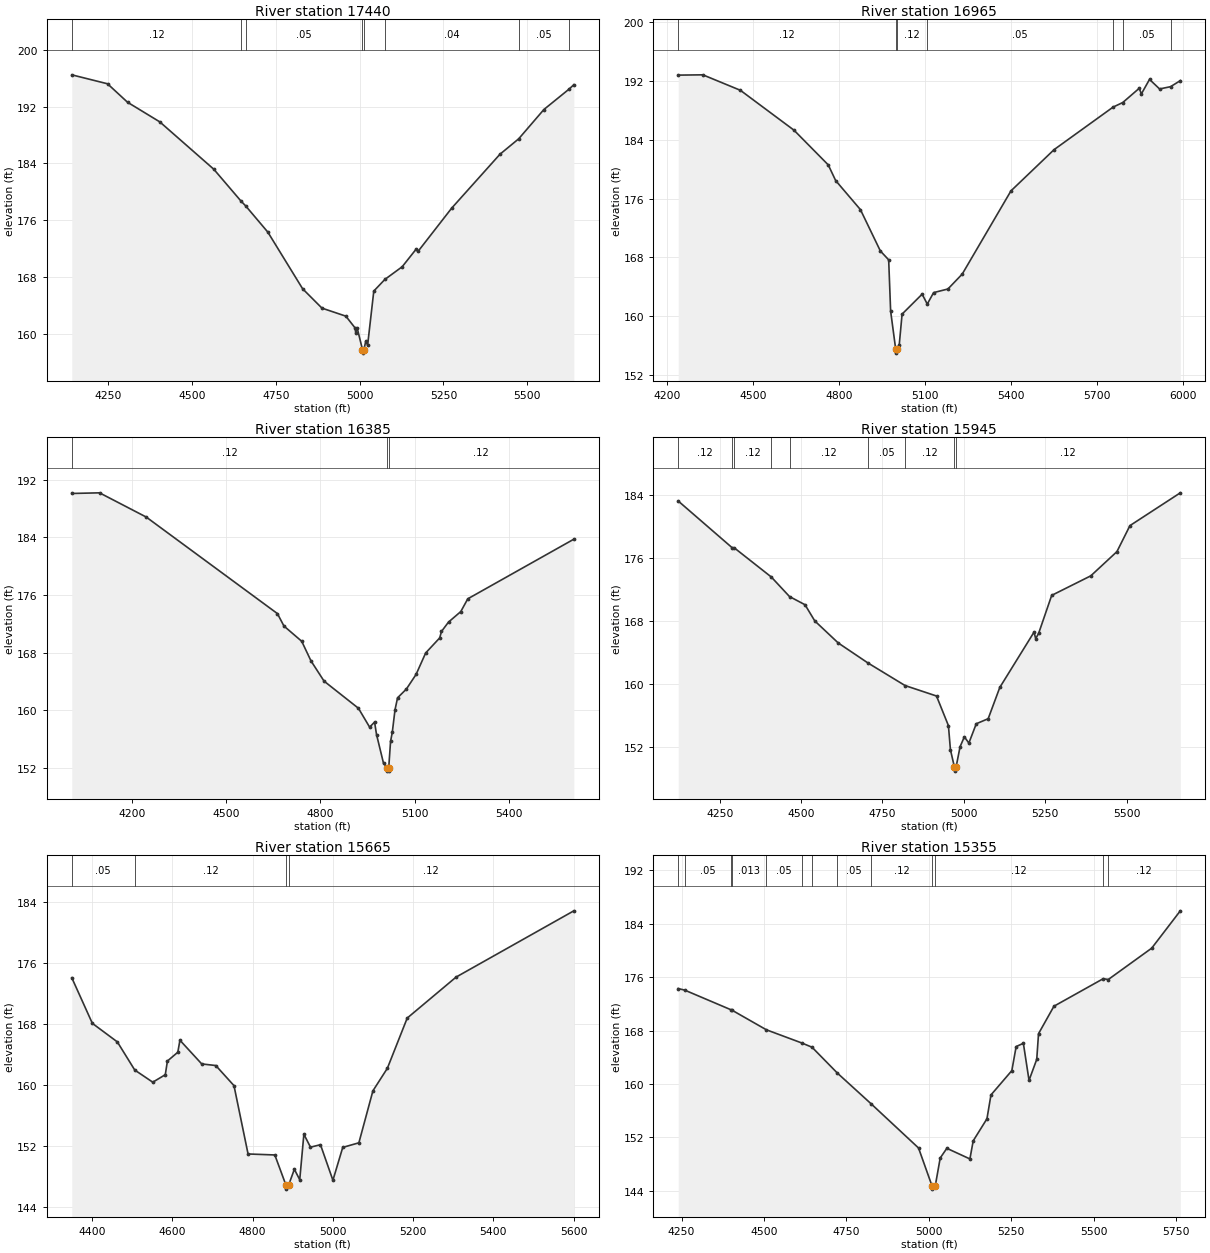
Type RM Length L Ch R = 1,17440,475,475,475
BEGIN DESCRIPTION:
Mapping XS ceccdcf7
END DESCRIPTION:
XS GIS Cut Line= 3
      2529560.60     13550568.48      2529720.33     13549735.11
      2529508.52     13549120.52
#Sta/Elev= 30
  4140.7  196.47  4247.4  195.21  4307.2  192.61  4403.5  189.85  4564.6  183.19
  4646.0  178.70  4659.8  178.03  4725.8  174.35  4829.8  166.37  4887.5  163.65
  4958.8  162.52  4985.9  160.89  4988.4  160.16  4992.4  160.89  5008.4  157.82
  5008.7  157.32  5012.6  157.82  5018.4  159.02  5023.7  158.42  5042.2  166.05
  5075.3  167.69  5126.9  169.47  5169.1  171.98  5174.4  171.64  5274.9  177.73
  5418.8  185.30  5474.7  187.47  5549.9  191.59  5624.0  194.42  5639.3  195.08
#Mann=8,-1,0
  4140.7    0.12       0  4646.0    0.04       0  4659.8    0.05       0
  5008.4    0.05       0  5012.6    0.05       0  5075.3    0.04       0
  5474.7    0.05       0  5624.0    0.04       0
Bank Sta=5008.4,5012.6
Exp/Cntr=0.3,0.1

Type RM Length L Ch R = 1,16965,580,580,580
BEGIN DESCRIPTION:
Mapping XS 2c2e3dcc
END DESCRIPTION:
XS GIS Cut Line= 4
      2529869.65     13550596.20      2530109.22     13549901.78
      2530098.80     13549405.25      2529751.56     13549016.34
#Sta/Elev= 30
  4238.9  192.76  4324.8  192.80  4455.8  190.70  4643.0  185.28  4762.5  180.57
  4788.4  178.44  4874.9  174.49  4944.4  168.88  4973.5  167.67  4980.3  160.71
  4998.1  155.50  4998.4  155.00  5002.4  155.50  5010.3  156.09  5020.3  160.30
  5090.3  163.01  5108.2  161.66  5130.3  163.22  5180.3  163.71  5230.3  165.74
  5400.4  177.04  5550.9  182.64  5757.0  188.42  5790.7  189.04  5848.1  190.97
  5855.6  190.21  5884.0  192.18  5919.2  190.88  5957.4  191.19  5991.5  192.01
#Mann=7,-1,0
  4238.9    0.12       0  4998.1    0.05       0  5002.4    0.12       0
  5108.2    0.05       0  5757.0    0.04       0  5790.7    0.05       0
  5957.4    0.04       0
Bank Sta=4998.1,5002.4
Exp/Cntr=0.3,0.1

Type RM Length L Ch R = 1,16385,440,440,440
BEGIN DESCRIPTION:
Mapping XS ee727dd4
END DESCRIPTION:
XS GIS Cut Line= 4
      2530015.48     13550547.61      2530574.50     13549766.36
      2530727.28     13549460.81      2530796.72     13549172.63
#Sta/Elev= 30
  4008.4  190.09  4096.8  190.18  4245.5  186.82  4663.2  173.43  4684.1  171.70
  4740.6  169.59  4770.1  166.87  4811.8  164.06  4921.2  160.30  4956.8  157.68
  4972.6  158.38  4978.8  156.66  5001.1  152.66  5012.8  152.08  5013.2  151.58
  5017.4  151.58  5017.7  152.08  5023.5  155.70  5029.1  157.00  5037.7  160.10
  5045.8  161.75  5073.8  162.96  5104.7  164.99  5135.3  167.97  5180.0  170.06
  5185.6  170.95  5208.0  172.25  5247.1  173.71  5269.4  175.48  5607.1  183.75
#Mann=3,-1,0
  4008.4    0.12       0  5012.8    0.05       0  5017.7    0.12       0
Bank Sta=5012.8,5017.7
Exp/Cntr=0.3,0.1

Type RM Length L Ch R = 1,15945,280,280,280
BEGIN DESCRIPTION:
Mapping XS de57b775
END DESCRIPTION:
XS GIS Cut Line= 4
      2530303.70     13550485.09      2530810.61     13550144.83
      2531053.67     13549797.61      2531022.41     13549290.62
#Sta/Elev= 30
  4122.8  183.18  4288.0  177.27  4294.9  177.24  4408.7  173.54  4464.6  171.06
  4512.3  170.02  4542.2  167.97  4614.3  165.17  4705.3  162.64  4819.5  159.77
  4916.2  158.44  4952.8  154.68  4958.9  151.63  4971.3  149.41  4971.7  148.91
  4976.2  149.41  4988.6  152.01  5001.7  153.26  5015.6  152.47  5038.3  154.92
  5074.9  155.56  5110.6  159.53  5215.8  166.55  5220.8  165.72  5229.9  166.39
  5270.0  171.21  5390.2  173.69  5470.4  176.76  5510.4  180.06  5665.1  184.22
#Mann=9,-1,0
  4122.8    0.12       0  4288.0    0.05       0  4294.9    0.12       0
  4408.7    0.05       0  4464.6    0.12       0  4705.3    0.05       0
  4819.5    0.12       0  4971.3    0.05       0  4976.2    0.12       0
Bank Sta=4971.3,4976.2
Exp/Cntr=0.3,0.1

Type RM Length L Ch R = 1,15665,310,310,310
BEGIN DESCRIPTION:
Mapping XS 13b77624
END DESCRIPTION:
XS GIS Cut Line= 4
      2531202.98     13550547.59      2531303.67     13550255.95
      2531182.14     13549797.61      2531102.27     13549335.77
#Sta/Elev= 30
  4349.4  174.05  4400.7  168.08  4463.0  165.65  4506.4  161.97  4551.3  160.38
  4582.5  161.36  4587.8  163.15  4613.7  164.30  4619.0  165.87  4673.3  162.77
  4708.4  162.56  4753.7  159.93  4788.8  150.99  4855.5  150.86  4883.4  146.89
  4883.9  146.39  4889.7  146.89  4904.2  148.99  4917.6  147.62  4927.9  153.57
  4944.4  151.88  4969.3  152.20  5000.3  147.55  5024.8  151.85  5065.0  152.45
  5100.0  159.25  5136.0  162.20  5185.5  168.77  5307.3  174.13  5600.8  182.80
#Mann=4,-1,0
  4349.4    0.05       0  4506.4    0.12       0  4883.4    0.05       0
  4889.7    0.12       0
Bank Sta=4883.4,4889.7
Exp/Cntr=0.3,0.1

Type RM Length L Ch R = 1,15355,182,182,182
BEGIN DESCRIPTION:
Mapping XS 84d775a5
END DESCRIPTION:
XS GIS Cut Line= 5
      2531255.04     13550558.06      2531473.80     13550099.70
      2531501.58     13549933.03      2531494.64     13549707.33
      2531744.17     13549138.96
#Sta/Elev= 30
  4239.9  174.29  4259.6  174.06  4399.9  171.12  4403.3  171.05  4507.4  168.12
  4615.2  166.14  4645.9  165.51  4723.0  161.63  4824.3  157.08  4969.0  150.43
  5009.8  144.77  5010.3  144.27  5019.8  144.77  5034.8  148.93  5054.9  150.38
  5124.9  148.79  5134.9  151.50  5176.6  154.80  5188.8  158.37  5252.1  162.01
  5265.2  165.61  5287.1  166.10  5304.3  160.55  5327.7  163.70  5333.1  167.54
  5379.9  171.65  5529.4  175.77  5544.8  175.65  5676.5  180.34  5763.3  185.93
#Mann=13,-1,0
  4239.9   0.013       0  4259.6    0.05       0  4399.9    0.12       0
  4403.3   0.013       0  4507.4    0.05       0  4615.2    0.12       0
  4645.9   0.013       0  4723.0    0.05       0  4824.3    0.12       0
  5009.8    0.05       0  5019.8    0.12       0  5529.4   0.013       0
  5544.8    0.12       0
Bank Sta=5009.8,5019.8
Exp/Cntr=0.3,0.1

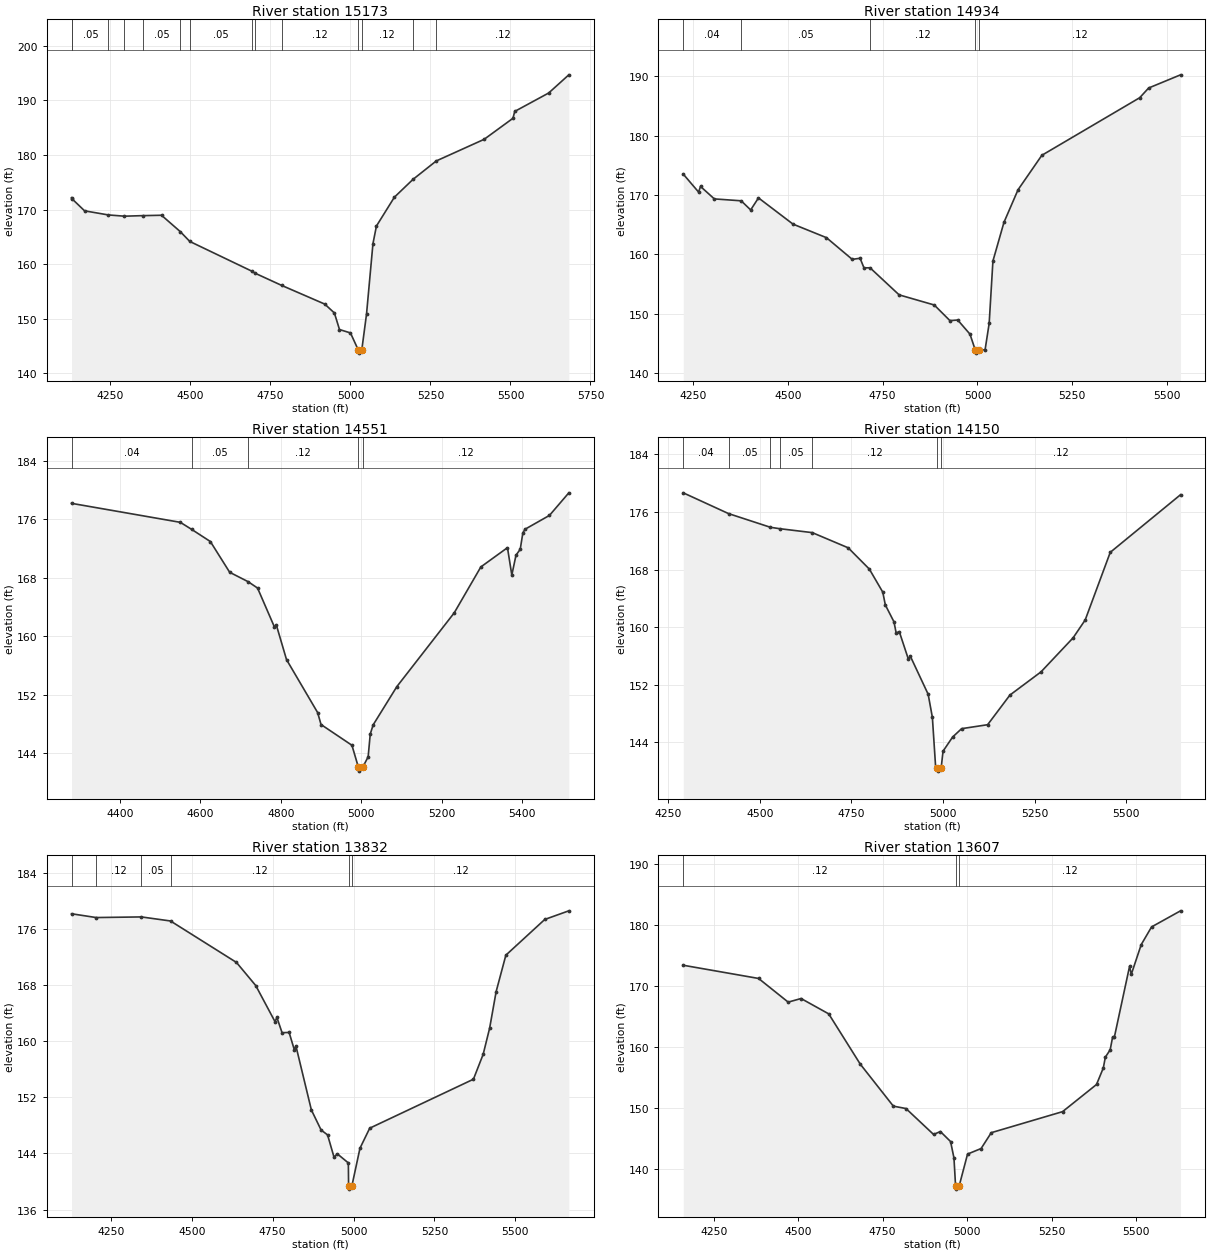
Type RM Length L Ch R = 1,15173,239,239,239
BEGIN DESCRIPTION:
Mapping XS 2ce09240
END DESCRIPTION:
XS GIS Cut Line= 5
      2531338.39     13550613.57      2531633.53     13550110.11
      2531661.30     13549953.86      2531685.61     13549686.50
      2531924.44     13549198.46
#Sta/Elev= 30
  4128.3  172.18  4130.8  171.92  4169.1  169.77  4243.2  169.02  4293.8  168.79
  4350.4  168.89  4409.5  168.96  4468.0  165.97  4498.0  164.16  4692.8  158.69
  4702.2  158.34  4785.5  156.10  4919.7  152.69  4949.8  151.06  4965.7  148.03
  5000.0  147.41  5025.0  144.21  5025.5  143.71  5035.2  144.21  5050.2  150.86
  5070.3  163.77  5081.2  166.99  5137.3  172.27  5195.0  175.51  5268.2  178.91
  5417.8  182.87  5507.8  186.72  5513.4  187.98  5619.4  191.35  5682.4  194.68
#Mann=14,-1,0
  4128.3    0.04       0  4130.8    0.05       0  4243.2   0.013       0
  4293.8    0.04       0  4350.4    0.05       0  4468.0   0.013       0
  4498.0    0.05       0  4692.8   0.013       0  4702.2    0.05       0
  4785.5    0.12       0  5025.0    0.05       0  5035.2    0.12       0
  5195.0   0.013       0  5268.2    0.12       0
Bank Sta=5025,5035.2
Exp/Cntr=0.3,0.1

Type RM Length L Ch R = 1,14934,383,383,383
BEGIN DESCRIPTION:
Mapping XS 16863386
END DESCRIPTION:
XS GIS Cut Line= 3
      2531709.91     13550627.49      2531900.89     13549853.17
      2532102.28     13549380.95
#Sta/Elev= 30
  4224.5  173.51  4264.9  170.48  4270.0  171.43  4306.4  169.33  4377.2  169.01
  4402.2  167.47  4422.8  169.50  4513.8  165.08  4601.9  162.80  4670.0  159.14
  4690.6  159.33  4700.9  157.71  4716.9  157.72  4793.5  153.16  4886.2  151.45
  4927.4  148.82  4948.0  148.92  4980.3  146.54  4994.4  143.84  4994.9  143.34
  5004.7  143.84  5020.2  143.92  5030.9  148.35  5040.8  158.86  5069.9  165.38
  5107.0  170.87  5169.8  176.68  5427.7  186.38  5451.3  188.02  5535.4  190.24
#Mann=5,-1,0
  4224.5    0.04       0  4377.2    0.05       0  4716.9    0.12       0
  4994.4    0.05       0  5004.7    0.12       0
Bank Sta=4994.4,5004.7
Exp/Cntr=0.3,0.1

Type RM Length L Ch R = 1,14551,401,401,401
BEGIN DESCRIPTION:
Mapping XS a6781a1d
END DESCRIPTION:
XS GIS Cut Line= 3
      2531963.40     13550738.55      2532216.86     13550054.56
      2532362.45     13549569.27
#Sta/Elev= 30
  4280.1  178.19  4550.5  175.59  4579.1  174.61  4625.2  172.96  4673.2  168.75
  4719.1  167.46  4742.5  166.59  4784.1  161.30  4789.4  161.49  4814.5  156.79
  4891.8  149.54  4900.3  147.90  4977.1  145.06  4993.3  142.02  4993.8  141.52
  5003.6  142.02  5017.4  143.48  5022.6  146.60  5030.0  147.87  5088.7  153.09
  5231.4  163.20  5297.5  169.48  5363.7  172.12  5374.5  168.37  5384.9  171.09
  5395.4  171.90  5401.9  174.13  5407.2  174.64  5468.1  176.54  5516.2  179.63
#Mann=5,-1,0
  4280.1    0.04       0  4579.1    0.05       0  4719.1    0.12       0
  4993.3    0.05       0  5003.6    0.12       0
Bank Sta=4993.3,5003.6
Exp/Cntr=0.3,0.1

Type RM Length L Ch R = 1,14150,318,318,318
BEGIN DESCRIPTION:
Mapping XS db7540c7
END DESCRIPTION:
XS GIS Cut Line= 3
      2532261.98     13550842.77      2532574.50     13550342.75
      2532446.03     13549585.83
#Sta/Elev= 30
  4290.9  178.66  4414.7  175.77  4528.9  173.87  4553.7  173.68  4643.1  173.13
  4741.1  171.02  4798.9  168.06  4835.5  164.86  4842.5  163.08  4866.1  160.73
  4872.0  159.19  4880.6  159.37  4905.5  155.53  4910.6  155.97  4959.4  150.67
  4970.9  147.46  4979.7  140.62  4984.6  140.49  4985.1  139.99  4995.0  140.49
  5000.0  142.76  5026.2  144.73  5050.7  145.89  5121.7  146.44  5182.6  150.56
  5267.4  153.78  5355.0  158.51  5388.0  160.99  5456.4  170.39  5648.3  178.40
#Mann=7,-1,0
  4290.9    0.04       0  4414.7    0.05       0  4528.9    0.04       0
  4553.7    0.05       0  4643.1    0.12       0  4984.6    0.05       0
  4995.0    0.12       0
Bank Sta=4984.6,4995
Exp/Cntr=0.3,0.1

Type RM Length L Ch R = 1,13832,225,225,225
BEGIN DESCRIPTION:
Mapping XS 40e1b200
END DESCRIPTION:
XS GIS Cut Line= 3
      2532494.62     13550908.76      2532831.44     13550301.08
      2532876.58     13549460.77
#Sta/Elev= 30
  4128.7  178.22  4204.9  177.68  4344.4  177.77  4434.5  177.19  4638.3  171.27
  4697.8  167.97  4757.4  162.81  4763.1  163.43  4779.1  161.24  4800.9  161.28
  4816.9  158.81  4822.0  159.33  4869.6  150.22  4899.7  147.35  4919.7  146.65
  4939.7  143.46  4949.7  143.95  4983.9  142.65  4984.6  139.41  4985.1  138.91
  4995.0  139.41  5019.8  144.75  5049.9  147.61  5370.3  154.60  5400.4  158.16
  5420.4  161.90  5440.5  167.12  5470.5  172.31  5590.7  177.41  5665.0  178.64
#Mann=6,-1,0
  4128.7    0.04       0  4204.9    0.12       0  4344.4    0.05       0
  4434.5    0.12       0  4984.6    0.05       0  4995.0    0.12       0
Bank Sta=4984.6,4995
Exp/Cntr=0.3,0.1

Type RM Length L Ch R = 1,13607,249,249,249
BEGIN DESCRIPTION:
Mapping XS bbedf7c3
END DESCRIPTION:
XS GIS Cut Line= 4
      2532702.99     13550884.38      2533022.42     13550294.14
      2533074.50     13549717.75      2533029.79     13549501.08
#Sta/Elev= 30
  4160.1  173.39  4383.0  171.23  4470.5  167.36  4508.6  167.95  4590.4  165.44
  4683.6  157.23  4781.6  150.35  4818.9  149.96  4900.6  145.72  4920.7  146.20
  4950.9  144.56  4960.9  141.88  4965.7  137.28  4966.2  136.78  4976.2  137.28
  5001.1  142.51  5041.2  143.42  5071.3  146.01  5282.2  149.45  5382.6  153.89
  5402.7  156.59  5408.8  158.37  5423.0  159.56  5430.2  161.64  5435.3  161.61
  5480.4  173.22  5485.5  171.91  5514.9  176.77  5545.5  179.66  5631.2  182.29
#Mann=3,-1,0
  4160.1    0.12       0  4965.7    0.05       0  4976.2    0.12       0
Bank Sta=4965.7,4976.2
Exp/Cntr=0.3,0.1

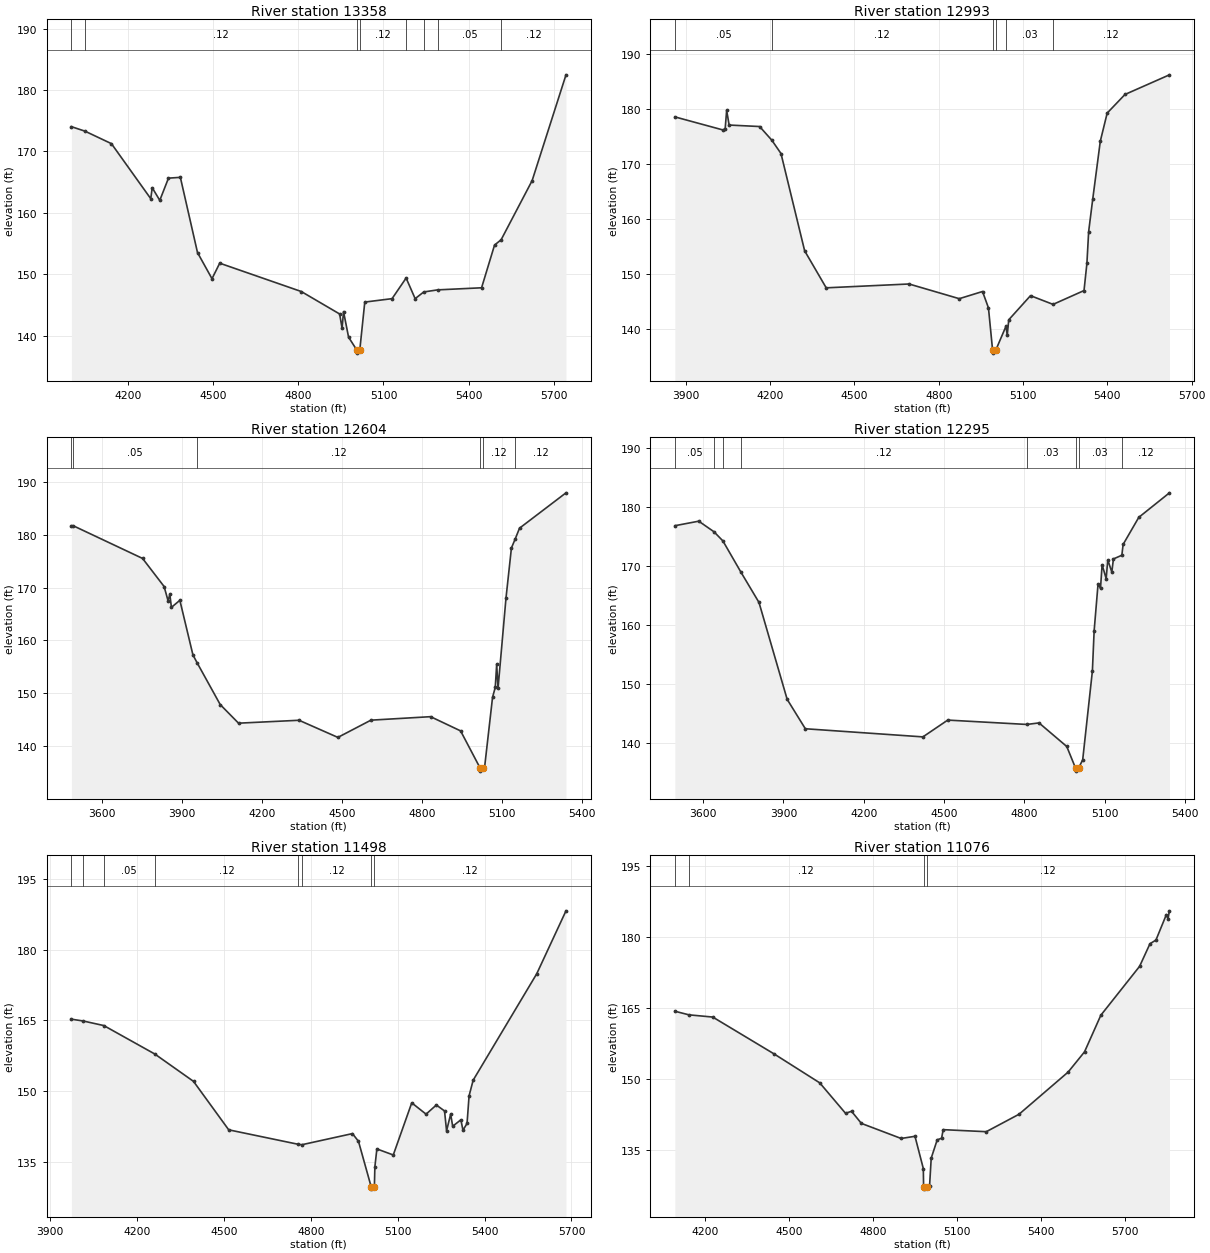
Type RM Length L Ch R = 1,13358,365,365,365
BEGIN DESCRIPTION:
Mapping XS fe59e439
END DESCRIPTION:
XS GIS Cut Line= 3
      2533071.04     13551099.65      2533272.42     13550151.78
      2533647.40     13549474.72
#Sta/Elev= 30
  4000.2  174.04  4048.0  173.31  4141.3  171.27  4279.9  162.30  4285.0  164.09
  4311.7  162.03  4342.3  165.65  4384.2  165.78  4444.6  153.52  4495.7  149.26
  4522.9  151.79  4810.4  147.17  4945.5  143.51  4954.1  141.20  4959.2  143.90
  4977.0  139.73  5006.0  137.63  5006.5  137.13  5016.5  137.63  5034.1  145.45
  5130.3  146.01  5179.8  149.37  5211.6  146.01  5241.9  147.10  5290.9  147.44
  5445.7  147.78  5491.4  154.74  5514.6  155.61  5623.8  165.24  5743.2  182.49
#Mann=8,-1,0
  4000.2    0.05       0  4048.0    0.12       0  5006.0    0.05       0
  5016.5    0.12       0  5179.8    0.05       0  5241.9    0.03       0
  5290.9    0.05       0  5514.6    0.12       0
Bank Sta=5006,5016.5
Exp/Cntr=0.3,0.1

Type RM Length L Ch R = 1,12993,389,389,389
BEGIN DESCRIPTION:
Mapping XS 5ad343c8
END DESCRIPTION:
XS GIS Cut Line= 3
      2533209.91     13551183.05      2533567.55     13550332.33
      2533768.91     13549519.96
#Sta/Elev= 30
  3861.2  178.61  4032.7  176.22  4040.1  176.38  4045.5  179.79  4054.3  177.12
  4162.8  176.85  4206.3  174.35  4238.8  171.93  4323.0  154.18  4399.7  147.43
  4694.4  148.13  4873.1  145.45  4955.9  146.76  4977.0  143.77  4991.8  136.02
  4992.3  135.52  5002.7  136.02  5039.4  140.43  5043.8  138.79  5049.2  141.60
  5126.6  146.00  5206.9  144.41  5317.0  146.93  5327.3  151.90  5333.5  157.69
  5347.9  163.56  5374.9  174.16  5399.4  179.30  5462.8  182.70  5621.0  186.28
#Mann=6,-1,0
  3861.2    0.05       0  4206.3    0.12       0  4991.8    0.05       0
  5002.7    0.12       0  5039.4    0.03       0  5206.9    0.12       0
Bank Sta=4991.8,5002.7
Exp/Cntr=0.3,0.1

Type RM Length L Ch R = 1,12604,309,309,309
BEGIN DESCRIPTION:
Mapping XS fe13be53
END DESCRIPTION:
XS GIS Cut Line= 3
      2533307.11     13551280.29      2533876.58     13550276.78
      2533977.27     13549582.38
#Sta/Elev= 30
  3483.8  181.68  3490.4  181.69  3750.8  175.50  3831.6  170.19  3846.3  167.52
  3853.2  168.69  3859.0  166.24  3890.7  167.58  3939.7  157.26  3955.0  155.80
  4042.1  147.86  4110.8  144.34  4337.8  144.89  4483.5  141.65  4607.5  144.91
  4831.4  145.57  4943.9  142.88  5018.0  135.77  5018.5  135.27  5028.9  135.77
  5033.5  135.81  5063.8  149.24  5073.9  151.10  5079.3  155.47  5084.3  150.90
  5114.3  168.05  5134.6  177.49  5148.3  179.12  5164.9  181.22  5339.3  187.91
#Mann=6,-1,0
  3483.8    0.04       0  3490.4    0.05       0  3955.0    0.12       0
  5018.0    0.05       0  5028.9    0.12       0  5148.3    0.12       0
Bank Sta=5018,5028.9
Exp/Cntr=0.3,0.1

Type RM Length L Ch R = 1,12295,797,797,797
BEGIN DESCRIPTION:
Mapping XS 6068fe88
END DESCRIPTION:
XS GIS Cut Line= 3
      2533591.85     13551297.64      2534199.50     13549943.45
      2534396.74     13549638.93
#Sta/Elev= 30
  3494.4  176.79  3583.6  177.56  3640.6  175.76  3673.8  174.21  3741.8  168.86
  3808.6  163.77  3913.8  147.33  3981.7  142.34  4420.8  140.96  4513.5  143.81
  4808.7  143.07  4854.4  143.33  4958.0  139.33  4990.9  135.65  4991.4  135.15
  5001.9  135.65  5017.5  137.07  5053.7  152.14  5060.2  158.94  5074.8  166.89
  5084.0  166.17  5090.0  170.17  5105.2  167.81  5111.1  170.99  5126.3  168.93
  5132.2  171.15  5163.7  171.78  5168.5  173.62  5227.0  178.21  5341.5  182.37
#Mann=8,-1,0
  3494.4    0.05       0  3640.6    0.12       0  3673.8    0.05       0
  3741.8    0.12       0  4808.7    0.03       0  4990.9    0.03       0
  5001.9    0.03       0  5163.7    0.12       0
Bank Sta=4990.9,5001.9
Exp/Cntr=0.3,0.1

Type RM Length L Ch R = 1,11498,422,422,422
BEGIN DESCRIPTION:
Mapping XS 8d8ad7bd
END DESCRIPTION:
XS GIS Cut Line= 3
      2533758.51     13551401.80      2534383.53     13550624.00
      2534876.60     13550113.57
#Sta/Elev= 30
  3973.5  165.23  4014.1  164.85  4085.4  163.88  4261.4  157.85  4395.1  152.05
  4516.6  141.78  4756.0  138.72  4769.1  138.62  4943.8  140.98  4964.6  139.34
  5008.4  129.71  5008.9  129.21  5019.5  129.71  5021.2  133.94  5028.1  137.73
  5084.7  136.45  5148.5  147.50  5197.9  145.10  5233.4  147.04  5261.7  145.78
  5268.7  141.56  5282.8  145.11  5289.8  142.54  5318.1  143.90  5325.3  141.70
  5339.4  143.13  5346.4  148.98  5360.5  152.30  5579.9  174.85  5681.0  188.20
#Mann=8,-1,0
  3973.5    0.04       0  4014.1    0.12       0  4085.4    0.05       0
  4261.4    0.12       0  4756.0    0.05       0  4769.1    0.12       0
  5008.4    0.05       0  5019.5    0.12       0
Bank Sta=5008.4,5019.5
Exp/Cntr=0.3,0.1

Type RM Length L Ch R = 1,11076,272,272,272
BEGIN DESCRIPTION:
Mapping XS f6f42dea
END DESCRIPTION:
XS GIS Cut Line= 3
      2533911.30     13551582.33      2534553.67     13551005.95
      2535014.91     13550229.11
#Sta/Elev= 30
  4091.0  164.36  4141.2  163.60  4226.4  163.13  4445.4  155.36  4608.4  149.26
  4700.6  142.84  4722.0  143.26  4757.2  140.71  4899.2  137.53  4948.6  137.99
  4978.4  131.19  4979.4  127.35  4979.9  126.85  4990.9  127.35  5000.7  127.50
  5006.6  133.39  5028.0  137.24  5043.6  137.58  5049.4  139.39  5203.3  138.96
  5320.3  142.64  5495.6  151.53  5554.1  155.79  5612.5  163.52  5750.9  173.83
  5787.9  178.59  5809.3  179.37  5846.4  184.73  5852.2  183.90  5857.5  185.53
#Mann=4,-1,0
  4091.0    0.04       0  4141.2    0.12       0  4979.4    0.05       0
  4990.9    0.12       0
Bank Sta=4979.4,4990.9
Exp/Cntr=0.3,0.1

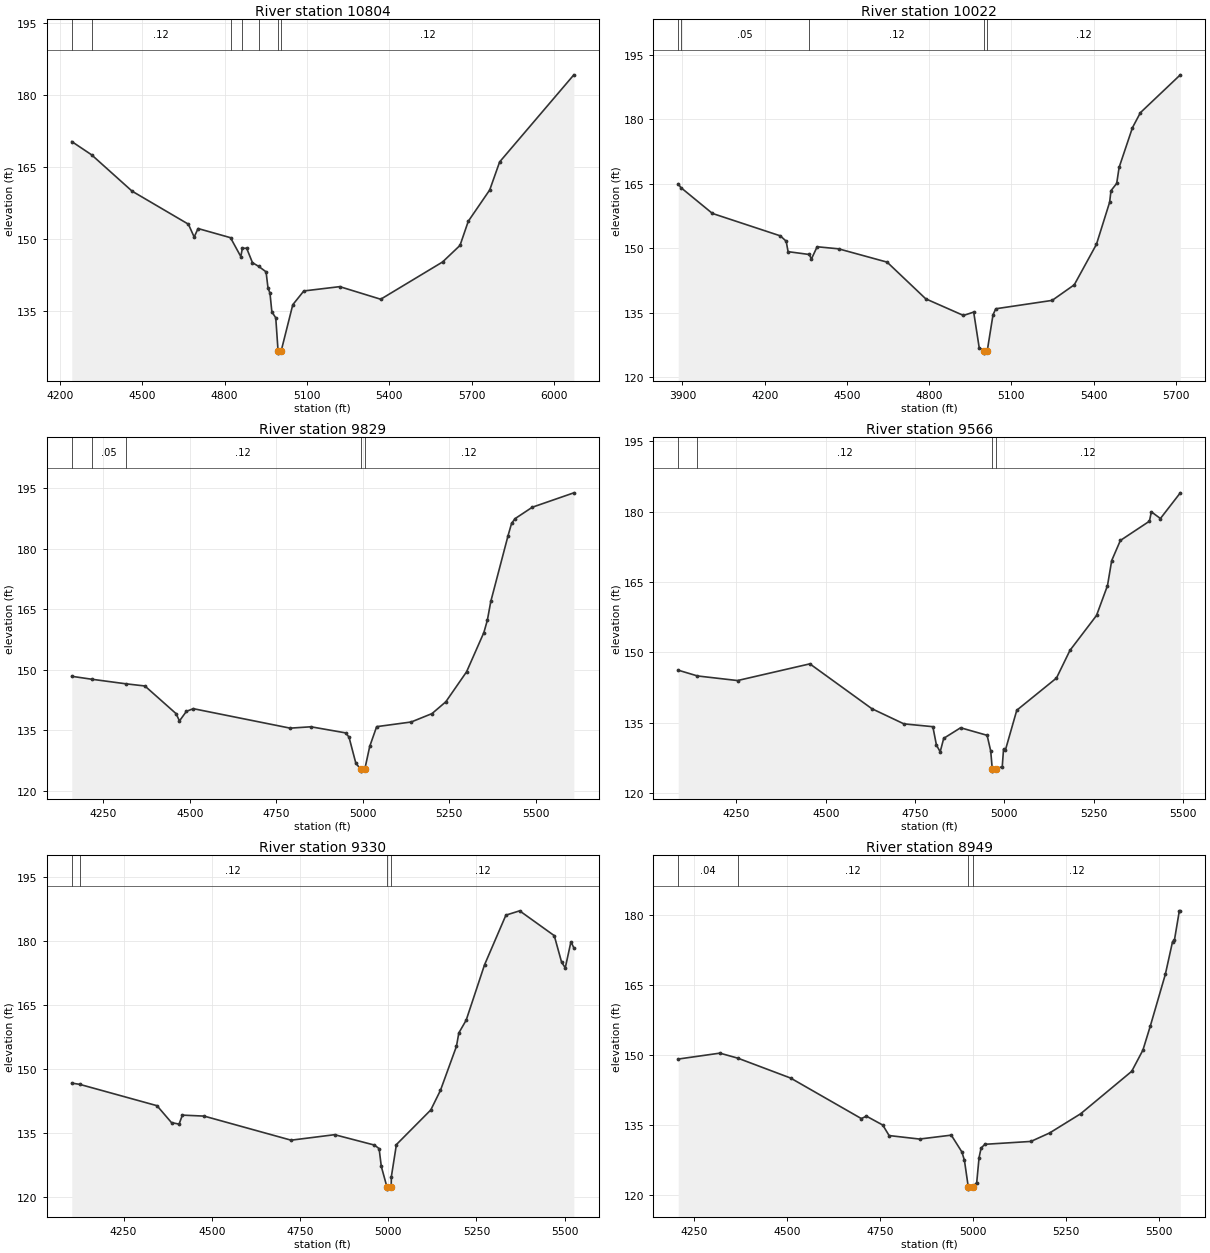
Type RM Length L Ch R = 1,10804,782,782,782
BEGIN DESCRIPTION:
Mapping XS 989f2dd4
END DESCRIPTION:
XS GIS Cut Line= 4
      2534157.80     13551728.19      2534706.44     13551193.45
      2534741.17     13550874.00      2535150.45     13550256.60
#Sta/Elev= 30
  4243.4  170.30  4315.6  167.53  4462.9  159.95  4668.0  153.05  4689.1  150.37
  4703.3  152.14  4821.4  150.23  4858.9  146.29  4864.6  148.01  4880.2  148.03
  4901.3  145.02  4924.2  144.23  4950.9  143.10  4957.9  139.74  4965.1  138.66
  4972.0  134.74  4986.2  133.50  4994.5  126.63  4995.0  126.13  5006.1  126.63
  5048.2  136.24  5088.4  139.11  5219.2  140.01  5368.3  137.38  5593.6  145.16
  5657.1  148.62  5687.2  153.66  5765.3  160.20  5801.4  166.05  6071.6  184.23
#Mann=7,-1,0
  4243.4    0.05       0  4315.6    0.12       0  4821.4    0.05       0
  4864.6    0.12       0  4924.2    0.05       0  4994.5    0.05       0
  5006.1    0.12       0
Bank Sta=4994.5,5006.1
Exp/Cntr=0.3,0.1

Type RM Length L Ch R = 1,10022,193,193,193
BEGIN DESCRIPTION:
Mapping XS 6ae7f97b
END DESCRIPTION:
XS GIS Cut Line= 5
      2534546.73     13551853.16      2535046.72     13551387.89
      2535150.89     13551141.36      2535074.50     13550526.78
      2535223.79     13550311.52
#Sta/Elev= 30
  3884.6  164.98  3893.9  164.14  4009.3  158.10  4257.1  152.88  4278.4  151.64
  4285.4  149.20  4362.8  148.54  4370.4  147.48  4391.4  150.34  4469.6  149.86
  4646.7  146.76  4787.8  138.21  4925.4  134.34  4962.6  135.13  4982.7  126.84
  5000.4  126.07  5000.9  125.57  5012.0  126.07  5033.1  134.49  5043.2  135.90
  5248.8  137.85  5329.6  141.48  5410.5  150.91  5458.7  160.73  5463.5  163.39
  5484.4  165.10  5493.2  168.82  5541.9  178.08  5570.9  181.57  5716.5  190.38
#Mann=5,-1,0
  3884.6    0.12       0  3893.9    0.05       0  4362.8    0.12       0
  5000.4    0.05       0  5012.0    0.12       0
Bank Sta=5000.4,5012
Exp/Cntr=0.3,0.1

Type RM Length L Ch R = 1,9829,263,263,263
BEGIN DESCRIPTION:
Mapping XS 41f813f9
END DESCRIPTION:
XS GIS Cut Line= 3
      2535300.19     13551766.38      2535307.14     13550999.00
      2535314.08     13550314.95
#Sta/Elev= 30
  4158.4  148.37  4216.3  147.64  4314.9  146.51  4369.8  145.97  4459.8  139.12
  4469.8  137.30  4489.8  139.68  4509.8  140.34  4789.8  135.51  4849.8  135.85
  4949.8  134.34  4959.8  133.32  4979.8  126.76  4994.0  125.35  4994.5  124.85
  5005.6  125.35  5019.8  130.99  5039.8  135.88  5139.8  137.04  5199.8  139.12
  5239.8  142.05  5299.8  149.49  5349.8  159.23  5359.8  162.26  5369.8  166.94
  5419.8  183.29  5429.8  186.28  5439.8  187.47  5489.8  190.31  5609.9  193.88
#Mann=5,-1,0
  4158.4    0.04       0  4216.3    0.05       0  4314.9    0.12       0
  4994.0    0.05       0  5005.6    0.12       0
Bank Sta=4994,5005.6
Exp/Cntr=0.3,0.1

Type RM Length L Ch R = 1,9566,236,236,236
BEGIN DESCRIPTION:
Mapping XS b3e1b7f5
END DESCRIPTION:
XS GIS Cut Line= 3
      2535425.19     13551828.89      2535567.55     13550936.50
      2535737.69     13550464.29
#Sta/Elev= 30
  4087.1  146.19  4141.0  144.96  4253.1  143.98  4455.6  147.54  4629.1  137.98
  4718.9  134.74  4799.9  134.14  4810.0  130.20  4820.5  128.79  4830.3  131.65
  4877.6  133.91  4951.8  132.30  4961.9  128.96  4966.2  125.16  4966.7  124.66
  4977.9  125.16  4994.2  125.63  4997.8  129.32  5003.2  129.20  5034.9  137.65
  5146.0  144.51  5183.7  150.41  5258.1  157.86  5288.8  164.22  5300.6  169.57
  5324.9  173.86  5406.3  177.97  5411.6  179.97  5437.0  178.54  5492.7  184.02
#Mann=4,-1,0
  4087.1    0.04       0  4141.0    0.12       0  4966.2    0.05       0
  4977.9    0.12       0
Bank Sta=4966.2,4977.9
Exp/Cntr=0.3,0.1

Type RM Length L Ch R = 1,9330,381,381,381
BEGIN DESCRIPTION:
Mapping XS 523593e1
END DESCRIPTION:
XS GIS Cut Line= 3
      2535581.45     13551860.08      2535782.83     13551002.47
      2535932.13     13550481.68
#Sta/Elev= 30
  4103.4  146.63  4125.7  146.34  4344.9  141.33  4386.0  137.36  4407.5  137.01
  4416.8  139.12  4478.4  138.89  4724.9  133.24  4848.2  134.53  4961.2  132.09
  4974.3  131.26  4980.5  127.09  4996.5  122.26  4997.0  121.76  5008.5  122.26
  5009.0  124.68  5023.3  132.21  5120.7  140.33  5148.1  144.93  5193.4  155.25
  5200.2  158.40  5221.0  161.39  5273.0  174.37  5333.6  186.03  5372.5  187.04
  5470.6  181.22  5491.4  174.99  5501.8  173.67  5517.9  179.79  5526.1  178.36
#Mann=4,-1,0
  4103.4    0.04       0  4125.7    0.12       0  4996.5    0.05       0
  5008.5    0.12       0
Bank Sta=4996.5,5008.5
Exp/Cntr=0.3,0.1

Type RM Length L Ch R = 1,8949,462,462,462
BEGIN DESCRIPTION:
Mapping XS 7f438353
END DESCRIPTION:
XS GIS Cut Line= 3
      2535765.47     13551915.66      2536123.11     13551127.47
      2536161.31     13550644.82
#Sta/Elev= 30
  4207.1  149.13  4319.0  150.40  4367.4  149.32  4509.1  145.05  4699.3  136.34
  4713.0  136.86  4756.9  134.95  4774.0  132.69  4855.7  131.94  4941.1  132.78
  4969.7  129.16  4976.5  127.35  4986.7  121.68  4987.2  121.18  4998.7  121.68
  5009.5  122.60  5015.8  127.95  5021.3  130.01  5031.4  130.81  5155.2  131.43
  5205.5  133.25  5288.8  137.37  5426.2  146.50  5456.3  151.06  5476.4  156.29
  5516.5  167.32  5535.9  174.34  5540.9  174.65  5554.2  180.98  5556.8  180.98
#Mann=4,-1,0
  4207.1    0.04       0  4367.4    0.12       0  4986.7    0.05       0
  4998.7    0.12       0
Bank Sta=4986.7,4998.7
Exp/Cntr=0.3,0.1