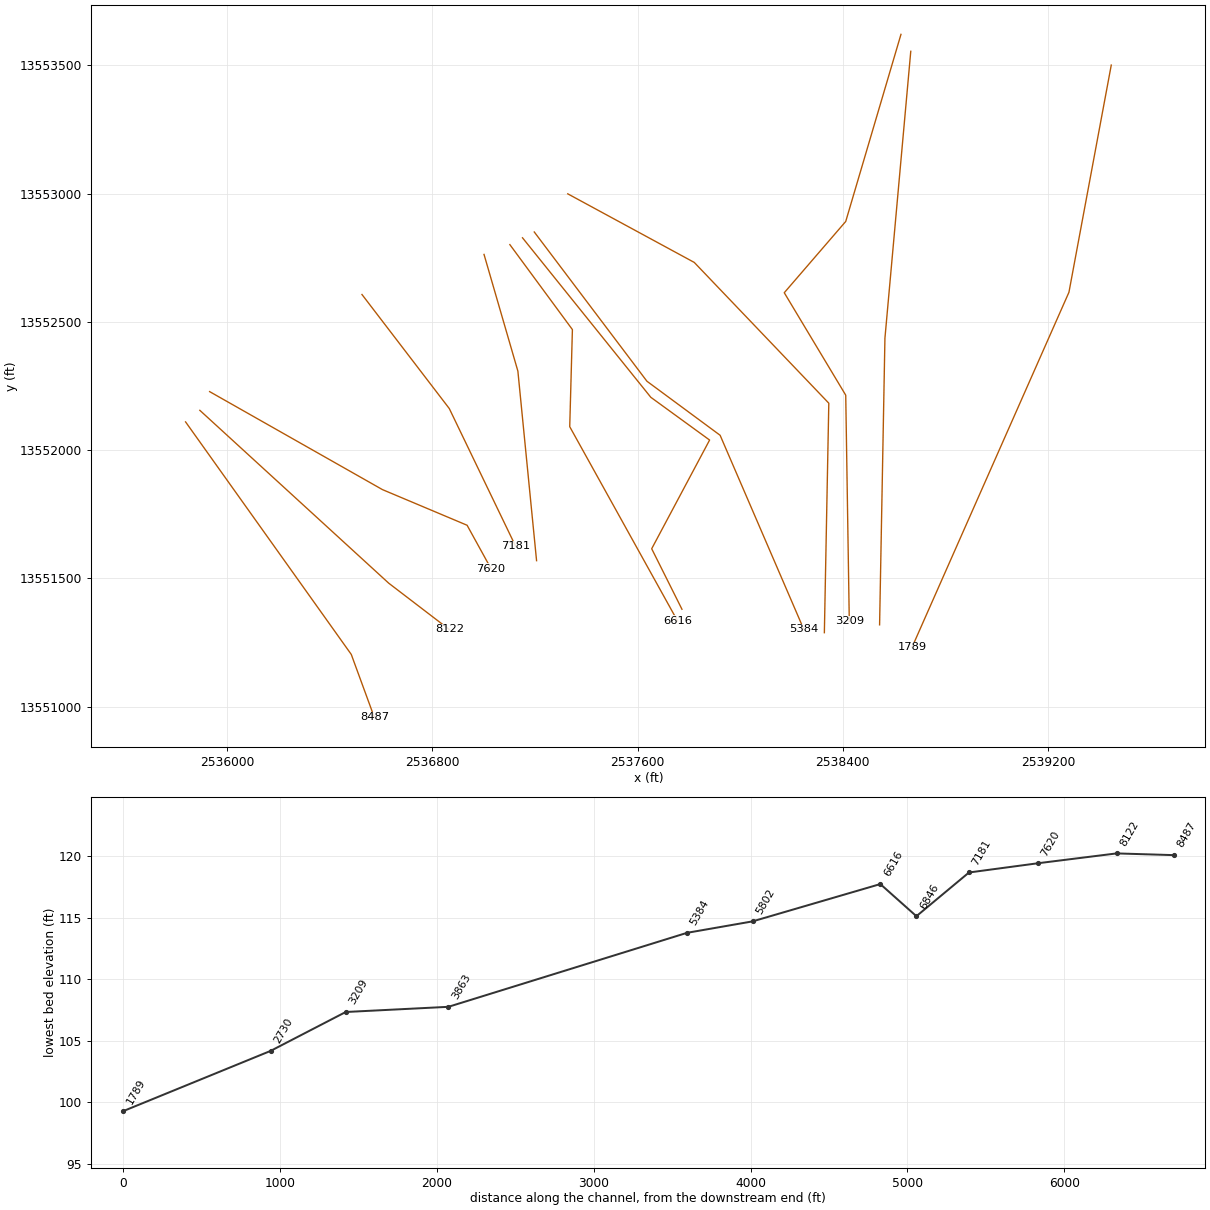
HEC-RAS study CARLISLE CREEK.prj: CARLISLE CREEK Base Level Engineering

--- CARLISLE CREEK.g01 (geometry) --- (continued)

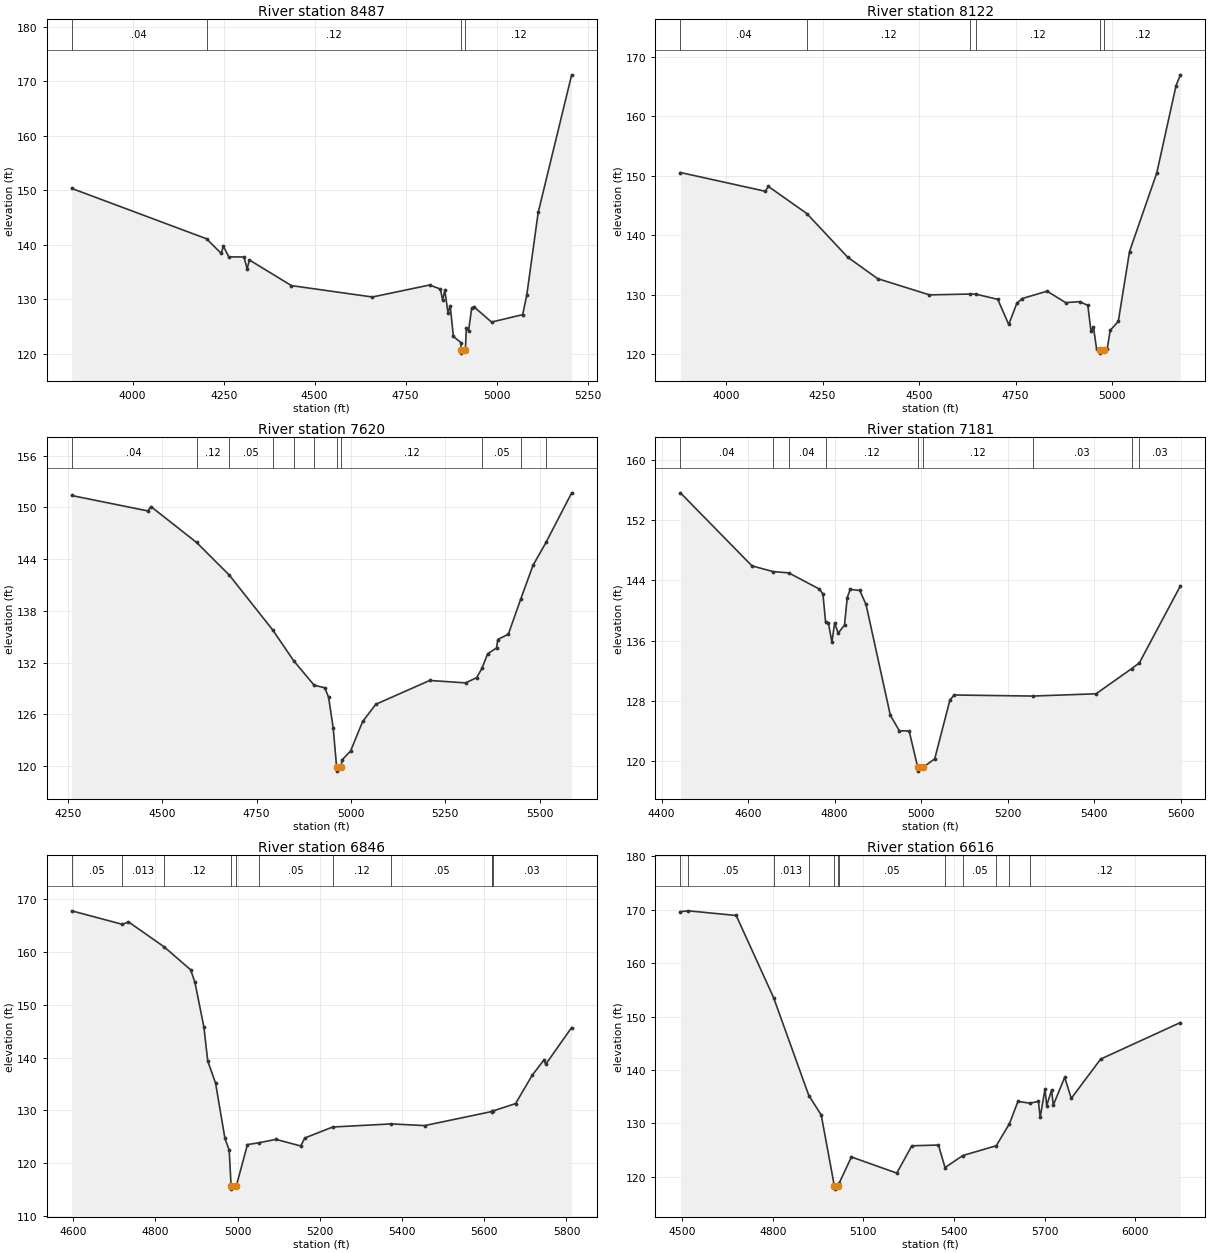
Type RM Length L Ch R = 1,8487,365,365,365
BEGIN DESCRIPTION:
Mapping XS 8880bdf0
END DESCRIPTION:
XS GIS Cut Line= 3
      2535838.38     13552110.12      2536484.22     13551203.86
      2536574.02     13550958.63
#Sta/Elev= 30
  3832.4  150.30  4203.2  141.05  4243.3  138.37  4249.4  139.68  4264.2  137.74
  4305.9  137.71  4314.6  135.54  4320.7  137.17  4436.3  132.46  4658.8  130.37
  4816.1  132.57  4845.6  131.83  4851.8  129.84  4857.9  131.58  4866.5  127.46
  4872.7  128.75  4881.3  123.13  4902.2  122.01  4902.3  120.57  4902.8  120.07
  4914.3  120.57  4916.9  124.61  4923.1  124.18  4931.6  128.31  4937.8  128.58
  4986.2  125.77  5071.8  127.13  5083.1  130.75  5114.4  145.88  5206.4  171.14
#Mann=4,-1,0
  3832.4    0.04       0  4203.2    0.12       0  4902.3    0.05       0
  4914.3    0.12       0
Bank Sta=4902.3,4914.3
Exp/Cntr=0.3,0.1

Type RM Length L Ch R = 1,8122,502,502,502
BEGIN DESCRIPTION:
Mapping XS af096410
END DESCRIPTION:
XS GIS Cut Line= 3
      2535893.93     13552155.27      2536630.05     13551481.64
      2536866.20     13551301.06
#Sta/Elev= 30
  3881.8  150.53  4101.9  147.38  4109.4  148.20  4209.1  143.65  4314.7  136.34
  4392.4  132.72  4526.8  129.99  4632.2  130.13  4646.9  130.11  4703.8  129.24
  4732.2  125.02  4753.1  128.57  4767.3  129.38  4831.5  130.61  4879.6  128.69
  4916.3  128.85  4937.1  128.22  4945.3  123.86  4951.6  124.60  4959.9  120.88
  4968.0  120.71  4968.5  120.21  4980.0  120.71  4987.0  120.88  4995.2  124.04
  5016.0  125.54  5045.1  137.27  5115.8  150.49  5165.6  165.13  5176.9  166.93
#Mann=6,-1,0
  3881.8    0.04       0  4209.1    0.12       0  4632.2    0.05       0
  4646.9    0.12       0  4968.0    0.05       0  4980.0    0.12       0
Bank Sta=4968,4980
Exp/Cntr=0.3,0.1

Type RM Length L Ch R = 1,7620,439,439,439
BEGIN DESCRIPTION:
Mapping XS 73a1cd1e
END DESCRIPTION:
XS GIS Cut Line= 4
      2535932.13     13552228.17      2536605.75     13551846.22
      2536935.61     13551707.33      2537028.57     13551538.63
#Sta/Elev= 30
  4260.1  151.39  4461.9  149.60  4470.3  150.10  4591.1  145.94  4677.9  142.15
  4792.8  135.79  4848.9  132.19  4902.8  129.37  4930.7  129.08  4940.8  128.01
  4953.1  124.43  4962.1  119.91  4962.6  119.41  4974.3  119.91  4976.1  120.69
  4999.1  121.74  5031.2  125.17  5066.2  127.17  5208.9  129.93  5303.8  129.65
  5333.0  130.25  5347.2  131.32  5362.2  133.02  5385.9  133.70  5389.3  134.68
  5417.2  135.30  5450.3  139.40  5482.5  143.28  5517.2  145.96  5585.0  151.70
#Mann=11,-1,0
  4260.1    0.04       0  4591.1    0.12       0  4677.9    0.05       0
  4792.8    0.04       0  4848.9    0.05       0  4902.8    0.12       0
  4962.1    0.05       0  4974.3    0.12       0  5347.2    0.05       0
  5450.3    0.12       0  5517.2    0.03       0
Bank Sta=4962.1,4974.3
Exp/Cntr=0.3,0.1

Type RM Length L Ch R = 1,7181,335,335,335
BEGIN DESCRIPTION:
CARLISLE CREEK 10.0
END DESCRIPTION:
XS GIS Cut Line= 3
      2536525.89     13552606.64      2536866.17     13552162.20
      2537125.02     13551624.96
#Sta/Elev= 30
  4443.4  155.62  4608.8  145.92  4657.7  145.16  4693.8  144.99  4764.7  142.84
  4772.9  142.19  4779.2  138.40  4785.5  138.36  4793.7  135.78  4800.0  138.36
  4808.2  136.98  4822.8  138.06  4829.1  141.70  4835.9  142.80  4858.1  142.65
  4872.6  140.79  4928.8  126.07  4949.6  124.02  4972.3  123.99  4992.1  119.16
  4992.6  118.66  5004.3  119.16  5031.4  120.29  5066.6  128.12  5076.6  128.77
  5257.6  128.63  5404.4  128.93  5486.7  132.27  5504.6  133.04  5599.5  143.27
#Mann=9,-1,0
  4443.4    0.04       0  4657.7    0.05       0  4693.8    0.04       0
  4779.2    0.12       0  4992.1    0.05       0  5004.3    0.12       0
  5257.6    0.03       0  5486.7    0.05       0  5504.6    0.03       0
Bank Sta=4992.1,5004.3
Exp/Cntr=0.3,0.1

Type RM Length L Ch R = 1,6846,230,230,230
BEGIN DESCRIPTION:
Mapping XS dae51c41
END DESCRIPTION:
XS GIS Cut Line= 3
      2537001.57     13552762.92      2537133.53     13552308.03
      2537206.36     13551569.26
#Sta/Elev= 30
  4596.6  167.80  4720.1  165.24  4734.8  165.71  4821.9  160.96  4886.0  156.63
  4896.4  154.25  4918.2  145.80  4927.6  139.33  4946.6  135.18  4969.3  124.74
  4979.7  122.49  4984.4  115.61  4984.9  115.11  4996.7  115.61  5024.1  123.55
  5051.0  123.87  5093.4  124.53  5153.7  123.28  5163.7  124.80  5231.5  126.87
  5373.9  127.46  5455.1  127.14  5618.2  129.80  5619.6  129.85  5621.0  129.90
  5676.2  131.31  5716.4  136.64  5744.6  139.52  5749.7  138.77  5812.6  145.71
#Mann=11,-1,0
  4596.6    0.05       0  4720.1   0.013       0  4821.9    0.12       0
  4984.4    0.05       0  4996.7    0.12       0  5051.0    0.05       0
  5231.5    0.12       0  5373.9    0.05       0  5618.2    0.03       0
  5619.6    0.05       0  5621.0    0.03       0
Bank Sta=4984.4,4996.7
Exp/Cntr=0.3,0.1

Type RM Length L Ch R = 1,6616,814,814,814
BEGIN DESCRIPTION:
Mapping XS 4bebec5d
END DESCRIPTION:
XS GIS Cut Line= 4
      2537102.26     13552801.10      2537346.02     13552469.96
      2537335.60     13552091.49      2537755.73     13551334.57
#Sta/Elev= 30
  4494.2  169.63  4520.1  169.79  4678.9  168.92  4802.6  153.57  4919.5  135.21
  4960.4  131.60  5004.2  118.22  5004.7  117.72  5016.5  118.22  5020.7  118.95
  5060.4  123.74  5210.5  120.72  5260.5  125.83  5348.6  125.97  5370.3  121.75
  5428.9  124.00  5539.9  125.84  5583.7  129.97  5611.7  134.13  5650.9  133.81
  5679.6  134.12  5685.3  131.15  5701.3  136.43  5707.0  133.36  5723.0  136.23
  5728.8  133.43  5766.5  138.65  5788.3  134.70  5885.5  142.05  6149.7  148.89
#Mann=12,-1,0
  4494.2    0.04       0  4520.1    0.05       0  4802.6   0.013       0
  4919.5    0.12       0  5004.2    0.05       0  5016.5    0.12       0
  5020.7    0.05       0  5370.3    0.12       0  5428.9    0.05       0
  5539.9    0.12       0  5583.7     0.1       0  5650.9    0.12       0
Bank Sta=5004.2,5016.5
Exp/Cntr=0.3,0.1

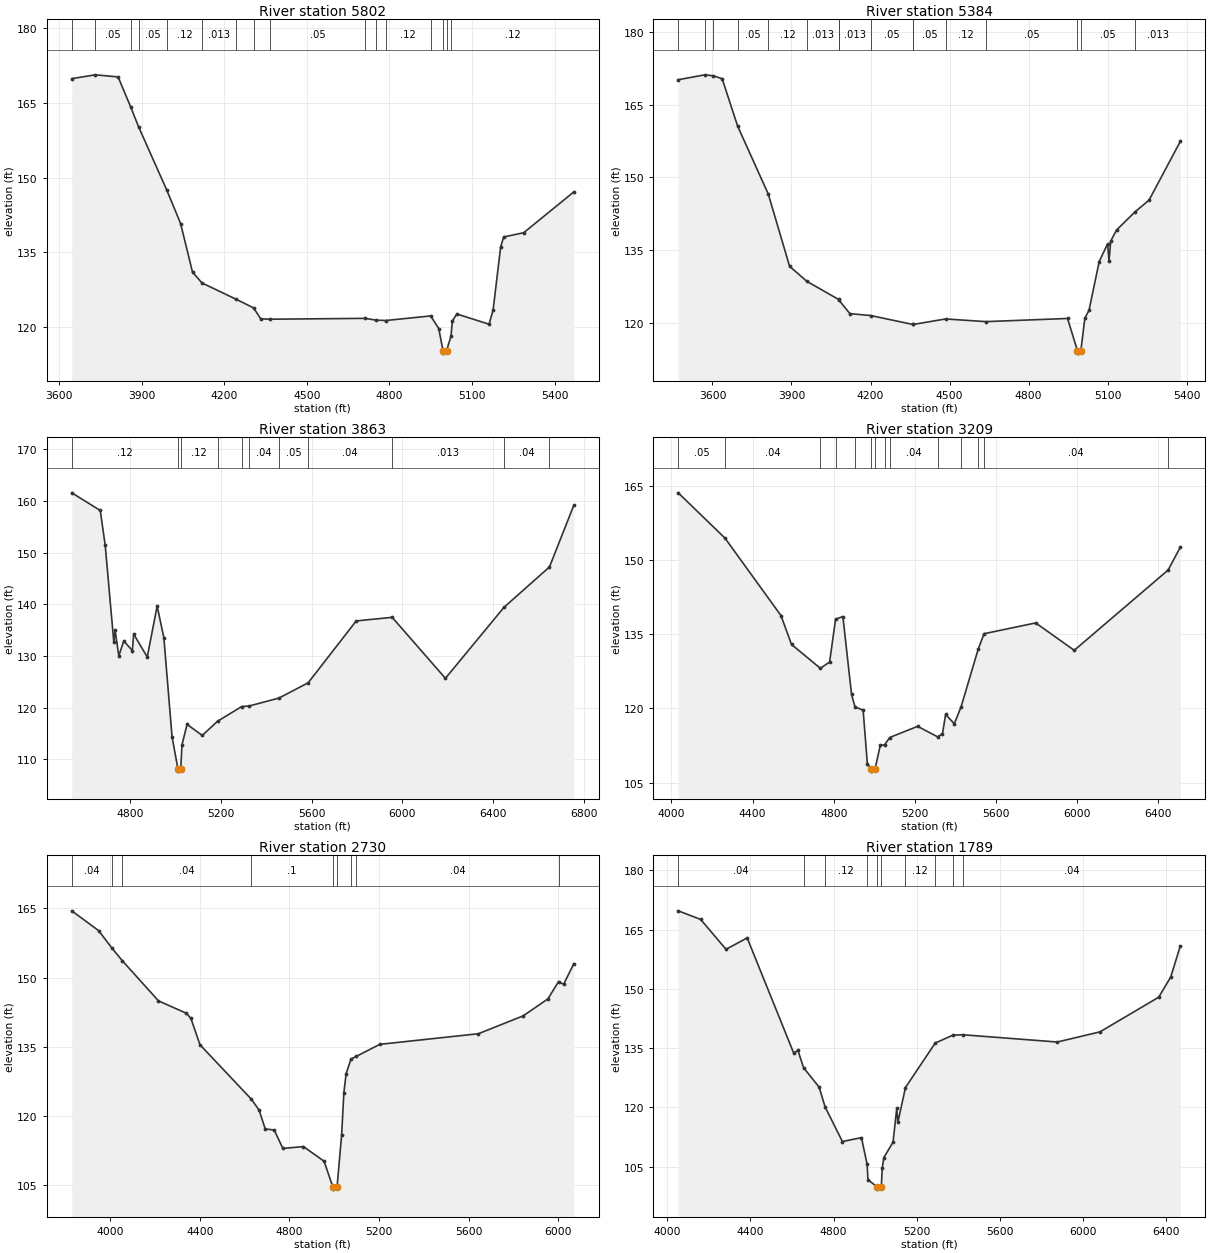
Type RM Length L Ch R = 1,5802,418,418,418
BEGIN DESCRIPTION:
Mapping XS d0414faf
END DESCRIPTION:
XS GIS Cut Line= 5
      2537151.56     13552827.61      2537651.57     13552206.07
      2537880.74     13552039.41      2537655.04     13551615.80
      2537773.00     13551379.89
#Sta/Elev= 30
  3645.3  169.88  3730.9  170.65  3813.7  170.23  3860.1  164.10  3888.0  160.22
  3991.1  147.41  4040.9  140.74  4084.1  130.98  4118.7  128.80  4242.4  125.53
  4306.3  123.78  4332.0  121.58  4366.1  121.51  4711.0  121.68  4751.0  121.33
  4786.7  121.25  4949.7  122.17  4979.0  119.64  4994.6  115.19  4995.1  114.69
  5007.5  115.19  5023.6  118.07  5028.6  121.18  5044.9  122.56  5161.9  120.50
  5176.7  123.37  5204.0  136.01  5215.1  138.05  5287.8  138.90  5470.1  147.11
#Mann=16,-1,0
  3645.3    0.04       0  3730.9    0.05       0  3860.1    0.04       0
  3888.0    0.05       0  3991.1    0.12       0  4118.7   0.013       0
  4242.4    0.05       0  4306.3   0.013       0  4366.1    0.05       0
  4711.0    0.12       0  4751.0    0.05       0  4786.7    0.12       0
  4949.7     0.1       0  4994.6    0.05       0  5007.5     0.1       0
  5023.6    0.12       0
Bank Sta=4994.6,5007.5
Exp/Cntr=0.3,0.1

Type RM Length L Ch R = 1,5384,1521,1521,1521
BEGIN DESCRIPTION:
Mapping XS 9ff717ed
END DESCRIPTION:
XS GIS Cut Line= 4
      2537197.42     13552850.28      2537636.49     13552268.63
      2537921.72     13552058.03      2538247.53     13551302.29
#Sta/Elev= 30
  3470.0  170.17  3570.6  171.18  3602.6  170.99  3636.7  170.38  3695.7  160.57
  3812.1  146.55  3892.8  131.67  3959.0  128.55  4079.1  124.83  4079.9  124.71
  4121.7  121.91  4201.5  121.51  4360.3  119.68  4361.4  119.67  4485.2  120.81
  4638.1  120.26  4948.2  120.91  4985.7  114.26  4986.2  113.76  4998.7  114.26
  5014.0  121.01  5029.6  122.59  5068.4  132.66  5100.2  136.31  5105.6  132.78
  5112.0  136.87  5134.6  139.19  5205.3  142.95  5257.6  145.33  5376.3  157.44
#Mann=16,-1,0
  3470.0    0.04       0  3570.6    0.05       0  3602.6    0.04       0
  3695.7    0.05       0  3812.1    0.12       0  3959.0   0.013       0
  4079.1    0.12       0  4079.9   0.013       0  4201.5    0.05       0
  4360.3   0.013       0  4361.4    0.05       0  4485.2    0.12       0
  4638.1    0.05       0  4985.7    0.05       0  4998.7    0.05       0
  5205.3   0.013       0
Bank Sta=4985.7,4998.7
Exp/Cntr=0.3,0.1

Type RM Length L Ch R = 1,3863,654,654,654
BEGIN DESCRIPTION:
Mapping XS 4f6bf05e
END DESCRIPTION:
XS GIS Cut Line= 4
      2537327.94     13552999.02      2537821.03     13552731.64
      2538345.33     13552183.03      2538328.00     13551288.57
#Sta/Elev= 30
  4542.3  161.58  4667.9  158.17  4689.8  151.42  4727.8  132.67  4733.5  135.00
  4749.7  130.03  4771.6  132.92  4809.6  131.07  4815.3  134.26  4875.2  129.82
  4918.9  139.68  4948.5  133.54  4984.5  114.43  5010.2  108.25  5010.7  107.75
  5023.2  108.25  5028.3  112.83  5050.9  116.80  5117.8  114.65  5185.3  117.40
  5291.8  120.24  5323.9  120.34  5456.7  121.89  5585.0  124.84  5796.8  136.80
  5955.5  137.50  6190.2  125.70  6448.6  139.43  6649.3  147.25  6756.7  159.19
#Mann=11,-1,0
  4542.3    0.12       0  5010.2    0.05       0  5023.2    0.12       0
  5185.3   0.013       0  5291.8    0.12       0  5323.9    0.04       0
  5456.7    0.05       0  5585.0    0.04       0  5955.5   0.013       0
  6448.6    0.04       0  6649.3    0.05       0
Bank Sta=5010.2,5023.2
Exp/Cntr=0.3,0.1

Type RM Length L Ch R = 1,3209,479,479,479
BEGIN DESCRIPTION:
Mapping XS 5ff0cf56
END DESCRIPTION:
XS GIS Cut Line= 5
      2538626.59     13553620.56      2538411.30     13552891.36
      2538171.72     13552613.58      2538411.30     13552214.28
      2538425.19     13551332.30
#Sta/Elev= 30
  4033.7  163.61  4264.1  154.45  4540.0  138.80  4592.1  132.95  4734.3  128.12
  4779.8  129.39  4809.3  138.06  4845.3  138.59  4888.1  122.83  4905.1  120.32
  4945.1  119.65  4966.0  108.82  4984.9  107.83  4985.4  107.33  5004.0  107.83
  5029.6  112.53  5051.0  112.66  5076.1  114.13  5213.7  116.39  5311.9  114.27
  5336.2  114.90  5351.7  118.79  5394.5  116.91  5428.1  120.35  5512.4  132.00
  5541.2  135.12  5795.8  137.30  5985.8  131.76  6448.7  148.00  6508.6  152.62
#Mann=14,-1,0
  4033.7    0.05       0  4264.1    0.04       0  4734.3    0.05       0
  4809.3    0.12       0  4905.1    0.05       0  4984.9    0.05       0
  5004.0    0.05       0  5051.0    0.12       0  5076.1    0.04       0
  5311.9    0.12       0  5428.1    0.04       0  5512.4     0.1       0
  5541.2    0.04       0  6448.7    0.05       0
Bank Sta=4984.9,5004
Exp/Cntr=0.3,0.1

Type RM Length L Ch R = 1,2730,941,941,941
BEGIN DESCRIPTION:
Mapping XS 1fd1a9df
END DESCRIPTION:
XS GIS Cut Line= 3
      2538664.78     13553554.58      2538564.08     13552436.50
      2538543.26     13551319.20
#Sta/Elev= 30
  3828.7  164.47  3948.8  160.17  4008.4  156.36  4055.0  153.62  4215.6  144.96
  4340.3  142.27  4360.4  141.15  4400.6  135.46  4630.1  123.65  4664.5  121.30
  4691.8  117.21  4731.9  116.98  4770.5  112.99  4862.5  113.39  4954.6  110.21
  4993.3  104.67  4993.8  104.17  5012.4  104.67  5032.8  115.95  5042.8  125.10
  5052.8  129.18  5074.5  132.34  5097.3  132.91  5202.9  135.54  5642.9  137.84
  5843.0  141.72  5953.0  145.38  6000.6  149.15  6023.0  148.54  6068.8  153.01
#Mann=9,-1,0
  3828.7    0.04       0  4008.4    0.05       0  4055.0    0.04       0
  4630.1     0.1       0  4993.3    0.05       0  5012.4     0.1       0
  5074.5    0.12       0  5097.3    0.04       0  6000.6    0.05       0
Bank Sta=4993.3,5012.4
Exp/Cntr=0.3,0.1

Type RM Length L Ch R = 1,1789,0,0,0
BEGIN DESCRIPTION:
CARLISLE CREEK 1.0
END DESCRIPTION:
XS GIS Cut Line= 3
      2539446.17     13553500.77      2539281.24     13552615.35
      2538669.64     13551231.65
#Sta/Elev= 30
  4053.6  169.78  4161.2  167.61  4283.3  160.03  4385.0  162.92  4608.8  133.72
  4628.7  134.45  4655.9  130.06  4730.8  125.11  4759.4  120.13  4842.7  111.32
  4934.3  112.32  4961.5  105.58  4965.6  101.68  5010.6   99.77  5011.1   99.27
  5029.8   99.77  5034.1  104.54  5042.1  107.27  5086.2  111.18  5104.0  119.72
  5109.5  116.23  5145.9  125.01  5288.8  136.27  5373.0  138.27  5423.0  138.38
  5875.5  136.54  6080.8  139.11  6363.4  147.90  6420.9  153.00  6467.1  160.86
#Mann=10,-1,0
  4053.6    0.04       0  4655.9    0.05       0  4759.4    0.12       0
  4961.5     0.1       0  5010.6    0.05       0  5029.8     0.1       0
  5145.9    0.12       0  5288.8    0.04       0  5373.0    0.12       0
  5423.0    0.04       0
Bank Sta=5010.6,5029.8
Exp/Cntr=0.3,0.1

Chan Stop Cuts=-1