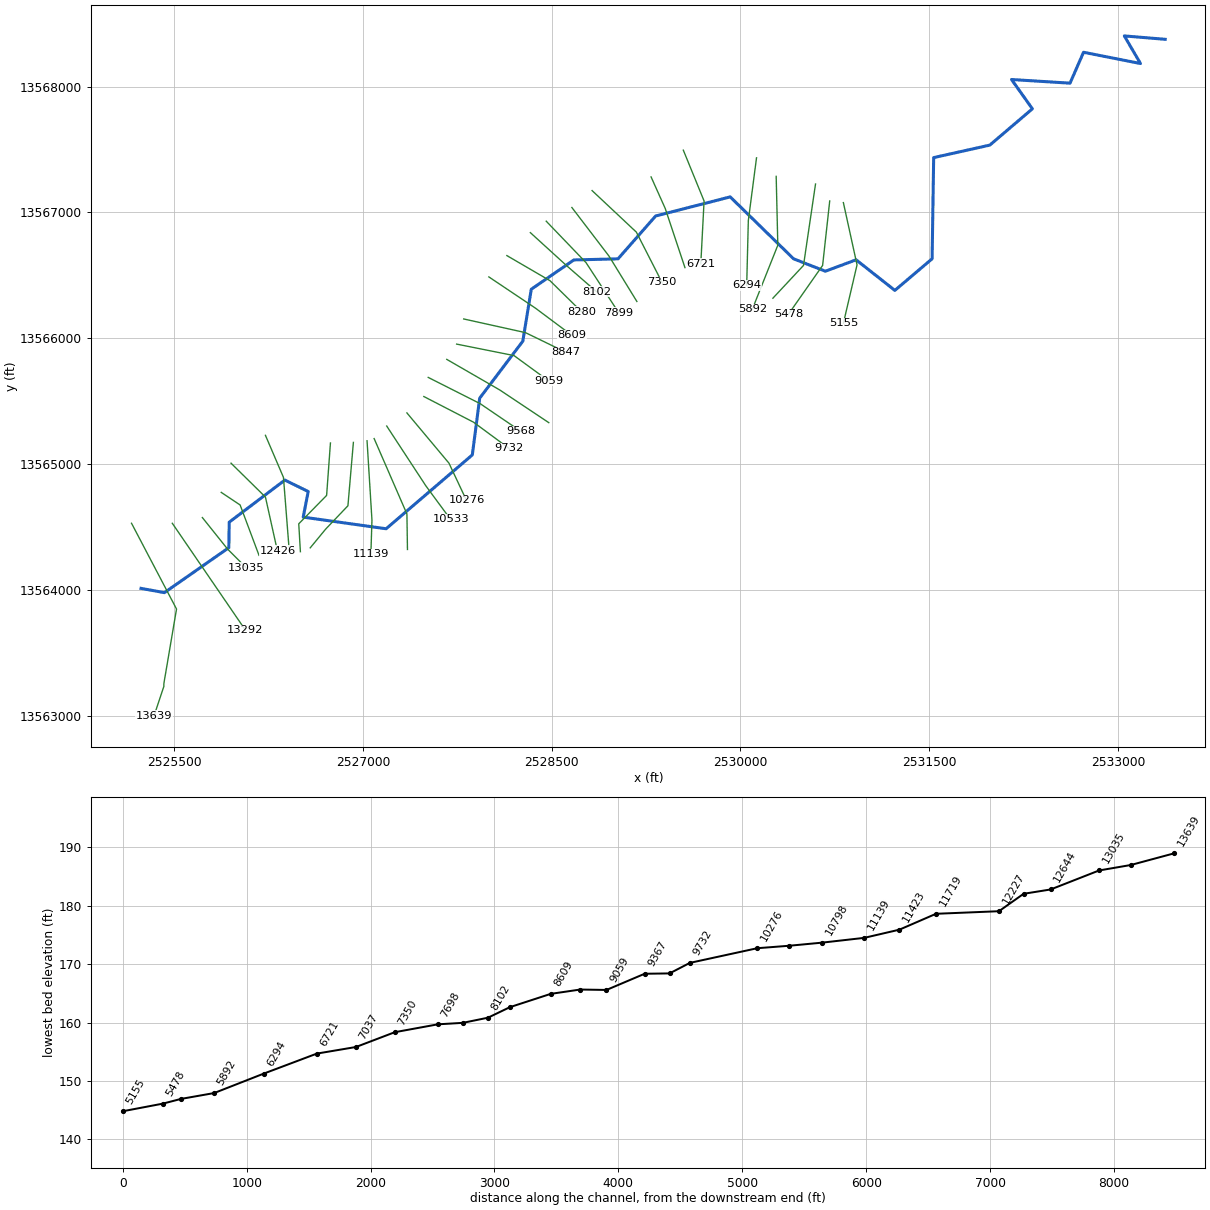
--- CATTAIL CREEK.prj (project) ---

Proj Title=CATTAIL CREEK Base Level Engineering
Current Plan=p01
Default Exp/Contr=0.3,0.1
English Units
Geom File=g01
Flow File=f01
Plan File=p01
BEGIN DESCRIPTION:
CATTAIL CREEK
END DESCRIPTION:

--- CATTAIL CREEK.p01 (plan) ---

Plan Title=Multiple Run
Short Identifier=Multiple
Geom File=g01
Flow File=f01
Subcritical Flow
K Sum by GR= 0
Std Step Tol= 0.01
Critical Tol= 0.01
Num of Std Step Trials= 20
Max Error Tol= 0.3
Flow Tol Ratio= 0.001
Split Flow NTrial= 30
Split Flow Tol= 0.02
Split Flow Ratio= 0.02
Log Output Level= 0
Friction Slope Method= 1
Unsteady Friction Slope Method= 2
Unsteady Bridges Friction Slope Method= 1
Parabolic Critical Depth
Global Vel Dist=  1 , 1 , 1
Global Log Level= 0
CheckData=True
Encroach Param= -1, 0, 0, 0
BEGIN DESCRIPTION:
Multiple Run
END DESCRIPTION:

--- CATTAIL CREEK.f01 (steady flow) ---

Flow Title=Multiple
Number of Profiles=7
Profile Names=10-year,25-year,50-year,1pct_min,100-year,1pct_plu,500-year
River Rch & RM= CATTAIL CREEK,Reach-1,13639
     666    1077    1450     946    1887    3765    3164
River Rch & RM= CATTAIL CREEK,Reach-1,13292
     883    1444    1959    1286    2567    5121    4362
River Rch & RM= CATTAIL CREEK,Reach-1,9732
    1089    1801    2461    1626    3244    6473    5585
River Rch & RM= CATTAIL CREEK,Reach-1,5892
    1283    2140    2939    1952    3894    7769    6771
Boundary for River Rch & Prof#=CATTAIL CREEK,Reach-1,1
Up Type=0
Dn Type=3
Dn Slope=0.005
Boundary for River Rch & Prof#=CATTAIL CREEK,Reach-1,2
Up Type=0
Dn Type=3
Dn Slope=0.005
Boundary for River Rch & Prof#=CATTAIL CREEK,Reach-1,3
Up Type=0
Dn Type=3
Dn Slope=0.005
Boundary for River Rch & Prof#=CATTAIL CREEK,Reach-1,4
Up Type=0
Dn Type=3
Dn Slope=0.005
Boundary for River Rch & Prof#=CATTAIL CREEK,Reach-1,5
Up Type=0
Dn Type=3
Dn Slope=0.005
Boundary for River Rch & Prof#=CATTAIL CREEK,Reach-1,6
Up Type=0
Dn Type=3
Dn Slope=0.005
Boundary for River Rch & Prof#=CATTAIL CREEK,Reach-1,7
Up Type=0
Dn Type=3
Dn Slope=0.005

--- CATTAIL CREEK.g01 (geometry) ---

Geom Title=Existing Conditions

River Reach=CATTAIL CREEK,Reach-1
Reach XY= 30
      2525237.60     13564012.40      2525423.53     13563978.53
      2525935.41     13564335.77      2525938.34     13564538.30
      2526380.89     13564873.04      2526566.05     13564781.69
      2526526.22     13564578.37      2527185.06     13564486.10
      2527869.91     13565072.69      2527928.52     13565523.72
      2528271.17     13565976.58      2528338.37     13566389.11
      2528676.63     13566621.87      2529027.59     13566630.71
      2529326.56     13566971.24      2529919.04     13567122.86
      2530422.70     13566630.83      2530675.10     13566532.33
      2530919.14     13566622.95      2531227.28     13566380.08
      2531523.21     13566631.09      2531535.59     13567435.06
      2531981.67     13567534.30      2532319.95     13567822.72
      2532154.23     13568055.55      2532619.16     13568026.49
      2532726.39     13568271.97      2533178.75     13568182.69
      2533050.51     13568401.94      2533375.00     13568375.00

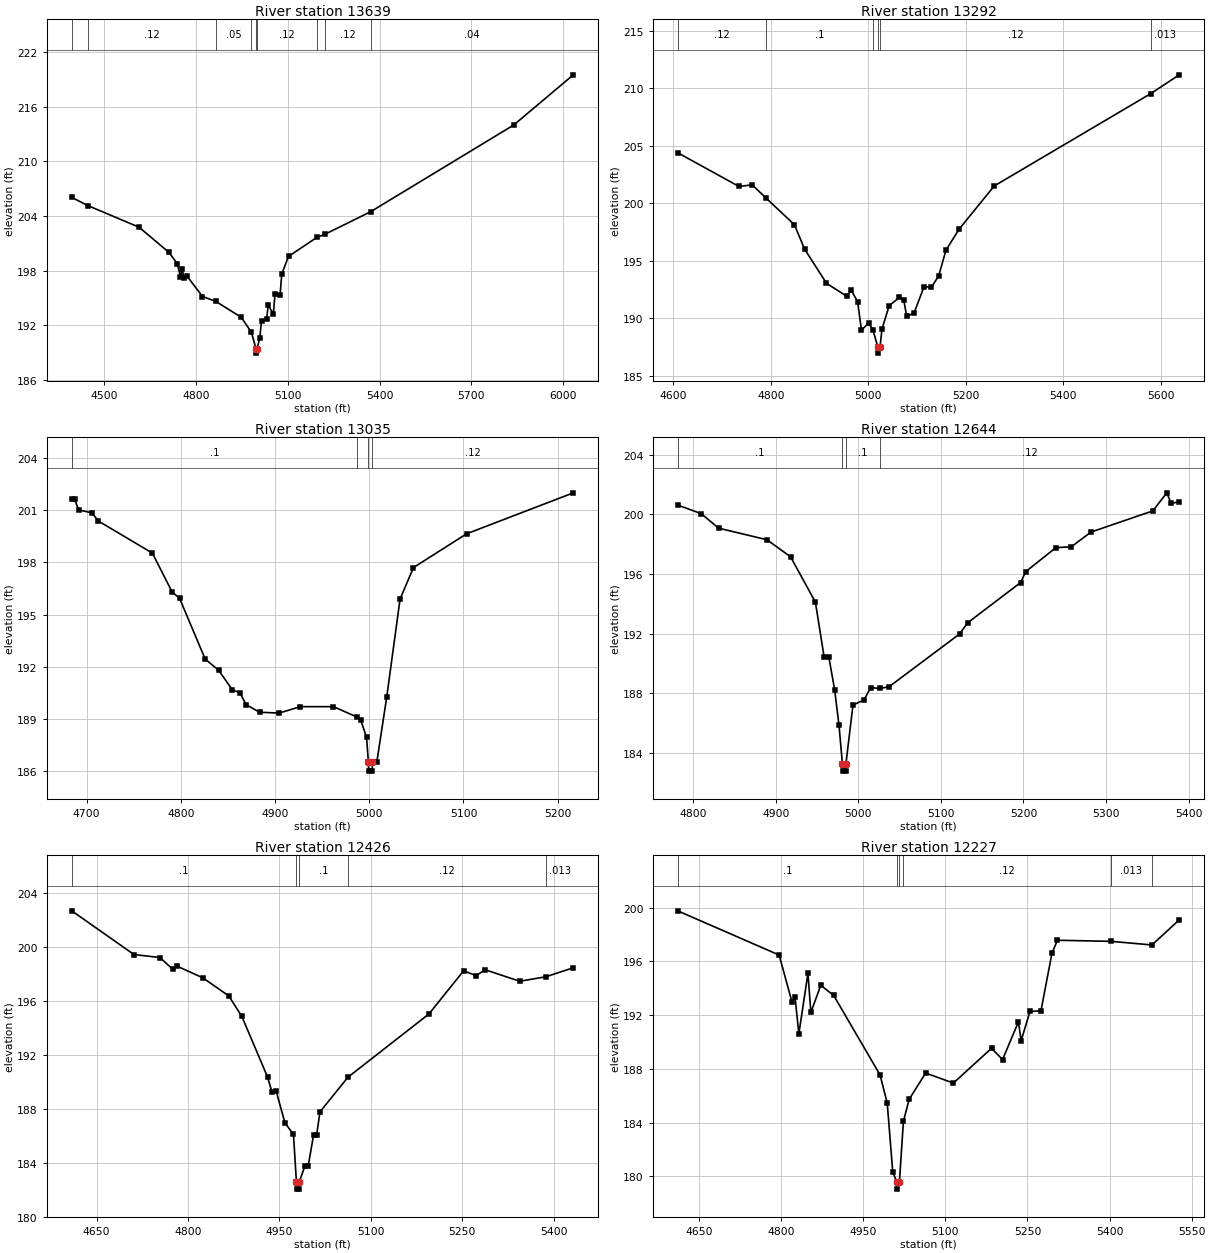
Type RM Length L Ch R = 1,13639,347,347,347
BEGIN DESCRIPTION:
LGII4513
END DESCRIPTION:
XS GIS Cut Line= 5
      2525162.22     13564529.60      2525519.69     13563848.18
      2525419.16     13563256.16      2525419.16     13563233.82
      2525341.21     13562999.99
#Sta/Elev= 30
  4394.3  206.05  4447.7  205.14  4614.1  202.78  4711.2  200.03  4738.9  198.78
  4749.6  197.34  4755.3  198.17  4761.0  197.19  4771.7  197.37  4821.5  195.16
  4864.9  194.63  4948.2  192.87  4981.3  191.24  4996.0  189.44  4996.2  188.94
  5000.0  189.44  5008.7  190.61  5014.4  192.52  5030.8  192.64  5036.4  194.23
  5052.8  193.21  5058.5  195.44  5074.9  195.31  5080.5  197.64  5102.6  199.57
  5194.9  201.65  5222.0  202.01  5370.9  204.48  5838.1  214.00  6033.1  219.52
#Mann=9,-1,0
  4394.3    0.05       0  4447.7    0.12       0  4864.9    0.05       0
  4981.3    0.12       0  4996.0    0.05       0  5000.0    0.12       0
  5194.9    0.05       0  5222.0    0.12       0  5370.9    0.04       0
Bank Sta=4996,5000
Exp/Cntr=0.3,0.1

Type RM Length L Ch R = 1,13292,257,257,257
BEGIN DESCRIPTION:
LGII4512
END DESCRIPTION:
XS GIS Cut Line= 2
      2525486.15     13564529.61      2526067.04     13563680.62
#Sta/Elev= 30
  4609.1  204.41  4734.8  201.47  4761.9  201.61  4791.1  200.43  4848.5  198.14
  4869.5  196.01  4914.3  193.04  4956.2  191.90  4965.1  192.44  4978.2  191.43
  4986.0  188.96  5000.9  189.58  5009.6  188.98  5019.8  187.46  5020.1  186.96
  5024.1  187.46  5028.0  189.04  5042.9  191.09  5063.9  191.81  5072.7  191.60
  5078.8  190.17  5093.7  190.44  5114.6  192.76  5129.6  192.69  5144.5  193.70
  5159.4  195.93  5186.4  197.76  5258.2  201.51  5579.5  209.56  5637.8  211.19
#Mann=6,-1,0
  4609.1    0.12       0  4791.1     0.1       0  5009.6    0.12       0
  5019.8    0.05       0  5024.1    0.12       0  5579.5   0.013       0
Bank Sta=5019.8,5024.1
Exp/Cntr=0.3,0.1

Type RM Length L Ch R = 1,13035,391,391,391
BEGIN DESCRIPTION:
CATTAIL CREEK 25.0
END DESCRIPTION:
XS GIS Cut Line= 3
      2525725.02     13564574.98      2525925.00     13564325.00
      2526075.03     13564174.97
#Sta/Elev= 30
  4684.3  201.61  4687.5  201.61  4691.5  201.01  4705.9  200.84  4712.3  200.38
  4769.9  198.53  4790.7  196.31  4798.7  195.94  4825.9  192.45  4840.3  191.80
  4854.8  190.68  4862.8  190.52  4869.2  189.84  4883.6  189.40  4904.4  189.35
  4926.8  189.72  4962.0  189.72  4987.2  189.12  4990.8  188.98  4997.2  187.95
  4999.1  186.52  4999.4  186.02  5003.1  186.02  5003.4  186.52  5008.0  186.52
  5018.6  190.28  5032.7  195.89  5046.9  197.70  5103.4  199.64  5216.6  201.99
#Mann=4,-1,0
  4684.3     0.1       0  4987.2    0.12       0  4999.1    0.05       0
  5003.4    0.12       0
Bank Sta=4999.1,5003.4
Exp/Cntr=0.3,0.1

Type RM Length L Ch R = 1,12644,218,218,218
BEGIN DESCRIPTION:
CATTAIL CREEK 24.0
END DESCRIPTION:
XS GIS Cut Line= 3
      2525874.98     13564775.02      2526025.00     13564675.00
      2526175.00     13564275.01
#Sta/Elev= 30
  4781.2  200.62  4809.8  200.04  4830.8  199.07  4889.4  198.29  4917.9  197.15
  4948.0  194.11  4958.5  190.45  4964.2  190.45  4971.3  188.23  4976.6  185.84
  4980.7  183.27  4981.0  182.77  4984.7  182.77  4985.0  183.27  4993.5  187.20
  5006.9  187.55  5014.9  188.37  5026.2  188.32  5037.2  188.43  5122.6  191.97
  5132.4  192.72  5196.5  195.42  5202.7  196.15  5239.2  197.76  5257.9  197.82
  5281.9  198.81  5356.7  200.23  5373.6  201.44  5378.9  200.73  5388.7  200.84
#Mann=4,-1,0
  4781.2     0.1       0  4980.7    0.05       0  4985.0     0.1       0
  5026.2    0.12       0
Bank Sta=4980.7,4985
Exp/Cntr=0.3,0.1

Type RM Length L Ch R = 1,12426,199,199,199
BEGIN DESCRIPTION:
Mapping XS 2287806a
END DESCRIPTION:
XS GIS Cut Line= 3
      2525952.70     13565007.16      2526226.13     13564738.06
      2526321.44     13564309.16
#Sta/Elev= 30
  4609.2  202.66  4711.3  199.42  4753.7  199.20  4775.0  198.33  4782.0  198.56
  4824.4  197.69  4866.9  196.35  4888.2  194.84  4930.6  190.33  4937.6  189.24
  4944.7  189.29  4958.9  186.95  4973.0  186.08  4977.9  182.53  4978.1  182.03
  4981.9  182.03  4982.2  182.53  4991.5  183.71  4997.0  183.71  5005.9  186.02
  5011.0  186.04  5016.5  187.76  5062.5  190.33  5195.4  195.02  5252.1  198.21
  5272.6  197.86  5287.6  198.29  5344.3  197.44  5386.9  197.77  5432.2  198.44
#Mann=5,-1,0
  4609.2     0.1       0  4977.9    0.05       0  4982.2     0.1       0
  5062.5    0.12       0  5386.9   0.013       0
Bank Sta=4977.9,4982.2
Exp/Cntr=0.3,0.1

Type RM Length L Ch R = 1,12227,508,508,508
BEGIN DESCRIPTION:
Mapping XS c1bfa70c
END DESCRIPTION:
XS GIS Cut Line= 3
      2526226.15     13565228.47      2526369.36     13564894.31
      2526412.77     13564343.07
#Sta/Elev= 30
  4610.9  199.76  4796.3  196.47  4819.9  192.95  4825.3  193.37  4832.3  190.60
  4848.9  195.11  4854.3  192.20  4872.4  194.22  4896.0  193.46  4980.7  187.55
  4993.8  185.45  5003.9  180.32  5011.7  179.55  5012.0  179.05  5016.0  179.55
  5023.4  184.10  5033.9  185.74  5064.0  187.69  5114.6  186.94  5184.4  189.53
  5204.5  188.69  5233.5  191.49  5238.5  190.10  5254.6  192.27  5274.7  192.32
  5294.8  196.61  5304.8  197.57  5402.1  197.49  5477.5  197.22  5527.4  199.09
#Mann=6,-1,0
  4610.9     0.1       0  5011.7    0.05       0  5016.0     0.1       0
  5023.4    0.12       0  5402.1   0.013       0  5477.5    0.04       0
Bank Sta=5011.7,5016
Exp/Cntr=0.3,0.1

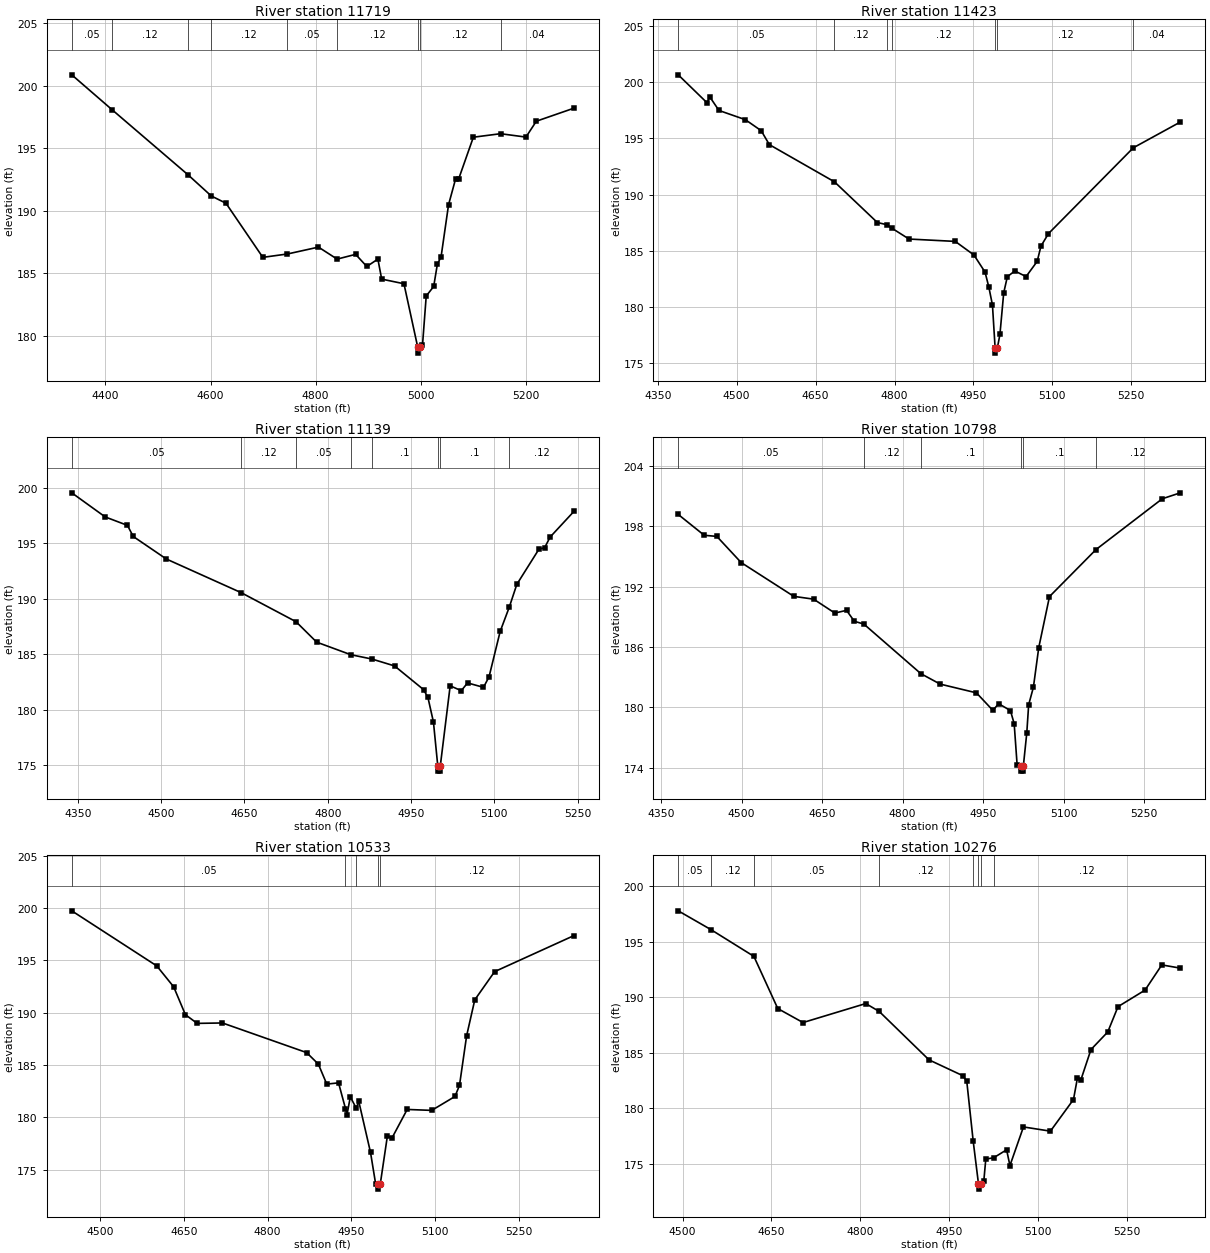
Type RM Length L Ch R = 1,11719,296,296,296
BEGIN DESCRIPTION:
Mapping XS a925cbd5
END DESCRIPTION:
XS GIS Cut Line= 4
      2526742.63     13565167.76      2526712.25     13564751.08
      2526490.89     13564525.39      2526503.91     13564303.98
#Sta/Elev= 30
  4335.9  200.87  4412.3  198.09  4557.0  192.88  4601.5  191.18  4629.4  190.60
  4699.6  186.27  4746.4  186.54  4805.5  187.09  4841.0  186.13  4876.2  186.51
  4897.5  185.54  4918.6  186.13  4925.8  184.53  4968.2  184.16  4994.3  179.11
  4994.6  178.61  4998.8  179.11  5003.5  179.24  5010.6  183.18  5024.8  183.94
  5031.8  185.72  5038.9  186.32  5053.1  190.48  5066.6  192.56  5072.5  192.56
  5100.3  195.88  5152.1  196.16  5200.4  195.89  5220.2  197.16  5291.6  198.20
#Mann=9,-1,0
  4335.9    0.05       0  4412.3    0.12       0  4557.0    0.05       0
  4601.5    0.12       0  4746.4    0.05       0  4841.0    0.12       0
  4994.3    0.05       0  4998.8    0.12       0  5152.1    0.04       0
Bank Sta=4994.3,4998.8
Exp/Cntr=0.3,0.1

Type RM Length L Ch R = 1,11423,284,284,284
BEGIN DESCRIPTION:
Mapping XS 9b71b653
END DESCRIPTION:
XS GIS Cut Line= 4
      2526924.92     13565172.10      2526881.52     13564668.61
      2526703.56     13564481.98      2526582.04     13564334.41
#Sta/Elev= 30
  4388.9  200.65  4443.7  198.16  4448.7  198.70  4466.3  197.48  4516.5  196.66
  4546.6  195.68  4562.1  194.44  4685.9  191.13  4767.4  187.51  4785.1  187.32
  4794.8  187.01  4827.6  186.04  4915.5  185.83  4951.0  184.62  4972.1  183.10
  4979.3  181.77  4986.2  180.17  4991.2  176.39  4991.5  175.89  4995.7  176.39
  5000.4  177.55  5007.6  181.25  5014.5  182.69  5028.7  183.20  5050.1  182.70
  5071.2  184.05  5078.4  185.41  5092.6  186.52  5254.0  194.16  5343.3  196.45
#Mann=7,-1,0
  4388.9    0.05       0  4685.9    0.12       0  4785.1    0.05       0
  4794.8    0.12       0  4991.2    0.05       0  4995.7    0.12       0
  5254.0    0.04       0
Bank Sta=4991.2,4995.7
Exp/Cntr=0.3,0.1

Type RM Length L Ch R = 1,11139,341,341,341
BEGIN DESCRIPTION:
Mapping XS fd86febb
END DESCRIPTION:
XS GIS Cut Line= 3
      2527033.43     13565185.11      2527072.49     13564555.77
      2527063.81     13564282.36
#Sta/Elev= 30
  4339.0  199.54  4399.2  197.37  4439.3  196.61  4449.7  195.61  4509.4  193.58
  4644.2  190.55  4742.8  187.94  4780.0  186.10  4841.4  184.97  4879.5  184.58
  4920.2  183.96  4972.4  181.83  4980.3  181.13  4990.3  178.90  4998.0  174.99
  4998.3  174.49  5002.3  174.49  5002.7  174.99  5020.4  182.17  5040.4  181.73
  5051.7  182.43  5080.4  182.03  5090.4  182.98  5110.4  187.06  5126.9  189.26
  5140.4  191.30  5180.4  194.48  5190.4  194.59  5200.4  195.56  5243.1  197.86
#Mann=8,-1,0
  4339.0    0.05       0  4644.2    0.12       0  4742.8    0.05       0
  4841.4    0.12       0  4879.5     0.1       0  4998.0    0.05       0
  5002.7     0.1       0  5126.9    0.12       0
Bank Sta=4998,5002.7
Exp/Cntr=0.3,0.1

Type RM Length L Ch R = 1,10798,265,265,265
BEGIN DESCRIPTION:
Mapping XS 510ab4a0
END DESCRIPTION:
XS GIS Cut Line= 3
      2527089.85     13565202.47      2527350.27     13564603.51
      2527354.61     13564321.37
#Sta/Elev= 30
  4382.1  199.18  4430.5  197.11  4454.0  197.00  4499.3  194.40  4597.4  191.04
  4634.4  190.76  4673.8  189.38  4695.6  189.65  4710.2  188.56  4727.8  188.29
  4834.0  183.36  4870.0  182.32  4937.6  181.45  4968.2  179.71  4979.0  180.37
  5000.9  179.69  5007.9  178.39  5013.4  174.29  5020.3  174.17  5020.6  173.67
  5024.7  173.67  5025.0  174.17  5031.4  177.47  5034.9  180.27  5043.7  182.00
  5053.7  185.95  5073.7  191.02  5160.3  195.69  5283.8  200.74  5317.4  201.33
#Mann=6,-1,0
  4382.1    0.05       0  4727.8    0.12       0  4834.0     0.1       0
  5020.3    0.05       0  5025.0     0.1       0  5160.3    0.12       0
Bank Sta=5020.3,5025
Exp/Cntr=0.3,0.1

Type RM Length L Ch R = 1,10533,257,257,257
BEGIN DESCRIPTION:
Mapping XS 5808c25c
END DESCRIPTION:
XS GIS Cut Line= 3
      2527189.70     13565302.26      2527502.18     13564824.86
      2527697.51     13564560.08
#Sta/Elev= 30
  4449.2  199.72  4601.5  194.46  4631.8  192.46  4652.8  189.80  4673.9  188.97
  4719.2  189.01  4870.0  186.18  4891.0  185.08  4906.1  183.17  4927.2  183.29
  4939.6  180.84  4942.3  180.24  4948.3  181.95  4959.0  180.86  4963.4  181.53
  4984.5  176.64  4993.6  173.66  4997.2  173.64  4997.6  173.14  5002.0  173.64
  5014.7  178.21  5022.8  178.01  5050.2  180.75  5094.1  180.66  5135.8  181.99
  5143.9  183.05  5156.7  187.79  5171.3  191.22  5206.8  193.91  5348.8  197.35
#Mann=5,-1,0
  4449.2    0.05       0  4939.6     0.1       0  4959.0    0.12       0
  4997.2    0.05       0  5002.0    0.12       0
Bank Sta=4997.2,5002
Exp/Cntr=0.3,0.1

Type RM Length L Ch R = 1,10276,544,544,544
BEGIN DESCRIPTION:
Mapping XS a152f963
END DESCRIPTION:
XS GIS Cut Line= 3
      2527350.28     13565406.45      2527684.47     13565007.16
      2527823.37     13564711.99
#Sta/Elev= 30
  4492.8  197.78  4547.9  196.09  4620.4  193.68  4660.7  188.98  4703.3  187.72
  4809.1  189.43  4831.8  188.72  4915.8  184.36  4973.0  182.93  4979.5  182.43
  4990.4  177.01  4999.2  173.22  4999.6  172.72  5004.0  173.22  5008.2  173.43
  5011.6  175.43  5024.7  175.54  5046.7  176.26  5052.3  174.84  5075.1  178.32
  5120.6  177.94  5159.5  180.79  5166.2  182.74  5171.8  182.53  5189.0  185.29
  5217.3  186.87  5234.6  189.15  5280.2  190.64  5308.5  192.91  5339.7  192.62
#Mann=8,-1,0
  4492.8    0.05       0  4547.9    0.12       0  4620.4    0.05       0
  4831.8    0.12       0  4990.4    0.05       0  4999.2    0.05       0
  5004.0    0.05       0  5024.7    0.12       0
Bank Sta=4999.2,5004
Exp/Cntr=0.3,0.1

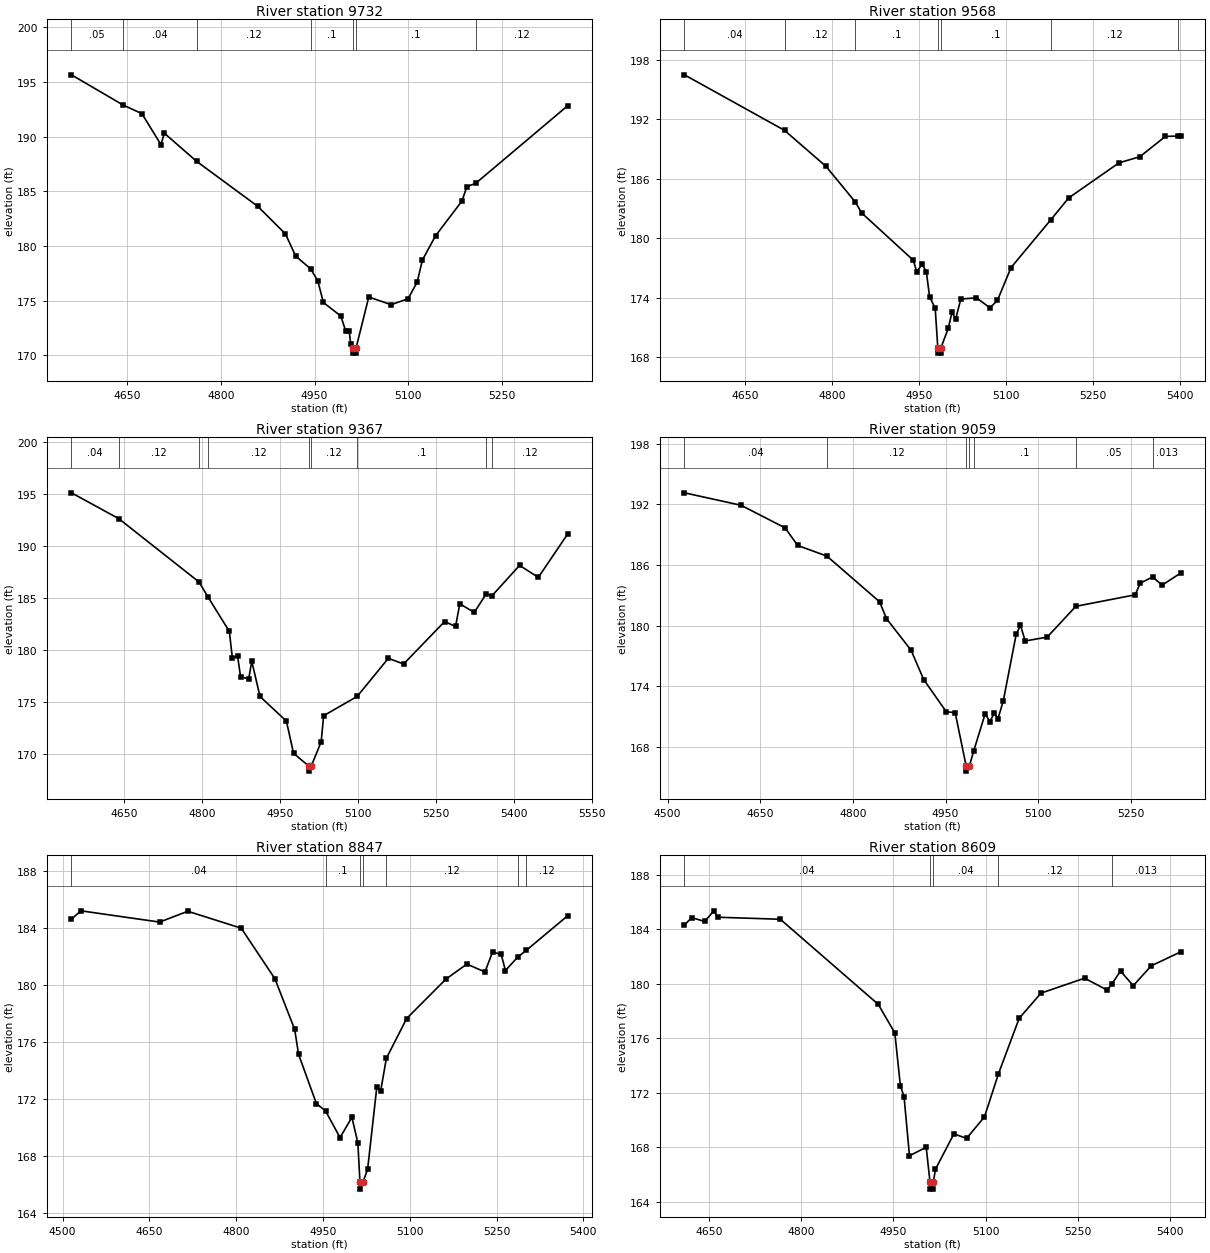
Type RM Length L Ch R = 1,9732,164,164,164
BEGIN DESCRIPTION:
Mapping XS ba546170
END DESCRIPTION:
XS GIS Cut Line= 3
      2527484.85     13565536.65      2527879.78     13565332.68
      2528160.93     13565125.06
#Sta/Elev= 30
  4561.0  195.65  4643.3  192.90  4673.7  192.10  4704.1  189.28  4709.7  190.31
  4761.3  187.74  4859.1  183.63  4903.4  181.11  4919.9  179.07  4943.7  177.92
  4955.1  176.83  4964.2  174.84  4992.0  173.60  5000.0  172.22  5005.5  172.22
  5007.9  171.05  5011.6  170.71  5012.0  170.21  5016.3  170.21  5016.6  170.71
  5036.8  175.34  5072.6  174.64  5099.7  175.18  5114.3  176.71  5122.7  178.73
  5143.6  180.93  5186.0  184.12  5193.7  185.43  5207.9  185.73  5355.0  192.82
#Mann=7,-1,0
  4561.0    0.05       0  4643.3    0.04       0  4761.3    0.12       0
  4943.7     0.1       0  5011.6    0.05       0  5016.6     0.1       0
  5207.9    0.12       0
Bank Sta=5011.6,5016.6
Exp/Cntr=0.3,0.1

Type RM Length L Ch R = 1,9568,201,201,201
BEGIN DESCRIPTION:
Mapping XS d95a98a7
END DESCRIPTION:
XS GIS Cut Line= 3
      2527519.54     13565688.58      2527931.86     13565480.25
      2528256.54     13565259.46
#Sta/Elev= 30
  4545.9  196.48  4718.2  190.88  4789.8  187.24  4840.2  183.65  4851.1  182.55
  4940.2  177.77  4945.8  176.63  4955.4  177.37  4962.5  176.62  4968.1  174.10
  4977.8  172.93  4982.3  168.91  4982.7  168.41  4987.0  168.41  4987.4  168.91
  5000.2  170.90  5006.8  172.54  5013.0  171.83  5021.9  173.87  5048.9  173.98
  5072.1  172.98  5084.9  173.72  5108.4  177.04  5177.1  181.87  5207.6  184.06
  5294.3  187.60  5330.3  188.22  5374.4  190.27  5396.3  190.30  5400.5  190.35
#Mann=7,-1,0
  4545.9    0.04       0  4718.2    0.12       0  4840.2     0.1       0
  4982.3    0.05       0  4987.4     0.1       0  5177.1    0.12       0
  5396.3   0.013       0
Bank Sta=4982.3,4987.4
Exp/Cntr=0.3,0.1

Type RM Length L Ch R = 1,9367,308,308,308
BEGIN DESCRIPTION:
Mapping XS e5306626
END DESCRIPTION:
XS GIS Cut Line= 3
      2527667.08     13565831.82      2528088.11     13565588.75
      2528477.47     13565329.19
#Sta/Elev= 30
  4549.5  195.11  4640.4  192.63  4794.7  186.54  4812.6  185.05  4853.1  181.78
  4858.9  179.23  4868.9  179.44  4874.7  177.41  4890.4  177.23  4896.2  178.93
  4912.0  175.53  4962.8  173.16  4976.6  170.06  5005.6  168.85  5006.0  168.35
  5010.7  168.85  5029.7  171.17  5034.4  173.68  5098.9  175.53  5158.9  179.20
  5188.2  178.65  5267.0  182.73  5288.1  182.26  5296.3  184.44  5324.1  183.61
  5346.9  185.38  5358.0  185.20  5411.2  188.13  5447.3  186.98  5503.6  191.14
#Mann=9,-1,0
  4549.5    0.04       0  4640.4    0.12       0  4794.7     0.1       0
  4812.6    0.12       0  5005.6    0.05       0  5010.7    0.12       0
  5098.9     0.1       0  5346.9   0.013       0  5358.0    0.12       0
Bank Sta=5005.6,5010.7
Exp/Cntr=0.3,0.1

Type RM Length L Ch R = 1,9059,212,212,212
BEGIN DESCRIPTION:
Mapping XS a8580f3f
END DESCRIPTION:
XS GIS Cut Line= 3
      2527745.25     13565953.33      2528200.96     13565862.19
      2528474.39     13565662.54
#Sta/Elev= 30
  4527.2  193.14  4618.7  191.91  4690.1  189.67  4710.5  187.93  4757.9  186.87
  4843.1  182.35  4854.3  180.68  4894.1  177.55  4914.5  174.65  4951.1  171.46
  4965.5  171.37  4983.3  166.08  4983.7  165.58  4988.5  166.08  4995.6  167.60
  5014.1  171.27  5021.7  170.47  5028.7  171.32  5034.9  170.79  5043.4  172.54
  5064.3  179.13  5071.2  180.02  5078.9  178.47  5114.5  178.85  5160.8  181.90
  5257.0  183.04  5265.1  184.19  5285.1  184.81  5300.6  184.00  5330.5  185.19
#Mann=7,-1,0
  4527.2    0.04       0  4757.9    0.12       0  4983.3    0.05       0
  4988.5    0.12       0  4995.6     0.1       0  5160.8    0.05       0
  5285.1   0.013       0
Bank Sta=4983.3,4988.5
Exp/Cntr=0.3,0.1

Type RM Length L Ch R = 1,8847,238,238,238
BEGIN DESCRIPTION:
Mapping XS 928a0bc8
END DESCRIPTION:
XS GIS Cut Line= 3
      2527801.62     13566153.00      2528292.11     13566044.48
      2528611.65     13565889.03
#Sta/Elev= 30
  4515.2  184.61  4531.6  185.19  4667.6  184.40  4716.3  185.16  4808.7  183.97
  4866.9  180.42  4901.1  176.86  4907.8  175.11  4938.6  171.66  4954.6  171.13
  4979.5  169.27  5000.0  170.69  5010.3  168.90  5013.9  166.15  5014.3  165.65
  5019.1  166.15  5027.1  167.03  5043.0  172.79  5049.6  172.51  5059.6  174.84
  5094.7  177.63  5162.4  180.39  5198.7  181.45  5230.0  180.90  5243.2  182.30
  5258.1  182.13  5265.4  181.00  5286.9  181.95  5301.3  182.41  5372.9  184.84
#Mann=7,-1,0
  4515.2    0.04       0  4954.6     0.1       0  5013.9    0.05       0
  5019.1     0.1       0  5059.6    0.12       0  5286.9   0.013       0
  5301.3    0.12       0
Bank Sta=5013.9,5019.1
Exp/Cntr=0.3,0.1

Type RM Length L Ch R = 1,8609,329,329,329
BEGIN DESCRIPTION:
Mapping XS ec379103
END DESCRIPTION:
XS GIS Cut Line= 3
      2528001.27     13566487.22      2528370.23     13566239.80
      2528660.48     13566023.19
#Sta/Elev= 30
  4610.3  184.32  4622.0  184.86  4643.1  184.58  4658.1  185.36  4664.1  184.89
  4766.1  184.74  4925.2  178.49  4952.2  176.39  4961.2  172.52  4967.2  171.70
  4976.0  167.36  5003.2  167.99  5009.4  165.41  5009.8  164.91  5014.4  164.91
  5014.8  165.41  5018.2  166.37  5048.2  168.97  5068.8  168.64  5097.9  170.22
  5120.6  173.38  5154.3  177.46  5189.7  179.31  5260.6  180.41  5297.6  179.53
  5305.3  180.01  5319.0  180.93  5339.8  179.86  5369.0  181.32  5416.7  182.34
#Mann=5,-1,0
  4610.3    0.04       0  5009.4    0.04       0  5014.8    0.04       0
  5120.6    0.12       0  5305.3   0.013       0
Bank Sta=5009.4,5014.8
Exp/Cntr=0.3,0.1

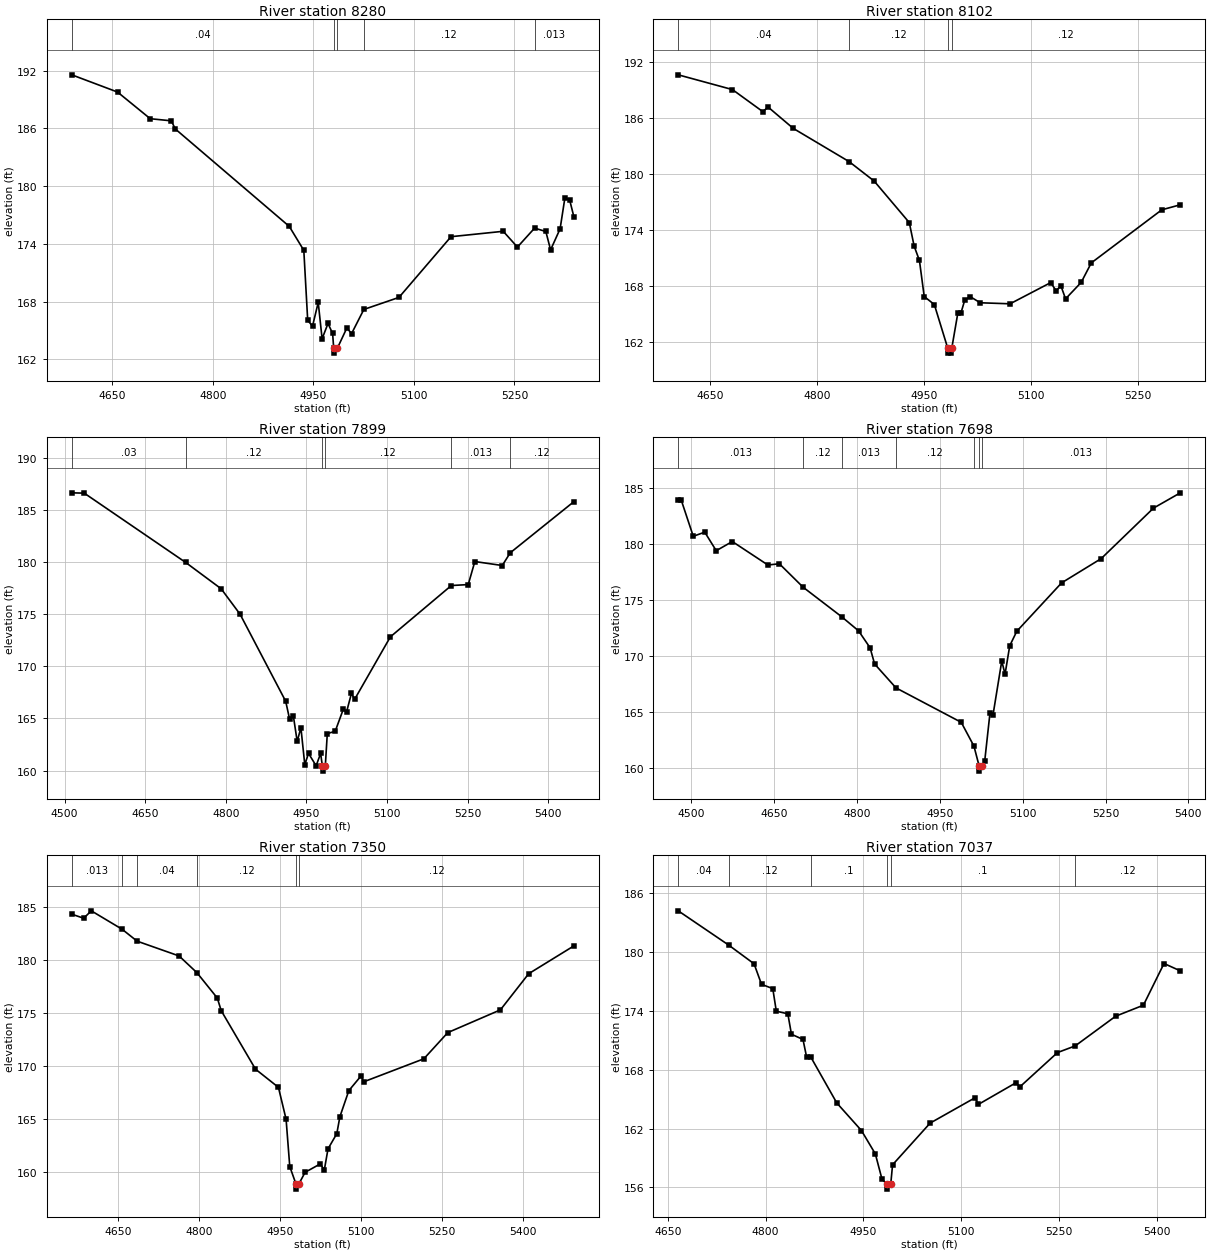
Type RM Length L Ch R = 1,8280,178,178,178
BEGIN DESCRIPTION:
Mapping XS cb54202f
END DESCRIPTION:
XS GIS Cut Line= 3
      2528144.52     13566656.47      2528487.42     13566456.81
      2528738.84     13566209.72
#Sta/Elev= 30
  4589.4  191.56  4657.7  189.77  4706.5  187.00  4738.0  186.78  4743.8  185.94
  4914.0  175.81  4935.7  173.32  4941.5  166.05  4948.7  165.44  4957.2  167.91
  4963.0  164.13  4971.8  165.72  4978.7  164.68  4980.3  163.14  4980.7  162.64
  4985.7  163.14  4999.9  165.25  5007.0  164.67  5025.3  167.18  5077.7  168.43
  5155.4  174.74  5233.3  175.30  5254.5  173.66  5280.1  175.63  5296.9  175.28
  5304.0  173.37  5318.2  175.56  5325.2  178.71  5332.3  178.60  5338.7  176.82
#Mann=5,-1,0
  4589.4    0.04       0  4980.3    0.04       0  4985.7    0.04       0
  5025.3    0.12       0  5280.1   0.013       0
Bank Sta=4980.3,4985.7
Exp/Cntr=0.3,0.1

Type RM Length L Ch R = 1,8102,203,203,203
BEGIN DESCRIPTION:
Mapping XS 8af5078c
END DESCRIPTION:
XS GIS Cut Line= 3
      2528331.15     13566838.77      2528621.97     13566574.00
      2528856.33     13566370.01
#Sta/Elev= 30
  4605.5  190.62  4681.5  189.04  4724.1  186.68  4731.5  187.17  4766.7  184.89
  4845.1  181.33  4880.2  179.25  4929.5  174.80  4936.3  172.28  4943.7  170.75
  4950.4  166.89  4964.6  166.03  4983.5  161.33  4983.9  160.83  4988.5  160.83
  4989.0  161.33  4997.5  165.10  5001.8  165.10  5007.2  166.49  5014.8  166.88
  5029.0  166.22  5070.8  166.11  5127.8  168.38  5135.4  167.50  5142.0  168.05
  5148.6  166.64  5170.5  168.40  5184.7  170.49  5283.5  176.17  5309.5  176.71
#Mann=4,-1,0
  4605.5    0.04       0  4845.1    0.12       0  4983.5    0.05       0
  4989.0    0.12       0
Bank Sta=4983.5,4989
Exp/Cntr=0.3,0.1

Type RM Length L Ch R = 1,7899,201,201,201
BEGIN DESCRIPTION:
Mapping XS fc3b0a49
END DESCRIPTION:
XS GIS Cut Line= 3
      2528457.02     13566929.91      2528773.88     13566600.04
      2529034.28     13566200.75
#Sta/Elev= 30
  4513.4  186.64  4536.6  186.61  4725.4  179.96  4791.3  177.44  4826.5  175.00
  4911.4  166.65  4918.6  164.95  4925.6  165.26  4932.8  162.80  4939.7  164.12
  4946.9  160.57  4953.9  161.65  4968.0  160.46  4976.4  161.65  4979.6  160.45
  4980.0  159.95  4985.1  160.45  4988.8  163.55  5003.5  163.77  5018.6  165.89
  5024.6  165.62  5033.7  167.40  5039.7  166.84  5106.2  172.83  5219.6  177.75
  5251.0  177.84  5263.3  180.05  5314.3  179.67  5329.2  180.89  5447.5  185.79
#Mann=6,-1,0
  4513.4    0.03       0  4725.4    0.12       0  4979.6    0.05       0
  4985.1    0.12       0  5219.6   0.013       0  5329.2    0.12       0
Bank Sta=4979.6,4985.1
Exp/Cntr=0.3,0.1

Type RM Length L Ch R = 1,7698,348,348,348
BEGIN DESCRIPTION:
Mapping XS 49e6ed67
END DESCRIPTION:
XS GIS Cut Line= 3
      2528661.05     13567038.39      2528956.17     13566652.12
      2529177.51     13566291.90
#Sta/Elev= 30
  4476.5  183.98  4481.8  183.98  4503.7  180.72  4524.5  181.09  4545.3  179.43
  4574.4  180.25  4638.8  178.15  4659.6  178.26  4702.6  176.16  4772.3  173.52
  4802.9  172.26  4823.8  170.74  4832.0  169.29  4870.7  167.15  4988.8  164.07
  5011.8  161.94  5021.0  160.20  5021.4  159.70  5026.6  160.20  5031.4  160.64
  5040.9  164.93  5046.3  164.72  5062.2  169.56  5068.1  168.37  5076.6  170.92
  5089.4  172.22  5170.5  176.55  5242.1  178.72  5336.8  183.24  5385.4  184.61
#Mann=7,-1,0
  4476.5   0.013       0  4702.6    0.12       0  4772.3   0.013       0
  4870.7    0.12       0  5011.8   0.013       0  5021.0    0.05       0
  5026.6   0.013       0
Bank Sta=5021,5026.6
Exp/Cntr=0.3,0.1

Type RM Length L Ch R = 1,7350,313,313,313
BEGIN DESCRIPTION:
Mapping XS 9f777da2
END DESCRIPTION:
XS GIS Cut Line= 3
      2528821.62     13567172.96      2529173.18     13566843.09
      2529377.19     13566443.77
#Sta/Elev= 30
  4563.4  184.36  4585.5  183.98  4599.6  184.68  4656.6  182.94  4684.5  181.81
  4762.3  180.41  4795.3  178.83  4833.1  176.43  4840.4  175.23  4903.9  169.70
  4946.4  167.98  4960.6  164.96  4967.4  160.49  4978.8  158.85  4979.3  158.35
  4984.4  158.85  4995.8  159.94  5024.1  160.74  5031.4  160.15  5038.3  162.16
  5054.6  163.60  5060.3  165.20  5076.9  167.67  5099.2  169.04  5104.8  168.51
  5215.9  170.68  5260.3  173.16  5357.8  175.31  5410.2  178.73  5493.9  181.36
#Mann=6,-1,0
  4563.4   0.013       0  4656.6    0.12       0  4684.5    0.04       0
  4795.3    0.12       0  4978.8    0.05       0  4984.4    0.12       0
Bank Sta=4978.8,4984.4
Exp/Cntr=0.3,0.1

Type RM Length L Ch R = 1,7037,316,316,316
BEGIN DESCRIPTION:
Mapping XS 5588ef44
END DESCRIPTION:
XS GIS Cut Line= 3
      2529290.35     13567281.50      2529403.22     13567029.73
      2529559.46     13566560.99
#Sta/Elev= 30
  4666.1  184.19  4743.2  180.71  4782.4  178.79  4793.8  176.70  4811.1  176.26
  4816.5  173.96  4834.2  173.69  4839.7  171.61  4857.4  171.08  4862.9  169.31
  4869.0  169.33  4909.3  164.60  4947.1  161.79  4968.4  159.41  4978.6  156.83
  4986.3  156.32  4986.8  155.82  4992.0  156.32  4994.8  158.30  5052.4  162.55
  5121.2  165.13  5126.5  164.46  5184.5  166.68  5189.8  166.23  5247.7  169.74
  5274.9  170.42  5337.0  173.45  5379.5  174.57  5411.1  178.82  5436.1  178.07
#Mann=6,-1,0
  4666.1    0.04       0  4743.2    0.12       0  4869.0     0.1       0
  4986.3    0.05       0  4992.0     0.1       0  5274.9    0.12       0
Bank Sta=4986.3,4992
Exp/Cntr=0.3,0.1

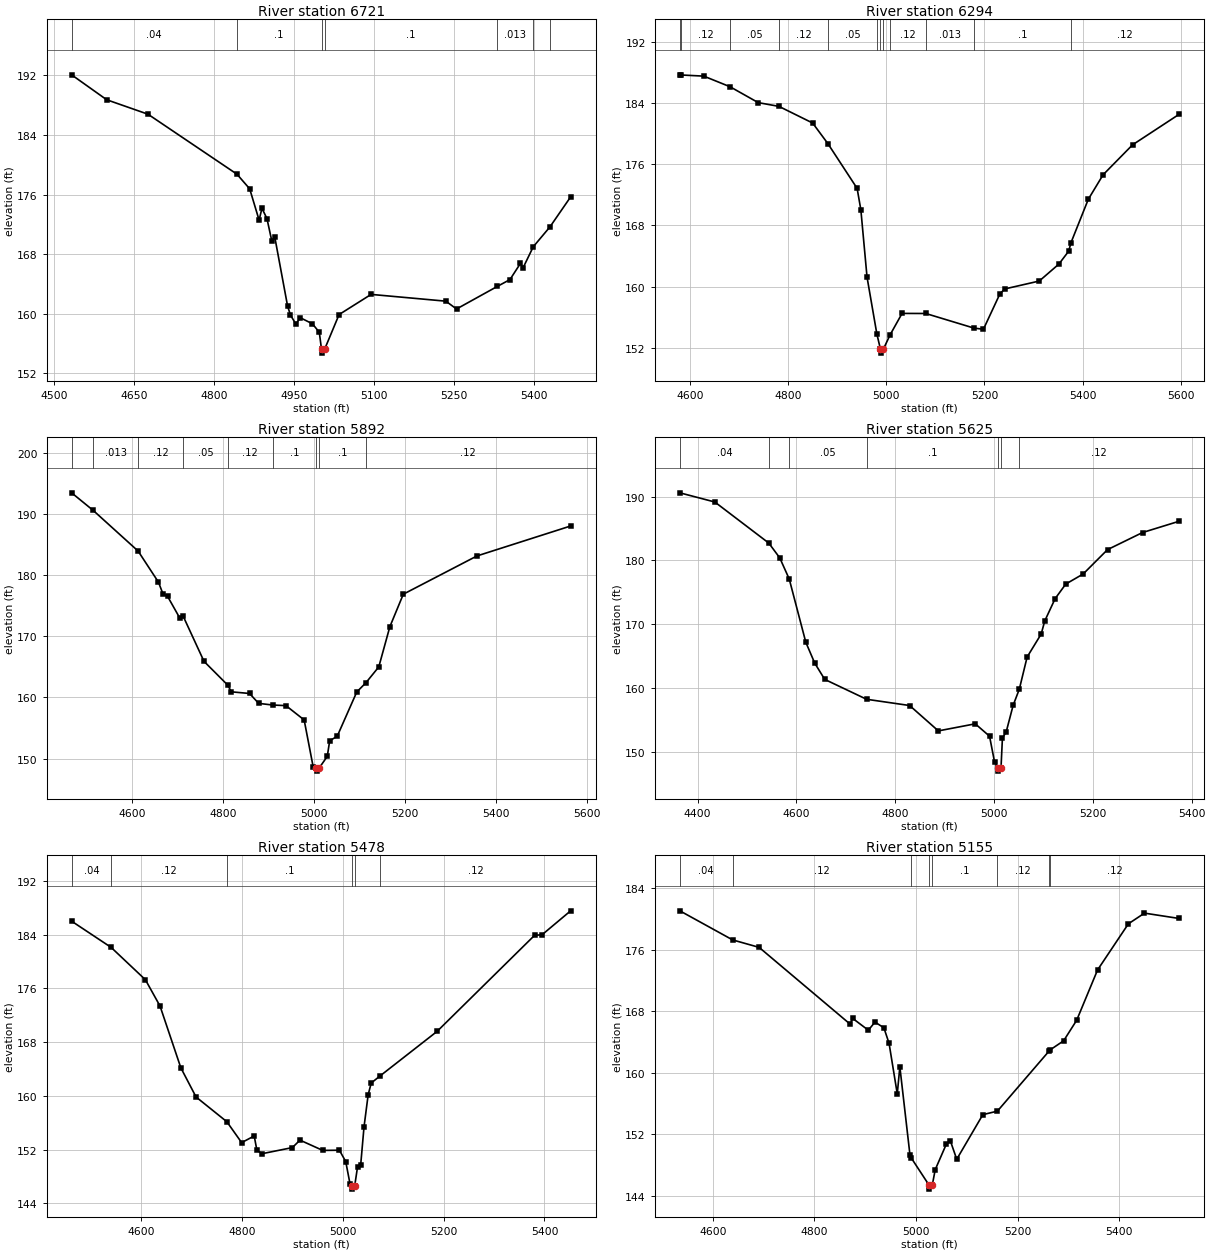
Type RM Length L Ch R = 1,6721,427,427,427
BEGIN DESCRIPTION:
Mapping XS 7915a159
END DESCRIPTION:
XS GIS Cut Line= 3
      2529546.44     13567494.14      2529711.38     13567090.49
      2529685.33     13566591.32
#Sta/Elev= 30
  4532.4  192.08  4598.2  188.73  4675.6  186.79  4842.5  178.73  4866.4  176.76
  4884.0  172.56  4889.4  174.15  4898.8  172.75  4908.0  169.70  4913.4  170.29
  4937.5  160.99  4942.9  159.80  4952.8  158.61  4961.5  159.44  4984.0  158.63
  4996.9  157.50  5001.1  155.19  5001.6  154.69  5006.8  155.19  5034.0  159.87
  5094.1  162.58  5234.3  161.67  5254.3  160.62  5330.7  163.65  5354.5  164.57
  5374.1  166.74  5379.1  166.15  5398.2  168.98  5429.5  171.65  5468.3  175.68
#Mann=7,-1,0
  4532.4    0.04       0  4842.5     0.1       0  5001.1    0.05       0
  5006.8     0.1       0  5330.7   0.013       0  5398.2     0.1       0
  5429.5   0.013       0
Bank Sta=5001.1,5006.8
Exp/Cntr=0.3,0.1

Type RM Length L Ch R = 1,6294,402,402,402
BEGIN DESCRIPTION:
Mapping XS 5fe9d61b
END DESCRIPTION:
XS GIS Cut Line= 3
      2530128.05     13567433.41      2530062.94     13566934.24
      2530049.99     13566420.50
#Sta/Elev= 30
  4579.1  187.72  4581.6  187.70  4627.9  187.55  4681.4  186.16  4738.9  184.08
  4781.1  183.59  4849.8  181.41  4880.9  178.71  4940.5  172.85  4948.1  170.05
  4960.7  161.23  4980.7  153.80  4988.1  151.78  4988.5  151.28  4993.9  151.78
  5007.5  153.65  5032.1  156.48  5080.4  156.47  5179.1  154.55  5198.0  154.41
  5231.8  159.07  5241.8  159.69  5311.8  160.72  5351.8  162.94  5371.8  164.63
  5376.4  165.73  5411.8  171.43  5441.9  174.63  5501.9  178.55  5596.4  182.53
#Mann=12,-1,0
  4579.1    0.05       0  4581.6    0.12       0  4681.4    0.05       0
  4781.1    0.12       0  4880.9    0.05       0  4980.7   0.013       0
  4988.1    0.03       0  4993.9   0.013       0  5007.5    0.12       0
  5080.4   0.013       0  5179.1     0.1       0  5376.4    0.12       0
Bank Sta=4988.1,4993.9
Exp/Cntr=0.3,0.1

Type RM Length L Ch R = 1,5892,267,267,267
BEGIN DESCRIPTION:
Mapping XS 050d3a4e
END DESCRIPTION:
XS GIS Cut Line= 3
      2530284.29     13567285.85      2530297.31     13566738.93
      2530093.97     13566228.41
#Sta/Elev= 30
  4467.6  193.49  4515.2  190.60  4613.7  183.96  4658.5  178.86  4668.5  176.91
  4678.5  176.54  4705.4  172.98  4712.3  173.37  4758.5  165.91  4810.8  162.01
  4818.5  160.92  4858.6  160.65  4878.6  159.03  4909.3  158.76  4938.6  158.66
  4978.6  156.32  4998.6  148.57  5005.6  148.44  5006.1  147.94  5011.5  148.44
  5029.4  150.35  5034.7  152.91  5051.2  153.64  5094.2  160.89  5114.5  162.42
  5142.6  165.00  5166.9  171.57  5196.5  176.90  5358.4  183.16  5564.2  188.06
#Mann=9,-1,0
  4467.6    0.12       0  4515.2   0.013       0  4613.7    0.12       0
  4712.3    0.05       0  4810.8    0.12       0  4909.3     0.1       0
  5005.6    0.05       0  5011.5     0.1       0  5114.5    0.12       0
Bank Sta=5005.6,5011.5
Exp/Cntr=0.3,0.1

Type RM Length L Ch R = 1,5625,147,147,147
BEGIN DESCRIPTION:
Mapping XS 6abd9d1e
END DESCRIPTION:
XS GIS Cut Line= 3
      2530596.80     13567225.08      2530501.31     13566578.34
      2530258.23     13566317.90
#Sta/Elev= 30
  4364.2  190.59  4435.0  189.15  4544.2  182.71  4566.4  180.39  4585.6  177.07
  4619.1  167.16  4637.2  163.88  4657.4  161.33  4742.1  158.21  4829.3  157.23
  4887.4  153.25  4962.1  154.36  4991.0  152.42  5001.1  148.39  5008.3  147.44
  5008.8  146.94  5014.2  147.44  5017.1  152.14  5024.6  153.06  5038.8  157.27
  5051.3  159.80  5067.1  164.84  5095.5  168.44  5102.8  170.50  5123.8  174.00
  5145.3  176.28  5180.5  177.86  5229.8  181.68  5300.6  184.36  5374.2  186.12
#Mann=7,-1,0
  4364.2    0.04       0  4544.2    0.12       0  4585.6    0.05       0
  4742.1     0.1       0  5008.3    0.05       0  5014.2     0.1       0
  5051.3    0.12       0
Bank Sta=5008.3,5014.2
Exp/Cntr=0.3,0.1

Type RM Length L Ch R = 1,5478,323,323,323
BEGIN DESCRIPTION:
Mapping XS 80167444
END DESCRIPTION:
XS GIS Cut Line= 3
      2530709.64     13567090.51      2530653.22     13566578.34
      2530380.69     13566189.01
#Sta/Elev= 30
  4461.5  186.00  4539.9  182.10  4607.9  177.29  4637.0  173.37  4678.3  164.18
  4708.5  159.84  4769.6  156.16  4799.0  153.05  4823.9  154.04  4829.2  151.94
  4839.3  151.40  4899.6  152.31  4914.8  153.42  4960.0  151.89  4993.0  151.92
  5005.6  150.23  5014.3  146.83  5017.5  146.63  5018.0  146.13  5023.4  146.63
  5029.1  149.47  5035.2  149.68  5041.9  155.40  5050.1  160.17  5056.2  161.92
  5074.2  163.00  5186.9  169.60  5380.5  183.90  5395.3  183.98  5452.0  187.54
#Mann=6,-1,0
  4461.5    0.04       0  4539.9    0.12       0  4769.6     0.1       0
  5017.5    0.05       0  5023.4     0.1       0  5074.2    0.12       0
Bank Sta=5017.5,5023.4
Exp/Cntr=0.3,0.1

Type RM Length L Ch R = 1,5155,382,382,382
BEGIN DESCRIPTION:
Mapping XS 2442a67a
END DESCRIPTION:
XS GIS Cut Line= 3
      2530818.15     13567077.47      2530926.66     13566582.68
      2530818.35     13566119.11
#Sta/Elev= 30
  4535.0  181.08  4639.0  177.29  4691.1  176.32  4870.3  166.32  4875.5  167.06
  4906.1  165.53  4919.3  166.59  4936.8  165.84  4947.0  163.81  4963.1  157.24
  4968.2  160.76  4988.0  149.34  4990.3  148.93  5025.9  145.33  5026.4  144.83
  5032.0  145.33  5037.8  147.36  5059.7  150.69  5067.8  151.09  5080.2  148.72
  5131.6  154.53  5160.3  154.99  5262.1  162.82  5264.2  162.97  5290.7  164.15
  5316.4  166.83  5357.5  173.38  5418.2  179.39  5449.9  180.78  5517.6  180.09
#Mann=8,-1,0
  4535.0    0.04       0  4639.0    0.12       0  4990.3     0.1       0
  5025.9    0.05       0  5032.0     0.1       0  5160.3    0.12       0
  5262.1     0.1       0  5264.2    0.12       0
Bank Sta=5025.9,5032
Exp/Cntr=0.3,0.1