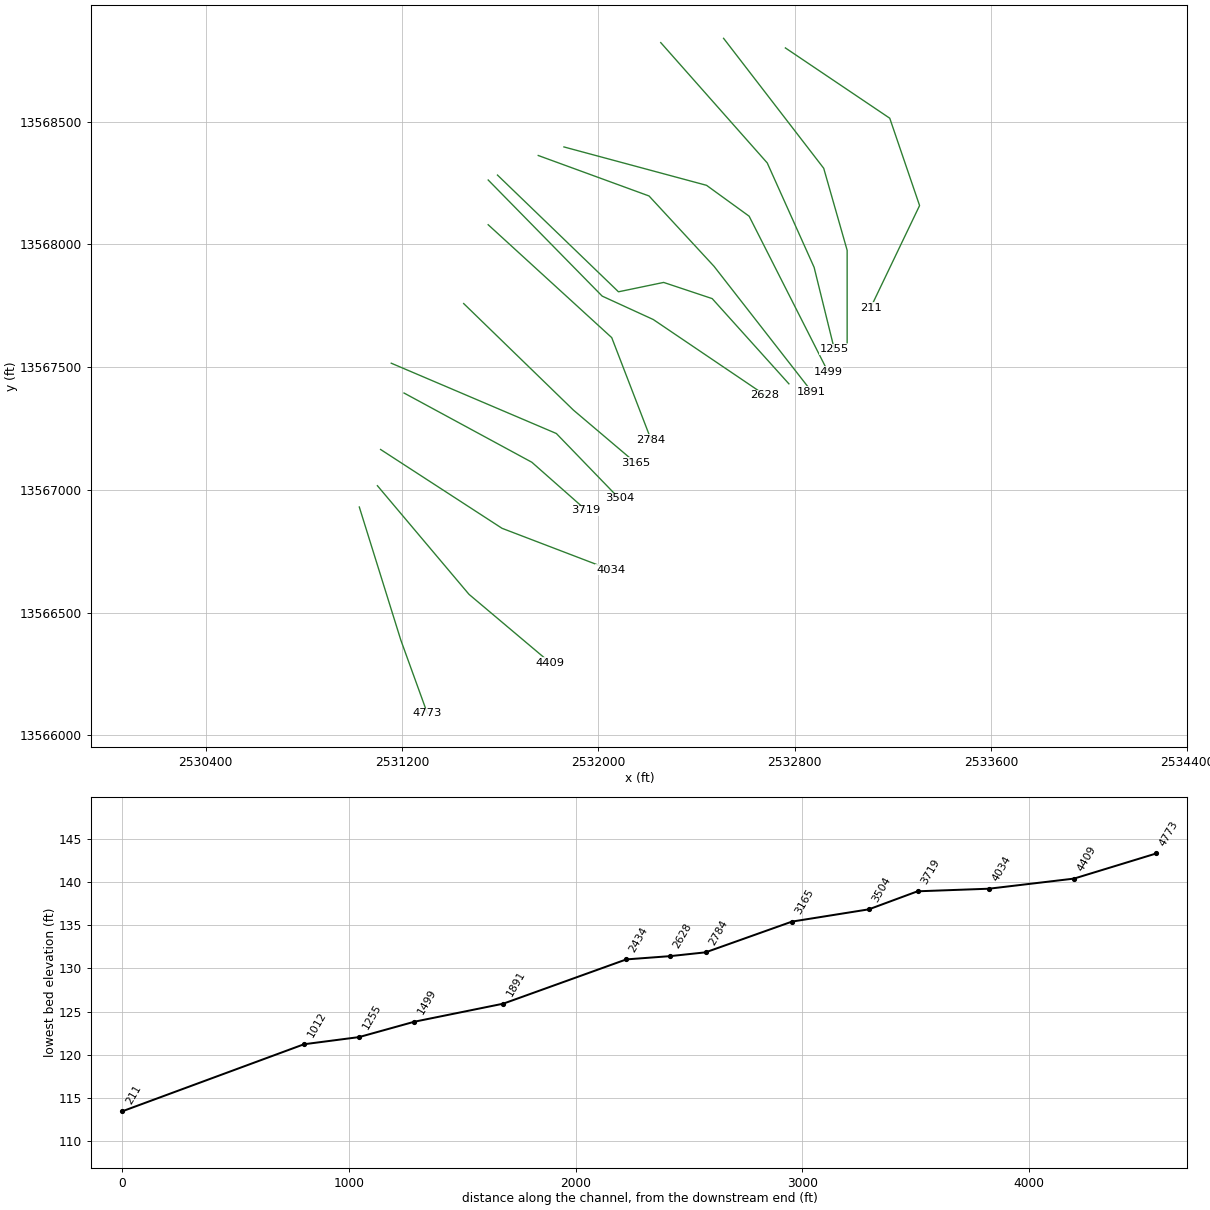
HEC-RAS study CATTAIL CREEK.prj: CATTAIL CREEK Base Level Engineering

--- CATTAIL CREEK.g01 (geometry) --- (continued)

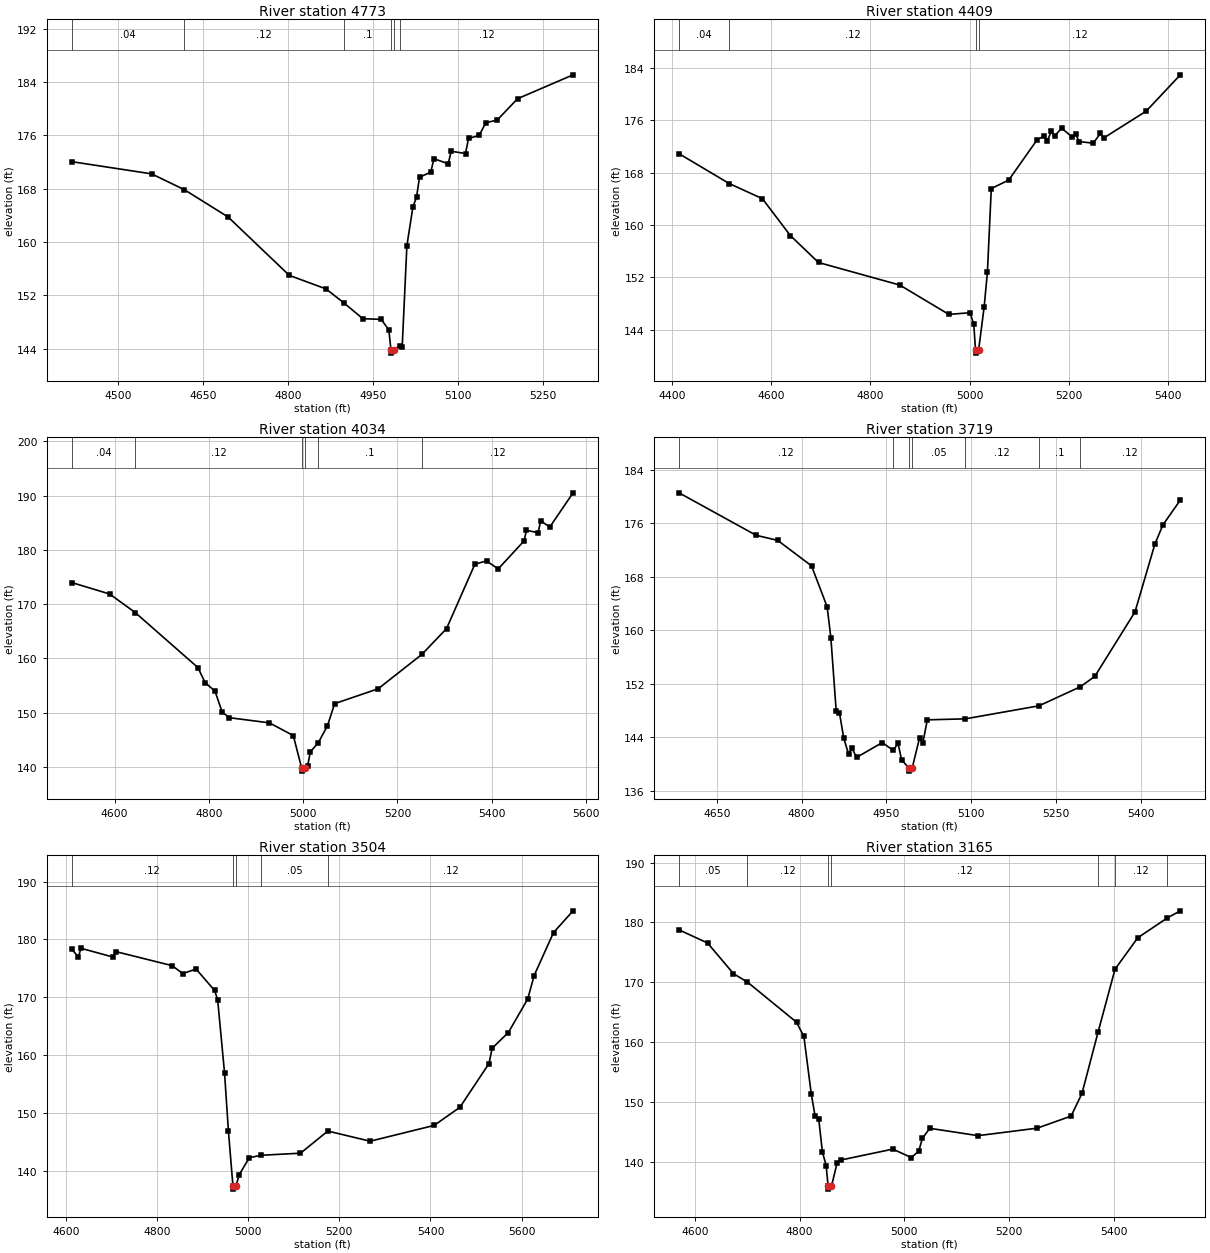
Type RM Length L Ch R = 1,4773,364,364,364
BEGIN DESCRIPTION:
Mapping XS 697db7d2
END DESCRIPTION:
XS GIS Cut Line= 3
      2531026.48     13566929.91      2531195.75     13566387.36
      2531303.86     13566088.98
#Sta/Elev= 30
  4417.9  172.07  4559.0  170.24  4617.1  167.85  4694.2  163.76  4802.2  155.00
  4867.2  152.96  4898.3  150.89  4932.2  148.49  4964.7  148.39  4978.2  146.79
  4981.8  143.82  4982.3  143.32  4988.0  143.82  4997.3  144.46  5001.7  144.23
  5010.0  159.45  5020.7  165.30  5027.0  166.71  5032.3  169.74  5052.3  170.50
  5057.7  172.52  5083.0  171.75  5088.3  173.64  5113.6  173.29  5118.9  175.55
  5137.7  176.02  5149.5  177.92  5169.5  178.31  5205.5  181.52  5303.6  185.11
#Mann=6,-1,0
  4417.9    0.04       0  4617.1    0.12       0  4898.3     0.1       0
  4981.8    0.05       0  4988.0     0.1       0  4997.3    0.12       0
Bank Sta=4981.8,4988
Exp/Cntr=0.3,0.1

Type RM Length L Ch R = 1,4409,375,375,375
BEGIN DESCRIPTION:
Mapping XS d135e3dc
END DESCRIPTION:
XS GIS Cut Line= 3
      2531100.28     13567016.68      2531473.53     13566574.00
      2531803.41     13566296.21
#Sta/Elev= 30
  4414.6  170.90  4515.9  166.33  4582.6  164.02  4639.2  158.36  4695.7  154.26
  4859.5  150.81  4958.4  146.32  5001.0  146.58  5008.6  144.81  5012.1  140.90
  5012.6  140.40  5018.4  140.90  5029.6  147.51  5036.1  152.81  5043.9  165.57
  5079.0  166.86  5136.2  173.02  5150.5  173.61  5157.0  172.88  5164.8  174.33
  5171.3  173.58  5185.6  174.80  5206.5  173.48  5214.2  173.91  5220.8  172.75
  5249.4  172.51  5263.7  173.99  5270.2  173.29  5356.0  177.40  5424.9  182.96
#Mann=4,-1,0
  4414.6    0.04       0  4515.9    0.12       0  5012.1    0.05       0
  5018.4    0.12       0
Bank Sta=5012.1,5018.4
Exp/Cntr=0.3,0.1

Type RM Length L Ch R = 1,4034,315,315,315
BEGIN DESCRIPTION:
Mapping XS 3435afdc
END DESCRIPTION:
XS GIS Cut Line= 3
      2531113.28     13567164.28      2531608.08     13566843.09
      2532050.35     13566673.99
#Sta/Elev= 30
  4509.2  173.99  4589.6  171.88  4643.9  168.46  4776.8  158.32  4792.0  155.56
  4813.1  153.97  4828.2  150.14  4843.4  149.08  4928.5  148.13  4979.2  145.78
  4997.1  139.73  4997.6  139.23  5003.5  139.73  5009.5  140.18  5015.4  142.80
  5031.9  144.43  5051.7  147.60  5066.8  151.67  5159.2  154.41  5252.2  160.77
  5304.2  165.50  5364.3  177.37  5389.0  177.99  5413.7  176.50  5468.5  181.65
  5473.8  183.62  5498.5  183.18  5503.9  185.38  5523.2  184.22  5572.6  190.53
#Mann=6,-1,0
  4509.2    0.04       0  4643.9    0.12       0  4997.1    0.05       0
  5003.5    0.12       0  5031.9     0.1       0  5252.2    0.12       0
Bank Sta=4997.1,5003.5
Exp/Cntr=0.3,0.1

Type RM Length L Ch R = 1,3719,215,215,215
BEGIN DESCRIPTION:
Mapping XS 8063c6d4
END DESCRIPTION:
XS GIS Cut Line= 3
      2531208.80     13567394.29      2531729.61     13567112.19
      2531950.51     13566917.28
#Sta/Elev= 30
  4583.1  180.55  4719.5  174.20  4757.6  173.44  4817.5  169.63  4845.1  163.52
  4851.7  158.90  4861.2  147.91  4866.9  147.68  4874.5  143.86  4883.1  141.46
  4888.8  142.43  4897.2  140.98  4942.7  143.20  4962.2  142.03  4970.6  143.09
  4976.8  140.63  4989.3  139.43  4989.8  138.93  4995.7  139.43  5008.6  143.88
  5014.3  143.07  5022.3  146.60  5089.7  146.75  5220.0  148.70  5292.7  151.53
  5318.7  153.10  5389.8  162.75  5424.9  172.87  5439.2  175.76  5470.0  179.47
#Mann=7,-1,0
  4583.1    0.12       0  4962.2    0.05       0  4989.3    0.05       0
  4995.7    0.05       0  5089.7    0.12       0  5220.0     0.1       0
  5292.7    0.12       0
Bank Sta=4989.3,4995.7
Exp/Cntr=0.3,0.1

Type RM Length L Ch R = 1,3504,339,339,339
BEGIN DESCRIPTION:
Mapping XS 62ff1fb4
END DESCRIPTION:
XS GIS Cut Line= 3
      2531156.71     13567515.83      2531829.43     13567229.38
      2532085.50     13566964.63
#Sta/Elev= 30
  4613.2  178.32  4627.9  176.96  4633.3  178.47  4704.2  176.94  4709.6  177.90
  4833.2  175.47  4856.8  174.10  4885.9  174.88  4926.5  171.18  4933.2  169.58
  4948.3  156.96  4956.8  146.91  4966.8  137.34  4967.3  136.84  4973.2  137.34
  4980.4  139.32  5002.6  142.26  5027.8  142.69  5114.9  143.05  5174.9  146.88
  5267.6  145.12  5407.9  147.85  5464.5  150.98  5528.3  158.55  5535.2  161.19
  5570.7  163.90  5613.2  169.69  5627.3  173.75  5669.8  181.18  5712.7  184.94
#Mann=5,-1,0
  4613.2    0.12       0  4966.8    0.05       0  4973.2    0.12       0
  5027.8    0.05       0  5174.9    0.12       0
Bank Sta=4966.8,4973.2
Exp/Cntr=0.3,0.1

Type RM Length L Ch R = 1,3165,381,381,381
BEGIN DESCRIPTION:
Mapping XS f6358381
END DESCRIPTION:
XS GIS Cut Line= 3
      2531451.82     13567758.90      2531898.88     13567324.86
      2532153.69     13567108.93
#Sta/Elev= 30
  4569.9  178.77  4624.4  176.57  4673.8  171.45  4700.6  170.03  4794.2  163.33
  4808.3  160.94  4822.5  151.27  4829.5  147.72  4836.6  147.18  4843.6  141.65
  4850.8  139.36  4854.5  135.92  4855.0  135.42  4861.0  135.92  4871.9  139.87
  4879.1  140.29  4978.1  142.11  5013.4  140.70  5027.5  141.76  5034.5  143.90
  5048.6  145.59  5140.7  144.36  5253.5  145.61  5318.4  147.63  5339.2  151.42
  5370.1  161.73  5402.3  172.19  5445.8  177.45  5502.1  180.76  5527.0  181.95
#Mann=7,-1,0
  4569.9    0.05       0  4700.6    0.12       0  4854.5    0.05       0
  4861.0    0.12       0  5370.1    0.05       0  5402.3    0.12       0
  5502.1    0.05       0
Bank Sta=4854.5,4861
Exp/Cntr=0.3,0.1

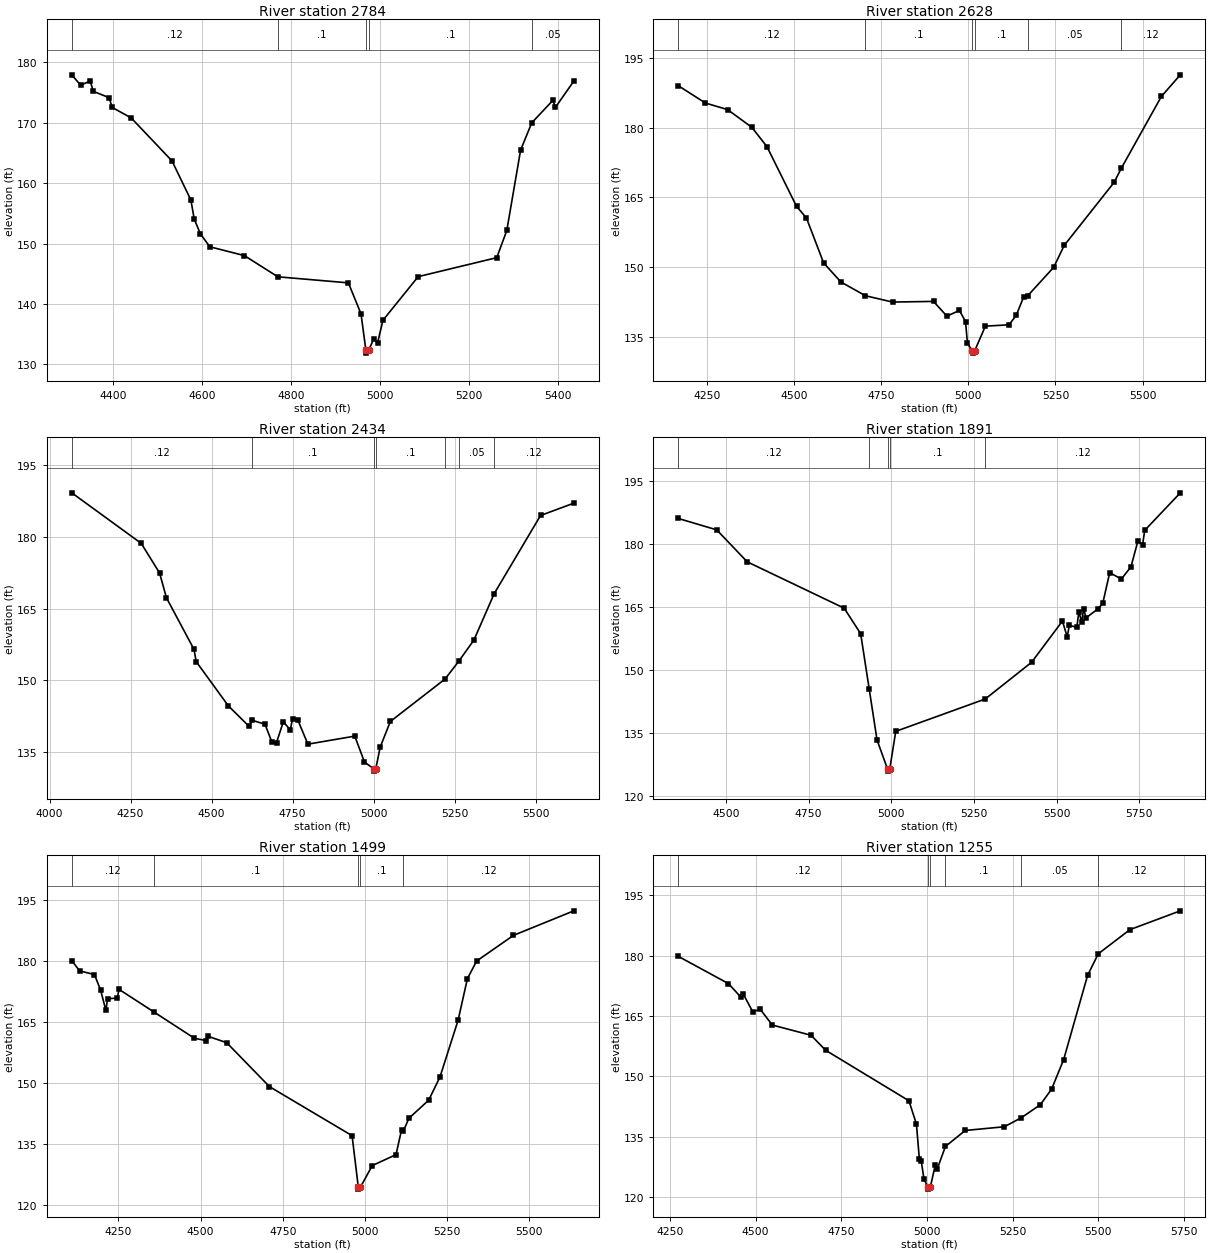
Type RM Length L Ch R = 1,2784,156,156,156
BEGIN DESCRIPTION:
Mapping XS 567d8413
END DESCRIPTION:
XS GIS Cut Line= 3
      2531551.65     13568080.07      2532055.13     13567620.00
      2532215.73     13567203.30
#Sta/Elev= 30
  4306.4  177.92  4326.3  176.21  4347.9  176.90  4354.7  175.19  4390.4  174.14
  4397.2  172.52  4439.8  170.80  4531.7  163.67  4574.2  157.19  4581.6  154.07
  4595.4  151.61  4616.8  149.46  4694.5  148.00  4769.7  144.49  4928.2  143.49
  4956.6  138.35  4967.5  132.36  4968.0  131.86  4974.1  132.36  4984.9  134.20
  4993.8  133.55  5005.9  137.30  5085.1  144.52  5261.7  147.66  5284.3  152.16
  5315.3  165.46  5340.4  169.98  5388.1  173.71  5393.5  172.53  5435.0  176.89
#Mann=5,-1,0
  4306.4    0.12       0  4769.7     0.1       0  4967.5    0.05       0
  4974.1     0.1       0  5340.4    0.05       0
Bank Sta=4967.5,4974.1
Exp/Cntr=0.3,0.1

Type RM Length L Ch R = 1,2628,194,194,194
BEGIN DESCRIPTION:
Mapping XS 9471d3a5
END DESCRIPTION:
XS GIS Cut Line= 4
      2531551.69     13568262.33      2532016.06     13567789.27
      2532224.40     13567693.79      2532680.04     13567385.69
#Sta/Elev= 30
  4166.5  189.08  4244.8  185.33  4308.4  183.92  4378.2  180.08  4421.5  175.91
  4506.4  163.05  4534.7  160.56  4584.1  150.87  4633.7  146.76  4704.3  143.79
  4782.1  142.43  4899.7  142.57  4938.2  139.39  4974.2  140.63  4991.7  138.22
  4997.2  133.52  5011.4  131.92  5011.9  131.42  5018.0  131.92  5048.7  137.24
  5116.3  137.52  5137.2  139.54  5158.2  143.46  5170.6  143.81  5245.1  149.94
  5275.1  154.64  5418.9  168.28  5439.0  171.26  5554.2  186.75  5608.6  191.42
#Mann=6,-1,0
  4166.5    0.12       0  4704.3     0.1       0  5011.4    0.05       0
  5018.0     0.1       0  5170.6    0.05       0  5439.0    0.12       0
Bank Sta=5011.4,5018
Exp/Cntr=0.3,0.1

Type RM Length L Ch R = 1,2434,543,543,543
BEGIN DESCRIPTION:
Mapping XS a50e995c
END DESCRIPTION:
XS GIS Cut Line= 5
      2531589.53     13568282.45      2532082.56     13567806.79
      2532266.59     13567844.98      2532464.50     13567779.01
      2532777.01     13567431.78
#Sta/Elev= 30
  4068.7  189.24  4283.0  178.67  4339.6  172.47  4360.7  167.30  4445.6  156.52
  4452.6  153.93  4551.6  144.70  4615.4  140.41  4626.0  141.66  4664.8  140.84
  4686.1  137.12  4700.3  137.01  4721.4  141.39  4742.7  139.63  4749.7  142.00
  4765.5  141.80  4797.1  136.68  4941.7  138.36  4971.7  132.93  5000.0  131.54
  5000.5  131.04  5006.6  131.54  5019.9  136.02  5051.5  141.43  5220.2  150.30
  5262.2  153.99  5309.3  158.46  5371.9  168.17  5514.8  184.50  5617.5  187.08
#Mann=7,-1,0
  4068.7    0.12       0  4626.0     0.1       0  5000.0    0.05       0
  5006.6     0.1       0  5220.2    0.12       0  5262.2    0.05       0
  5371.9    0.12       0
Bank Sta=5000,5006.6
Exp/Cntr=0.3,0.1

Type RM Length L Ch R = 1,1891,392,392,392
BEGIN DESCRIPTION:
Mapping XS 44fbce80
END DESCRIPTION:
XS GIS Cut Line= 4
      2531755.70     13568362.17      2532207.04     13568197.26
      2532471.79     13567910.80      2532870.04     13567400.00
#Sta/Elev= 30
  4355.8  186.00  4472.2  183.28  4564.4  175.68  4857.6  164.66  4907.5  158.59
  4933.2  145.49  4956.9  133.34  4988.7  126.41  4989.2  125.91  4995.4  126.41
  5013.6  135.37  5284.2  143.06  5424.5  151.80  5517.6  161.60  5532.1  157.82
  5538.5  160.59  5561.1  160.09  5567.4  163.85  5575.5  161.38  5581.9  164.58
  5588.8  162.34  5625.3  164.52  5639.5  165.80  5660.6  173.11  5695.9  171.58
  5724.8  174.49  5745.6  180.55  5760.1  179.78  5766.4  183.16  5874.1  192.09
#Mann=5,-1,0
  4355.8    0.12       0  4933.2     0.1       0  4988.7    0.05       0
  4995.4     0.1       0  5284.2    0.12       0
Bank Sta=4988.7,4995.4
Exp/Cntr=0.3,0.1

Type RM Length L Ch R = 1,1499,244,244,244
BEGIN DESCRIPTION:
Mapping XS 4b76ad1f
END DESCRIPTION:
XS GIS Cut Line= 4
      2531860.31     13568397.07      2532441.41     13568240.66
      2532615.02     13568114.80      2532936.18     13567481.16
#Sta/Elev= 30
  4108.5  180.00  4132.3  177.47  4177.4  176.57  4196.2  172.74  4212.2  167.76
  4217.4  170.61  4247.0  170.79  4252.1  172.93  4357.6  167.40  4481.5  160.90
  4516.3  160.35  4521.4  161.42  4579.4  159.83  4709.5  149.02  4960.8  136.96
  4979.7  124.32  4980.2  123.82  4986.4  124.32  5022.0  129.60  5094.4  132.30
  5111.1  138.37  5116.8  138.05  5133.3  141.22  5193.6  145.67  5228.0  151.37
  5283.2  165.35  5311.5  175.57  5339.4  179.88  5451.4  186.19  5635.1  192.23
#Mann=5,-1,0
  4108.5    0.12       0  4357.6     0.1       0  4979.7    0.05       0
  4986.4     0.1       0  5116.8    0.12       0
Bank Sta=4979.7,4986.4
Exp/Cntr=0.3,0.1

Type RM Length L Ch R = 1,1255,243,243,243
BEGIN DESCRIPTION:
Mapping XS fb8d11f7
END DESCRIPTION:
XS GIS Cut Line= 4
      2532254.81     13568822.22      2532688.81     13568331.81
      2532879.78     13567906.46      2532962.26     13567572.21
#Sta/Elev= 30
  4274.2  179.82  4420.9  173.04  4456.9  169.69  4463.6  170.53  4492.1  165.98
  4513.0  166.73  4548.9  162.76  4661.8  160.23  4704.5  156.50  4947.5  143.97
  4969.4  138.19  4977.9  129.57  4983.3  129.14  4991.3  124.57  5003.1  122.54
  5003.6  122.04  5010.0  122.54  5024.2  127.96  5029.7  126.93  5054.0  132.63
  5111.9  136.60  5226.0  137.52  5275.3  139.74  5331.2  143.00  5364.0  146.88
  5399.1  154.18  5468.9  175.07  5500.2  180.45  5592.5  186.44  5739.6  191.11
#Mann=6,-1,0
  4274.2    0.12       0  5003.1    0.05       0  5010.0    0.12       0
  5054.0     0.1       0  5275.3    0.05       0  5500.2    0.12       0
Bank Sta=5003.1,5010
Exp/Cntr=0.3,0.1

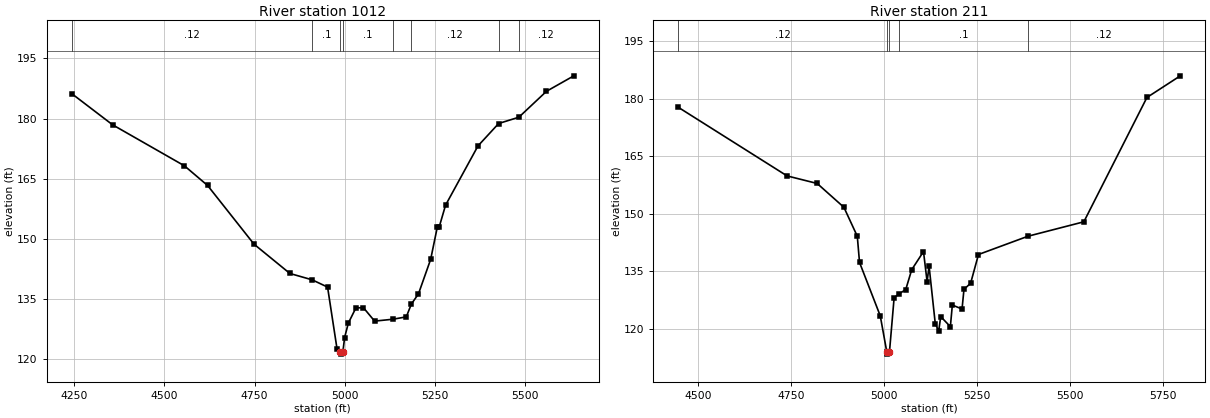
Type RM Length L Ch R = 1,1012,801,801,801
BEGIN DESCRIPTION:
Mapping XS 033dbdfb
END DESCRIPTION:
XS GIS Cut Line= 4
      2532510.88     13568839.60      2532918.84     13568310.11
      2533014.33     13567975.91      2533014.33     13567599.11
#Sta/Elev= 30
  4243.0  186.22  4356.2  178.45  4555.5  168.21  4619.8  163.30  4748.5  148.66
  4848.1  141.34  4910.0  139.75  4952.6  137.94  4979.1  122.38  4988.1  121.71
  4988.6  121.21  4995.0  121.71  4999.9  125.36  5010.3  128.97  5031.1  132.73
  5051.9  132.82  5083.1  129.45  5134.0  129.92  5171.0  130.51  5185.0  133.69
  5204.8  136.26  5238.6  144.87  5256.9  152.86  5262.0  152.86  5279.9  158.38
  5369.9  173.18  5427.2  178.77  5483.3  180.34  5559.9  186.81  5635.8  190.67
#Mann=8,-1,0
  4243.0    0.12       0  4910.0     0.1       0  4988.1    0.05       0
  4995.0     0.1       0  5134.0    0.05       0  5185.0    0.12       0
  5427.2    0.05       0  5483.3    0.12       0
Bank Sta=4988.1,4995
Exp/Cntr=0.3,0.1

Type RM Length L Ch R = 1,211,0,0,0
BEGIN DESCRIPTION:
CATTAIL CREEK 1.0
END DESCRIPTION:
XS GIS Cut Line= 4
      2532762.61     13568800.55      2533187.94     13568514.10
      2533309.47     13568158.20      2533109.90     13567741.72
#Sta/Elev= 30
  4446.4  177.78  4739.2  159.89  4820.2  157.92  4892.1  151.71  4928.1  144.17
  4934.1  137.35  4989.9  123.42  5007.6  113.95  5008.1  113.45  5014.6  113.95
  5027.2  128.17  5040.6  129.15  5058.5  130.29  5074.5  135.45  5106.2  140.18
  5115.9  132.32  5121.2  136.41  5137.9  121.36  5147.2  119.50  5152.5  123.24
  5178.5  120.61  5183.8  126.24  5209.9  125.20  5215.1  130.33  5233.0  131.92
  5254.1  139.41  5387.5  144.18  5537.6  147.93  5707.3  180.33  5797.1  185.97
#Mann=5,-1,0
  4446.4    0.12       0  5007.6    0.05       0  5014.6    0.12       0
  5040.6     0.1       0  5387.5    0.12       0
Bank Sta=5007.6,5014.6
Exp/Cntr=0.3,0.1

Chan Stop Cuts=-1