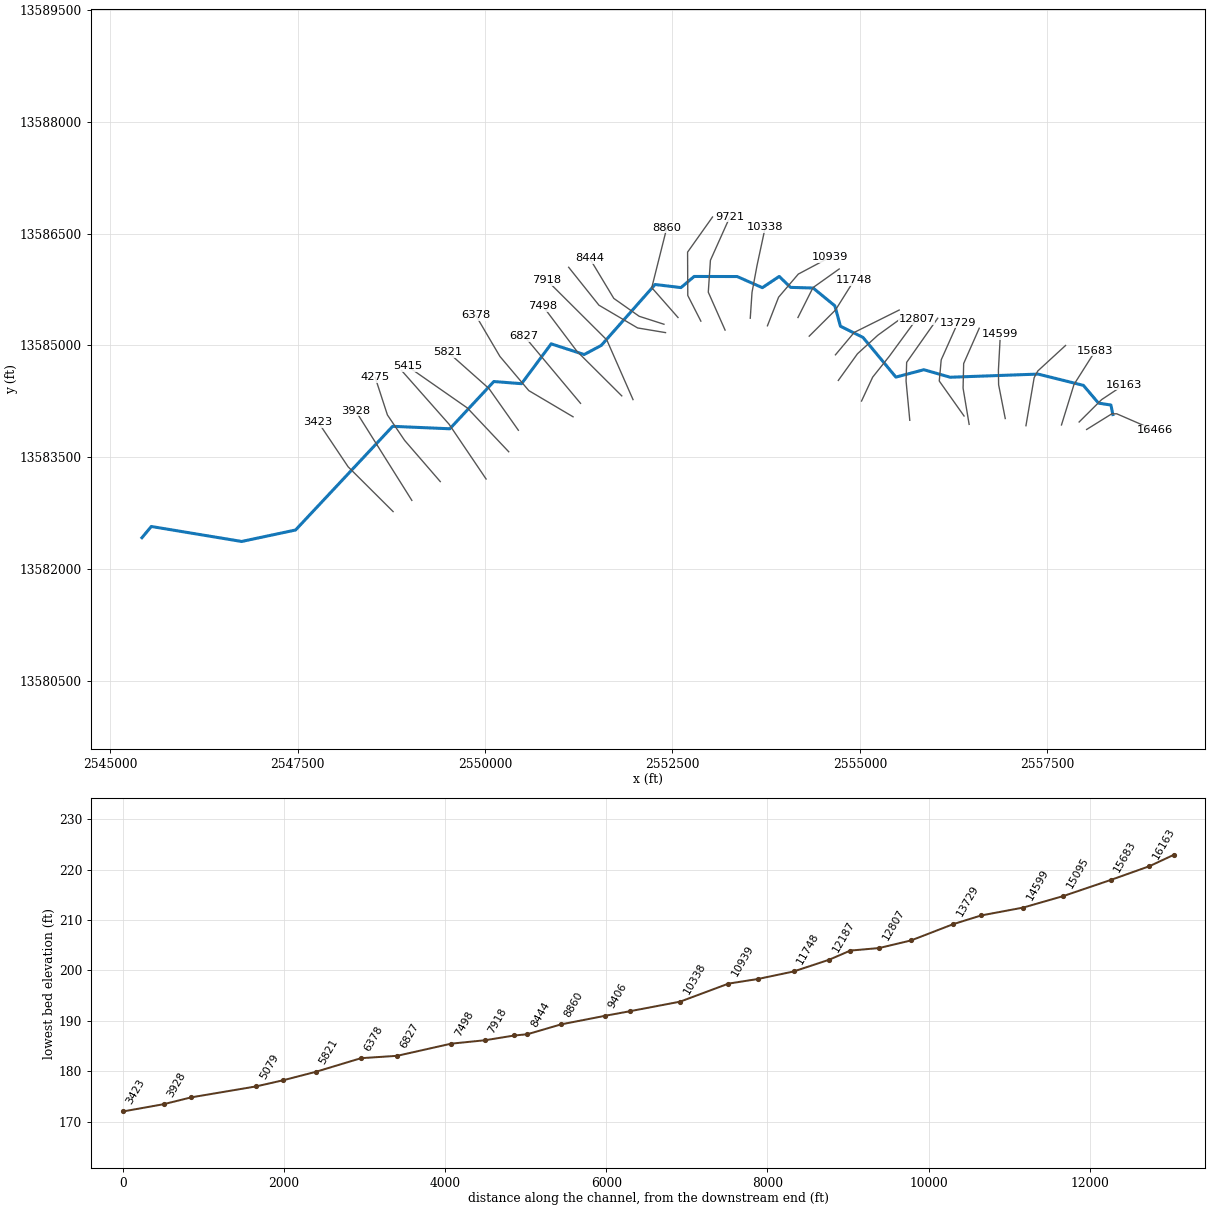
--- CRITTENOON HOLLOW.prj (project) ---

Proj Title=CRITTENOON HOLLOW Base Level Engineering
Current Plan=p01
Default Exp/Contr=0.3,0.1
English Units
Geom File=g01
Flow File=f01
Plan File=p01
Y Axis Title=Elevation
X Axis Title(PF)=Main Channel Distance
X Axis Title(XS)=Station
BEGIN DESCRIPTION:
CRITTENOON HOLLOW
END DESCRIPTION:
DSS Export Rating Curves= 0
DSS Export Rating Curve Sorted= 0
DSS Export Volume Flow Curves= 0
DXF OffsetX= 0
DXF OffsetY= 0
DXF ScaleX= 1
DXF ScaleY= 10

--- CRITTENOON HOLLOW.p01 (plan) ---

Plan Title=Multiple Run
Short Identifier=Multiple
Geom File=g01
Flow File=f01
Subcritical Flow
K Sum by GR= 0
Std Step Tol= 0.01
Critical Tol= 0.01
Num of Std Step Trials= 20
Max Error Tol= 0.3
Flow Tol Ratio= 0.001
Split Flow NTrial= 30
Split Flow Tol= 0.02
Split Flow Ratio= 0.02
Log Output Level= 0
Friction Slope Method= 1
Unsteady Friction Slope Method= 2
Unsteady Bridges Friction Slope Method= 1
Parabolic Critical Depth
Global Vel Dist=  1 , 1 , 1
Global Log Level= 0
CheckData=True
Encroach Param= -1, 0, 0, 0
BEGIN DESCRIPTION:
Multiple Run
END DESCRIPTION:

--- CRITTENOON HOLLOW.f01 (steady flow) ---

Flow Title=Multiple
Number of Profiles=7
Profile Names=10-year,25-year,50-year,1pct_min,100-year,1pct_plu,500-year
River Rch & RM= CRITTENOON HOLLO,Reach-1,16466
     606     963    1281     826    1648    3289    2697
River Rch & RM= CRITTENOON HOLLO,Reach-1,16163
     642    1022    1361     879    1754    3500    2878
River Rch & RM= CRITTENOON HOLLO,Reach-1,14599
     799    1293    1741    1135    2264    4517    3789
River Rch & RM= CRITTENOON HOLLO,Reach-1,13206
     952    1554    2104    1378    2749    5486    4650
River Rch & RM= CRITTENOON HOLLO,Reach-1,10338
    1267    2099    2870    1897    3784    7550    6516
River Rch & RM= CRITTENOON HOLLO,Reach-1,8444
    1493    2493    3427    2276    4542    9062    7899
River Rch & RM= CRITTENOON HOLLO,Reach-1,7918
    1631    2731    3763    2503    4993    9963    8712
River Rch & RM= CRITTENOON HOLLO,Reach-1,5821
    1701    2849    3925    2610    5208   10392    9083
River Rch & RM= CRITTENOON HOLLO,Reach-1,1874
    1935    3261    4511    3011    6008   11987   10557
Boundary for River Rch & Prof#=CRITTENOON HOLLO,Reach-1,1
Up Type=0
Dn Type=3
Dn Slope=0.005
Boundary for River Rch & Prof#=CRITTENOON HOLLO,Reach-1,2
Up Type=0
Dn Type=3
Dn Slope=0.005
Boundary for River Rch & Prof#=CRITTENOON HOLLO,Reach-1,3
Up Type=0
Dn Type=3
Dn Slope=0.005
Boundary for River Rch & Prof#=CRITTENOON HOLLO,Reach-1,4
Up Type=0
Dn Type=3
Dn Slope=0.005
Boundary for River Rch & Prof#=CRITTENOON HOLLO,Reach-1,5
Up Type=0
Dn Type=3
Dn Slope=0.005
Boundary for River Rch & Prof#=CRITTENOON HOLLO,Reach-1,6
Up Type=0
Dn Type=3
Dn Slope=0.005
Boundary for River Rch & Prof#=CRITTENOON HOLLO,Reach-1,7
Up Type=0
Dn Type=3
Dn Slope=0.005

--- CRITTENOON HOLLOW.g01 (geometry) ---

Geom Title=Existing Conditions

River Reach=CRITTENOON HOLLO,Reach-1
Reach XY= 30
      2558375.00     13584075.00      2558349.02     13584202.38
      2558183.31     13584228.08      2557981.67     13584465.71
      2557378.30     13584616.92      2556204.64     13584574.63
      2555854.82     13584675.44      2555481.03     13584576.62
      2555041.75     13585108.54      2554741.44     13585258.21
      2554667.15     13585531.19      2554377.29     13585769.89
      2554076.47     13585778.54      2553925.00     13585925.00
      2553700.00     13585774.41      2553364.50     13585923.78
      2552790.16     13585924.62      2552614.38     13585775.60
      2552268.81     13585817.19      2551551.82     13585001.29
      2551323.45     13584878.75      2550883.34     13585022.03
      2550488.56     13584488.46      2550118.54     13584517.36
      2549531.67     13583884.30      2548768.81     13583917.19
      2547473.97     13582528.14      2546754.85     13582374.64
      2545549.87     13582575.30      2545425.00     13582425.00

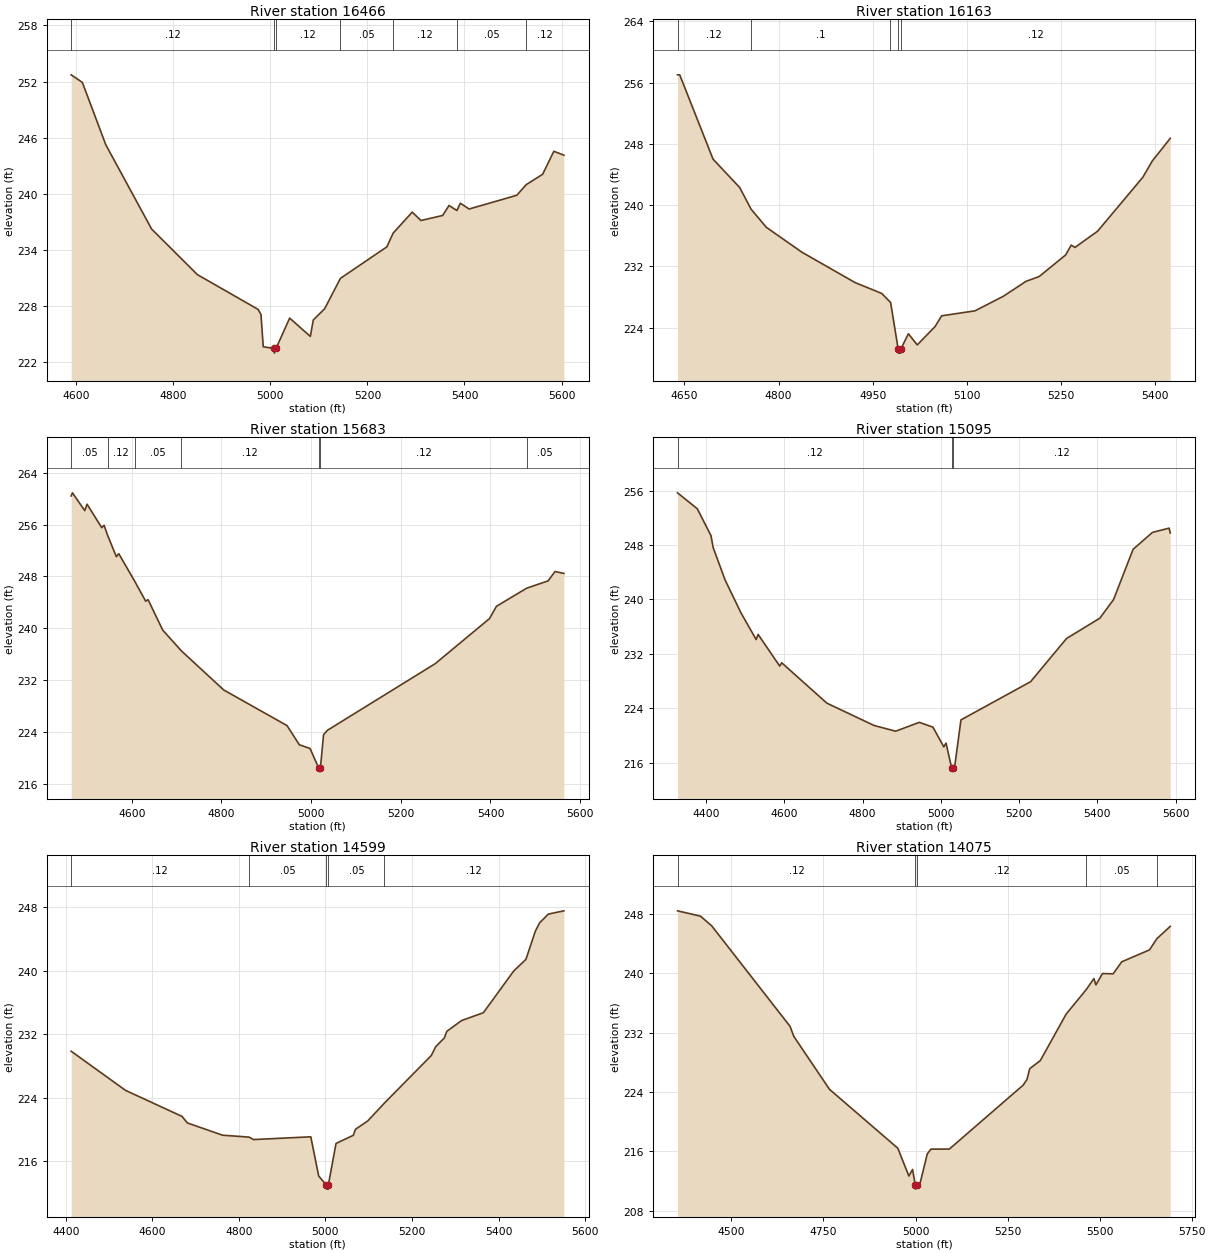
Type RM Length L Ch R = 1,16466,303,303,303
BEGIN DESCRIPTION:
CRITTENOON HOLLOW 34.0
END DESCRIPTION:
XS GIS Cut Line= 4
      2558025.04     13583875.02      2558361.31     13584084.97
      2558426.83     13584084.97      2558933.99     13583864.15
#Sta/Elev= 30
  4589.8  252.72  4612.8  251.91  4661.1  245.24  4755.5  236.22  4849.8  231.34
  4974.9  227.62  4980.8  227.08  4985.5  223.62  5007.9  223.44  5008.2  222.94
  5011.9  223.44  5039.9  226.69  5082.5  224.73  5088.6  226.49  5112.0  227.69
  5144.5  230.94  5240.1  234.31  5253.1  235.78  5292.4  238.03  5310.4  237.13
  5355.1  237.67  5368.2  238.74  5384.4  238.20  5391.6  238.98  5409.6  238.36
  5507.8  239.83  5527.3  240.97  5561.1  242.08  5584.2  244.54  5604.9  244.12
#Mann=7,-1,0
  4589.8    0.12       0  5007.9    0.05       0  5011.9    0.12       0
  5144.5    0.05       0  5253.1    0.12       0  5384.4    0.05       0
  5527.3    0.12       0
Bank Sta=5007.9,5011.9
Exp/Cntr=0.3,0.1

Type RM Length L Ch R = 1,16163,480,480,480
BEGIN DESCRIPTION:
CRITTENOON HOLLOW 33.0
END DESCRIPTION:
XS GIS Cut Line= 3
      2557925.00     13583975.00      2558225.00     13584275.00
      2558524.99     13584474.99
#Sta/Elev= 30
  4638.9  257.01  4642.4  257.01  4695.5  246.00  4737.9  242.30  4756.0  239.48
  4780.3  237.11  4836.9  233.86  4921.7  229.89  4964.2  228.47  4976.7  227.42
  4978.3  227.29  4990.4  221.18  4990.7  220.68  4994.2  220.68  4994.4  221.18
  5006.6  223.21  5020.7  221.75  5049.0  224.14  5059.6  225.55  5112.7  226.20
  5157.8  228.10  5193.9  230.05  5214.9  230.68  5257.0  233.49  5266.0  234.78
  5272.0  234.48  5308.0  236.60  5380.1  243.65  5395.2  245.78  5423.7  248.72
#Mann=5,-1,0
  4638.9    0.12       0  4756.0     0.1       0  4976.7    0.12       0
  4990.4    0.05       0  4994.4    0.12       0
Bank Sta=4990.4,4994.4
Exp/Cntr=0.3,0.1

Type RM Length L Ch R = 1,15683,588,588,588
BEGIN DESCRIPTION:
Mapping XS e7b4624f
END DESCRIPTION:
XS GIS Cut Line= 3
      2557689.72     13583935.63      2557856.39     13584477.31
      2558140.12     13584927.64
#Sta/Elev= 30
  4464.8  260.43  4467.6  260.91  4495.0  258.17  4500.3  259.15  4533.0  255.53
  4538.2  255.90  4546.2  254.33  4565.6  251.05  4570.9  251.52  4606.7  247.24
  4631.0  244.18  4636.3  244.42  4669.0  239.72  4710.7  236.51  4805.0  230.48
  4946.2  224.98  4973.7  222.02  4997.7  221.44  5016.7  218.45  5016.9  217.95
  5020.7  218.45  5027.7  223.58  5036.5  224.26  5276.6  234.53  5397.9  241.50
  5413.2  243.39  5480.8  246.19  5528.6  247.32  5543.9  248.76  5563.8  248.47
#Mann=7,-1,0
  4464.8    0.05       0  4546.2    0.12       0  4606.7    0.05       0
  4710.7    0.12       0  5016.7    0.05       0  5020.7    0.12       0
  5480.8    0.05       0
Bank Sta=5016.7,5020.7
Exp/Cntr=0.3,0.1

Type RM Length L Ch R = 1,15095,496,496,496
BEGIN DESCRIPTION:
Mapping XS 1f281102
END DESCRIPTION:
XS GIS Cut Line= 4
      2557215.77     13583925.26      2557325.14     13584568.46
      2557374.62     13584659.60      2557744.01     13585000.37
#Sta/Elev= 30
  4327.4  255.68  4377.9  253.34  4412.8  249.40  4418.4  247.64  4448.9  242.87
  4489.4  238.04  4528.3  234.10  4533.3  234.86  4588.5  230.20  4593.6  230.69
  4709.0  224.75  4829.5  221.47  4884.7  220.63  4945.0  221.93  4979.8  221.23
  5007.7  218.32  5013.3  218.89  5027.5  215.26  5027.8  214.76  5031.5  215.26
  5035.2  215.34  5051.4  222.29  5229.3  227.91  5321.1  234.26  5406.2  237.25
  5441.3  239.99  5491.2  247.38  5540.6  249.86  5583.1  250.49  5586.1  249.78
#Mann=3,-1,0
  4327.4    0.12       0  5027.5    0.05       0  5031.5    0.12       0
Bank Sta=5027.5,5031.5
Exp/Cntr=0.3,0.1

Type RM Length L Ch R = 1,14599,524,524,524
BEGIN DESCRIPTION:
Mapping XS c70a36ed
END DESCRIPTION:
XS GIS Cut Line= 4
      2556939.73     13584021.55      2556851.18     13584474.71
      2556848.58     13584670.02      2556874.57     13585150.86
#Sta/Elev= 30
  4412.5  229.87  4538.3  224.93  4668.7  221.65  4680.9  220.83  4762.4  219.28
  4823.7  219.04  4833.8  218.73  4966.2  219.08  4984.5  214.13  5002.4  212.98
  5002.7  212.48  5006.4  212.48  5006.7  212.98  5024.5  218.24  5064.5  219.27
  5069.5  220.03  5097.8  221.08  5136.1  223.32  5244.8  229.34  5254.8  230.44
  5274.8  231.55  5280.5  232.38  5314.9  233.75  5365.0  234.73  5435.1  239.99
  5463.3  241.46  5485.1  245.02  5495.2  246.08  5515.2  247.17  5551.1  247.58
#Mann=5,-1,0
  4412.5    0.12       0  4823.7    0.05       0  5002.4    0.05       0
  5006.7    0.05       0  5136.1    0.12       0
Bank Sta=5002.4,5006.7
Exp/Cntr=0.3,0.1

Type RM Length L Ch R = 1,14075,346,346,346
BEGIN DESCRIPTION:
Mapping XS 7a90dcac
END DESCRIPTION:
XS GIS Cut Line= 4
      2556457.95     13583943.46      2556377.22     13584427.83
      2556385.04     13584758.56      2556592.81     13585231.24
#Sta/Elev= 30
  4353.7  248.41  4416.1  247.69  4446.5  246.39  4659.4  232.84  4669.5  231.49
  4766.4  224.36  4952.0  216.42  4982.0  212.67  4992.0  213.56  4999.7  211.41
  5000.1  210.91  5004.2  211.41  5012.0  211.62  5032.0  215.66  5042.0  216.30
  5092.0  216.31  5292.3  224.92  5302.8  225.69  5310.2  227.14  5339.0  228.23
  5409.1  234.49  5463.7  237.80  5484.6  239.28  5490.0  238.43  5507.9  239.96
  5536.7  239.92  5560.1  241.54  5635.6  243.15  5655.4  244.65  5691.9  246.32
#Mann=5,-1,0
  4353.7    0.12       0  4999.7    0.05       0  5004.2    0.12       0
  5463.7    0.05       0  5655.4    0.12       0
Bank Sta=4999.7,5004.2
Exp/Cntr=0.3,0.1

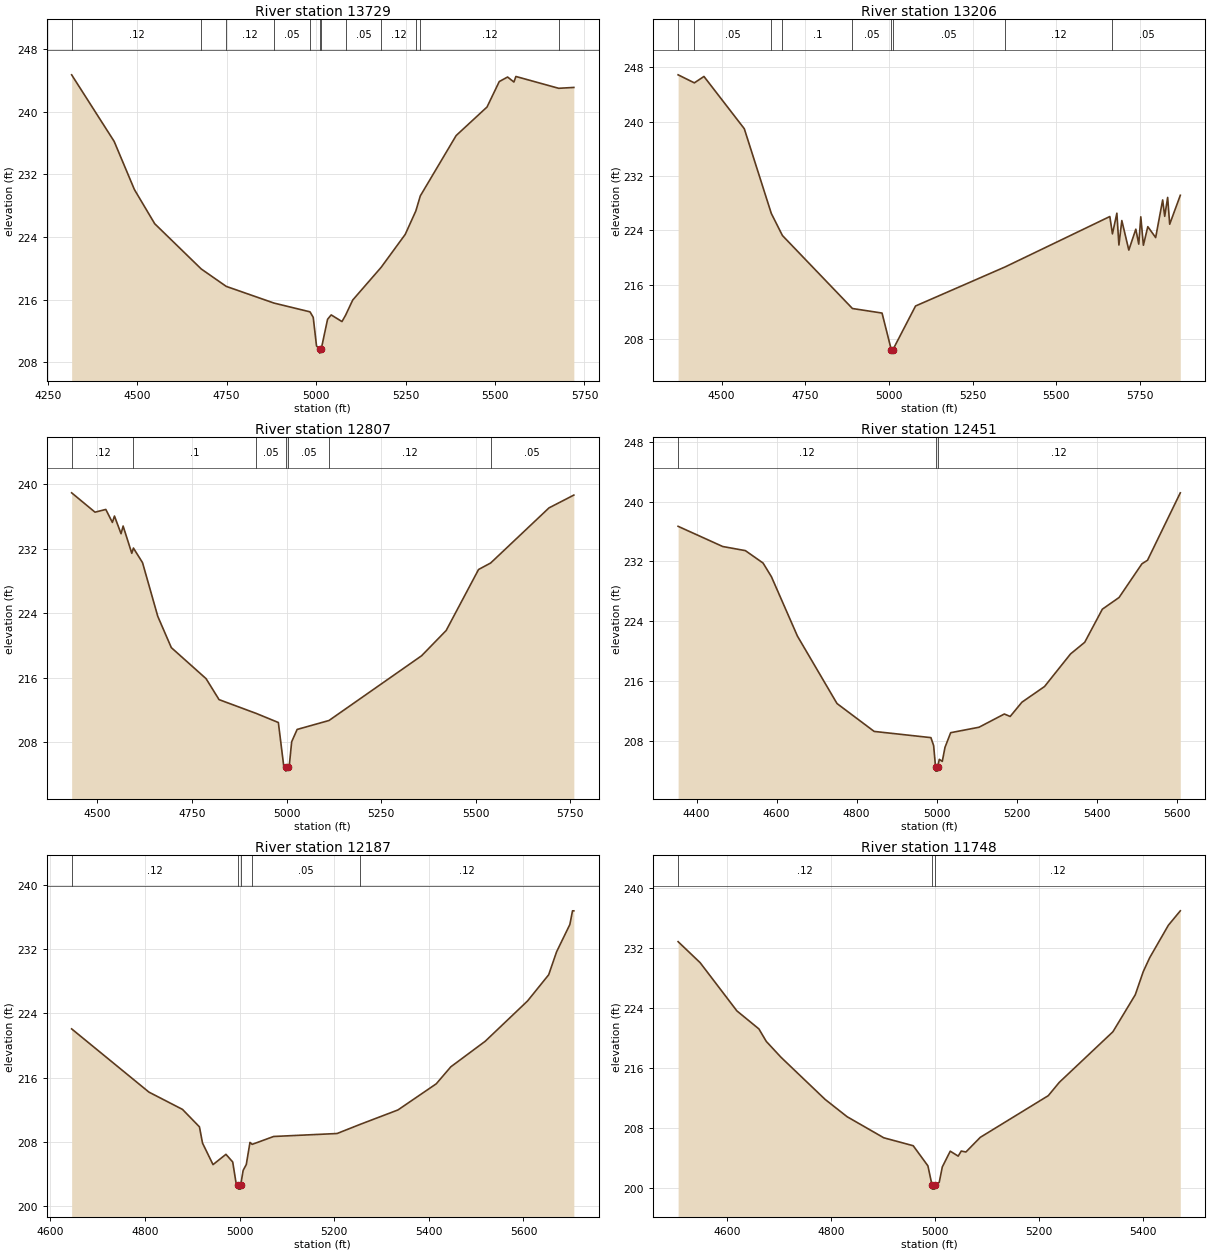
Type RM Length L Ch R = 1,13729,523,523,523
BEGIN DESCRIPTION:
Mapping XS 2348c4c5
END DESCRIPTION:
XS GIS Cut Line= 4
      2556390.27     13584055.40      2556059.51     13584524.18
      2556085.56     13584808.04      2556306.91     13585305.44
#Sta/Elev= 30
  4317.1  244.72  4435.9  236.22  4492.5  230.07  4549.2  225.71  4679.3  219.93
  4749.1  217.71  4882.5  215.58  4983.1  214.46  4992.1  213.76  5001.3  210.11
  5009.9  209.69  5010.2  209.19  5014.4  209.69  5032.2  213.51  5042.3  214.07
  5072.4  213.22  5082.3  214.01  5102.5  215.97  5182.0  220.15  5249.2  224.35
  5278.8  227.34  5291.3  229.26  5391.5  236.97  5477.7  240.61  5511.9  243.86
  5535.2  244.44  5552.9  243.80  5558.4  244.51  5677.9  243.00  5720.3  243.11
#Mann=12,-1,0
  4317.1    0.12       0  4679.3    0.05       0  4749.1    0.12       0
  4882.5    0.05       0  4983.1    0.12       0  5009.9    0.05       0
  5014.4    0.12       0  5082.3    0.05       0  5182.0    0.12       0
  5278.8    0.05       0  5291.3    0.12       0  5677.9    0.05       0
Bank Sta=5009.9,5014.4
Exp/Cntr=0.3,0.1

Type RM Length L Ch R = 1,13206,399,399,399
BEGIN DESCRIPTION:
Mapping XS 91a8b363
END DESCRIPTION:
XS GIS Cut Line= 4
      2555666.28     13583998.15      2555616.81     13584524.18
      2555624.62     13584774.18      2556038.68     13585365.32
#Sta/Elev= 30
  4370.0  246.87  4418.5  245.69  4447.2  246.63  4567.7  238.95  4648.4  226.49
  4681.6  223.25  4890.7  212.52  4979.2  211.85  5006.8  206.46  5007.2  205.96
  5011.6  206.46  5079.3  212.89  5346.8  218.63  5659.7  226.04  5667.5  223.49
  5680.7  226.53  5686.8  221.85  5695.5  225.45  5716.4  221.11  5737.3  224.18
  5746.1  221.98  5752.2  226.00  5759.9  221.82  5773.1  224.55  5796.6  222.95
  5817.5  228.48  5823.6  226.07  5832.4  228.85  5838.5  224.91  5870.2  229.16
#Mann=9,-1,0
  4370.0    0.12       0  4418.5    0.05       0  4648.4    0.12       0
  4681.6     0.1       0  4890.7    0.05       0  5006.8    0.05       0
  5011.6    0.05       0  5346.8    0.12       0  5667.5    0.05       0
Bank Sta=5006.8,5011.6
Exp/Cntr=0.3,0.1

Type RM Length L Ch R = 1,12807,356,356,356
BEGIN DESCRIPTION:
Mapping XS d290f98e
END DESCRIPTION:
XS GIS Cut Line= 4
      2555023.05     13584255.94      2555171.49     13584576.27
      2555392.85     13584854.91      2555757.42     13585354.90
#Sta/Elev= 30
  4431.9  238.96  4493.7  236.56  4522.2  236.90  4539.6  235.29  4545.1  236.08
  4562.5  233.89  4568.0  234.84  4590.9  231.46  4595.2  232.11  4619.3  230.30
  4659.6  223.64  4695.4  219.76  4787.3  215.91  4821.6  213.31  4920.3  211.59
  4978.4  210.47  4992.8  205.00  4998.0  204.94  4998.3  204.44  5002.9  204.94
  5007.2  205.09  5013.6  208.08  5028.0  209.61  5112.3  210.72  5357.1  218.75
  5422.0  221.88  5507.7  229.45  5539.8  230.26  5693.9  237.09  5759.6  238.68
#Mann=7,-1,0
  4431.9    0.12       0  4595.2     0.1       0  4920.3    0.05       0
  4998.0    0.05       0  5002.9    0.05       0  5112.3    0.12       0
  5539.8    0.05       0
Bank Sta=4998,5002.9
Exp/Cntr=0.3,0.1

Type RM Length L Ch R = 1,12451,264,264,264
BEGIN DESCRIPTION:
Mapping XS 8955c51e
END DESCRIPTION:
XS GIS Cut Line= 4
      2554713.16     13584532.00      2554968.37     13584888.77
      2555241.81     13585138.77      2555602.58     13585400.91
#Sta/Elev= 30
  4354.0  236.68  4465.5  233.98  4522.1  233.43  4566.3  231.77  4587.2  229.94
  4652.3  221.99  4751.1  212.98  4844.0  209.25  4985.8  208.42  4992.6  207.36
  4997.5  204.44  4997.9  203.94  5002.1  203.94  5002.5  204.44  5006.8  205.52
  5014.2  205.24  5021.0  207.12  5035.2  209.08  5106.1  209.81  5169.3  211.58
  5183.9  211.25  5213.3  213.16  5269.7  215.25  5334.7  219.61  5370.2  221.17
  5414.3  225.60  5456.0  227.16  5513.2  231.67  5527.1  232.14  5609.1  241.16
#Mann=3,-1,0
  4354.0    0.12       0  4997.5    0.05       0  5002.5    0.12       0
Bank Sta=4997.5,5002.5
Exp/Cntr=0.3,0.1

Type RM Length L Ch R = 1,12187,439,439,439
BEGIN DESCRIPTION:
CRITTENOON HOLLOW 25.0
END DESCRIPTION:
XS GIS Cut Line= 3
      2554674.99     13584874.98      2554925.00     13585175.00
      2555525.04     13585475.02
#Sta/Elev= 30
  4645.0  222.06  4808.4  214.19  4879.3  212.04  4915.1  209.87  4921.6  207.85
  4943.8  205.17  4971.1  206.45  4985.4  205.50  4993.2  202.62  4997.2  202.62
  4997.6  202.12  5001.8  202.12  5002.2  202.62  5007.5  204.46  5014.1  205.18
  5021.9  207.93  5026.6  207.69  5071.9  208.67  5206.0  209.04  5254.4  210.17
  5334.6  211.97  5415.7  215.23  5446.4  217.34  5519.1  220.52  5608.5  225.53
  5653.2  228.79  5670.0  231.66  5698.0  235.05  5703.6  236.75  5706.4  236.75
#Mann=5,-1,0
  4645.0    0.12       0  4997.2    0.05       0  5002.2    0.12       0
  5026.6    0.05       0  5254.4    0.12       0
Bank Sta=4997.2,5002.2
Exp/Cntr=0.3,0.1

Type RM Length L Ch R = 1,11748,446,446,446
BEGIN DESCRIPTION:
CRITTENOON HOLLOW 24.0
END DESCRIPTION:
XS GIS Cut Line= 3
      2554325.03     13585125.03      2554675.00     13585475.00
      2554924.99     13585874.98
#Sta/Elev= 30
  4505.0  232.87  4547.4  230.06  4618.1  223.62  4660.5  221.21  4674.7  219.54
  4702.9  217.43  4787.8  211.80  4830.2  209.48  4900.9  206.66  4957.5  205.60
  4985.8  202.91  4993.8  200.30  4994.2  199.80  4998.6  199.80  4998.9  200.30
  5007.6  200.71  5013.5  202.76  5028.8  204.87  5044.1  204.21  5050.0  204.89
  5058.9  204.76  5086.6  206.72  5217.5  212.29  5238.7  214.07  5341.9  220.83
  5384.9  225.77  5400.3  228.87  5412.7  230.73  5448.6  235.06  5471.6  236.99
#Mann=3,-1,0
  4505.0    0.12       0  4993.8    0.05       0  4998.9    0.12       0
Bank Sta=4993.8,4998.9
Exp/Cntr=0.3,0.1

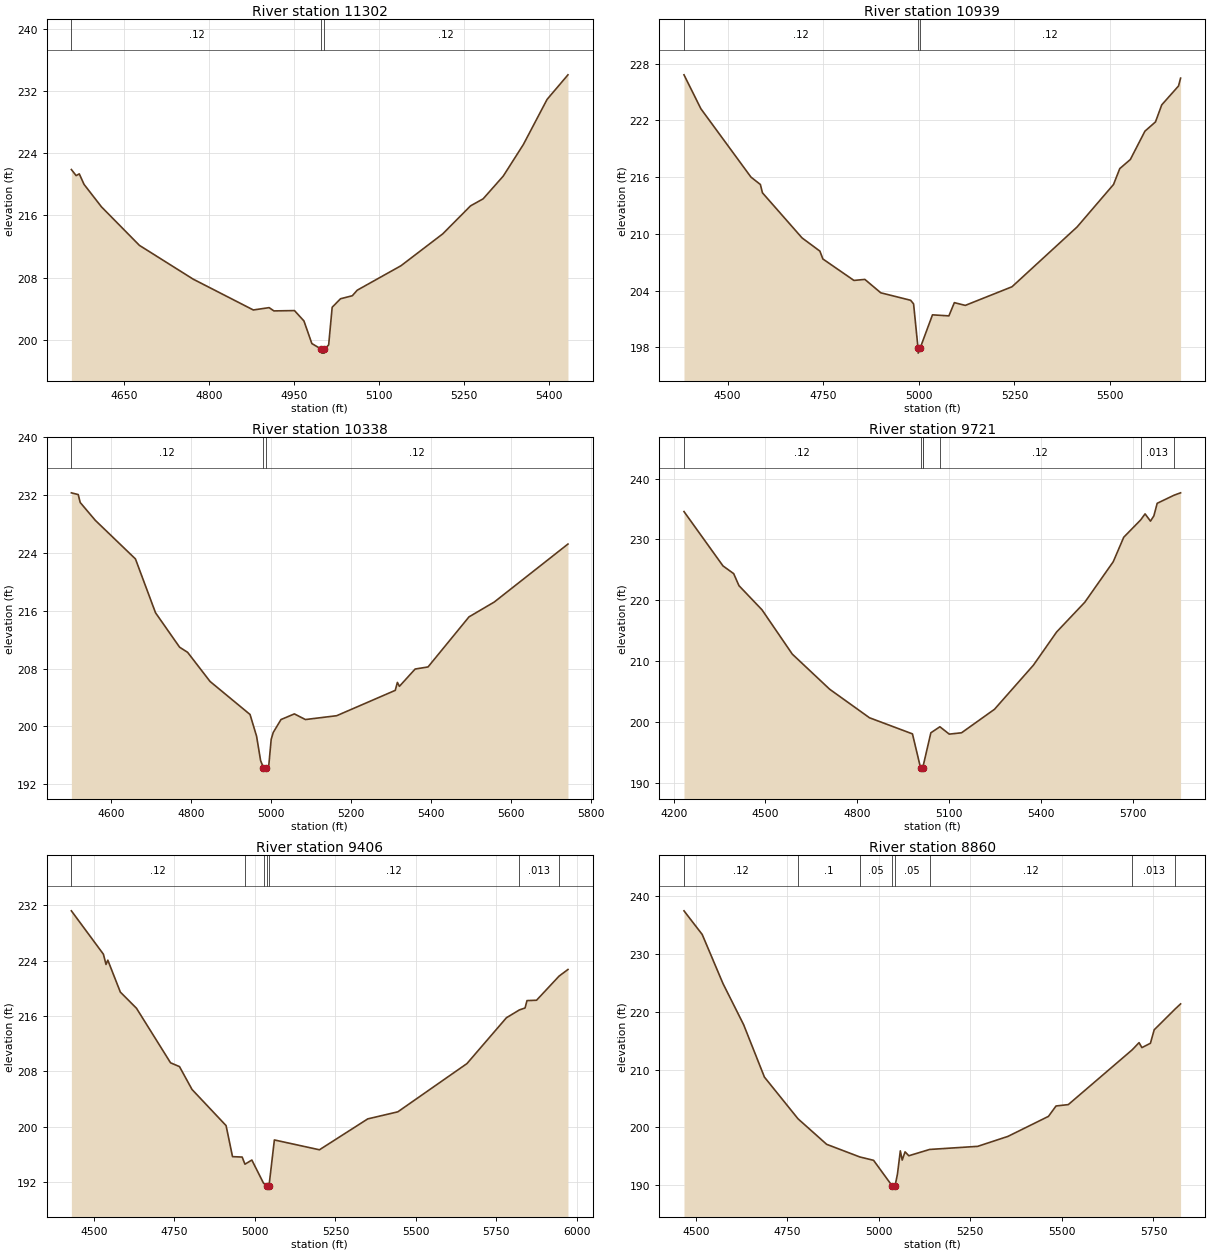
Type RM Length L Ch R = 1,11302,363,363,363
BEGIN DESCRIPTION:
CRITTENOON HOLLOW 23.0
END DESCRIPTION:
XS GIS Cut Line= 3
      2554174.98     13585374.96      2554375.00     13585775.00
      2554725.02     13586025.01
#Sta/Elev= 30
  4556.3  221.91  4564.7  221.13  4570.3  221.35  4578.7  220.00  4609.5  217.11
  4676.5  212.16  4771.6  207.81  4877.8  203.85  4905.7  204.15  4914.1  203.73
  4950.5  203.77  4967.2  202.44  4981.2  199.53  4998.2  198.80  4998.6  198.30
  5003.0  198.30  5003.4  198.80  5010.9  199.36  5017.1  204.20  5031.8  205.29
  5052.7  205.68  5061.3  206.39  5138.7  209.54  5212.5  213.64  5261.6  217.24
  5283.8  218.14  5319.4  221.07  5355.0  225.14  5396.8  230.93  5433.7  234.09
#Mann=3,-1,0
  4556.3    0.12       0  4998.2    0.05       0  5003.4    0.12       0
Bank Sta=4998.2,5003.4
Exp/Cntr=0.3,0.1

Type RM Length L Ch R = 1,10939,601,601,601
BEGIN DESCRIPTION:
Mapping XS 69da1cbb
END DESCRIPTION:
XS GIS Cut Line= 4
      2553767.85     13585263.77      2553916.29     13585646.58
      2554179.31     13585956.48      2554603.78     13586183.03
#Sta/Elev= 30
  4386.2  226.83  4430.4  223.24  4561.3  216.01  4585.9  215.23  4591.3  214.35
  4694.8  209.58  4741.5  208.18  4749.3  207.35  4830.5  205.08  4859.0  205.19
  4900.7  203.77  4978.7  202.98  4986.4  202.60  4998.1  197.89  4998.5  197.39
  5003.3  197.89  5035.8  201.44  5078.7  201.33  5093.0  202.73  5121.6  202.44
  5243.7  204.41  5413.7  210.73  5509.1  215.23  5525.4  216.91  5553.0  217.87
  5591.2  220.87  5618.8  221.85  5635.1  223.65  5679.0  225.65  5684.4  226.48
#Mann=3,-1,0
  4386.2    0.12       0  4998.1    0.05       0  5003.3    0.12       0
Bank Sta=4998.1,5003.3
Exp/Cntr=0.3,0.1

Type RM Length L Ch R = 1,10338,617,617,617
BEGIN DESCRIPTION:
Mapping XS 01654895
END DESCRIPTION:
XS GIS Cut Line= 4
      2553538.68     13585365.37      2553562.12     13585711.68
      2553629.83     13586076.27      2553739.20     13586586.65
#Sta/Elev= 30
  4501.7  232.33  4518.8  232.09  4523.8  230.99  4561.5  228.52  4661.7  223.18
  4711.8  215.73  4772.0  210.96  4792.0  210.25  4848.0  206.22  4947.8  201.65
  4964.1  198.65  4974.2  195.27  4981.1  194.31  4981.6  193.81  4987.8  194.31
  4994.6  194.59  5000.6  198.21  5005.7  199.16  5025.1  200.95  5058.5  201.73
  5086.1  200.95  5164.1  201.48  5310.4  204.99  5315.7  206.09  5320.8  205.55
  5360.0  207.94  5392.2  208.23  5494.5  215.16  5557.7  217.22  5741.6  225.24
#Mann=3,-1,0
  4501.7    0.12       0  4981.1    0.05       0  4987.8    0.12       0
Bank Sta=4981.1,4987.8
Exp/Cntr=0.3,0.1

Type RM Length L Ch R = 1,9721,315,315,315
BEGIN DESCRIPTION:
Mapping XS c8aabcb3
END DESCRIPTION:
XS GIS Cut Line= 4
      2553202.75     13585206.47      2552978.79     13585714.29
      2553007.43     13586141.37      2553267.86     13586724.73
#Sta/Elev= 30
  4233.8  234.58  4361.2  225.65  4396.1  224.38  4413.3  222.41  4488.7  218.43
  4587.5  211.16  4709.5  205.39  4839.6  200.70  4980.0  198.05  5006.6  192.43
  5007.1  191.93  5013.4  192.43  5014.9  192.77  5040.1  198.23  5069.6  199.22
  5100.2  198.01  5140.3  198.23  5247.9  202.09  5375.0  209.34  5450.8  214.79
  5543.0  219.69  5635.8  226.34  5670.0  230.36  5725.2  233.20  5739.7  234.20
  5757.4  233.01  5768.4  233.87  5779.3  235.94  5834.5  237.27  5855.7  237.66
#Mann=7,-1,0
  4233.8    0.12       0  5006.6    0.05       0  5013.4    0.12       0
  5014.9     0.1       0  5069.6    0.12       0  5725.2   0.013       0
  5834.5    0.12       0
Bank Sta=5006.6,5013.4
Exp/Cntr=0.3,0.1

Type RM Length L Ch R = 1,9406,546,546,546
BEGIN DESCRIPTION:
Mapping XS e17eb137
END DESCRIPTION:
XS GIS Cut Line= 4
      2552879.83     13585326.26      2552705.35     13585670.02
      2552702.74     13586250.75      2553035.36     13586721.08
#Sta/Elev= 30
  4429.9  231.18  4529.4  224.92  4537.5  223.44  4543.1  224.06  4582.0  219.45
  4632.2  217.11  4737.9  209.24  4765.7  208.69  4804.6  205.39  4910.4  200.17
  4930.4  195.69  4960.4  195.63  4969.0  194.60  4990.4  195.20  5026.8  191.85
  5037.0  191.50  5037.5  191.00  5043.8  191.50  5060.4  198.10  5200.4  196.68
  5350.4  201.14  5443.8  202.16  5658.6  209.13  5781.0  215.74  5821.6  216.88
  5838.9  217.15  5845.0  218.22  5874.6  218.27  5944.7  221.76  5972.2  222.71
#Mann=7,-1,0
  4429.9    0.12       0  4969.0     0.1       0  5026.8    0.12       0
  5037.0    0.05       0  5043.8    0.12       0  5821.6   0.013       0
  5944.7    0.12       0
Bank Sta=5037,5043.8
Exp/Cntr=0.3,0.1

Type RM Length L Ch R = 1,8860,416,416,416
BEGIN DESCRIPTION:
CRITTENOON HOLLOW 18.0
END DESCRIPTION:
XS GIS Cut Line= 3
      2552574.99     13585375.01      2552225.00     13585775.00
      2552425.00     13586574.98
#Sta/Elev= 30
  4468.0  237.50  4517.8  233.40  4574.3  224.93  4630.8  217.79  4687.7  208.70
  4779.4  201.48  4857.6  197.06  4947.8  194.88  4985.7  194.29  5037.2  189.80
  5037.7  189.30  5044.2  189.80  5051.0  191.93  5058.8  195.93  5063.9  194.33
  5071.7  195.76  5082.0  195.08  5138.7  196.17  5270.1  196.71  5352.5  198.43
  5463.3  201.90  5484.0  203.70  5517.5  203.94  5692.0  213.43  5710.7  214.67
  5718.5  213.81  5741.7  214.56  5752.0  216.89  5809.3  220.50  5824.1  221.38
#Mann=8,-1,0
  4468.0    0.12       0  4779.4     0.1       0  4947.8    0.05       0
  5037.2    0.05       0  5044.2    0.05       0  5138.7    0.12       0
  5692.0   0.013       0  5809.3    0.12       0
Bank Sta=5037.2,5044.2
Exp/Cntr=0.3,0.1

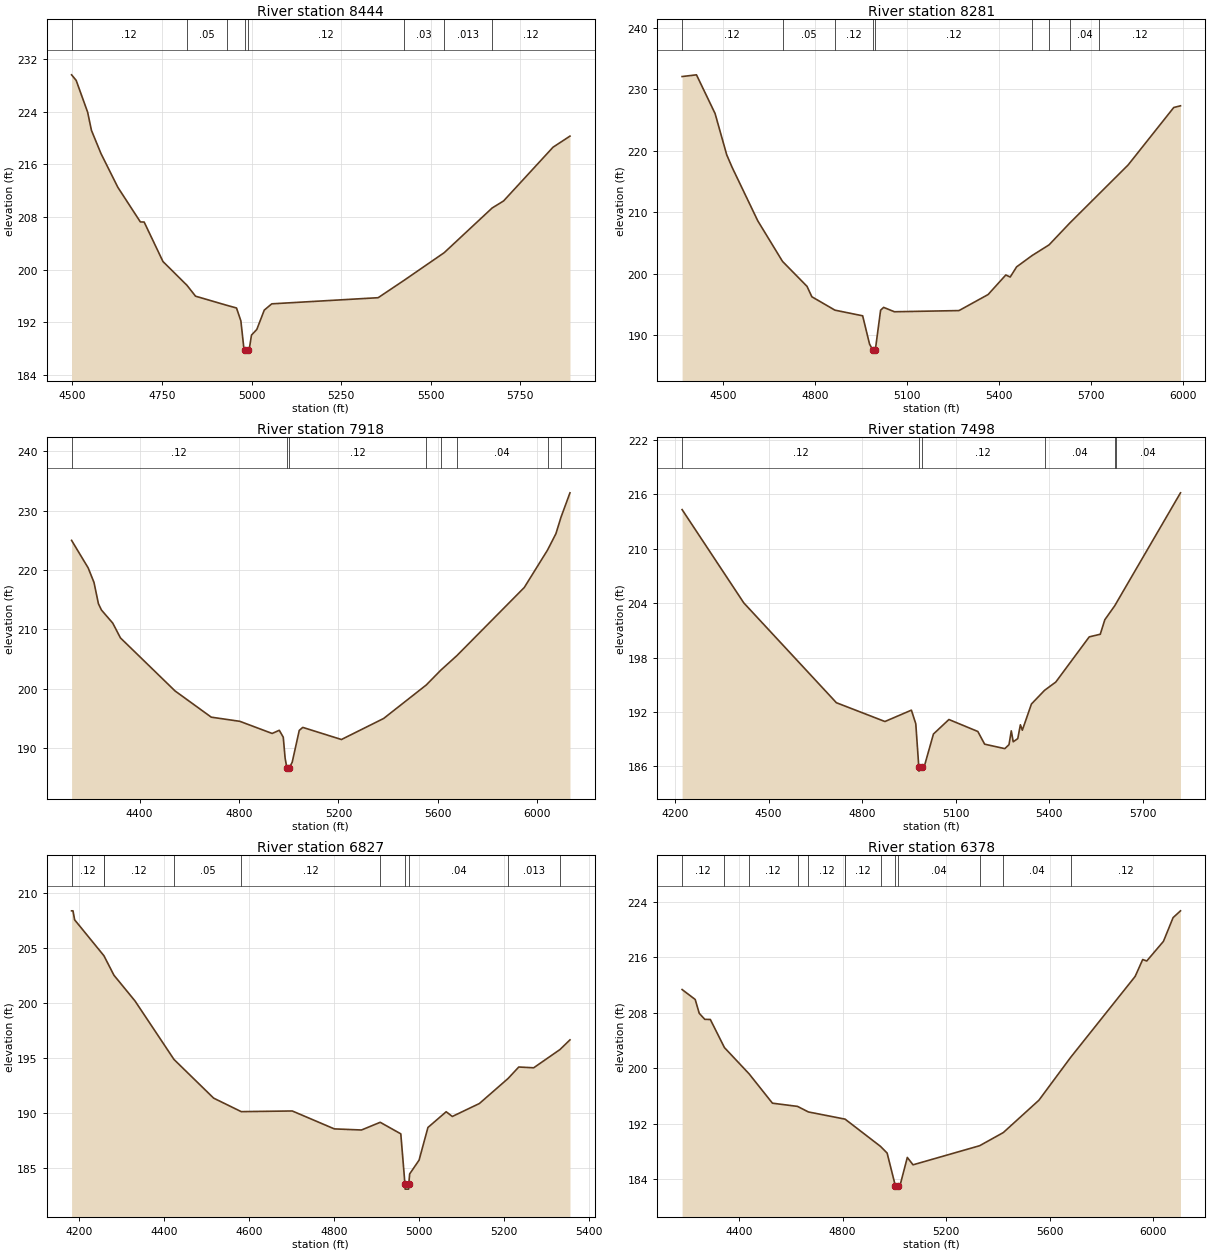
Type RM Length L Ch R = 1,8444,163,163,163
BEGIN DESCRIPTION:
Mapping XS b6402a46
END DESCRIPTION:
XS GIS Cut Line= 4
      2552387.66     13585284.59      2552056.91     13585391.37
      2551718.37     13585630.96      2551395.44     13586170.03
#Sta/Elev= 30
  4497.8  229.58  4510.6  228.74  4542.6  223.91  4553.2  221.16  4580.0  217.61
  4626.7  212.53  4689.7  207.26  4700.3  207.24  4752.8  201.25  4819.8  197.64
  4843.7  195.99  4930.7  194.61  4958.0  194.20  4970.2  192.24  4978.9  187.91
  4980.8  187.85  4981.3  187.35  4989.3  187.85  4993.7  188.00  4999.8  190.09
  5014.6  190.94  5035.5  193.88  5056.4  194.83  5353.2  195.76  5425.7  198.40
  5537.5  202.59  5671.3  209.37  5703.2  210.44  5841.3  218.60  5888.5  220.28
#Mann=8,-1,0
  4497.8    0.12       0  4819.8    0.05       0  4930.7    0.12       0
  4980.8    0.05       0  4989.3    0.12       0  5425.7    0.03       0
  5537.5   0.013       0  5671.3    0.12       0
Bank Sta=4980.8,4989.3
Exp/Cntr=0.3,0.1

Type RM Length L Ch R = 1,8281,363,363,363
BEGIN DESCRIPTION:
Mapping XS 4c5254ae
END DESCRIPTION:
XS GIS Cut Line= 4
      2552408.52     13585172.61      2552036.08     13585235.12
      2551520.45     13585539.81      2551116.78     13586047.65
#Sta/Elev= 30
  4365.8  232.09  4412.7  232.37  4473.3  226.08  4511.3  219.36  4528.9  217.32
  4612.7  208.61  4693.3  202.02  4773.2  197.96  4788.9  196.27  4864.2  194.09
  4954.6  193.17  4977.0  188.59  4987.4  187.60  4987.9  187.10  4995.9  187.60
  5013.1  194.08  5023.0  194.54  5058.3  193.83  5268.7  194.02  5363.7  196.63
  5421.4  199.81  5435.8  199.48  5456.6  201.13  5506.7  202.96  5562.5  204.71
  5629.8  208.25  5726.3  213.04  5820.2  217.70  5969.2  227.06  5991.1  227.33
#Mann=9,-1,0
  4365.8    0.12       0  4693.3    0.05       0  4864.2    0.12       0
  4987.4    0.05       0  4995.9    0.12       0  5506.7    0.03       0
  5562.5   0.013       0  5629.8    0.04       0  5726.3    0.12       0
Bank Sta=4987.4,4995.9
Exp/Cntr=0.3,0.1

Type RM Length L Ch R = 1,7918,420,420,420
BEGIN DESCRIPTION:
CRITTENOON HOLLOW 16.0
END DESCRIPTION:
XS GIS Cut Line= 3
      2551975.01     13584274.98      2551625.00     13585075.00
      2550825.00     13585875.00
#Sta/Elev= 30
  4126.8  224.99  4193.5  220.36  4216.9  217.92  4234.8  214.33  4246.9  213.27
  4292.5  211.06  4323.3  208.58  4542.8  199.66  4688.6  195.24  4803.6  194.54
  4933.4  192.50  4962.2  193.03  4978.2  191.87  4985.6  188.38  4992.8  186.66
  4993.3  186.16  5001.9  186.66  5014.2  187.66  5042.5  193.01  5056.6  193.52
  5212.2  191.48  5381.9  195.02  5553.2  200.65  5611.7  203.14  5676.4  205.59
  5947.6  217.06  6041.0  223.35  6074.8  226.11  6095.5  228.91  6131.4  232.99
#Mann=8,-1,0
  4126.8    0.12       0  4992.8    0.05       0  5001.9    0.12       0
  5553.2    0.03       0  5611.7   0.013       0  5676.4    0.04       0
  6041.0    0.12       0  6095.5    0.05       0
Bank Sta=4992.8,5001.9
Exp/Cntr=0.3,0.1

Type RM Length L Ch R = 1,7498,671,671,671
BEGIN DESCRIPTION:
CRITTENOON HOLLOW 15.0
END DESCRIPTION:
XS GIS Cut Line= 3
      2551824.98     13584325.02      2551225.00     13584925.00
      2550775.00     13585525.00
#Sta/Elev= 30
  4222.8  214.31  4420.8  204.02  4717.7  193.02  4873.3  190.95  4958.2  192.20
  4972.3  190.70  4981.9  185.98  4982.4  185.48  4991.0  185.98  5000.6  186.12
  5028.9  189.57  5078.6  191.17  5171.3  189.85  5193.2  188.45  5257.8  187.96
  5271.3  188.40  5278.6  189.92  5284.8  188.71  5299.4  189.07  5307.8  190.59
  5314.0  189.99  5343.2  192.88  5385.4  194.39  5421.3  195.30  5528.6  200.28
  5564.0  200.57  5578.6  202.17  5610.2  203.70  5612.9  203.86  5821.3  216.16
#Mann=6,-1,0
  4222.8    0.12       0  4981.9    0.05       0  4991.0    0.12       0
  5385.4    0.04       0  5610.2   0.013       0  5612.9    0.04       0
Bank Sta=4981.9,4991
Exp/Cntr=0.3,0.1

Type RM Length L Ch R = 1,6827,449,449,449
BEGIN DESCRIPTION:
CRITTENOON HOLLOW 14.0
END DESCRIPTION:
XS GIS Cut Line= 3
      2551275.02     13584224.97      2550775.00     13584825.00
      2550524.98     13585125.02
#Sta/Elev= 30
  4183.1  208.39  4186.4  208.39  4190.3  207.57  4258.6  204.33  4259.2  204.30
  4282.7  202.53  4332.2  200.19  4423.8  194.87  4517.0  191.35  4581.9  190.12
  4701.9  190.18  4800.8  188.55  4864.6  188.45  4908.6  189.15  4957.0  188.10
  4966.7  183.57  4967.2  183.07  4975.4  183.07  4975.9  183.57  4977.8  184.45
  5000.0  185.71  5020.8  188.68  5063.7  190.11  5078.1  189.68  5141.8  190.86
  5209.3  193.14  5234.3  194.18  5269.4  194.11  5331.2  195.77  5354.7  196.65
#Mann=10,-1,0
  4183.1    0.12       0  4258.6    0.05       0  4259.2    0.12       0
  4423.8    0.05       0  4581.9    0.12       0  4908.6    0.04       0
  4966.7    0.04       0  4975.9    0.04       0  5209.3   0.013       0
  5331.2    0.04       0
Bank Sta=4966.7,4975.9
Exp/Cntr=0.3,0.1

Type RM Length L Ch R = 1,6378,557,557,557
BEGIN DESCRIPTION:
Mapping XS c3fdb109
END DESCRIPTION:
XS GIS Cut Line= 4
      2551174.95     13584045.03      2550584.69     13584395.71
      2550199.27     13584854.05      2549876.36     13585406.12
#Sta/Elev= 30
  4180.0  211.33  4230.6  209.90  4246.2  207.91  4267.6  207.04  4289.0  207.02
  4343.6  202.97  4438.9  199.19  4528.9  194.97  4625.7  194.51  4667.9  193.71
  4807.4  192.69  4809.0  192.69  4946.4  188.75  4971.9  187.79  5003.5  183.10
  5004.0  182.60  5013.1  183.10  5022.4  183.23  5049.9  187.16  5072.0  186.10
  5329.3  188.85  5420.6  190.74  5558.2  195.40  5680.8  201.57  5929.9  213.22
  5959.0  215.65  5974.7  215.44  6039.2  218.27  6076.4  221.68  6105.0  222.66
#Mann=13,-1,0
  4180.0    0.12       0  4343.6    0.05       0  4438.9    0.12       0
  4625.7    0.05       0  4667.9    0.12       0  4807.4    0.05       0
  4809.0    0.12       0  4946.4    0.04       0  5003.5    0.04       0
  5013.1    0.04       0  5329.3   0.013       0  5420.6    0.04       0
  5680.8    0.12       0
Bank Sta=5003.5,5013.1
Exp/Cntr=0.3,0.1

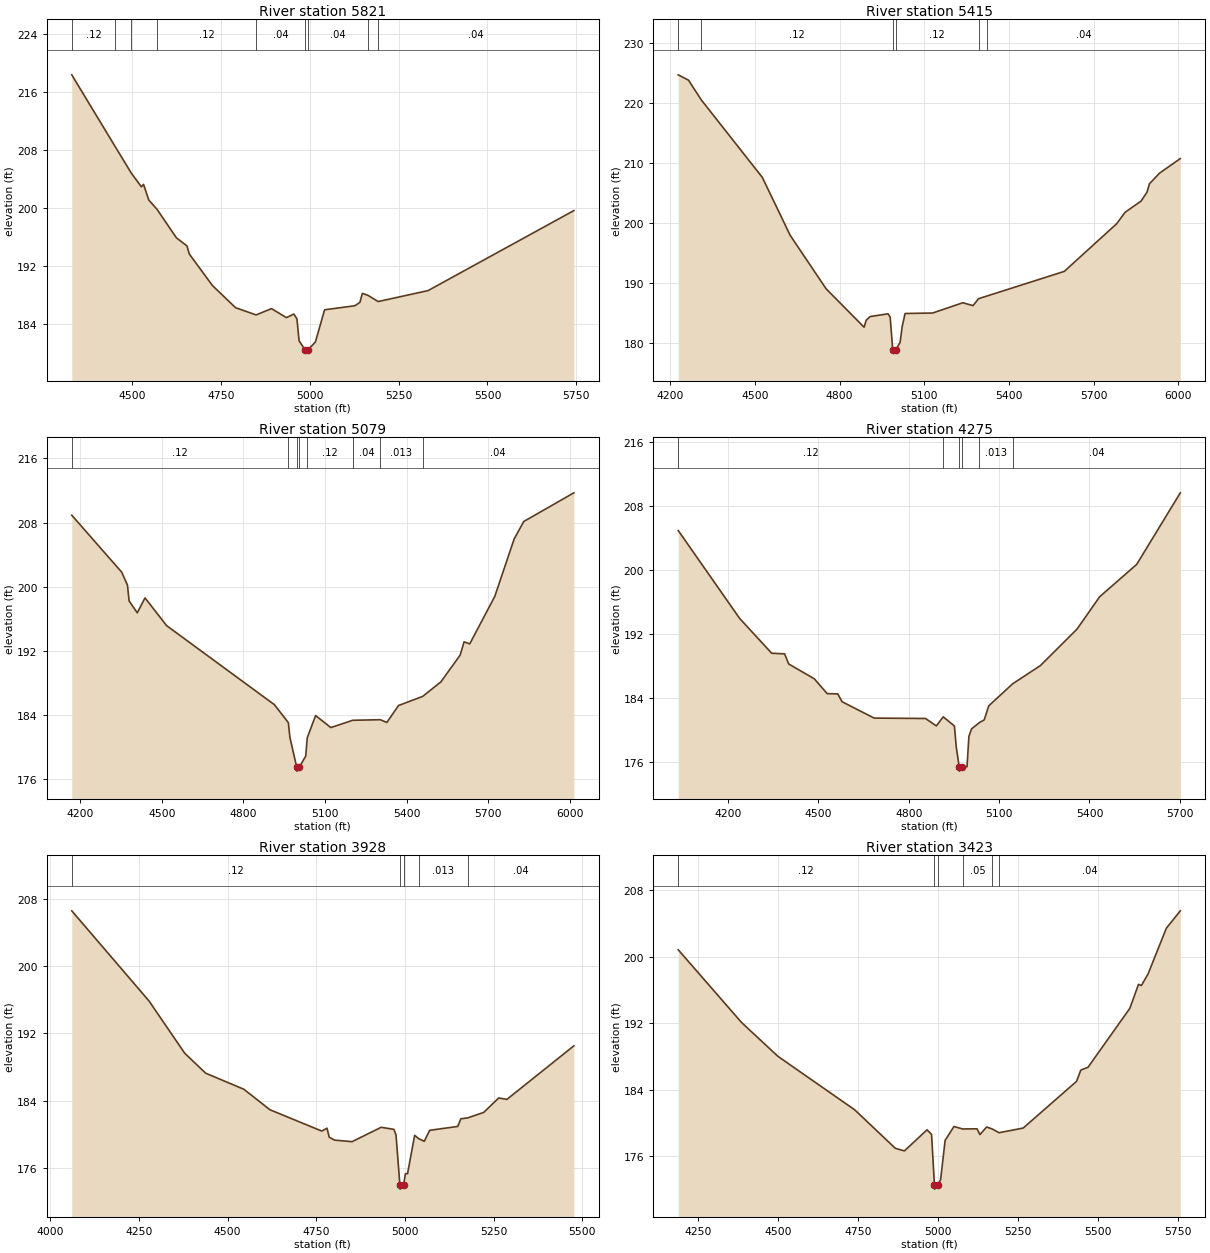
Type RM Length L Ch R = 1,5821,406,406,406
BEGIN DESCRIPTION:
Mapping XS 421cecb8
END DESCRIPTION:
XS GIS Cut Line= 3
      2550445.80     13583864.46      2550053.44     13584423.49
      2549509.18     13584908.82
#Sta/Elev= 30
  4330.7  218.38  4452.3  208.50  4498.6  204.76  4526.5  202.90  4532.6  203.24
  4547.4  201.07  4570.4  199.80  4625.0  195.85  4654.6  194.74  4661.2  193.62
  4726.1  189.27  4791.4  186.19  4849.2  185.19  4892.5  186.06  4934.4  184.82
  4955.3  185.31  4964.0  184.66  4970.1  181.62  4986.2  180.41  4986.7  179.91
  4995.9  180.41  5016.0  181.45  5041.8  185.90  5127.1  186.46  5141.3  186.94
  5148.0  188.17  5163.9  187.90  5192.5  187.04  5332.7  188.55  5742.9  199.61
#Mann=9,-1,0
  4330.7    0.12       0  4452.3    0.05       0  4498.6   0.013       0
  4570.4    0.12       0  4849.2    0.04       0  4986.2    0.04       0
  4995.9    0.04       0  5163.9   0.013       0  5192.5    0.04       0
Bank Sta=4986.2,4995.9
Exp/Cntr=0.3,0.1

Type RM Length L Ch R = 1,5415,336,336,336
BEGIN DESCRIPTION:
Mapping XS bbd33494
END DESCRIPTION:
XS GIS Cut Line= 3
      2550317.34     13583576.25      2549765.24     13584163.07
      2548968.14     13584721.05
#Sta/Elev= 30
  4228.1  224.72  4264.4  223.83  4310.0  220.52  4526.1  207.58  4624.8  197.90
  4752.3  188.96  4886.6  182.56  4893.9  183.72  4908.1  184.34  4971.6  184.80
  4978.9  184.25  4988.1  178.73  4988.6  178.23  4997.9  178.73  5014.1  180.04
  5021.4  182.64  5031.7  184.85  5129.4  184.93  5236.6  186.65  5272.4  186.16
  5291.9  187.32  5321.9  187.77  5595.6  191.88  5781.5  199.85  5811.2  201.76
  5867.9  203.63  5888.8  205.12  5897.5  206.52  5933.3  208.30  6006.8  210.73
#Mann=6,-1,0
  4228.1   0.013       0  4310.0    0.12       0  4988.1    0.04       0
  4997.9    0.12       0  5291.9   0.013       0  5321.9    0.04       0
Bank Sta=4988.1,4997.9
Exp/Cntr=0.3,0.1

Type RM Length L Ch R = 1,5079,804,804,804
BEGIN DESCRIPTION:
Mapping XS a364b1e7
END DESCRIPTION:
XS GIS Cut Line= 3
      2550015.25     13583211.67      2549522.19     13583944.32
      2548886.75     13584666.57
#Sta/Elev= 30
  4169.5  208.92  4353.2  201.81  4374.2  200.20  4380.2  198.23  4410.2  196.75
  4438.7  198.61  4518.1  195.15  4914.0  185.30  4965.4  183.06  4971.0  181.24
  4996.1  177.51  4996.6  177.01  5005.9  177.51  5029.3  178.89  5034.9  181.17
  5065.6  183.94  5121.6  182.44  5201.8  183.35  5303.3  183.42  5327.5  183.08
  5370.2  185.19  5458.7  186.32  5525.8  188.13  5596.9  191.48  5611.2  193.13
  5632.1  192.88  5724.1  198.80  5795.2  205.95  5830.4  208.13  6014.6  211.71
#Mann=8,-1,0
  4169.5    0.12       0  4965.4    0.05       0  4996.1    0.05       0
  5005.9    0.05       0  5034.9    0.12       0  5201.8    0.04       0
  5303.3   0.013       0  5458.7    0.04       0
Bank Sta=4996.1,5005.9
Exp/Cntr=0.3,0.1

Type RM Length L Ch R = 1,4275,347,347,347
BEGIN DESCRIPTION:
Mapping XS 348c5d19
END DESCRIPTION:
XS GIS Cut Line= 4
      2549404.15     13583176.94      2548928.44     13583729.05
      2548699.27     13584069.32      2548536.54     13584571.37
#Sta/Elev= 30
  4034.8  204.96  4238.6  193.96  4345.0  189.60  4387.8  189.52  4401.8  188.25
  4486.5  186.40  4529.3  184.54  4564.4  184.51  4578.7  183.53  4685.1  181.48
  4855.7  181.43  4891.7  180.50  4914.5  181.64  4951.6  180.49  4957.7  177.91
  4967.6  175.34  4968.1  174.84  4977.8  175.34  4993.5  175.39  4999.8  179.19
  5008.6  180.13  5034.8  180.92  5050.7  181.26  5065.6  183.01  5145.3  185.78
  5237.0  188.05  5358.5  192.61  5434.1  196.68  5556.8  200.72  5701.6  209.68
#Mann=6,-1,0
  4034.8    0.12       0  4914.5    0.04       0  4967.6    0.04       0
  4977.8    0.04       0  5034.8   0.013       0  5145.3    0.04       0
Bank Sta=4967.6,4977.8
Exp/Cntr=0.3,0.1

Type RM Length L Ch R = 1,3928,505,505,505
BEGIN DESCRIPTION:
CRITTENOON HOLLOW 8.0
END DESCRIPTION:
XS GIS Cut Line= 3
      2549025.01     13582924.98      2548525.00     13583725.00
      2548275.01     13584124.98
#Sta/Elev= 30
  4061.0  206.59  4278.6  195.87  4379.4  189.64  4438.4  187.27  4546.3  185.35
  4619.4  182.92  4765.6  180.38  4780.4  180.72  4786.8  179.64  4802.2  179.30
  4851.1  179.12  4933.1  180.83  4969.0  180.58  4974.9  179.92  4985.8  173.97
  4986.3  173.47  4996.0  173.97  5001.5  175.31  5007.4  175.31  5027.4  179.87
  5038.4  179.49  5054.5  179.16  5069.9  180.47  5148.9  180.93  5157.7  181.84
  5177.0  181.95  5222.0  182.60  5264.4  184.32  5287.4  184.15  5476.1  190.52
#Mann=5,-1,0
  4061.0    0.12       0  4985.8    0.05       0  4996.0    0.12       0
  5038.4   0.013       0  5177.0    0.04       0
Bank Sta=4985.8,4996
Exp/Cntr=0.3,0.1

Type RM Length L Ch R = 1,3423,478,478,478
BEGIN DESCRIPTION:
CRITTENOON HOLLOW 7.0
END DESCRIPTION:
XS GIS Cut Line= 3
      2548775.02     13582774.98      2548175.00     13583375.00
      2547774.98     13583975.03
#Sta/Elev= 30
  4186.8  200.84  4384.8  192.09  4498.0  188.03  4738.4  181.58  4865.7  176.94
  4893.9  176.63  4964.6  179.17  4978.8  178.62  4987.8  172.53  4988.3  172.03
  4998.1  172.53  5007.1  173.17  5021.2  177.90  5048.9  179.57  5076.2  179.27
  5121.0  179.29  5130.0  178.59  5151.0  179.51  5167.8  179.28  5189.7  178.82
  5265.2  179.38  5432.0  185.00  5445.5  186.36  5468.0  186.70  5598.7  193.79
  5625.8  196.68  5634.8  196.54  5655.8  197.94  5712.9  203.44  5756.5  205.53
#Mann=6,-1,0
  4186.8    0.12       0  4987.8    0.05       0  4998.1    0.12       0
  5076.2    0.05       0  5167.8   0.013       0  5189.7    0.04       0
Bank Sta=4987.8,4998.1
Exp/Cntr=0.3,0.1