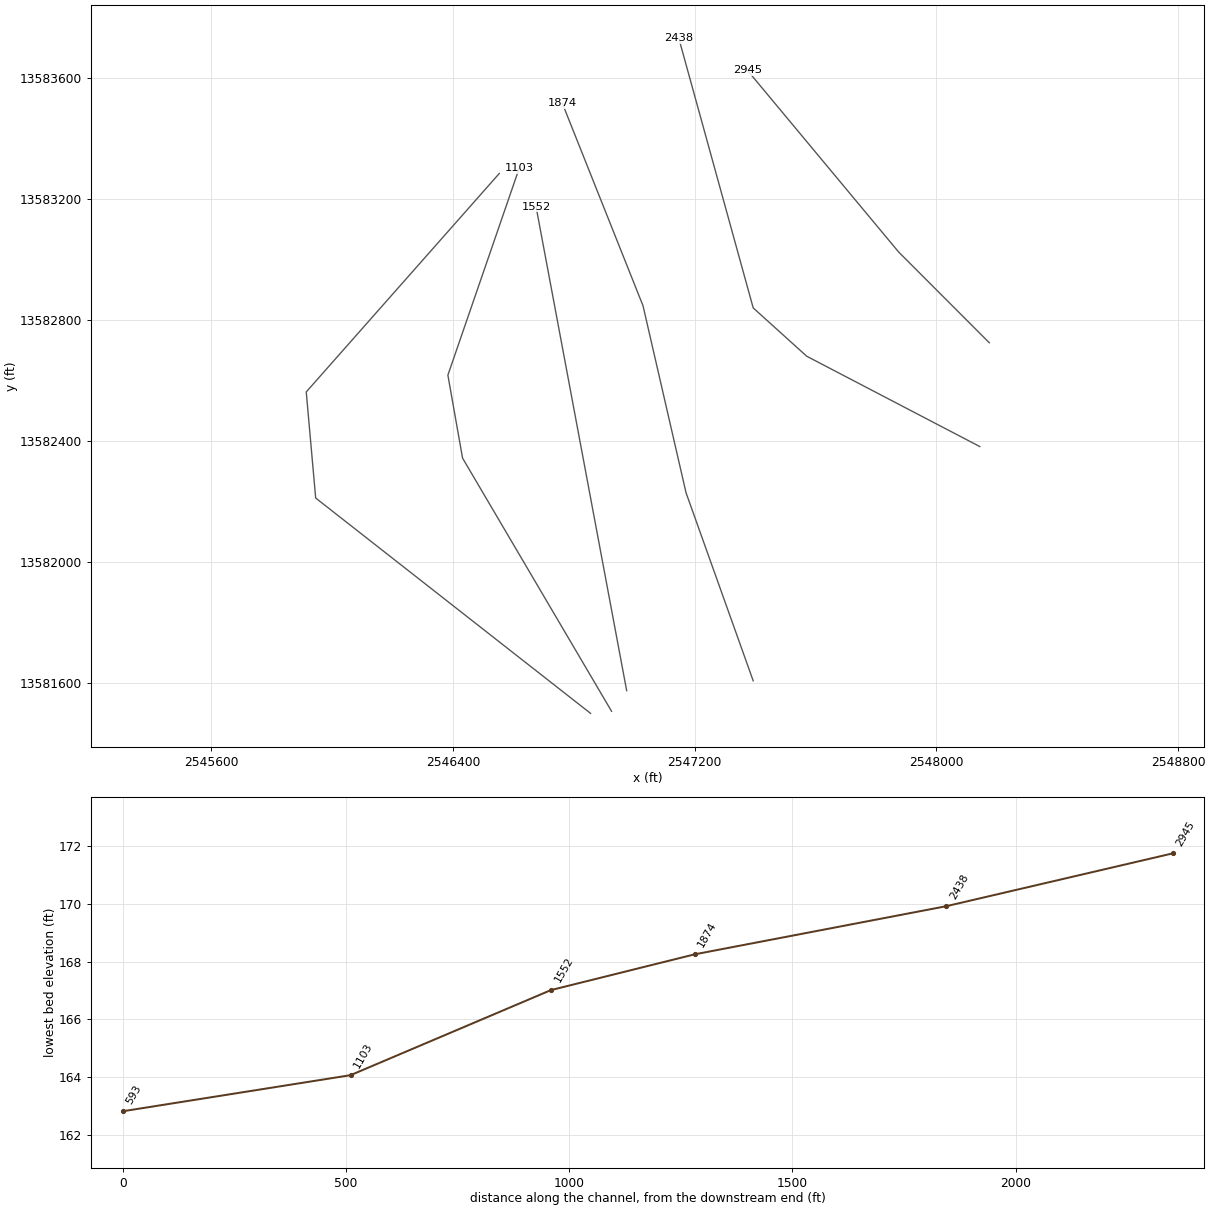
HEC-RAS study CRITTENOON HOLLOW.prj: CRITTENOON HOLLOW Base Level Engineering

--- CRITTENOON HOLLOW.g01 (geometry) --- (continued)

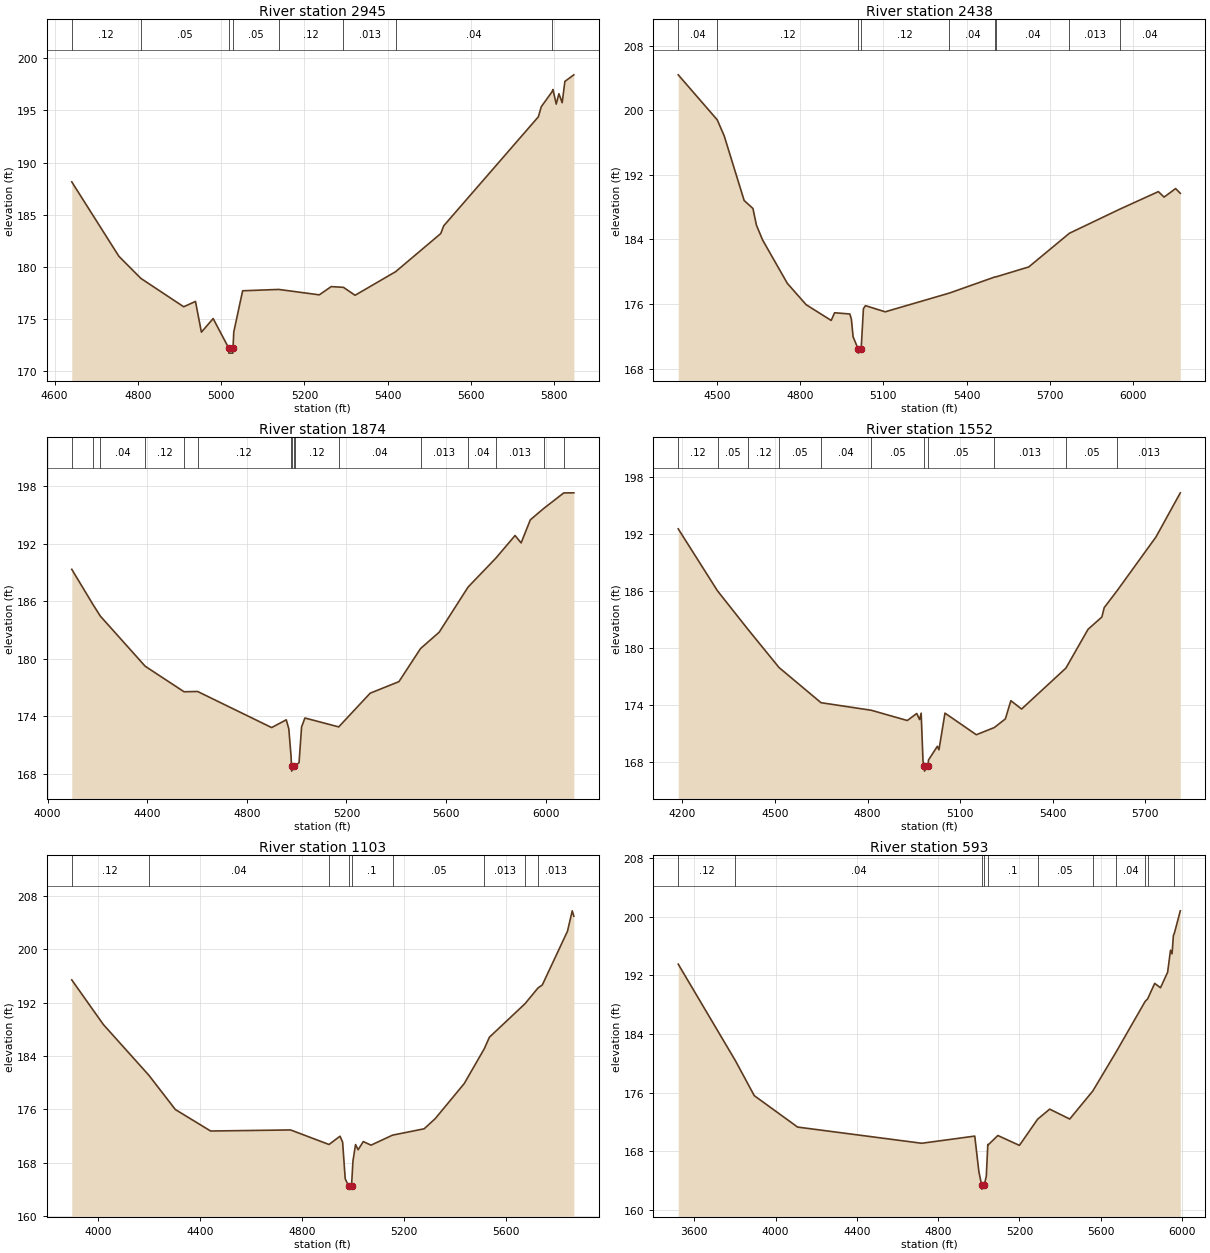
Type RM Length L Ch R = 1,2945,507,507,507
BEGIN DESCRIPTION:
CRITTENOON HOLLOW 6.0
END DESCRIPTION:
XS GIS Cut Line= 3
      2548175.02     13582724.98      2547875.00     13583025.00
      2547375.01     13583624.98
#Sta/Elev= 30
  4641.4  188.15  4754.6  181.02  4807.2  178.91  4910.1  176.19  4938.4  176.70
  4952.6  173.76  4980.8  175.06  5018.0  172.25  5018.5  171.75  5028.0  171.75
  5028.5  172.25  5030.3  173.77  5051.6  177.72  5138.2  177.85  5235.6  177.33
  5264.2  178.12  5293.6  178.05  5321.5  177.29  5418.9  179.55  5527.2  183.20
  5534.3  183.94  5761.5  194.38  5768.6  195.35  5794.2  196.77  5796.6  196.99
  5804.4  195.60  5810.9  196.59  5818.7  195.73  5825.2  197.77  5846.7  198.40
#Mann=8,-1,0
  4641.4    0.12       0  4807.2    0.05       0  5018.0    0.05       0
  5028.5    0.05       0  5138.2    0.12       0  5293.6   0.013       0
  5418.9    0.04       0  5794.2   0.013       0
Bank Sta=5018,5028.5
Exp/Cntr=0.3,0.1

Type RM Length L Ch R = 1,2438,564,564,564
BEGIN DESCRIPTION:
Mapping XS 070bf345
END DESCRIPTION:
XS GIS Cut Line= 4
      2548143.70     13582381.83      2547570.80     13582680.43
      2547393.72     13582840.16      2547147.54     13583731.25
#Sta/Elev= 30
  4361.1  204.40  4501.7  198.82  4526.7  196.84  4598.6  188.83  4630.3  187.84
  4642.8  185.78  4664.9  183.95  4754.3  178.56  4822.0  175.92  4912.2  173.97
  4924.4  174.92  4979.4  174.77  4985.0  174.13  4991.1  171.95  5009.5  170.42
  5010.0  169.92  5020.1  170.42  5028.4  175.43  5035.8  175.80  5106.8  175.04
  5338.0  177.36  5503.9  179.38  5505.2  179.36  5624.1  180.60  5770.5  184.77
  5952.3  187.76  6091.0  189.93  6111.7  189.25  6153.2  190.31  6170.1  189.72
#Mann=9,-1,0
  4361.1    0.04       0  4501.7    0.12       0  5009.5    0.05       0
  5020.1    0.12       0  5338.0    0.04       0  5503.9   0.013       0
  5505.2    0.04       0  5770.5   0.013       0  5952.3    0.04       0
Bank Sta=5009.5,5020.1
Exp/Cntr=0.3,0.1

Type RM Length L Ch R = 1,1874,322,322,322
BEGIN DESCRIPTION:
Mapping XS 18324db0
END DESCRIPTION:
XS GIS Cut Line= 4
      2547393.72     13581607.51      2547171.49     13582229.05
      2547029.13     13582847.10      2546761.78     13583517.23
#Sta/Elev= 30
  4097.3  189.33  4182.8  185.64  4211.8  184.45  4391.9  179.21  4548.2  176.54
  4602.5  176.57  4899.8  172.80  4958.5  173.61  4968.7  172.67  4977.9  169.75
  4979.6  168.75  4980.1  168.25  4991.3  168.75  4993.4  168.78  5009.8  169.13
  5020.0  172.87  5033.4  173.80  5169.1  172.87  5295.3  176.39  5410.9  177.60
  5497.5  181.05  5572.4  182.76  5688.6  187.48  5799.7  190.49  5877.1  192.86
  5901.4  192.09  5938.4  194.50  5991.3  195.67  6072.6  197.31  6113.1  197.32
#Mann=16,-1,0
  4097.3    0.04       0  4182.8    0.12       0  4211.8    0.04       0
  4391.9    0.12       0  4548.2    0.05       0  4602.5    0.12       0
  4977.9    0.05       0  4979.6    0.05       0  4991.3    0.05       0
  4993.4    0.12       0  5169.1    0.04       0  5497.5   0.013       0
  5688.6    0.04       0  5799.7   0.013       0  5991.3    0.04       0
  6072.6    0.05       0
Bank Sta=4979.6,4991.3
Exp/Cntr=0.3,0.1

Type RM Length L Ch R = 1,1552,449,449,449
BEGIN DESCRIPTION:
CRITTENOON HOLLOW 3.0
END DESCRIPTION:
XS GIS Cut Line= 3
      2546974.99     13581575.04      2546825.00     13582375.00
      2546675.01     13583174.96
#Sta/Elev= 30
  4186.2  192.57  4313.5  186.03  4413.2  181.93  4513.0  177.94  4649.1  174.23
  4812.2  173.43  4928.9  172.35  4959.4  173.09  4968.7  172.45  4973.8  173.12
  4979.8  168.05  4984.0  167.51  4984.5  167.01  4995.8  167.51  4997.6  168.19
  5026.4  169.63  5031.5  169.26  5051.0  173.13  5152.7  170.85  5211.1  171.61
  5246.8  172.52  5264.6  174.44  5299.4  173.56  5443.1  177.88  5514.8  181.97
  5559.7  183.27  5567.3  184.26  5610.1  186.09  5735.2  191.72  5814.0  196.37
#Mann=11,-1,0
  4186.2    0.12       0  4313.5    0.05       0  4413.2    0.12       0
  4513.0    0.05       0  4649.1    0.04       0  4812.2    0.05       0
  4984.0    0.05       0  4995.8    0.05       0  5211.1   0.013       0
  5443.1    0.05       0  5610.1   0.013       0
Bank Sta=4984,4995.8
Exp/Cntr=0.3,0.1

Type RM Length L Ch R = 1,1103,510,510,510
BEGIN DESCRIPTION:
Mapping XS c1a33620
END DESCRIPTION:
XS GIS Cut Line= 4
      2546924.99     13581506.78      2546431.91     13582343.63
      2546383.30     13582617.93      2546619.08     13583301.00
#Sta/Elev= 30
  3895.0  195.42  4018.9  188.74  4198.1  181.12  4301.9  175.99  4440.5  172.77
  4754.8  172.93  4905.6  170.75  4948.9  171.99  4959.1  171.10  4969.3  165.61
  4982.3  164.56  4982.8  164.06  4994.1  164.56  4999.7  168.28  5009.9  170.74
  5020.0  169.96  5040.3  171.19  5070.8  170.65  5155.1  172.15  5279.3  173.10
  5322.8  174.62  5437.0  179.89  5515.9  185.12  5535.8  186.83  5675.7  191.85
  5726.5  194.20  5743.6  194.66  5842.5  202.71  5861.2  205.77  5867.5  204.97
#Mann=9,-1,0
  3895.0    0.12       0  4198.1    0.04       0  4905.6     0.1       0
  4982.3    0.05       0  4994.1     0.1       0  5155.1    0.05       0
  5515.9   0.013       0  5675.7    0.04       0  5726.5   0.013       0
Bank Sta=4982.3,4994.1
Exp/Cntr=0.3,0.1

Type RM Length L Ch R = 1,593,0,0,0
BEGIN DESCRIPTION:
CRITTENOON HOLLOW 1.0
END DESCRIPTION:
XS GIS Cut Line= 4
      2546855.53     13581499.88      2545945.80     13582211.68
      2545914.55     13582562.38      2546553.41     13583284.57
#Sta/Elev= 30
  3520.7  193.52  3802.0  180.35  3895.0  175.57  4108.4  171.28  4719.3  169.07
  4980.3  170.05  5000.4  165.23  5014.6  163.31  5015.1  162.81  5026.4  163.31
  5037.1  164.56  5044.6  168.91  5046.4  168.85  5094.0  170.13  5200.2  168.78
  5289.5  172.35  5349.1  173.73  5447.8  172.38  5561.5  176.21  5675.0  181.48
  5818.9  188.43  5831.3  188.78  5866.0  190.90  5894.5  190.30  5929.6  192.41
  5943.8  195.42  5951.4  194.93  5958.0  197.42  5962.8  197.74  5992.1  200.80
#Mann=11,-1,0
  3520.7    0.12       0  3802.0    0.04       0  5014.6    0.04       0
  5026.4    0.04       0  5046.4     0.1       0  5289.5    0.05       0
  5561.5   0.013       0  5675.0    0.04       0  5818.9   0.013       0
  5831.3    0.04       0  5962.8   0.013       0
Bank Sta=5014.6,5026.4
Exp/Cntr=0.3,0.1

Chan Stop Cuts=-1