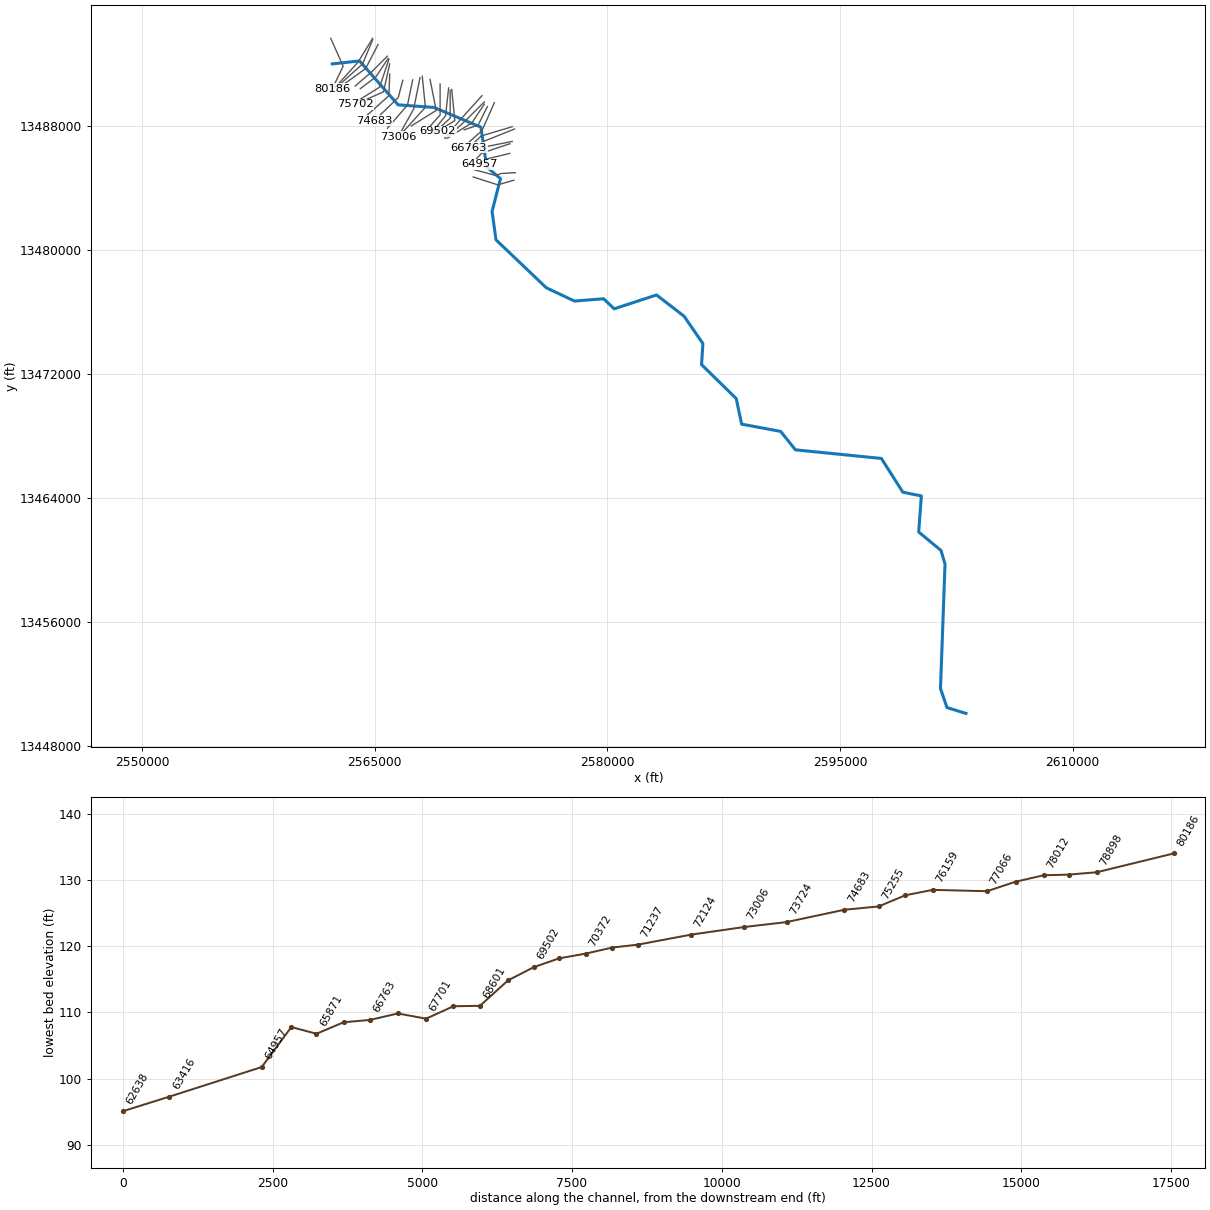
--- DRY CREEK.prj (project) ---

Proj Title=DRY CREEK Base Level Engineering
Current Plan=p01
Default Exp/Contr=0.3,0.1
English Units
Geom File=g01
Flow File=f01
Plan File=p01
Y Axis Title=Elevation
X Axis Title(PF)=Main Channel Distance
X Axis Title(XS)=Station
BEGIN DESCRIPTION:
DRY CREEK
END DESCRIPTION:
DSS Export Rating Curves= 0
DSS Export Rating Curve Sorted= 0
DSS Export Volume Flow Curves= 0
DXF OffsetX= 0
DXF OffsetY= 0
DXF ScaleX= 1
DXF ScaleY= 10

--- DRY CREEK.p01 (plan) ---

Plan Title=Multiple Run
Short Identifier=Multiple
Geom File=g01
Flow File=f01
Subcritical Flow
K Sum by GR= 0
Std Step Tol= 0.01
Critical Tol= 0.01
Num of Std Step Trials= 20
Max Error Tol= 0.3
Flow Tol Ratio= 0.001
Split Flow NTrial= 30
Split Flow Tol= 0.02
Split Flow Ratio= 0.02
Log Output Level= 0
Friction Slope Method= 1
Unsteady Friction Slope Method= 2
Unsteady Bridges Friction Slope Method= 1
Parabolic Critical Depth
Global Vel Dist=  1 , 1 , 1
Global Log Level= 0
CheckData=True
Encroach Param= -1, 0, 0, 0
BEGIN DESCRIPTION:
Multiple Run
END DESCRIPTION:

--- DRY CREEK.f01 (steady flow) ---

Flow Title=Multiple
Program Version=4.10
Number of Profiles= 7
Profile Names=10-year,25-year,50-year,1pct_min,100-year,1pct_plu,500-year
River Rch & RM=DRY CREEK,Reach-1         ,80186
     928    1488    1991    1287    2567    5122    4220
River Rch & RM=DRY CREEK,Reach-1         ,77545
    1076    1738    2334    1513    3020    6025    4998
River Rch & RM=DRY CREEK,Reach-1         ,74683
    1369    2233    3021    1970    3931    7843    6585
River Rch & RM=DRY CREEK,Reach-1         ,70809
    1444    2361    3197    2088    4166    8312    6997
River Rch & RM=DRY CREEK,Reach-1         ,68601
    1703    2806    3822    2508    5005    9986    8491
River Rch & RM=DRY CREEK,Reach-1         ,66763
    2416    4045    5568    3690    7362   14689   12735
River Rch & RM=DRY CREEK,Reach-1         ,59829
    2796    4707    6503    4324    8627   17212   15020
River Rch & RM=DRY CREEK,Reach-1         ,55703
    2867    4824    6662    4426    8831   17621   15357
River Rch & RM=DRY CREEK,Reach-1         ,53745
    3645    6190    8603    5749   11471   22888   20181
River Rch & RM=DRY CREEK,Reach-1         ,50337
    3811    6455    8955    5974   11920   23784   20888
River Rch & RM=DRY CREEK,Reach-1         ,46124
    4344    7379   10257    6852   13672   27280   24026
River Rch & RM=DRY CREEK,Reach-1         ,37406
    4830    8239   11487    7696   15356   30639   27136
River Rch & RM=DRY CREEK,Reach-1         ,35270
    4919    8379   11671    7810   15584   31094   27475
River Rch & RM=DRY CREEK,Reach-1         ,28551
    4986    8492   11828    7915   15792   31508   27835
River Rch & RM=DRY CREEK,Reach-1         ,24620
    5052    8597   11966    8001   15963   31851   28093
Boundary for River Rch & Prof#=DRY CREEK,Reach-1         , 1
Up Type= 0
Dn Type= 3
Dn Slope=0.0014
Boundary for River Rch & Prof#=DRY CREEK,Reach-1         , 2
Up Type= 0
Dn Type= 3
Dn Slope=0.0014
Boundary for River Rch & Prof#=DRY CREEK,Reach-1         , 3
Up Type= 0
Dn Type= 3
Dn Slope=0.0014
Boundary for River Rch & Prof#=DRY CREEK,Reach-1         , 4
Up Type= 0
Dn Type= 3
Dn Slope=0.0014
Boundary for River Rch & Prof#=DRY CREEK,Reach-1         , 5
Up Type= 0
Dn Type= 3
Dn Slope=0.0014
Boundary for River Rch & Prof#=DRY CREEK,Reach-1         , 6
Up Type= 0
Dn Type= 3
Dn Slope=0.0014
Boundary for River Rch & Prof#=DRY CREEK,Reach-1         , 7
Up Type= 0
Dn Type= 3
Dn Slope=0.0014
DSS Import GetInterval= 0
DSS Import GetPeak= 0
DSS Import FillOption= 0

--- DRY CREEK.g01 (geometry) ---

Geom Title=Existing Conditions
Program Version=4.10

River Reach=DRY CREEK       ,Reach-1
Reach XY= 30
        2562275.       13491975.      2564031.95     13492166.15
      2566518.33      13489334.3      2568828.58      13489167.5
      2571855.39      13487895.2      2572228.47      13485326.5
      2573117.67      13484574.9      2572575.06     13482454.97
      2572828.62      13480626.5      2576068.81     13477532.81
       2577885.5      13476676.2      2579769.35     13476823.03
      2580445.05     13476174.79      2583177.53     13477069.24
      2584955.44      13475695.2      2586166.86     13473931.06
      2586078.75     13472576.55      2588313.77     13470385.02
      2588665.17     13468735.47      2591181.67      13468265.7
      2592131.12     13467076.84       2597673.5     13466521.38
      2599055.07     13464344.18      2600248.65     13464101.96
      2600078.61      13461776.5      2601514.83     13460584.68
      2601774.99     13459709.64      2601483.04     13451671.68
      2601901.42     13450447.85        2603125.       13450075.

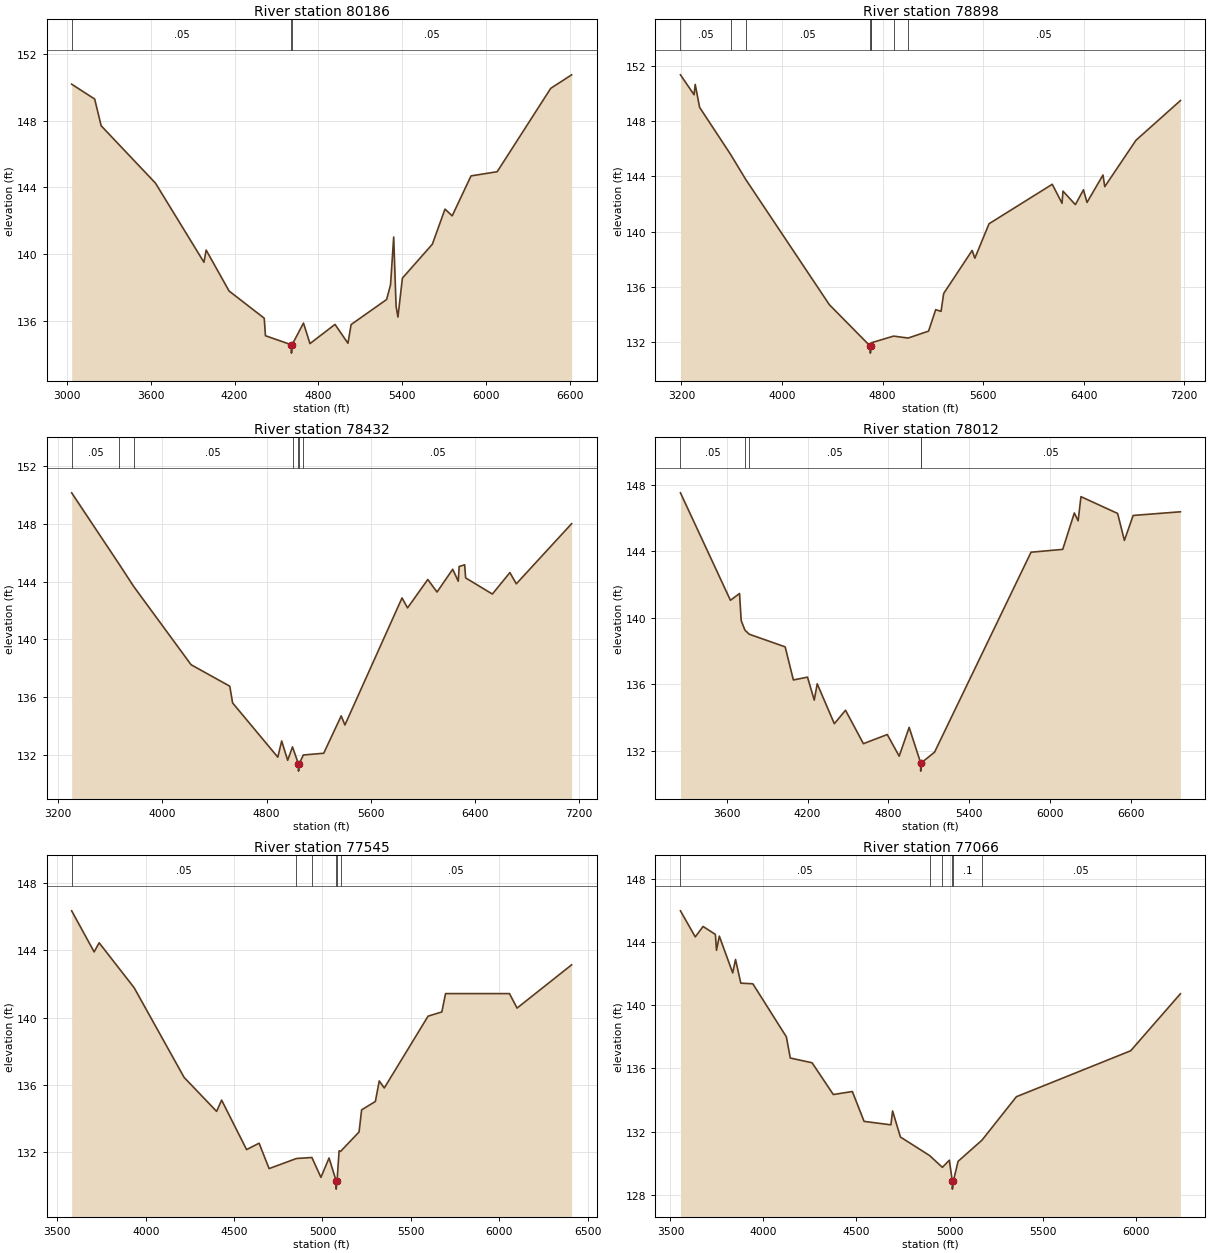
Type RM Length L Ch R = 1 ,80186   ,1288,1288,1288
BEGIN DESCRIPTION:
DRY CREEK 124.0
END DESCRIPTION:
XS GIS Cut Line= 3
      2562175.02     13493624.96        2562975.       13491825.
      2562275.02     13490375.04
#Sta/Elev= 30
  3033.9  150.18  3198.7  149.29  3245.2  147.69  3633.7  144.26  3981.1  139.52
  3996.9  140.25    4161   137.8  4412.7  136.17  4421.6  135.12  4607.3  134.58
  4607.7  134.08    4612  134.58  4693.8  135.88  4740.3  134.65  4919.5   135.8
  5012.1  134.67  5034.8  135.79    5289  137.29  5317.1  138.17  5339.7  141.03
  5356.8  136.89  5370.1  136.24    5402  138.57  5616.5   140.6    5707   142.7
  5758.7   142.3  5893.4  144.69  6080.7  144.94    6464  149.93  6613.7  150.74
#Mann= 3 ,-1 , 0
  3033.9     .05       0  4607.3     .05       0    4612     .05       0
Bank Sta=4607.3,4612
XS Rating Curve= 0 ,0
Exp/Cntr=0.3,0.1

Type RM Length L Ch R = 1 ,78898   ,466,466,466
BEGIN DESCRIPTION:
DRY CREEK 123.0
END DESCRIPTION:
XS GIS Cut Line= 3
      2564874.98     13493624.97        2563925.       13492075.
      2562475.01     13490475.01
#Sta/Elev= 30
  3191.9  151.34  3300.2   149.9  3309.2  150.65  3344.3  148.99  3592.8  145.56
  3710.5  143.79  4376.5  134.73  4702.3  131.73  4702.7  131.23  4707.5  131.73
  4710.6  131.98  4887.2  132.46  5003.2  132.32  5165.6  132.82  5222.4  134.37
    5265  134.25  5285.9  135.54  5512.3  138.65  5533.9  138.09  5646.8  140.58
  6149.6  143.43  6227.3  142.06  6234.8  142.94  6333.4  141.96  6397.7  143.03
    6426  142.12  6553.1   144.1  6567.3  143.26  6815.3  146.61  7169.1  149.48
#Mann= 8 ,-1 , 0
  3191.9     .05       0  3592.8    .035       0  3710.5     .05       0
  4702.3     .05       0  4707.5     .05       0  4710.6    .035       0
  4887.2     .15       0  5003.2     .05       0
Bank Sta=4702.3,4707.5
XS Rating Curve= 0 ,0
Exp/Cntr=0.3,0.1

Type RM Length L Ch R = 1 ,78432   ,420,420,420
BEGIN DESCRIPTION:
DRY CREEK 122.0
END DESCRIPTION:
XS GIS Cut Line= 3
      2564875.01     13493525.02        2564225.       13491975.
      2562624.99     13490524.99
#Sta/Elev= 30
  3302.6  150.17  3669.8  145.19    3778  143.69  4219.8  138.25  4517.1  136.76
  4538.8   135.6  4885.8  131.84  4915.8  132.96  4961.7  131.62  4998.8  132.55
  5044.6  131.37  5045.1  130.87  5049.9  131.37  5082.2  131.99  5238.5  132.11
    5373   134.7  5401.4  134.07    5840  142.88  5882.6  142.19    6038  144.16
    6109  143.29  6229.3  144.87  6271.9  144.04    6279  145.06  6321.2  145.18
  6328.6  144.27  6534.1  143.15  6668.6  144.64  6717.9  143.86  7142.7  148.03
#Mann= 7 ,-1 , 0
  3302.6     .05       0  3669.8    .035       0    3778     .05       0
  4998.8     .15       0  5044.6     .05       0  5049.9     .15       0
  5082.2     .05       0
Bank Sta=5044.6,5049.9
XS Rating Curve= 0 ,0
Exp/Cntr=0.3,0.1

Type RM Length L Ch R = 1 ,78012   ,467,467,467
BEGIN DESCRIPTION:
DRY CREEK 121.0
END DESCRIPTION:
XS GIS Cut Line= 3
      2565224.99     13493224.97        2564425.       13491675.
      2562824.96     13490524.97
#Sta/Elev= 30
  3255.5   147.5  3626.8  141.04  3694.4  141.45  3706.8  139.82  3734.2  139.25
  3766.5     139  4033.5  138.24  4094.4  136.25  4199.5  136.42  4249.5  135.04
  4271.6  136.02  4398.9  133.62  4481.9  134.43  4614.8  132.42  4792.1  132.97
  4880.7  131.67  4954.7   133.4  5040.1  131.27  5040.5  130.77  5045.4  131.27
  5143.4  131.91  5860.3  143.93  6095.8   144.1    6182  146.29  6210.2  145.82
  6231.3  147.27  6503.7  146.26    6554  144.64    6619  146.14  6970.2  146.36
#Mann= 5 ,-1 , 0
  3255.5     .05       0  3734.2    .035       0  3766.5     .05       0
  5040.1     .05       0  5045.4     .05       0
Bank Sta=5040.1,5045.4
XS Rating Curve= 0 ,0
Exp/Cntr=0.3,0.1

Type RM Length L Ch R = 1 ,77545   ,479,479,479
BEGIN DESCRIPTION:
DRY CREEK 120.0
END DESCRIPTION:
XS GIS Cut Line= 3
      2565825.02     13492475.02        2564825.       13491475.
      2563753.93     13490550.23
#Sta/Elev= 30
  3580.8  146.34  3708.1   143.9  3736.4  144.44  3934.4  141.77  4217.2  136.44
  4401.1  134.42  4429.4  135.09  4570.8  132.15  4641.5  132.53  4698.1  131.02
  4852.8  131.62  4940.2  131.68  4991.5   130.5  5037.3  131.65  5077.4   130.3
  5077.8   129.8  5082.7   130.3  5094.3  132.08  5102.5  132.04  5207.3   133.2
  5221.6  134.51  5299.5  135.01  5321.4  136.23  5349.9  135.81  5597.8  140.08
  5675.7  140.33  5696.6  141.42  6058.5  141.42  6101.3  140.56  6410.1  143.13
#Mann= 6 ,-1 , 0
  3580.8     .05       0  4852.8     .07       0  4940.2      .1       0
  5077.4     .05       0  5082.7      .1       0  5102.5     .05       0
Bank Sta=5077.4,5082.7
XS Rating Curve= 0 ,0
Exp/Cntr=0.3,0.1

Type RM Length L Ch R = 1 ,77066   ,907,907,907
BEGIN DESCRIPTION:
DRY CREEK 119.0
END DESCRIPTION:
XS GIS Cut Line= 3
      2565874.98     13492324.97        2565075.       13491125.
      2564079.73     13490376.83
#Sta/Elev= 30
  3553.8  145.98  3633.4  144.33  3675.4  144.99  3741.5  144.49  3747.6  143.48
  3762.6  144.38  3834.7  142.05  3849.7   142.9  3878.3   141.4  3942.9  141.36
  4123.1     138  4144.2  136.66  4261.3  136.36  4375.5  134.35  4477.7  134.54
  4540.8  132.65    4685  132.43    4694  133.31  4736.1  131.66  4892.5  130.49
  4961.7  129.74  4999.1  130.19    5015  128.86  5015.5  128.36  5020.6  128.86
    5046  130.12  5174.5  131.46  5359.4  134.21  5973.8  137.12  6241.1  140.73
#Mann= 6 ,-1 , 0
  3553.8     .05       0  4892.5     .07       0  4961.7      .1       0
    5015     .05       0  5020.6      .1       0  5174.5     .05       0
Bank Sta=5015,5020.6
XS Rating Curve= 0 ,0
Exp/Cntr=0.3,0.1

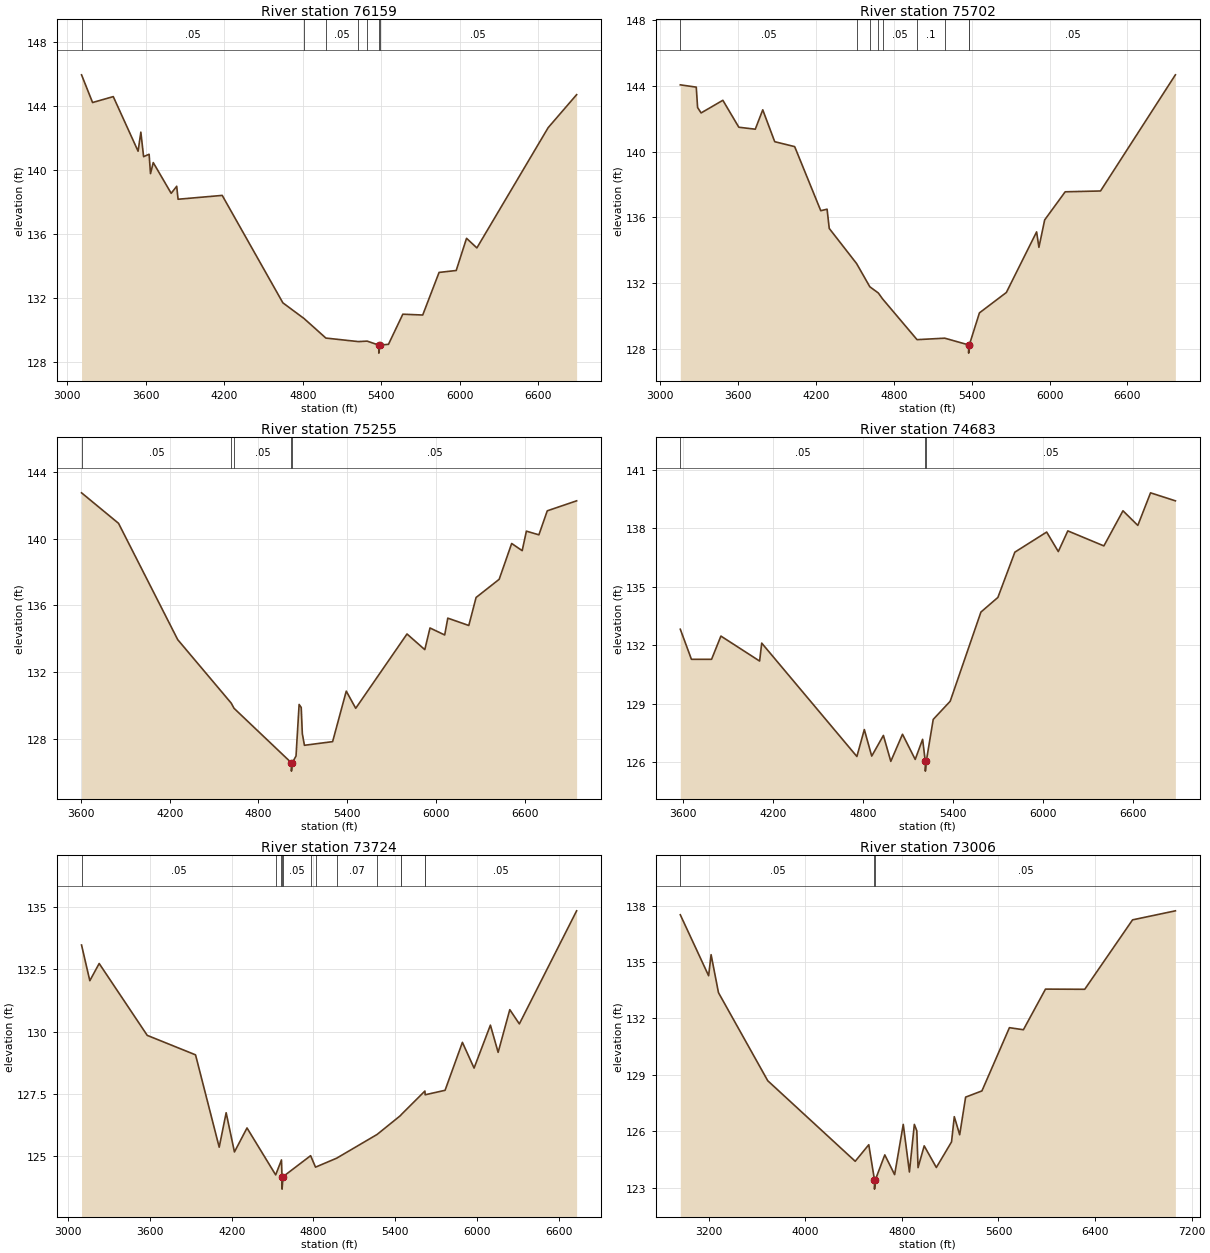
Type RM Length L Ch R = 1 ,76159   ,457,457,457
BEGIN DESCRIPTION:
DRY CREEK 118.0
END DESCRIPTION:
XS GIS Cut Line= 3
        2565925.     13492275.01        2565325.       13490475.
      2563724.98     13489474.99
#Sta/Elev= 30
  3108.8  145.94  3193.1  144.21  3351.3  144.58    3541  141.17  3562.1  142.36
  3583.2  140.83  3625.3  140.98  3635.9  139.77  3656.9  140.46    3794  138.54
  3836.1  138.98  3846.7  138.17    4184  138.41  4647.8   131.7  4809.7  130.72
  4976.5   129.5    5225  129.28  5291.8  129.31  5380.7  129.06  5381.2  128.56
  5386.3  129.06  5454.9  129.11  5564.6  130.99  5716.7  130.94  5841.7   133.6
  5972.6  133.72  6051.6  135.73  6130.6  135.13  6675.4  142.64    6893   144.7
#Mann= 7 ,-1 , 0
  3108.8     .05       0  4809.7     .07       0  4976.5     .05       0
    5225      .1       0  5291.8     .05       0  5380.7     .05       0
  5386.3     .05       0
Bank Sta=5380.7,5386.3
XS Rating Curve= 0 ,0
Exp/Cntr=0.3,0.1

Type RM Length L Ch R = 1 ,75702   ,447,447,447
BEGIN DESCRIPTION:
DRY CREEK 117.0
END DESCRIPTION:
XS GIS Cut Line= 3
        2565975.     13491975.01        2565575.       13490175.
      2563774.99       13489375.
#Sta/Elev= 30
  3155.8  144.07  3278.7  143.93    3289  142.69  3315.9  142.36  3483.6  143.13
  3606.5  141.49  3733.3  141.37  3790.9  142.55  3883.1  140.61  4036.8  140.31
  4237.8  136.41  4286.5   136.5  4303.1  135.33    4514  133.19  4615.6  131.78
  4681.2   131.4    4714  131.04  4979.5  128.56  5192.9  128.65  5376.5  128.24
  5376.9  127.74  5382.2  128.24    5460  130.19  5667.3  131.43  5900.5  135.12
  5918.3  134.18  5962.7  135.85  6120.7  137.56  6392.9  137.61  6969.5  144.68
#Mann= 9 ,-1 , 0
  3155.8     .05       0    4514    .035       0  4615.6     .05       0
  4681.2    .035       0    4714     .05       0  4979.5      .1       0
  5192.9     .05       0  5376.5     .05       0  5382.2     .05       0
Bank Sta=5376.5,5382.2
XS Rating Curve= 0 ,0
Exp/Cntr=0.3,0.1

Type RM Length L Ch R = 1 ,75255   ,572,572,572
BEGIN DESCRIPTION:
DRY CREEK 116.0
END DESCRIPTION:
XS GIS Cut Line= 3
        2565975.     13491325.01        2565925.       13489925.
      2564475.02     13488625.02
#Sta/Elev= 30
  3603.3  142.75  3853.5  140.92  4253.7  133.94  4615.6  130.13  4634.6  129.82
  5022.4  126.55  5022.9  126.05  5028.7  126.55  5053.9  126.96  5074.8  130.05
    5089  129.87  5096.5   128.3  5110.7   127.6  5301.4  127.82  5393.7  130.85
  5457.6  129.82  5804.5  134.28  5924.8  133.34    5960  134.64  6059.4  134.22
  6080.3  135.23  6222.4  134.79  6271.7  136.47  6427.8  137.56  6512.4  139.71
  6583.5  139.28  6611.9  140.45  6696.5  140.23  6753.1  141.67  6951.6  142.27
#Mann= 5 ,-1 , 0
  3603.3     .05       0  4615.6    .035       0  4634.6     .05       0
  5022.4     .05       0  5028.7     .05       0
Bank Sta=5022.4,5028.7
XS Rating Curve= 0 ,0
Exp/Cntr=0.3,0.1

Type RM Length L Ch R = 1 ,74683   ,959,959,959
BEGIN DESCRIPTION:
Mapping XS 384ac91b
END DESCRIPTION:
XS GIS Cut Line= 3
      2566817.54     13490916.72      2566525.88     13489805.65
      2564978.62     13488306.96
#Sta/Elev= 30
    3583  132.82  3657.2  131.28  3791.6  131.28  3853.9  132.47  4112.1  131.19
  4126.1  132.11    4761   126.3  4810.6  127.68    4860  126.32  4937.9  127.38
  4987.3  126.05  5065.3  127.44  5150.1  126.15  5199.5  127.18  5217.4  126.05
  5217.9  125.55  5223.9  126.05  5270.3   128.2  5383.5  129.13  5588.5   133.7
  5701.7  134.45  5814.9  136.77  6027.1   137.8  6104.8   136.8  6168.3  137.86
  6408.8  137.09  6536.2  138.89  6635.2  138.14  6720.1  139.81  6885.8   139.4
#Mann= 3 ,-1 , 0
    3583     .05       0  5217.4     .05       0  5223.9     .05       0
Bank Sta=5217.4,5223.9
XS Rating Curve= 0 ,0
Exp/Cntr=0.3,0.1

Type RM Length L Ch R = 1 ,73724   ,718,718,718
BEGIN DESCRIPTION:
Mapping XS 3d687376
END DESCRIPTION:
XS GIS Cut Line= 3
      2567456.45     13490944.57       2567123.1     13489319.54
      2565831.45     13487826.49
#Sta/Elev= 30
    3098  133.47  3158.8  132.04  3227.4  132.73  3580.2  129.85  3934.6  129.07
  4108.2  125.37  4159.2  126.75  4220.1  125.18  4312.3  126.14  4522.7  124.26
  4565.2  124.86  4569.1  124.19  4569.6  123.69  4576.9  124.19  4779.1  125.03
    4815  124.57  4970.3  124.93  5266.8  125.88  5439.2  126.64  5443.2  126.67
  5617.8  127.62  5619.6  127.47  5765.8  127.65    5893  129.57  5978.6  128.54
  6098.4  130.26  6155.2  129.17  6240.7  130.88  6310.9  130.31  6731.1  134.84
#Mann= 13 ,-1 , 0
    3098     .05       0  4522.7     .07       0  4565.2     .05       0
  4569.1     .05       0  4576.9     .05       0  4779.1      .1       0
    4815     .05       0  4970.3     .07       0  5266.8     .05       0
  5439.2     .07       0  5443.2     .05       0  5617.8     .07       0
  5619.6     .05       0
Bank Sta=4569.1,4576.9
XS Rating Curve= 0 ,0
Exp/Cntr=0.3,0.1

Type RM Length L Ch R = 1 ,73006   ,882,882,882
BEGIN DESCRIPTION:
DRY CREEK 113.0
END DESCRIPTION:
XS GIS Cut Line= 3
        2567925.     13491074.98        2567525.       13489075.
      2566525.01     13487275.02
#Sta/Elev= 30
  2966.1  137.51  3200.6  134.27    3221  135.39  3282.2  133.37  3690.1  128.69
  4414.2  124.41  4526.4  125.29  4573.4  123.43  4573.9  122.93  4581.3  123.43
    4659  124.75  4740.5   123.7  4811.9  126.37  4862.9  123.84  4903.7  126.37
  4924.1  126.03  4934.3  124.07  4985.3  125.23  5085.8  124.08  5211.6  125.44
  5234.5  126.78  5279.1  125.82  5328.3  127.82  5463.3  128.15  5690.9  131.51
  5806.5   131.4  5989.5  133.56  6314.4  133.55  6710.2  137.24  7064.8  137.72
#Mann= 3 ,-1 , 0
  2966.1     .05       0  4573.4     .05       0  4581.3     .05       0
Bank Sta=4573.4,4581.3
XS Rating Curve= 0 ,0
Exp/Cntr=0.3,0.1

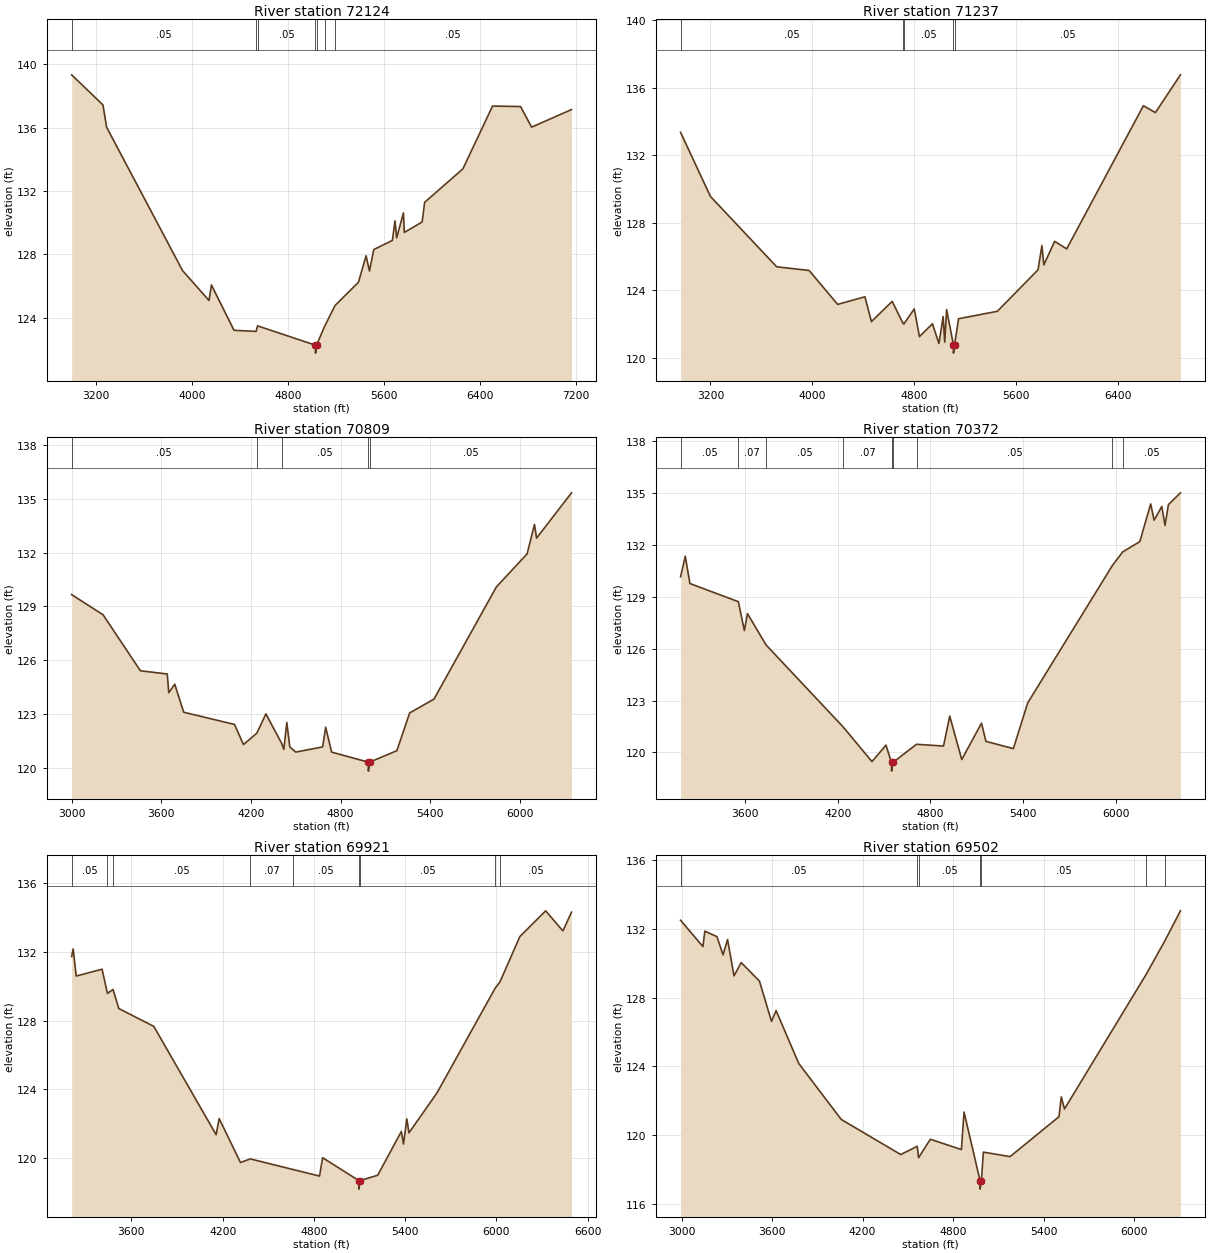
Type RM Length L Ch R = 1 ,72124   ,887,887,887
BEGIN DESCRIPTION:
DRY CREEK 112.0
END DESCRIPTION:
XS GIS Cut Line= 3
        2568075.     13491174.98        2568275.       13489175.
      2566825.03     13487575.03
#Sta/Elev= 30
  2995.4  139.33  3256.7  137.43  3286.8  136.03    3920  126.99  4141.1   125.1
  4161.2  126.08  4349.6  123.22    4534  123.15  4545.8   123.5  5029.1  122.28
  5029.6  121.78  5037.7  122.28  5106.7  123.49  5191.9  124.78  5387.5  126.25
  5451.1  127.92  5479.4  126.96  5515.3  128.31  5670.7  128.89  5692.4  130.12
  5706.5  129.05  5762.6  130.62  5770.1  129.39  5918.7  130.05  5939.7  131.29
  6258.7   133.4    6506  137.36  6739.9  137.33  6831.8  136.03  7164.6  137.14
#Mann= 7 ,-1 , 0
  2995.4     .05       0    4534     .07       0  4545.8     .05       0
  5029.1     .05       0  5037.7     .05       0  5106.7     .07       0
  5191.9     .05       0
Bank Sta=5029.1,5037.7
XS Rating Curve= 0 ,0
Exp/Cntr=0.3,0.1

Type RM Length L Ch R = 1 ,71237   ,428,428,428
BEGIN DESCRIPTION:
DRY CREEK 111.0
END DESCRIPTION:
XS GIS Cut Line= 3
      2568574.99     13490975.05        2568975.       13488975.
      2567374.96     13487974.98
#Sta/Elev= 30
  2965.7  133.36  3200.3  129.56  3720.4  125.39  3975.4  125.17  4199.7  123.16
  4413.9  123.61  4464.9  122.14    4628  123.34  4714.2  122.02  4719.8     122
  4801.4  122.89  4842.2  121.25  4944.2  122.01  4995.2  120.84  5028.4  122.44
  5040.7  120.92  5055.5  122.85    5109  120.77  5109.5  120.27  5117.6  120.77
  5149.8  122.31  5454.1  122.75  5773.6  125.21  5804.3  126.65    5819   125.5
  5904.5   126.9  5998.9  126.45  6601.5  134.94  6695.8  134.53  6892.2  136.77
#Mann= 5 ,-1 , 0
  2965.7     .05       0  4714.2     .07       0  4719.8     .05       0
    5109     .05       0  5117.6     .05       0
Bank Sta=5109,5117.6
XS Rating Curve= 0 ,0
Exp/Cntr=0.3,0.1

Type RM Length L Ch R = 1 ,70809   ,437,437,437
BEGIN DESCRIPTION:
DRY CREEK 110.0
END DESCRIPTION:
XS GIS Cut Line= 3
        2569225.     13490675.01        2569225.       13488675.
      2568324.98     13487674.98
#Sta/Elev= 30
  2999.7  129.66  3209.7  128.54  3459.7  125.42  3639.7  125.24  3649.7   124.2
  3689.7  124.67  3749.7  123.11  4089.7  122.43  4149.7  121.31  4239.7  121.95
  4299.7  123.02  4405.6  121.37  4419.7  121.04  4439.7  122.54  4459.7  121.18
  4499.7  120.89  4679.7  121.18  4699.7  122.28  4739.7  120.89  4985.3  120.33
  4985.8  119.83  4994.1  120.33  5176.5  120.97  5261.7  123.07  5424.6  123.84
  5842.4  130.09    6048  131.93  6097.3  133.57  6111.5  132.81  6345.1  135.33
#Mann= 5 ,-1 , 0
  2999.7     .05       0  4239.7     .07       0  4405.6     .05       0
  4985.3     .05       0  4994.1     .05       0
Bank Sta=4985.3,4994.1
XS Rating Curve= 0 ,0
Exp/Cntr=0.3,0.1

Type RM Length L Ch R = 1 ,70372   ,451,451,451
BEGIN DESCRIPTION:
DRY CREEK 109.0
END DESCRIPTION:
XS GIS Cut Line= 3
        2569775.       13490425.        2569575.       13488625.
      2568675.03     13487525.03
#Sta/Elev= 30
  3184.3  130.15  3214.5  131.34  3244.7  129.76  3557.9  128.71  3596.8  127.04
  3616.9  128.02  3737.2  126.21  4235.9  121.47  4421.9  119.47  4512.4  120.42
  4548.3  119.42  4548.8  118.92  4557.1  119.42  4710.1  120.47  4884.7  120.37
  4924.9   122.1  5002.6  119.59  5130.3  121.69    5159  120.64  5336.3  120.22
  5428.9  122.86  5977.2  130.81  6043.8  131.59  6153.9  132.18  6224.3  134.36
  6246.5  133.42  6296.1  134.21  6316.9  133.12  6339.1  134.32  6416.6     135
#Mann= 9 ,-1 , 0
  3184.3     .05       0  3557.9     .07       0  3737.2     .05       0
  4235.9     .07       0  4548.3     .05       0  4557.1     .07       0
  4710.1     .05       0  5977.2    .035       0  6043.8     .05       0
Bank Sta=4548.3,4557.1
XS Rating Curve= 0 ,0
Exp/Cntr=0.3,0.1

Type RM Length L Ch R = 1 ,69921   ,419,419,419
BEGIN DESCRIPTION:
DRY CREEK 108.0
END DESCRIPTION:
XS GIS Cut Line= 3
        2569875.     13490275.01        2569875.       13488475.
      2568775.02     13487475.01
#Sta/Elev= 30
  3207.3  131.74  3217.3  132.18  3237.3   130.6  3407.3     131  3442.5  129.59
  3479.5  129.82  3517.3  128.71  3747.3  127.67  4157.3  121.36  4177.3   122.3
  4317.3  119.74  4382.1  119.95    4660  119.34  4837.3  118.95  4857.3  120.02
  5095.2  118.69  5095.7  118.19    5104  118.69  5219.8     119  5375.2  121.55
  5389.4  120.82  5411.1  122.28  5425.3  121.47  5609.1  123.79  5992.3   129.9
  6022.8  130.25  6154.4   132.9    6324   134.4  6437.5  133.23  6493.9  134.32
#Mann= 9 ,-1 , 0
  3207.3     .05       0  3442.5     .07       0  3479.5     .05       0
  4382.1     .07       0    4660     .05       0  5095.2     .05       0
    5104     .05       0  5992.3    .035       0  6022.8     .05       0
Bank Sta=5095.2,5104
XS Rating Curve= 0 ,0
Exp/Cntr=0.3,0.1

Type RM Length L Ch R = 1 ,69502   ,433,433,433
BEGIN DESCRIPTION:
DRY CREEK 107.0
END DESCRIPTION:
XS GIS Cut Line= 3
        2569975.       13490325.        2570175.       13488325.
      2569075.01     13487625.01
#Sta/Elev= 30
  2993.8   132.5    3142  130.97  3154.6  131.87    3235  131.55  3275.2  130.49
  3305.3  131.38  3348.1  129.27  3395.8  130.04  3516.4  128.97  3596.8  126.62
  3626.9  127.25  3777.7  124.17  4059.1  120.92  4453.5  118.88  4562.7  119.36
  4571.8   118.7  4649.5  119.77  4855.5  119.17  4873.1  121.35  4979.1  117.37
  4979.6  116.87  4988.2  117.37  5001.3  119.02  5178.2  118.76  5502.5  121.08
  5517.7  122.23  5538.9  121.53  6078.7  129.33  6203.5  131.29  6307.6  133.05
#Mann= 7 ,-1 , 0
  2993.8     .05       0  4562.7     .07       0  4571.8     .05       0
  4979.1     .05       0  4988.2     .05       0  6078.7    .035       0
  6203.5     .05       0
Bank Sta=4979.1,4988.2
XS Rating Curve= 0 ,0
Exp/Cntr=0.3,0.1

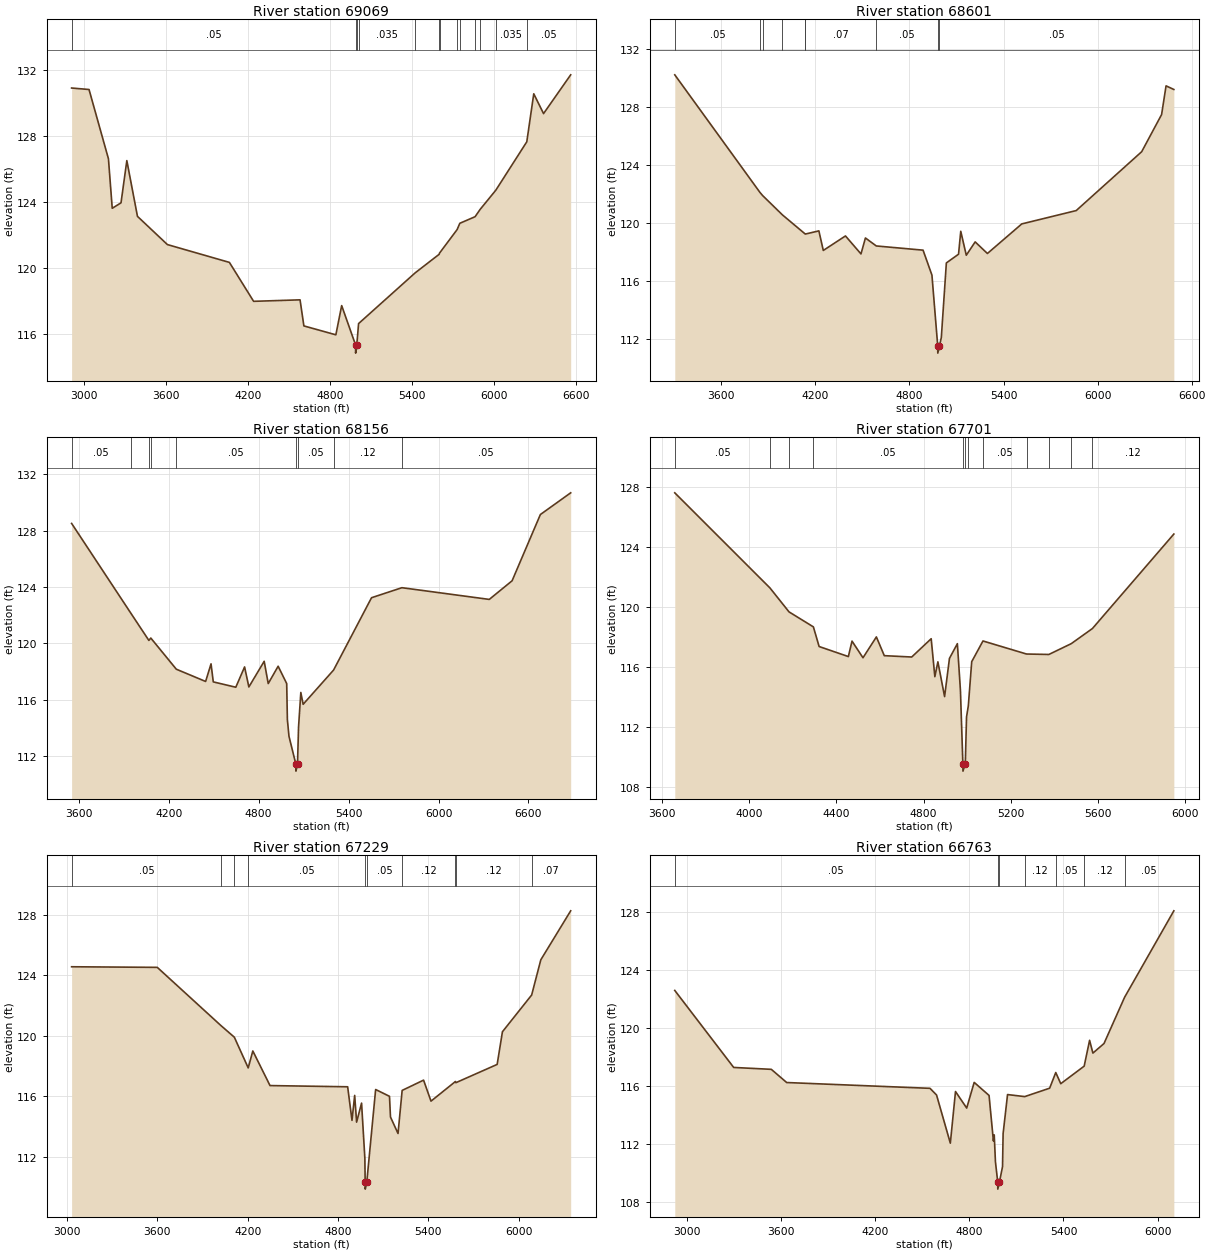
Type RM Length L Ch R = 1 ,69069   ,468,468,468
BEGIN DESCRIPTION:
DRY CREEK 106.0
END DESCRIPTION:
XS GIS Cut Line= 3
      2571925.02     13489925.02        2570525.       13488375.
      2569525.03     13487175.03
#Sta/Elev= 30
  2911.3  130.93  3038.7  130.84  3180.7  126.64  3208.4  123.64  3272.6  123.97
  3315.2  126.53    3393  123.15    3612  121.44  4065.5  120.36  4242.6     118
  4582.3  118.09  4610.3  116.51  4844.2  115.97  4886.8  117.74  4988.3  115.36
  4988.8  114.86  4997.5  115.36  5010.4  116.65    5425  119.73  5599.8  120.85
  5602.4  120.92  5731.3  122.35    5751  122.73  5862.7  123.13  5899.5  123.57
  6014.6  124.74  6240.9  127.67  6291.9  130.58  6363.5  129.38    6562  131.73
#Mann= 13 ,-1 , 0
  2911.3     .05       0  4988.3     .05       0  4997.5     .05       0
  5010.4    .035       0    5425     .05       0  5599.8    .035       0
  5602.4     .05       0  5731.3    .035       0    5751     .05       0
  5862.7    .035       0  5899.5     .05       0  6014.6    .035       0
  6240.9     .05       0
Bank Sta=4988.3,4997.5
XS Rating Curve= 0 ,0
Exp/Cntr=0.3,0.1

Type RM Length L Ch R = 1 ,68601   ,445,445,445
BEGIN DESCRIPTION:
DRY CREEK 105.0
END DESCRIPTION:
XS GIS Cut Line= 3
        2572075.       13489525.        2570875.       13488325.
      2569774.97     13487324.98
#Sta/Elev= 30
  3302.7   130.2  3846.2  122.09  3863.6  121.87  3989.7  120.54  4133.1  119.24
  4135.7  119.22  4221.9  119.44  4250.2  118.09  4391.6  119.09  4490.6  117.85
  4518.9  118.95  4588.2   118.4  4886.6  118.11  4943.2  116.39  4980.1  111.51
  4980.6  111.01  4991.2  111.51  5003.1  112.09  5035.2  117.23  5112.9  117.83
  5127.1  119.41  5162.3  117.76    5219  118.68  5297.1  117.88  5516.4  119.92
  5863.7  120.84  6281.3   124.9  6408.3  127.46  6436.7  129.44  6486.4  129.19
#Mann= 9 ,-1 , 0
  3302.7     .05       0  3846.2    .035       0  3863.6     .05       0
  3989.7     .07       0  4133.1     .05       0  4135.7     .07       0
  4588.2     .05       0  4980.1     .05       0  4991.2     .05       0
Bank Sta=4980.1,4991.2
XS Rating Curve= 0 ,0
Exp/Cntr=0.3,0.1

Type RM Length L Ch R = 1 ,68156   ,455,455,455
BEGIN DESCRIPTION:
DRY CREEK 104.0
END DESCRIPTION:
XS GIS Cut Line= 3
      2572075.01     13489375.02        2571275.       13488175.
      2569675.04     13487175.02
#Sta/Elev= 30
  3552.5  128.51  3947.1  122.15  4067.9  120.21  4080.7  120.38  4250.8  118.17
  4446.4   117.3  4482.5  118.55  4497.5  117.27  4647.7  116.89  4706.3  118.33
  4734.8  116.91    4837  118.73    4864  117.15  4930.1  118.38  4987.2  117.15
  4991.7   114.6  5002.4  113.41  5048.2  111.44  5048.7  110.94  5059.3  111.44
  5066.1  114.04  5081.4  116.52  5096.8  115.68    5300  118.11  5553.1  123.24
  5755.7  123.95  6338.5  123.12  6490.6  124.44  6679.3  129.14  6881.5  130.68
#Mann= 9 ,-1 , 0
  3552.5     .05       0  3947.1    .035       0  4067.9     .05       0
  4080.7     .07       0  4250.8     .05       0  5048.2     .05       0
  5059.3     .05       0    5300     .12       0  5755.7     .05       0
Bank Sta=5048.2,5059.3
XS Rating Curve= 0 ,0
Exp/Cntr=0.3,0.1

Type RM Length L Ch R = 1 ,67701   ,472,472,472
BEGIN DESCRIPTION:
DRY CREEK 103.0
END DESCRIPTION:
XS GIS Cut Line= 3
      2572275.01     13489225.01        2571675.       13488025.
      2570775.03     13487725.01
#Sta/Elev= 30
  3658.4  127.62    4095  121.28  4182.7  119.68  4294.5  118.68  4320.8  117.37
    4455   116.7  4471.8  117.73  4522.1  116.62  4583.6  118.01  4619.9  116.76
  4745.7  116.67  4835.1  117.89  4851.9  115.36  4865.9  116.35  4896.6  114.03
    4919  116.58  4955.3  117.56  4969.3  114.45  4980.5  109.56    4981  109.06
  4991.7  109.56  4997.3  112.67  5005.5  113.41  5021.1  116.36  5072.8  117.74
  5272.5  116.87  5375.1  116.84  5477.8  117.56  5575.1  118.57  5948.7  124.87
#Mann= 12 ,-1 , 0
  3658.4     .05       0    4095    .035       0  4182.7     .07       0
  4294.5     .05       0  4980.5     .05       0  4991.7     .05       0
  5005.5     .12       0  5072.8     .05       0  5272.5     .07       0
  5375.1     .05       0  5477.8     .07       0  5575.1     .12       0
Bank Sta=4980.5,4991.7
XS Rating Curve= 0 ,0
Exp/Cntr=0.3,0.1

Type RM Length L Ch R = 1 ,67229   ,466,466,466
BEGIN DESCRIPTION:
DRY CREEK 102.0
END DESCRIPTION:
XS GIS Cut Line= 3
      2572724.99     13489474.98        2571925.       13487675.
      2570925.01     13486775.01
#Sta/Elev= 30
  3030.2  124.56  3599.2  124.52  4024.2  120.65  4111.1   119.9  4203.3  117.87
  4233.9  118.99  4348.1   116.7  4863.8  116.62  4892.6   114.4  4910.4  116.05
  4923.3  114.28  4956.2  115.54  4978.1  111.89    4980  110.35  4980.5  109.85
  4991.2  110.35  5049.7  116.44  5141.6  115.99  5148.3  114.62  5198.4  113.53
  5225.8  116.38  5368.1  117.06  5417.4  115.67  5579.9  116.97  5582.5  116.89
  5856.9   118.1    5892  120.26    6086  122.69  6146.9  125.02  6345.3  128.26
#Mann= 10 ,-1 , 0
  3030.2     .05       0  4024.2    .035       0  4111.1     .07       0
  4203.3     .05       0    4980     .05       0  4991.2     .05       0
  5225.8     .12       0  5579.9     .05       0  5582.5     .12       0
    6086     .07       0
Bank Sta=4980,4991.2
XS Rating Curve= 0 ,0
Exp/Cntr=0.3,0.1

Type RM Length L Ch R = 1 ,66763   ,438,438,438
BEGIN DESCRIPTION:
DRY CREEK 101.0
END DESCRIPTION:
XS GIS Cut Line= 3
      2573875.04     13487925.01        2571875.       13487325.
        2571075.       13486575.
#Sta/Elev= 30
  2919.5  122.57  3295.4  117.26  3535.5  117.13  3633.8  116.22  4548.2  115.82
    4590  115.36  4677.9  112.04  4710.9   115.6  4782.3  114.46  4830.1  116.23
    4925  115.33  4952.8  112.19    4958  112.61  4965.8  110.75  4980.3  109.37
  4980.8  108.87  4991.5  109.37    5011  110.42  5014.7   112.7    5043  115.39
  5152.7  115.25  5311.7  115.83  5350.7  116.91  5382.5  116.14    5532  117.35
  5566.6  119.13  5587.7  118.25  5658.5  118.91    5790   122.1  6104.2  128.06
#Mann= 7 ,-1 , 0
  2919.5     .05       0  4980.3     .05       0  4991.5     .05       0
  5152.7     .12       0  5350.7     .05       0    5532     .12       0
    5790     .05       0
Bank Sta=4980.3,4991.5
XS Rating Curve= 0 ,0
Exp/Cntr=0.3,0.1

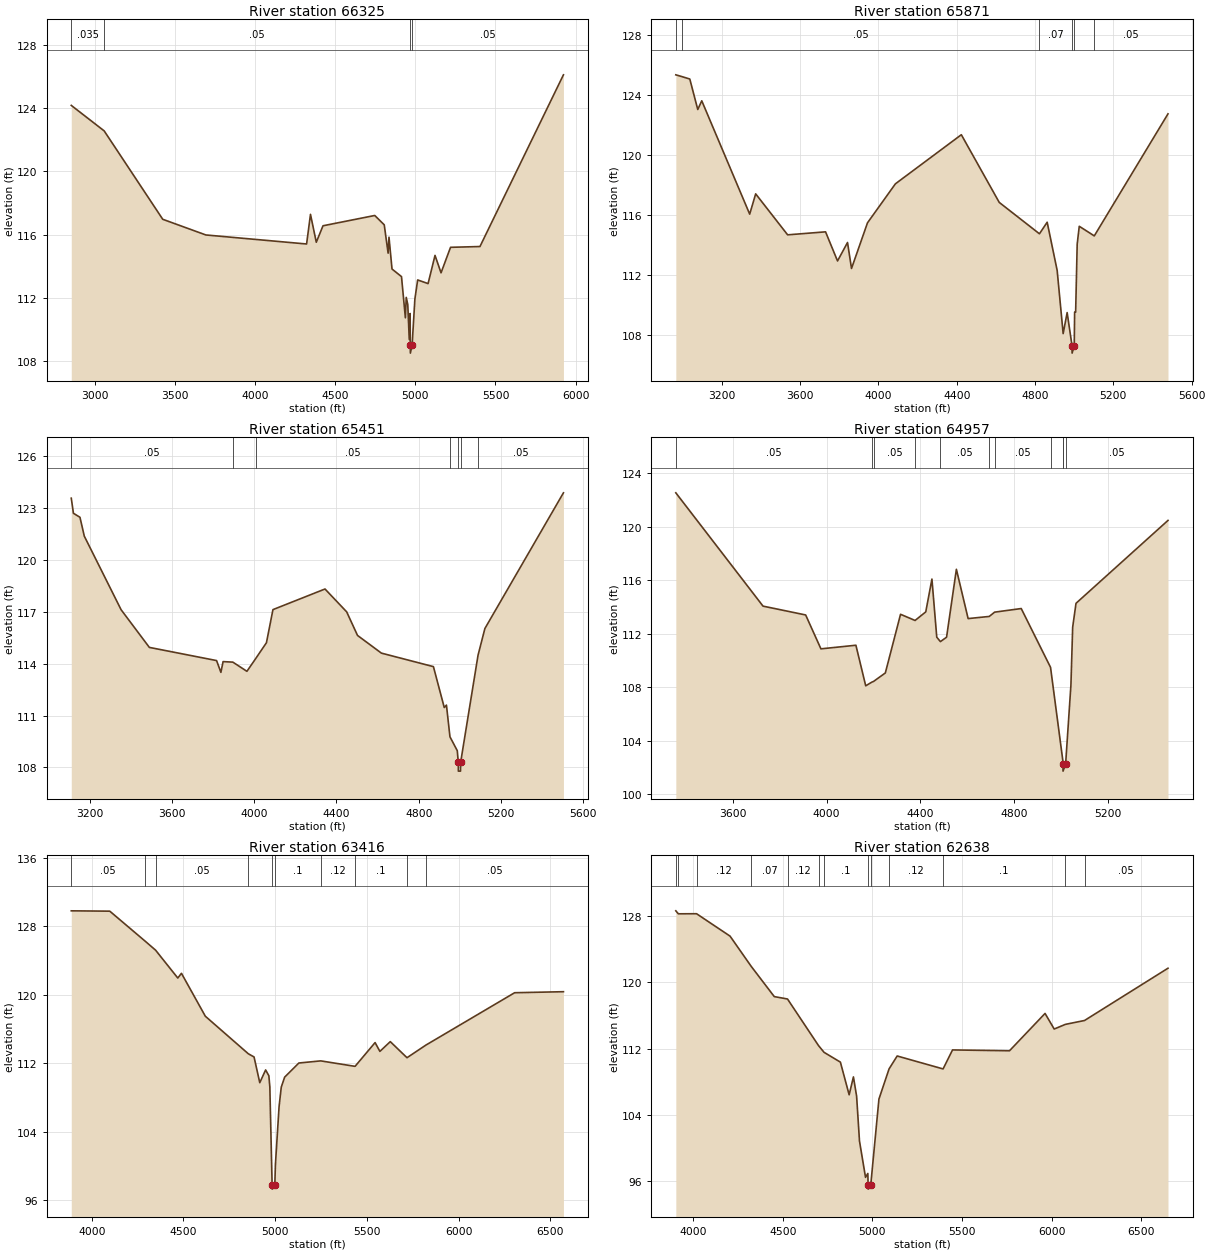
Type RM Length L Ch R = 1 ,66325   ,454,454,454
BEGIN DESCRIPTION:
DRY CREEK 100.0
END DESCRIPTION:
XS GIS Cut Line= 3
      2574025.04     13487775.02        2572025.       13486975.
      2571224.99     13486524.99
#Sta/Elev= 30
  2852.1  124.16  3057.5  122.55    3423  116.97  3692.2  115.98  4320.9  115.41
  4345.2  117.28  4381.5  115.52  4423.3  116.56  4746.4  117.21  4805.6  116.62
  4829.8  114.83  4835.2  115.84  4854.1  113.83  4913.3  113.35  4937.5  110.75
  4942.9  112.04  4952.4  111.59  4961.8  109.38  4967.2  111.02  4968.2  109.02
  4968.7  108.52  4979.5  109.02  4996.8  111.93  5014.2  113.14  5079.2  112.91
  5122.5  114.69  5160.1  113.59  5219.4   115.2    5403  115.25  5924.1  126.09
#Mann= 4 ,-1 , 0
  2852.1    .035       0  3057.5     .05       0  4968.2     .05       0
  4979.5     .05       0
Bank Sta=4968.2,4979.5
XS Rating Curve= 0 ,0
Exp/Cntr=0.3,0.1

Type RM Length L Ch R = 1 ,65871   ,420,420,420
BEGIN DESCRIPTION:
DRY CREEK 99.0
END DESCRIPTION:
XS GIS Cut Line= 3
      2573874.97     13486974.99        2571875.       13486575.
      2571425.01       13486425.
#Sta/Elev= 30
  2965.2  125.32  2999.2  125.19  3036.6  125.04  3077.3  123.01  3097.7  123.59
  3342.5  116.04  3373.1  117.39  3536.3  114.66    3730  114.86  3791.2  112.92
  3842.2  114.15  3862.6  112.42  3944.2  115.46  4086.9  118.06  4423.5  121.33
  4617.2  116.82  4822.5  114.73    4862   115.5    4913  112.29  4943.6  108.08
    4964  109.48  4988.9  107.28  4989.4  106.78  5000.3  107.28  5002.2  109.51
  5007.4  109.51  5015.3  114.04  5025.9  115.23  5102.6  114.59  5479.1  122.72
#Mann= 6 ,-1 , 0
  2965.2     .07       0  2999.2     .05       0  4822.5     .07       0
  4988.9     .05       0  5000.3     .07       0  5102.6     .05       0
Bank Sta=4988.9,5000.3
XS Rating Curve= 0 ,0
Exp/Cntr=0.3,0.1

Type RM Length L Ch R = 1 ,65451   ,494,494,494
BEGIN DESCRIPTION:
DRY CREEK 98.0
END DESCRIPTION:
XS GIS Cut Line= 3
      2573725.01       13486825.        2571925.       13486225.
      2571575.03     13485875.03
#Sta/Elev= 30
  3111.3  123.54  3121.8  122.67  3153.5  122.44  3174.6  121.35  3353.7   117.1
  3490.8  114.93  3817.5  114.17  3838.6  113.49  3849.2  114.11  3896.6  114.08
  3965.1  113.55    4008  114.29    4060   115.2  4091.6  117.11  4344.6   118.3
    4450  116.98  4502.7  115.62  4618.7   114.6  4871.6  113.82  4924.3  111.46
  4934.9   111.6    4952  109.77  4987.6  108.97  4992.4  108.29  4992.9  107.79
  5003.3  107.79  5003.8  108.29  5088.5  114.48  5121.8  116.02  5503.6  123.85
#Mann= 7 ,-1 , 0
  3111.3     .05       0  3896.6     .07       0    4008     .05       0
    4952     .07       0  4992.4     .05       0  5003.8     .07       0
  5088.5     .05       0
Bank Sta=4992.4,5003.8
XS Rating Curve= 0 ,0
Exp/Cntr=0.3,0.1

Type RM Length L Ch R = 1 ,64957   ,1541,1541,1541
BEGIN DESCRIPTION:
Mapping XS 063618e6
END DESCRIPTION:
XS GIS Cut Line= 3
       2573716.3      13486200.8      2572139.87     13485818.84
      2571786.07     13485499.73
#Sta/Elev= 30
  3357.4  122.52  3729.2  114.06    3911   113.4  3976.1  110.87  4125.2  111.14
  4167.1  108.11  4192.6  108.38  4200.7  108.44  4250.7  109.07  4315.6  113.45
  4377.5  112.99  4423.1  113.63  4449.4  116.08    4470  111.74  4485.6  111.41
  4511.8  111.74  4553.7  116.81  4603.7  113.13  4693.8  113.29  4716.6  113.61
  4830.1  113.88  4955.1  109.49  5007.5  102.53  5007.9  102.24  5008.4  101.74
  5019.3  102.24    5042  108.16  5049.5  112.49  5063.7  114.27  5455.9  120.46
#Mann= 11 ,-1 , 0
  3357.4     .05       0  4192.6     .07       0  4200.7     .05       0
  4377.5     .07       0  4485.6     .05       0  4693.8     .07       0
  4716.6     .05       0  4955.1     .07       0  5007.5     .05       0
  5007.9     .05       0  5019.3     .05       0
Bank Sta=5007.9,5019.3
XS Rating Curve= 0 ,0
Exp/Cntr=0.3,0.1

Type RM Length L Ch R = 1 ,63416   ,778,778,778
BEGIN DESCRIPTION:
Mapping XS e12a7458
END DESCRIPTION:
XS GIS Cut Line= 4
      2574074.51     13484958.43      2573150.88     13484902.87
       2572810.6     13484777.87      2571463.37     13485138.99
#Sta/Elev= 30
  3888.5  129.81  4098.4  129.77  4290.2  126.28    4348  125.21  4469.1  121.95
  4489.1   122.5  4619.3  117.48  4853.6  113.09  4884.7  112.72  4915.9  109.71
  4947.9   111.2  4965.5  110.52  4970.8  109.22  4983.2   97.76  4983.7   97.26
  4997.8   97.76  5001.3  100.16  5021.1   106.9  5033.1  109.19  5051.6  110.36
    5129  112.01  5248.2  112.26  5435.3  111.62  5544.5   114.4  5570.6  113.37
  5627.3  114.51  5718.4  112.63  5820.9   114.1    6305  120.23  6571.1  120.35
#Mann= 10 ,-1 , 0
  3888.5     .05       0  4290.2     .12       0    4348     .05       0
  4853.6      .1       0  4983.2     .05       0  4997.8      .1       0
  5248.2     .12       0  5435.3      .1       0  5718.4     .07       0
  5820.9     .05       0
Bank Sta=4983.2,4997.8
XS Rating Curve= 0 ,0
Exp/Cntr=0.3,0.1

Type RM Length L Ch R = 1 ,62638   ,551,551,551
BEGIN DESCRIPTION:
Mapping XS 2a89aba6
END DESCRIPTION:
XS GIS Cut Line= 3
       2573984.2     13484472.31      2572942.55     13484173.71
      2571360.66     13484680.19
#Sta/Elev= 30
    3904   128.6  3918.1  128.24  4019.6  128.25  4206.4  125.55  4323.9  121.92
    4453  118.26  4526.8  117.97  4699.9  112.35  4730.7  111.54  4821.7  110.36
  4870.6  106.42  4894.4  108.58  4912.2  106.25  4928.2  100.85  4961.9   96.47
  4974.7   96.94  4976.4   95.55  4976.9   95.05    4991   95.55  5036.7  105.91
  5093.3  109.55  5138.4   111.1  5394.4  109.54    5447  111.83  5764.9  111.73
    5963  116.23    6014  114.35  6076.1  114.91  6183.3  115.38  6648.6  121.68
#Mann= 13 ,-1 , 0
    3904     .12       0  3918.1     .07       0  4019.6     .12       0
  4323.9     .07       0  4526.8     .12       0  4699.9     .07       0
  4730.7      .1       0  4976.4     .05       0    4991      .1       0
  5093.3     .12       0  5394.4      .1       0  6076.1     .07       0
  6183.3     .05       0
Bank Sta=4976.4,4991
XS Rating Curve= 0 ,0
Exp/Cntr=0.3,0.1