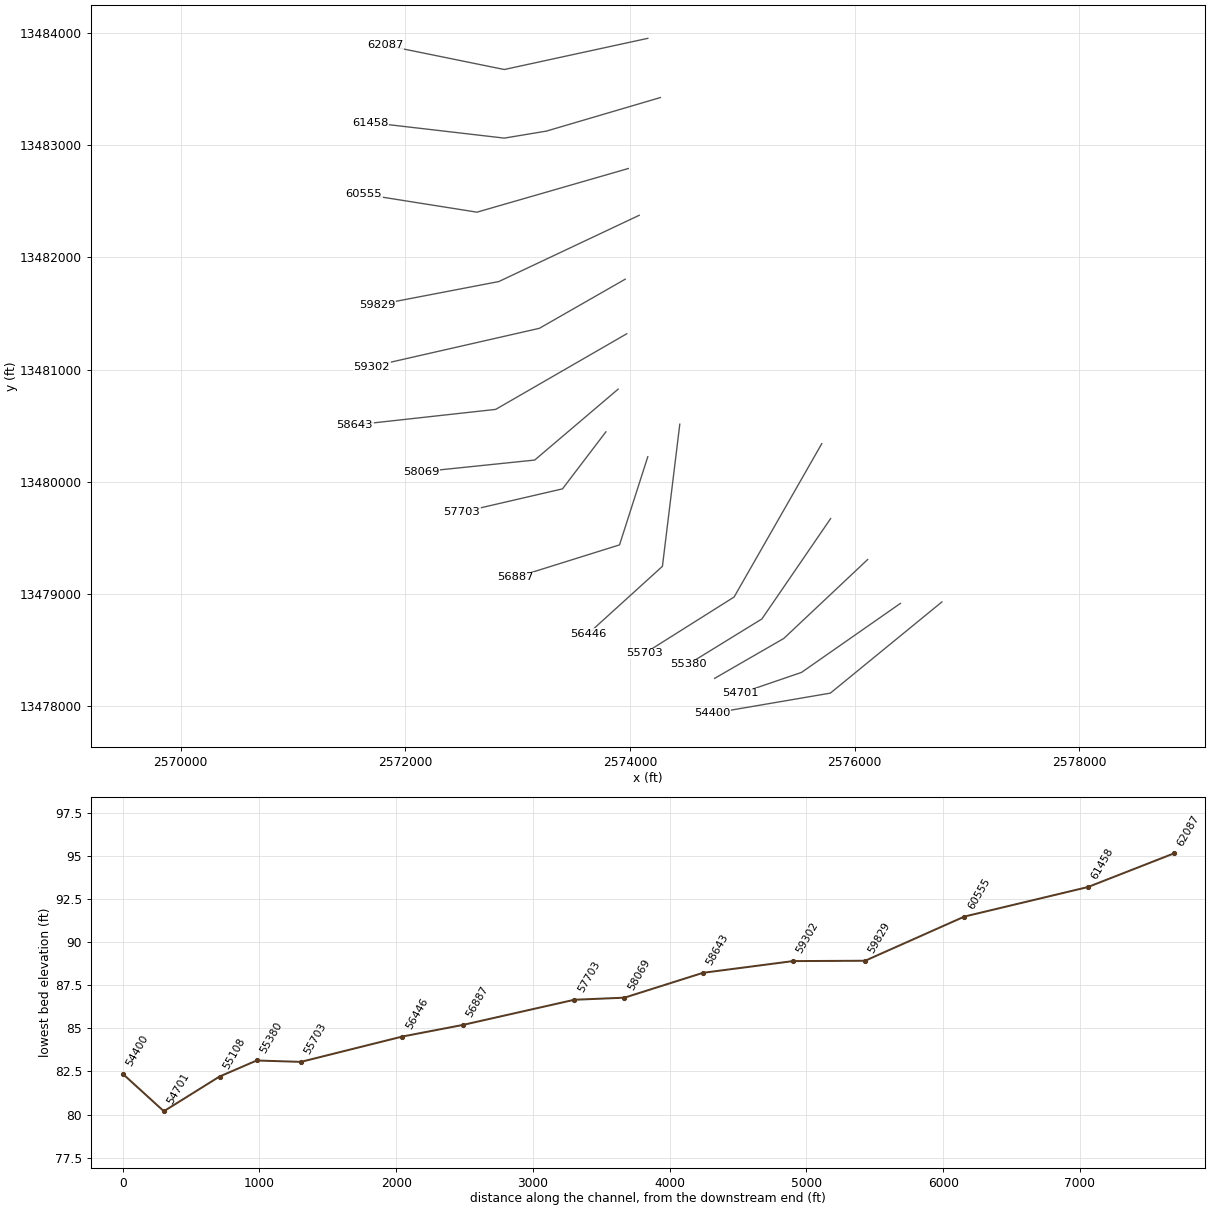
HEC-RAS study DRY CREEK.prj: DRY CREEK Base Level Engineering

--- DRY CREEK.g01 (geometry) --- (continued)

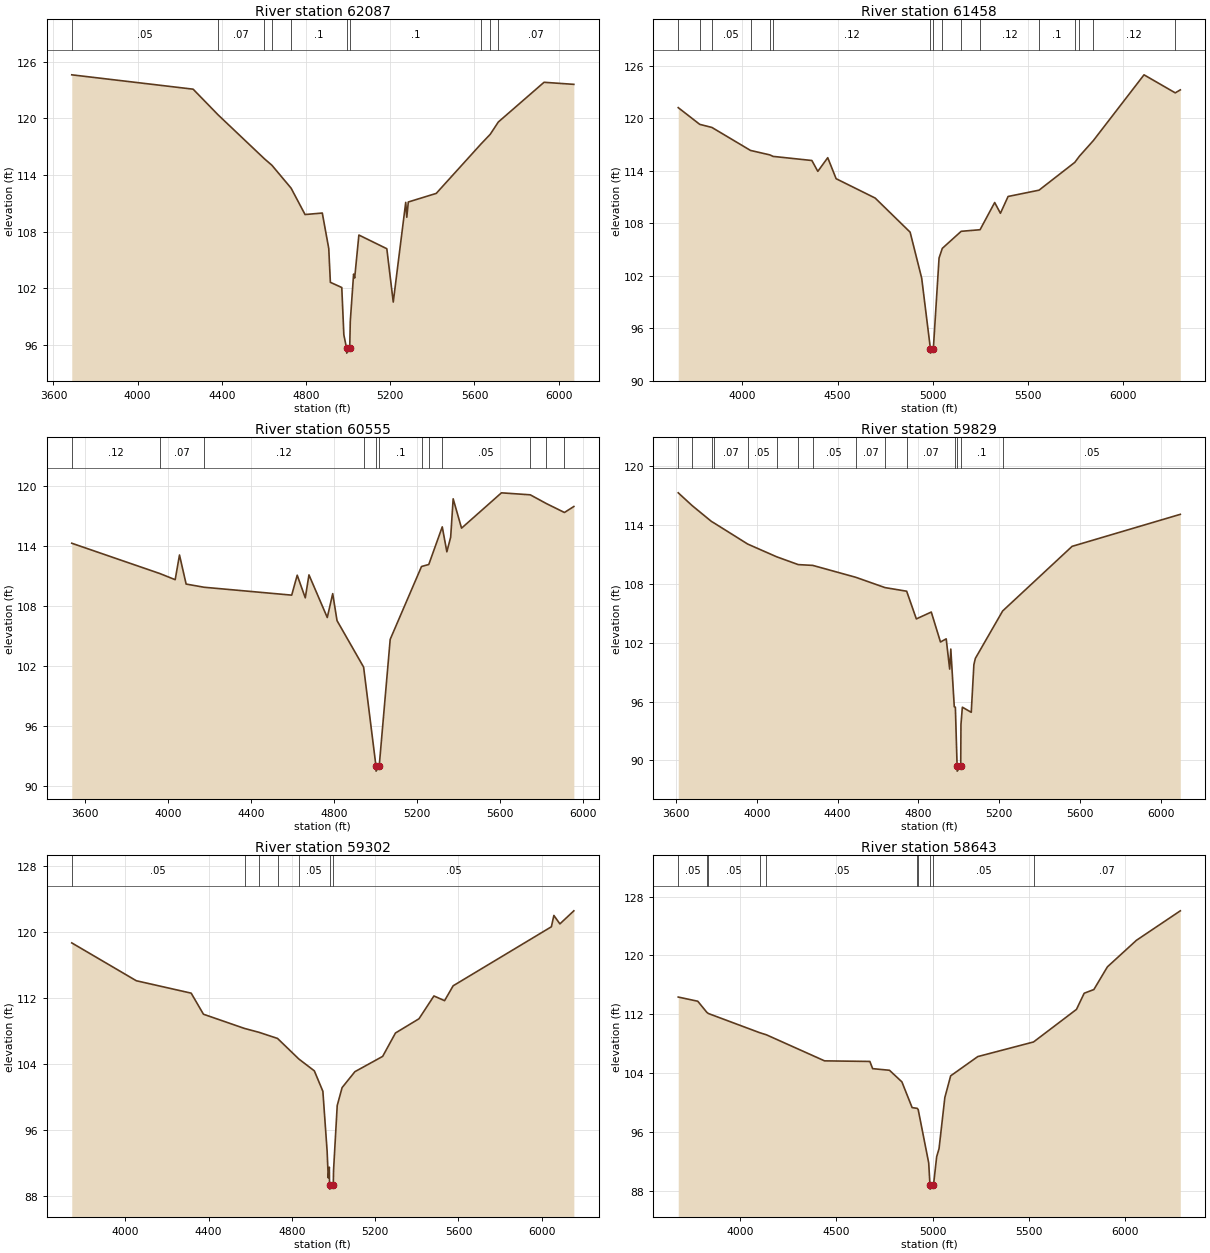
Type RM Length L Ch R = 1 ,62087   ,629,629,629
BEGIN DESCRIPTION:
Mapping XS ec744ebd
END DESCRIPTION:
XS GIS Cut Line= 3
      2574157.86     13483951.49      2572880.05     13483673.71
      2571824.54     13483888.97
#Sta/Elev= 30
  3687.1  124.61  4263.6  123.09  4382.2  120.37  4602.5  115.71  4637.8  115.03
  4728.8  112.61  4795.3  109.81  4877.1  109.97  4907.8  106.22  4915.5  102.63
  4969.7  102.08  4979.5   97.07  4992.6   95.63  4993.1   95.13  5007.3   95.63
  5010.1   98.51  5025.8   103.5  5030.9  103.09  5050.9  107.64  5183.6  106.19
  5214.2  100.54  5273.4   111.1  5278.5  109.52  5285.7  111.14  5418.4  112.05
  5630.8  117.28  5674.8  118.31  5713.2  119.61  5930.4  123.82    6072   123.6
#Mann= 10 ,-1 , 0
  3687.1     .05       0  4382.2     .07       0  4602.5      .1       0
  4637.8     .07       0  4728.8      .1       0  4992.6     .05       0
  5007.3      .1       0  5630.8     .07       0  5674.8      .1       0
  5713.2     .07       0
Bank Sta=4992.6,5007.3
XS Rating Curve= 0 ,0
Exp/Cntr=0.3,0.1

Type RM Length L Ch R = 1 ,61458   ,903,903,903
BEGIN DESCRIPTION:
Mapping XS 5c542877
END DESCRIPTION:
XS GIS Cut Line= 4
      2574268.95     13483423.71      2573255.05     13483125.09
      2572880.05     13483062.59      2571685.63     13483201.48
#Sta/Elev= 30
  3662.6  121.23  3775.7  119.32  3839.4  118.97  4042.7  116.34  4144.3  115.83
  4161.3  115.66  4365.2  115.19  4396.4  113.95  4448.6  115.51  4492.7  113.11
  4697.9   110.9  4881.8     107  4942.6  101.74  4988.4   93.68  4988.9   93.18
  5003.8   93.68  5033.9  104.05  5050.9  105.15  5150.2   107.1  5249.4  107.28
  5326.3  110.39  5356.5  109.16  5396.8  111.08  5559.5   111.8  5747.6  114.98
  5771.7  115.68  5845.1  117.47  6111.4  124.98  6275.6  122.92  6302.2  123.26
#Mann= 16 ,-1 , 0
  3662.6     .05       0  3775.7    .035       0  3839.4     .05       0
  4042.7    .035       0  4144.3     .05       0  4161.3     .12       0
  4988.4     .05       0  5003.8     .12       0  5050.9      .1       0
  5150.2     .07       0  5249.4     .12       0  5559.5      .1       0
  5747.6     .12       0  5771.7      .1       0  5845.1     .12       0
  6275.6     .05       0
Bank Sta=4988.4,5003.8
XS Rating Curve= 0 ,0
Exp/Cntr=0.3,0.1

Type RM Length L Ch R = 1 ,60555   ,726,726,726
BEGIN DESCRIPTION:
Mapping XS a841478b
END DESCRIPTION:
XS GIS Cut Line= 3
       2573984.2     13482791.76      2572636.99     13482402.87
      2571630.09     13482562.59
#Sta/Elev= 30
  3534.7   114.3    3960  111.26  4033.5  110.65  4054.3  113.12  4086.3  110.21
  4173.1  109.89  4595.5   109.1  4622.1   111.1    4661  108.83  4678.8  111.13
  4767.1  106.86  4793.3  109.25  4814.1  106.55  4942.4  101.89    5002   91.97
  5002.5   91.47  5017.6   91.97  5070.6  104.67  5221.7  111.97  5256.7  112.17
  5321.7  115.94  5343.9  113.44  5362.3  114.91  5374.3  118.75  5414.8  115.81
  5607.2  119.35  5746.2  119.15  5824.3  118.27  5911.1  117.38  5956.4  117.98
#Mann= 12 ,-1 , 0
  3534.7     .12       0    3960     .07       0  4173.1     .12       0
  4942.4      .1       0    5002     .05       0  5017.6      .1       0
  5221.7     .07       0  5256.7      .1       0  5321.7     .05       0
  5746.2     .07       0  5824.3     .05       0  5911.1     .07       0
Bank Sta=5002,5017.6
XS Rating Curve= 0 ,0
Exp/Cntr=0.3,0.1

Type RM Length L Ch R = 1 ,59829   ,527,527,527
BEGIN DESCRIPTION:
Mapping XS 95626207
END DESCRIPTION:
XS GIS Cut Line= 3
      2574081.41     13482375.08      2572831.44     13481784.82
       2571749.1     13481576.67
#Sta/Elev= 30
  3611.3  117.25  3680.1  115.95    3776  114.33  3786.1  114.21  3955.3  112.03
  4097.9  110.74  4205.2  109.94    4277  109.86  4489.7  108.65  4634.4   107.6
  4741.7  107.23  4789.6  104.41  4863.5  105.11    4909  102.06  4937.3  102.38
  4954.5    99.3  4960.1  101.34  4977.3   95.46  4982.7   95.42  4991.3   89.41
  4991.8   88.91  5009.1   89.41  5010.4   93.68  5017.3   95.42  5061.3    94.9
  5074.3   99.75  5081.6  100.39  5216.7  105.22  5560.3   111.8  6095.8  115.06
#Mann= 15 ,-1 , 0
  3611.3     .12       0  3680.1     .07       0    3776     .12       0
  3786.1     .07       0  3955.3     .05       0  4097.9     .07       0
  4205.2     .12       0    4277     .05       0  4489.7     .07       0
  4634.4     .05       0  4741.7     .07       0  4982.7      .1       0
  4991.3     .05       0  5009.1      .1       0  5216.7     .05       0
Bank Sta=4991.3,5009.1
XS Rating Curve= 0 ,0
Exp/Cntr=0.3,0.1

Type RM Length L Ch R = 1 ,59302   ,659,659,659
BEGIN DESCRIPTION:
Mapping XS 4850b85f
END DESCRIPTION:
XS GIS Cut Line= 3
      2573956.47     13481805.67      2573192.55     13481368.15
      2571699.76     13481027.93
#Sta/Elev= 30
  3742.7  118.68  4052.8   114.1  4316.2   112.6  4375.2  110.05  4572.4  108.33
  4642.2  107.86    4731  107.12  4833.4  104.63  4907.7   103.2  4948.7  100.73
  4969.2   93.46  4974.5   90.25  4979.7   91.55  4980.8   89.39  4981.3   88.89
  4998.7   89.39    5000   91.16  5017.6      99    5041  101.17  5102.6   103.1
  5235.9  104.95  5297.4  107.78  5410.3   109.5  5482.1  112.26  5533.3  111.69
  5574.4  113.49  6046.2  120.63  6058.2     122  6087.2  120.98  6154.1  122.56
#Mann= 7 ,-1 , 0
  3742.7     .05       0  4572.4     .07       0  4642.2     .05       0
    4731     .07       0  4833.4     .05       0  4980.8     .05       0
  4998.7     .05       0
Bank Sta=4980.8,4998.7
XS Rating Curve= 0 ,0
Exp/Cntr=0.3,0.1

Type RM Length L Ch R = 1 ,58643   ,574,574,574
BEGIN DESCRIPTION:
Mapping XS 3dd88b69
END DESCRIPTION:
XS GIS Cut Line= 3
      2573970.29     13481319.52      2572803.66     13480645.93
      2571548.32     13480507.22
#Sta/Elev= 30
  3677.3  114.34  3778.9  113.77  3825.4  112.28    3834   112.1  4099.9   109.5
    4136   109.2    4438  105.66  4673.5  105.58    4688   104.6  4775.5  104.38
  4840.1   102.8  4893.2    99.3  4919.5    99.2  4924.8   99.03  4979.4   91.78
  4986.1   88.71  4986.6   88.21  5004.1   88.71  5020.8   92.62  5033.1   93.71
  5063.3  100.67  5093.5  103.62  5234.4  106.24  5524.4  108.23  5747.5  112.66
  5787.7  114.86    5838  115.36  5908.4  118.45  6059.3  122.06  6287.4  126.07
#Mann= 10 ,-1 , 0
  3677.3     .05       0  3825.4     .07       0    3834     .05       0
  4099.9     .07       0    4136     .05       0  4919.5     .12       0
  4924.8     .05       0  4986.1     .05       0  5004.1     .05       0
  5524.4     .07       0
Bank Sta=4986.1,5004.1
XS Rating Curve= 0 ,0
Exp/Cntr=0.3,0.1

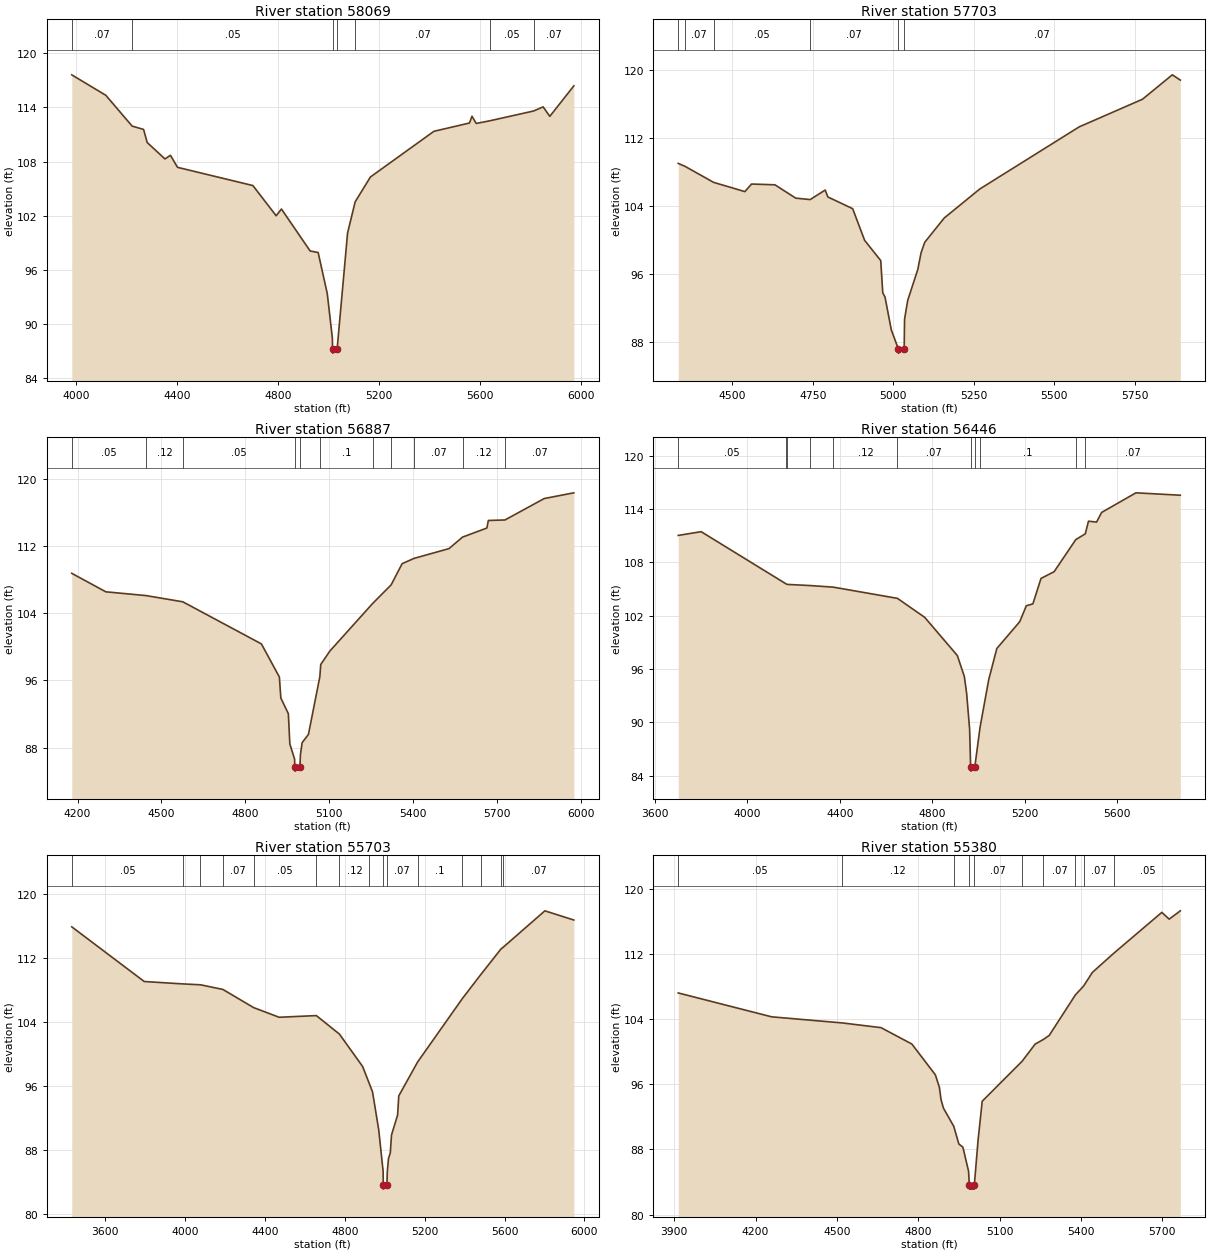
Type RM Length L Ch R = 1 ,58069   ,366,366,366
BEGIN DESCRIPTION:
Mapping XS f091ce8c
END DESCRIPTION:
XS GIS Cut Line= 3
      2573893.91     13480826.46      2573150.88     13480194.54
      2572143.96     13480090.37
#Sta/Elev= 30
  3983.2  117.61  4118.1  115.34  4222.1  111.93  4267.5  111.56  4281.8  110.11
    4352  108.29    4374  108.69  4401.8  107.36  4700.2  105.34  4792.5  101.99
  4813.3  102.74  4926.9   98.09  4958.6   97.92  4994.7   93.37  5014.8   88.47
  5015.8   87.27  5016.3   86.77  5033.9   87.27  5075.1  100.08  5105.2  103.54
  5165.6  106.29  5416.9  111.35  5557.7  112.27  5567.7  113.02  5584.3  112.22
  5638.9  112.52  5811.5   113.6  5849.2  114.06  5875.8  113.01  5970.9  116.39
#Mann= 7 ,-1 , 0
  3983.2     .07       0  4222.1     .05       0  5015.8     .05       0
  5033.9     .05       0  5105.2     .07       0  5638.9     .05       0
  5811.5     .07       0
Bank Sta=5015.8,5033.9
XS Rating Curve= 0 ,0
Exp/Cntr=0.3,0.1

Type RM Length L Ch R = 1 ,57703   ,816,816,816
BEGIN DESCRIPTION:
Mapping XS 280ff558
END DESCRIPTION:
XS GIS Cut Line= 3
      2573784.47     13480445.73      2573398.19     13479937.91
      2572500.74     13479729.81
#Sta/Elev= 30
  4332.1  108.99  4352.9  108.65  4441.8  106.76    4539  105.67  4559.8  106.56
  4632.5  106.47    4697   104.9  4741.8  104.73  4788.5  105.85  4796.8  105.04
  4873.8  103.66    4911   99.93    4961   97.55  4967.3   93.76  4974.3   93.25
  4993.9   89.38  5015.7   87.15  5016.2   86.65  5033.8   87.15    5035   90.64
  5044.8   92.86  5076.1    96.5  5086.3   98.47  5097.7    99.7  5158.2  102.56
  5268.4  105.97  5577.3  113.29  5774.1  116.55  5866.5  119.42  5891.4   118.8
#Mann= 6 ,-1 , 0
  4332.1     .05       0  4352.9     .07       0  4441.8     .05       0
  4741.8     .07       0  5015.7     .05       0  5033.8     .07       0
Bank Sta=5015.7,5033.8
XS Rating Curve= 0 ,0
Exp/Cntr=0.3,0.1

Type RM Length L Ch R = 1 ,56887   ,441,441,441
BEGIN DESCRIPTION:
Mapping XS e1ffcf50
END DESCRIPTION:
XS GIS Cut Line= 3
      2574157.74      13480224.4        2573906.     13479438.78
      2572978.56     13479148.41
#Sta/Elev= 30
  4179.1  108.73    4301  106.53    4445  106.08  4576.6  105.34  4857.8  100.33
  4922.1   96.39  4927.3   93.89  4954.2   92.03  4959.5   88.43  4976.5   86.63
  4977.3   85.69  4977.8   85.19  4995.5   85.69  4997.5   87.15  5003.4   88.57
  5026.1   89.56  5066.9   96.43  5070.1   97.88  5102.5   99.47  5256.1  105.15
  5322.1  107.36  5361.4  109.88  5404.3  110.51    5529  111.67  5577.6  113.04
  5664.7  114.12  5669.9  115.02  5729.5  115.08  5869.9  117.63  5975.9  118.31
#Mann= 11 ,-1 , 0
  4179.1     .05       0    4445     .12       0  4576.6     .05       0
  4977.3     .05       0  4995.5     .05       0  5066.9      .1       0
  5256.1     .07       0  5322.1      .1       0  5404.3     .07       0
  5577.6     .12       0  5729.5     .07       0
Bank Sta=4977.3,4995.5
XS Rating Curve= 0 ,0
Exp/Cntr=0.3,0.1

Type RM Length L Ch R = 1 ,56446   ,743,743,743
BEGIN DESCRIPTION:
Mapping XS e49326ab
END DESCRIPTION:
XS GIS Cut Line= 3
      2574442.55     13480514.03      2574287.94     13479247.81
      2573623.89     13478644.52
#Sta/Elev= 30
  3700.7  111.03  3799.9  111.45  4165.5  105.61  4172.1  105.52  4272.6  105.39
  4372.3  105.21  4649.4  103.95  4767.6  101.81  4908.6   97.52  4938.9   95.16
  4948.9   93.25  4961.7   89.24  4966.1   85.02  4966.6   84.52  4984.3   85.02
  5006.8   89.44  5044.3    94.8  5079.4   98.31  5178.7  101.33  5207.1  103.12
  5235.5  103.33  5270.6  106.19  5327.4  106.95  5421.2  110.56  5462.3  111.21
  5476.1  112.63  5511.2  112.53  5532.8  113.61  5681.5  115.82  5873.5  115.55
#Mann= 11 ,-1 , 0
  3700.7     .05       0  4165.5     .07       0  4172.1     .05       0
  4272.6     .07       0  4372.3     .12       0  4649.4     .07       0
  4966.1     .05       0  4984.3     .07       0  5006.8      .1       0
  5421.2     .12       0  5462.3     .07       0
Bank Sta=4966.1,4984.3
XS Rating Curve= 0 ,0
Exp/Cntr=0.3,0.1

Type RM Length L Ch R = 1 ,55703   ,323,323,323
BEGIN DESCRIPTION:
Mapping XS 06c24438
END DESCRIPTION:
XS GIS Cut Line= 3
      2575706.43     13480340.36      2574925.96     13478974.37
      2574128.71     13478471.75
#Sta/Elev= 30
  3431.7  115.85  3794.9  109.01  3989.1  108.71  4076.7   108.6    4189  108.02
  4342.7  105.75  4470.7  104.54  4657.2  104.75  4772.7  102.44    4889   98.39
    4923   96.22  4938.6   95.22  4969.7   90.48  4991.9   85.25  4992.4   83.55
  4992.9   83.05  5010.9   83.55  5012.6   85.19  5018.5   86.85  5027.8   87.61
  5033.8   89.82  5064.3   92.31  5070.2   94.71  5164.7   98.95  5389.4   106.9
  5480.6  109.86  5582.9   113.1  5592.1  113.27  5802.3  117.85  5947.4   116.7
#Mann= 15 ,-1 , 0
  3431.7     .05       0  3989.1     .07       0  4076.7     .05       0
    4189     .07       0  4342.7     .05       0  4657.2     .07       0
  4772.7     .12       0    4923     .07       0  4992.4     .05       0
  5010.9     .07       0  5164.7      .1       0  5389.4     .05       0
  5480.6     .07       0  5582.9     .05       0  5592.1     .07       0
Bank Sta=4992.4,5010.9
XS Rating Curve= 0 ,0
Exp/Cntr=0.3,0.1

Type RM Length L Ch R = 1 ,55380   ,272,272,272
BEGIN DESCRIPTION:
Mapping XS cb7b85d7
END DESCRIPTION:
XS GIS Cut Line= 3
      2575785.36     13479673.19      2575173.36     13478779.06
      2574519.03     13478376.06
#Sta/Elev= 30
  3914.7  107.21  4259.2  104.28  4519.8  103.53  4662.8  102.95  4776.5  100.94
  4863.2   97.16  4878.1   95.62  4884.1   94.12    4893   93.07  4931.2   90.83
  4949.8   88.67  4964.7   88.28  4985.7   85.32  4988.4   83.63  4988.9   83.13
  5006.4   83.13  5006.9   83.63  5020.6    89.1    5036   93.92  5183.3   98.83
  5231.2  100.93    5262  101.51  5283.2     102  5379.7  106.97  5409.8  108.05
  5442.6  109.74  5523.3  112.14  5698.5   117.1  5725.7  116.27  5766.7  117.29
#Mann= 10 ,-1 , 0
  3914.7     .05       0  4519.8     .12       0  4931.2     .07       0
  4988.4     .05       0  5006.9     .07       0  5183.3      .1       0
    5262     .07       0  5379.7     .12       0  5409.8     .07       0
  5523.3     .05       0
Bank Sta=4988.4,5006.9
XS Rating Curve= 0 ,0
Exp/Cntr=0.3,0.1

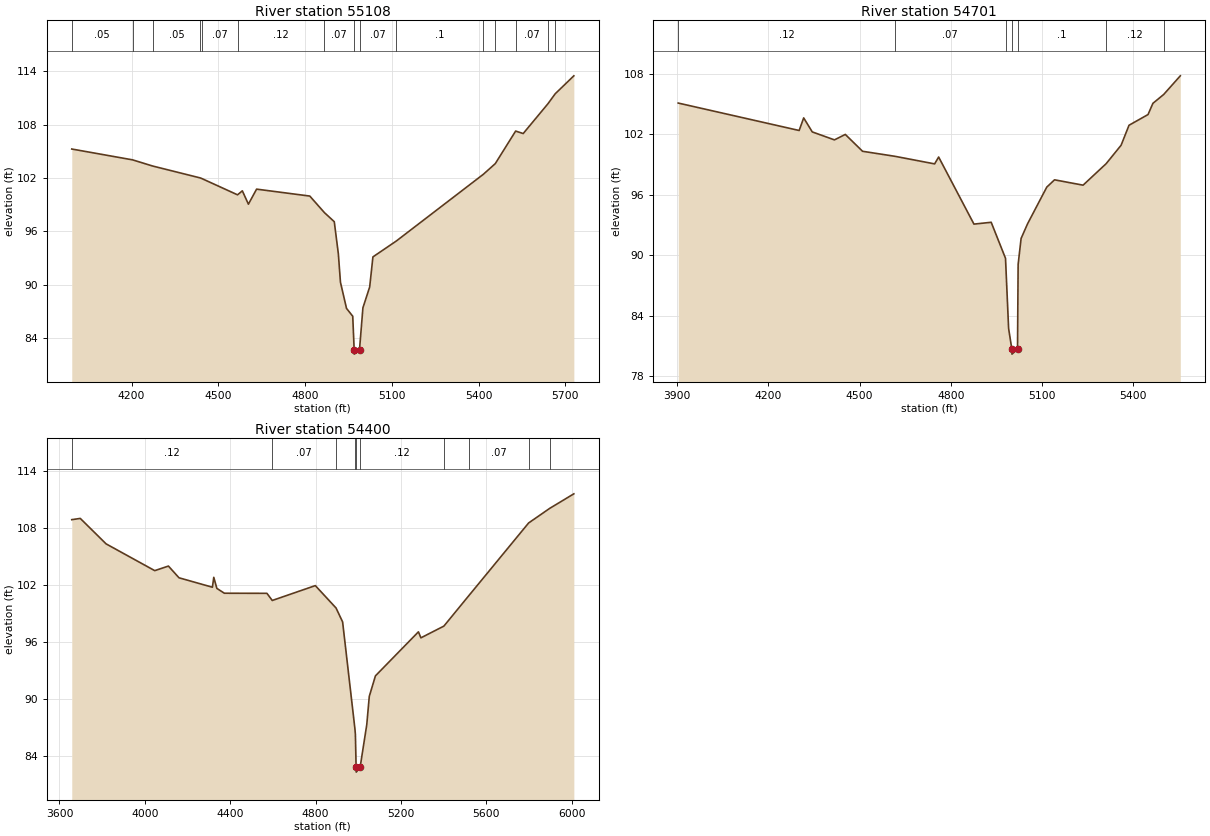
Type RM Length L Ch R = 1 ,55108   ,407,407,407
BEGIN DESCRIPTION:
Mapping XS 2b267b54
END DESCRIPTION:
XS GIS Cut Line= 3
      2576115.18     13479308.55      2575368.67     13478605.45
      2574752.77     13478249.79
#Sta/Elev= 30
    3993  105.26  4203.7  104.04  4272.6  103.35  4437.5  102.01  4443.6  101.93
  4566.4  100.11    4583  100.56    4604   99.06  4632.3  100.75  4816.4   99.97
  4866.9   98.11    4901   97.09  4915.1   93.49  4922.4   90.28  4943.4   87.34
  4964.9   86.46  4969.8    82.7  4970.3    82.2  4988.3    82.7  5000.1   87.41
  5023.5   89.75  5034.7   93.13  5115.7   94.92  5416.7  102.42    5458  103.62
  5528.4  107.28  5554.5     107  5640.1  110.35  5665.2  111.47  5729.7  113.49
#Mann= 15 ,-1 , 0
    3993     .05       0  4203.7     .07       0  4272.6     .05       0
  4437.5     .12       0  4443.6     .07       0  4566.4     .12       0
  4866.9     .07       0  4969.8     .05       0  4988.3     .07       0
  5115.7      .1       0  5416.7     .07       0    5458     .12       0
  5528.4     .07       0  5640.1     .05       0  5665.2     .07       0
Bank Sta=4969.8,4988.3
XS Rating Curve= 0 ,0
Exp/Cntr=0.3,0.1

Type RM Length L Ch R = 1 ,54701   ,301,301,301
BEGIN DESCRIPTION:
Mapping XS 13723b03
END DESCRIPTION:
XS GIS Cut Line= 3
       2576406.4     13478917.49      2575526.22     13478302.93
      2574979.66     13478115.54
#Sta/Elev= 30
  3903.4  105.08  4301.1  102.36    4316  103.61  4344.2  102.22  4417.2  101.43
  4452.9  101.97  4509.6   100.3  4616.4    99.8  4746.7   99.05  4759.9   99.73
    4876   93.08  4932.7   93.26  4979.8   89.69    4990   82.73  5000.6   80.69
  5001.1   80.19  5019.3   80.69  5021.3   89.08  5031.1   91.66  5052.5   93.12
  5115.6   96.75  5141.1   97.47  5234.9   96.94  5310.8   99.07    5360   100.9
    5386  102.88  5448.5  103.94  5464.5  105.05    5500  105.93  5554.7  107.78
#Mann= 7 ,-1 , 0
  3903.4     .12       0  4616.4     .07       0  4979.8      .1       0
  5000.6     .05       0  5019.3      .1       0  5310.8     .12       0
    5500     .07       0
Bank Sta=5000.6,5019.3
XS Rating Curve= 0 ,0
Exp/Cntr=0.3,0.1

Type RM Length L Ch R = 1 ,54400   ,655,655,655
BEGIN DESCRIPTION:
Mapping XS 967ea1c8
END DESCRIPTION:
XS GIS Cut Line= 3
      2576775.89     13478930.65      2575782.83     13478118.15
      2574728.63     13477937.83
#Sta/Elev= 30
  3657.5  108.85  3697.4  108.98  3818.3  106.31  4046.3   103.5  4110.4  103.98
    4160  102.75  4316.5  101.76  4322.9   102.8  4337.3  101.64  4372.5  101.13
    4572  101.12  4596.9  100.37  4798.8  101.93  4895.9   99.58  4926.6   98.12
  4984.2   86.92  4986.5   86.32  4989.9   82.86  4990.4   82.36  5008.6   82.86
  5039.8   87.34  5051.6   90.31  5080.4   92.46  5281.9   97.08  5293.5   96.45
  5401.1   97.68  5517.5  100.86  5798.1   108.5  5897.4  110.04  6010.1  111.56
#Mann= 10 ,-1 , 0
  3657.5     .12       0  4596.9     .07       0  4895.9      .1       0
  4984.2     .12       0  4989.9     .05       0  5008.6     .12       0
  5401.1     .12       0  5517.5     .07       0  5798.1     .12       0
  5897.4     .07       0
Bank Sta=4989.9,5008.6
XS Rating Curve= 0 ,0
Exp/Cntr=0.3,0.1