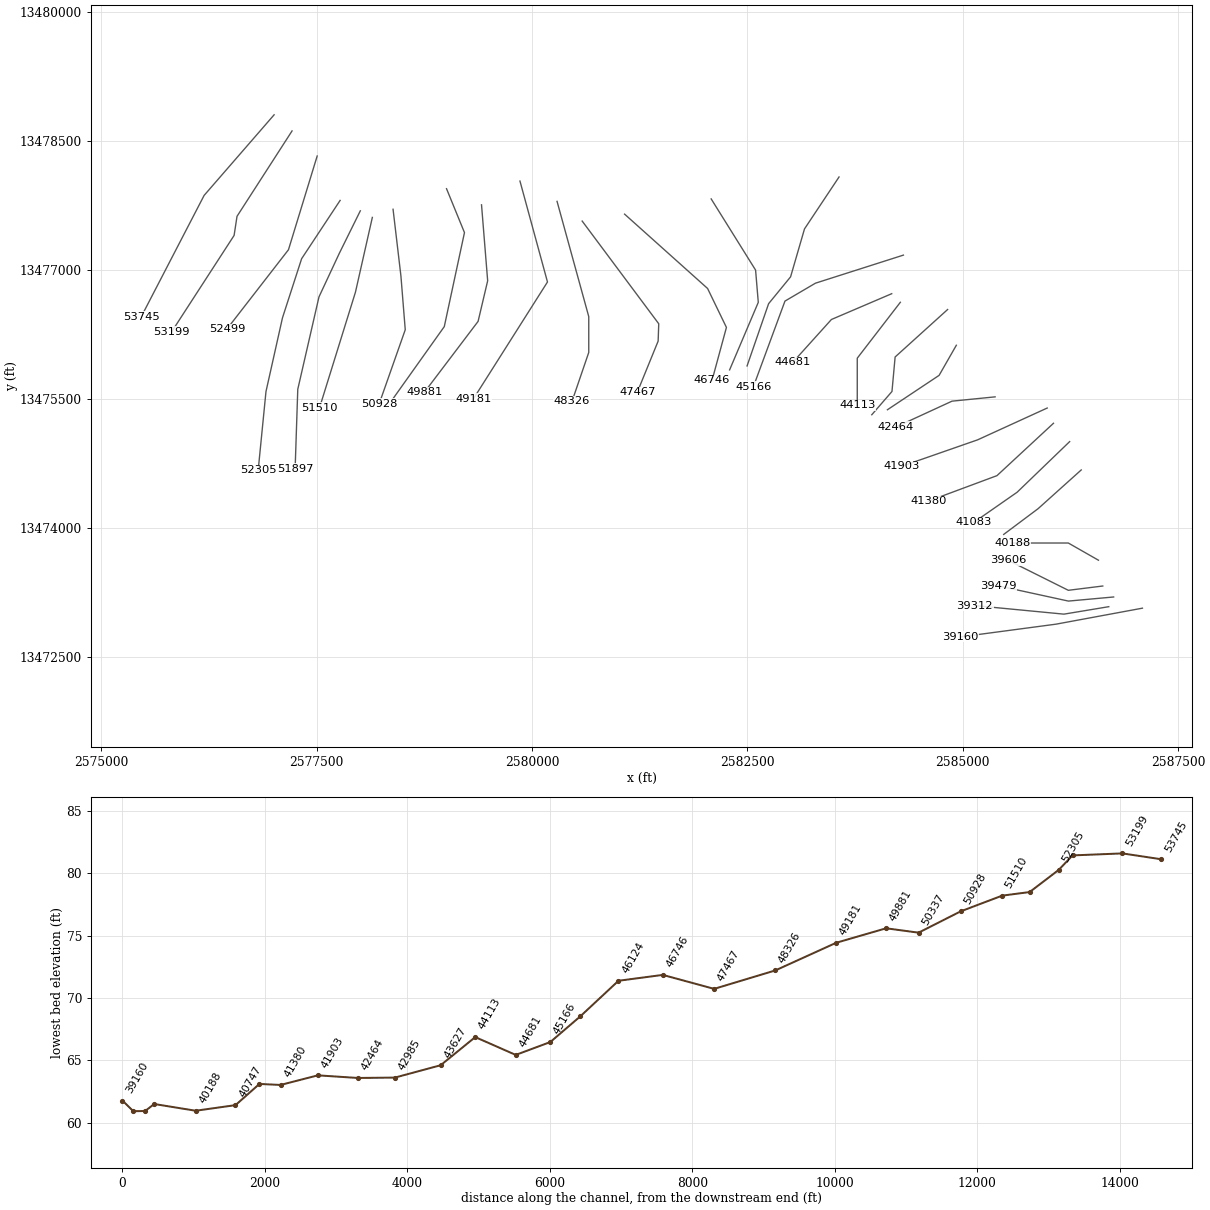
HEC-RAS study DRY CREEK.prj: DRY CREEK Base Level Engineering

--- DRY CREEK.g01 (geometry) --- (continued)

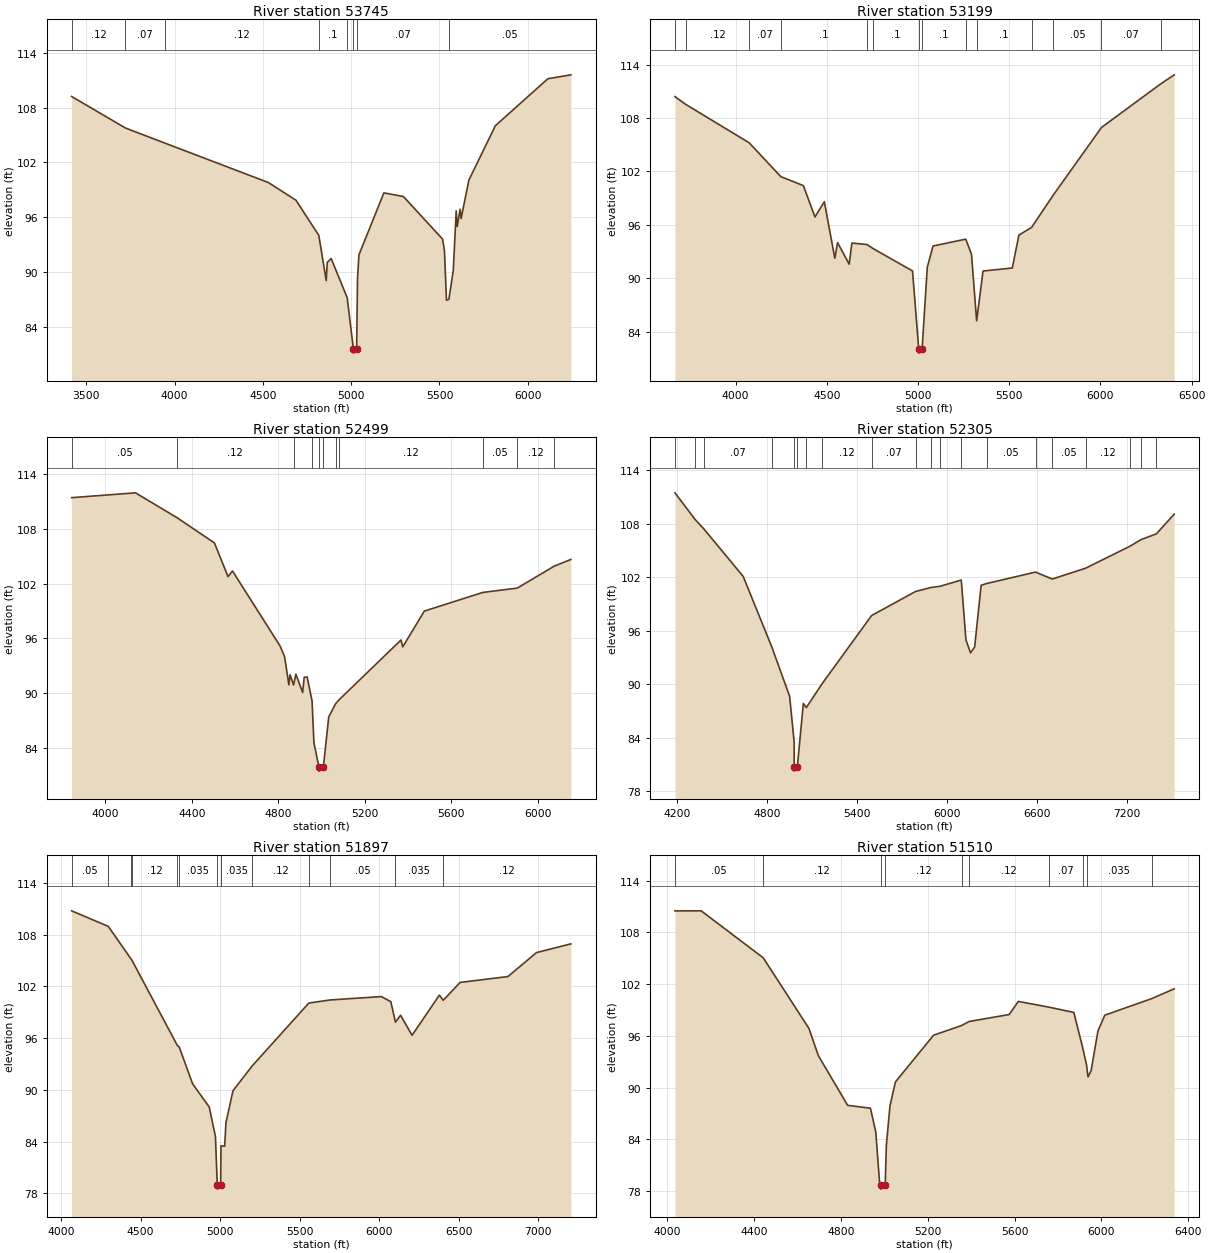
Type RM Length L Ch R = 1 ,53745   ,546,546,546
BEGIN DESCRIPTION:
Mapping XS 6edad23e
END DESCRIPTION:
XS GIS Cut Line= 3
      2577005.08     13478805.68      2576192.55     13477868.15
      2575463.78      13476459.2
#Sta/Elev= 30
  3417.1  109.22  3721.8  105.77  3946.2  104.11  4530.2   99.81  4687.2   97.87
  4816.7   94.02  4858.7   89.07  4864.4   91.05  4886.5   91.49  4977.3   87.21
  5012.2   81.63  5012.7   81.13  5030.9   81.63  5035.9   89.28  5044.1   91.89
  5185.2   98.67  5295.9   98.27  5517.4   93.61  5528.2   92.35  5539.5   86.93
  5553.3   87.02  5578.2   90.21  5594.7    96.7  5600.3   94.98  5616.8   96.88
  5622.4   95.86  5666.7  100.08  5816.1  106.01  6113.6  111.16    6244  111.59
#Mann= 8 ,-1 , 0
  3417.1     .12       0  3721.8     .07       0  3946.2     .12       0
  4816.7      .1       0  4977.3     .07       0  5012.2     .05       0
  5030.9     .07       0  5553.3     .05       0
Bank Sta=5012.2,5030.9
XS Rating Curve= 0 ,0
Exp/Cntr=0.3,0.1

Type RM Length L Ch R = 1 ,53199   ,700,700,700
BEGIN DESCRIPTION:
Mapping XS 321d55b9
END DESCRIPTION:
XS GIS Cut Line= 4
      2577213.36     13478618.11      2576574.49     13477625.09
      2576540.66     13477402.74      2575817.54     13476284.81
#Sta/Elev= 30
  3667.4   110.4  3725.7  109.54    4074  105.22  4248.1  101.41  4371.3  100.41
  4434.7   96.89  4486.2    98.6  4543.7   92.26  4558.9   94.01  4622.4   91.59
  4637.4   93.96  4719.4    93.8  4752.8   93.35  4969.6   90.83  5003.7    82.1
  5004.2    81.6  5022.4    82.1  5050.6   91.24  5082.3   93.63  5261.6    94.4
    5293   92.69  5321.2   85.23  5356.3   90.82  5516.6   91.16  5552.9   94.85
  5622.5   95.72  5742.1   99.37  6005.7  106.94    6331  111.84  6404.5  112.85
#Mann= 14 ,-1 , 0
  3667.4     .07       0  3725.7     .12       0    4074     .07       0
  4248.1      .1       0  4719.4     .12       0  4752.8      .1       0
  5003.7     .05       0  5022.4      .1       0  5261.6     .07       0
  5321.2      .1       0  5622.5     .12       0  5742.1     .05       0
  6005.7     .07       0    6331     .05       0
Bank Sta=5003.7,5022.4
XS Rating Curve= 0 ,0
Exp/Cntr=0.3,0.1

Type RM Length L Ch R = 1 ,52499   ,194,194,194
BEGIN DESCRIPTION:
Mapping XS 08c83ce7
END DESCRIPTION:
XS GIS Cut Line= 3
      2577505.04     13478326.46      2577171.72     13477236.21
      2576456.42     13476312.57
#Sta/Elev= 30
  3844.3  111.41  4139.5  111.94  4331.9  109.21  4504.6  106.45  4567.4  102.76
  4588.3  103.37  4807.9   95.16  4828.8   93.99  4848.9    90.9  4854.2      92
  4870.6   90.88  4881.1   92.07  4912.4   90.06  4919.7   91.73  4933.3   91.76
  4955.9   89.14  4964.7   84.53  4987.4   81.94  4987.9   81.44  5008.4   81.94
  5033.2   87.39    5065   88.83  5079.2   89.22  5367.2   95.81  5375.4   95.06
    5475   98.98  5744.7  101.02  5904.9   101.5  6074.5  103.89  6152.6  104.64
#Mann= 11 ,-1 , 0
  3844.3     .05       0  4331.9     .12       0  4870.6      .1       0
  4955.9     .12       0  4987.4     .05       0  5008.4     .12       0
    5065      .1       0  5079.2     .12       0  5744.7     .05       0
  5904.9     .12       0  6074.5     .05       0
Bank Sta=4987.4,5008.4
XS Rating Curve= 0 ,0
Exp/Cntr=0.3,0.1

Type RM Length L Ch R = 1 ,52305   ,408,408,408
BEGIN DESCRIPTION:
Mapping XS 57809e2f
END DESCRIPTION:
XS GIS Cut Line= 5
       2577771.3     13477809.82      2577324.49     13477132.04
      2577102.27     13476444.54      2576910.67      13475586.6
      2576819.94     13474669.37
#Sta/Elev= 30
  4183.3  111.46  4317.3  108.48  4376.1  107.42  4639.1  102.09  4829.9    94.2
  4949.2   88.67  4979.3   83.56  4979.8   80.78  4980.3   80.28  5000.8   80.78
  5040.7   87.86  5060.7    87.4  5165.2   90.05  5496.7   97.71  5790.6  100.41
  5892.3  100.85  5954.2  100.99  6095.7  101.69    6127   94.99  6157.7   93.53
  6185.1   94.19  6228.5   101.1    6268  101.31  6591.9  102.58  6703.2   101.8
    6927  103.02  7220.5  105.46  7299.5  106.24  7398.8  106.86  7518.4  109.07
#Mann= 20 ,-1 , 0
  4183.3     .07       0  4317.3     .12       0  4376.1     .07       0
  4829.9      .1       0  4979.8     .05       0  5000.8      .1       0
  5060.7      .1       0  5165.2     .12       0  5496.7     .07       0
  5790.6     .12       0  5892.3    .035       0  5954.2     .12       0
  6095.7     .05       0    6268     .05       0  6591.9    .035       0
  6703.2     .05       0    6927     .12       0  7220.5    .035       0
  7299.5     .12       0  7398.8    .035       0
Bank Sta=4979.8,5000.8
XS Rating Curve= 0 ,0
Exp/Cntr=0.3,0.1

Type RM Length L Ch R = 1 ,51897   ,387,387,387
BEGIN DESCRIPTION:
Mapping XS fd8f34c0
END DESCRIPTION:
XS GIS Cut Line= 5
      2578005.84     13477688.91      2577761.99     13477194.54
      2577525.88     13476687.59      2577279.78     13475613.15
      2577249.09      13474689.3
#Sta/Elev= 30
  4067.2  110.76  4297.4  108.96  4442.4  105.13  4447.4  104.99  4731.3   95.16
  4743.8   94.95  4827.5    90.7  4931.7   88.03  4970.9    84.6  4982.4      79
  4982.9    78.5  5003.5      79  5005.8   83.53  5028.7   83.48  5037.1   86.22
  5081.2   89.91    5203   92.81  5557.8  100.07  5693.2  100.43  6013.3  100.82
  6072.9  100.23    6102   97.86  6134.4   98.66  6206.2   96.33  6378.1  100.99
  6402.1  100.39  6508.2  102.46  6808.4  103.14  6988.5  105.92  7204.3  106.93
#Mann= 13 ,-1 , 0
  4067.2     .05       0  4297.4     .12       0  4442.4     .07       0
  4447.4     .12       0  4731.3     .07       0  4743.8    .035       0
  4982.4    .035       0  5003.5    .035       0    5203     .12       0
  5557.8    .035       0  5693.2     .05       0    6102    .035       0
  6402.1     .12       0
Bank Sta=4982.4,5003.5
XS Rating Curve= 0 ,0
Exp/Cntr=0.3,0.1

Type RM Length L Ch R = 1 ,51510   ,582,582,582
BEGIN DESCRIPTION:
Mapping XS 69ca5cbd
END DESCRIPTION:
XS GIS Cut Line= 3
      2578145.45     13477612.18      2577949.49     13476743.15
       2577532.8     13475399.63
#Sta/Elev= 30
  4037.4  110.49  4157.9   110.5  4443.5  105.05  4653.9   96.85  4697.2    93.7
    4832   87.93  4936.8    87.6  4961.6   84.82  4978.7   79.03  4983.7   78.71
  4984.2   78.21  5004.8   78.71  5010.1   83.29  5026.8   87.88  5051.9   90.65
  5227.5   96.07  5356.2   97.19    5391   97.66  5575.4   98.47  5617.3   99.99
  5759.1   99.32  5872.8   98.71    5913   94.68  5931.2   92.64    5938   91.23
  5952.4   91.97  5983.8   96.55  6015.2   98.39  6230.8  100.31  6334.9  101.45
#Mann= 10 ,-1 , 0
  4037.4     .05       0  4443.5     .12       0  4983.7     .05       0
  5004.8     .12       0  5356.2     .07       0    5391     .12       0
  5759.1     .07       0    5913     .12       0  5931.2    .035       0
  6230.8     .12       0
Bank Sta=4983.7,5004.8
XS Rating Curve= 0 ,0
Exp/Cntr=0.3,0.1

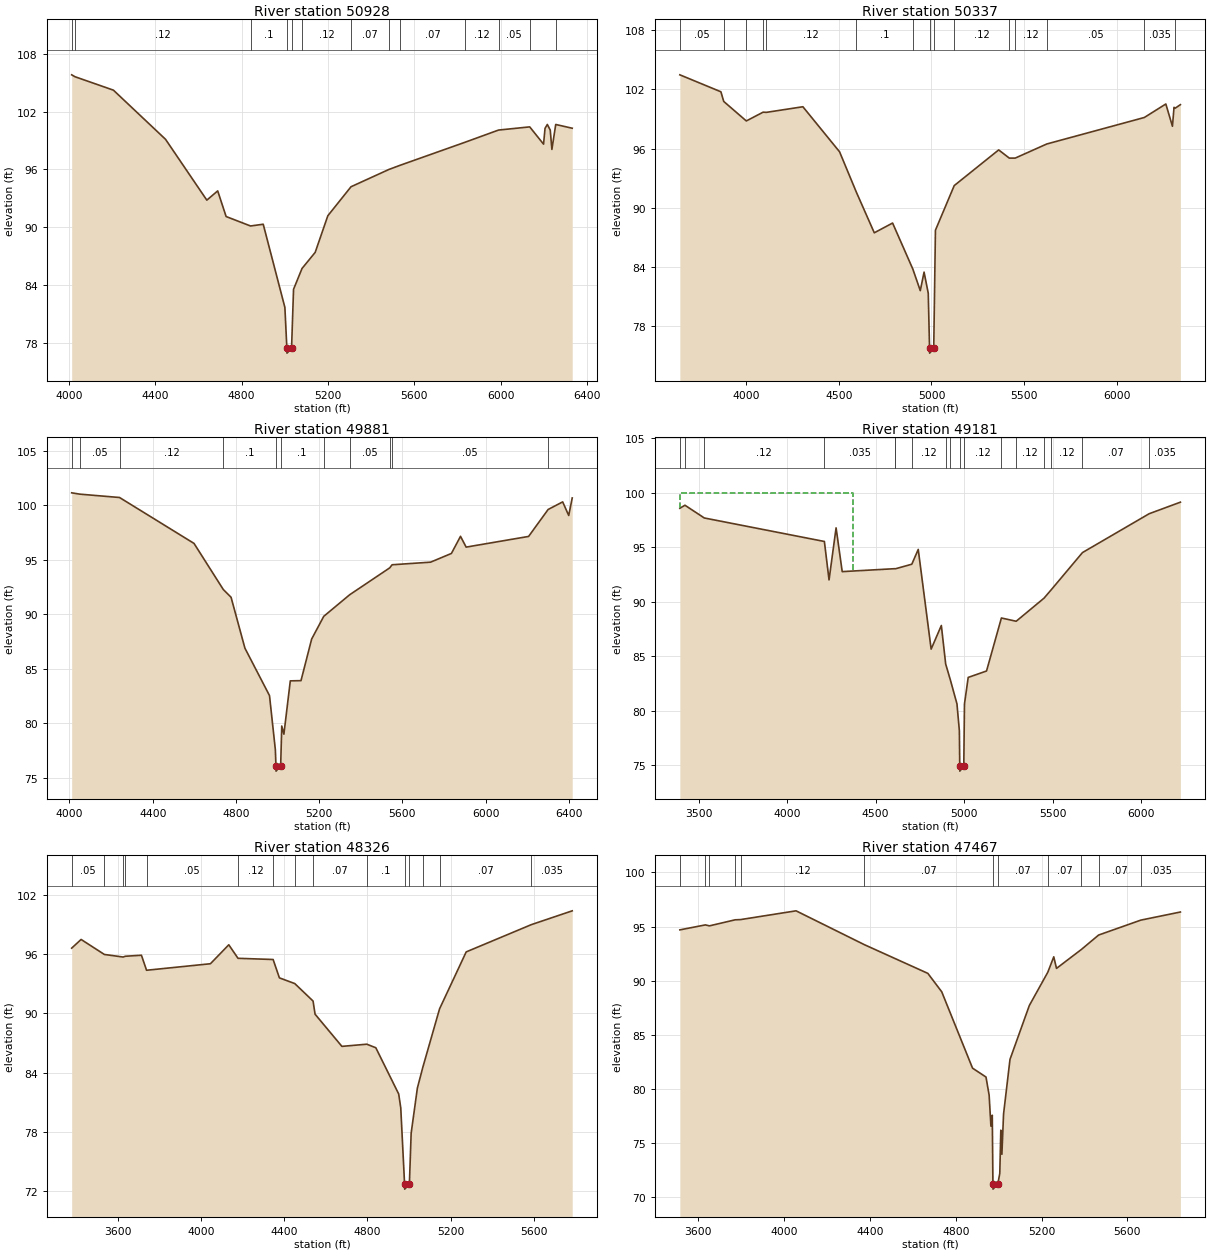
Type RM Length L Ch R = 1 ,50928   ,591,591,591
BEGIN DESCRIPTION:
Mapping XS c62ab30c
END DESCRIPTION:
XS GIS Cut Line= 4
      2578385.93     13477707.05      2578477.27     13476930.65
      2578527.48     13476305.53       2578225.4     13475446.17
#Sta/Elev= 30
  4012.3  105.82  4027.9  105.62  4205.7  104.23  4447.3   99.13  4638.6   92.82
    4689   93.78    4728   91.12  4841.1   90.14    4900   90.32  5000.4   81.69
  5009.6   77.45  5010.1   76.95  5031.3   77.45  5040.5   83.57  5079.8   85.73
  5140.8    87.4  5199.4    91.2  5306.9   94.21  5482.2      96    5535   96.44
  5833.5   98.81  5990.6  100.09  6135.1  100.42  6199.2   98.63  6206.1  100.27
  6216.7  100.67  6230.2  100.09  6237.9   98.08  6255.7  100.67  6332.1  100.28
#Mann= 13 ,-1 , 0
  4012.3     .07       0  4027.9     .12       0  4841.1      .1       0
  5009.6     .05       0  5031.3      .1       0  5079.8     .12       0
  5306.9     .07       0  5482.2     .12       0    5535     .07       0
  5833.5     .12       0  5990.6     .05       0  6135.1    .035       0
  6255.7     .12       0
Bank Sta=5009.6,5031.3
XS Rating Curve= 0 ,0
Exp/Cntr=0.3,0.1

Type RM Length L Ch R = 1 ,50337   ,456,456,456
BEGIN DESCRIPTION:
Mapping XS 8ed56048
END DESCRIPTION:
XS GIS Cut Line= 4
      2579006.63     13477946.19      2579214.98     13477435.74
      2578980.61     13476341.99      2578382.25     13475499.09
#Sta/Elev= 30
  3640.8  103.48  3862.5  101.76  3877.8  100.78  3999.7    98.8  4090.6   99.69
  4107.7   99.67  4305.4  100.24  4503.5   95.67  4593.8   91.59    4691   87.45
  4789.9   88.44    4899   83.78  4939.5   81.58  4959.9   83.46  4982.5   81.32
  4989.5   75.74    4990   75.24  5012.1   75.74  5021.3   87.71  5122.8   92.24
  5362.9   95.86  5420.2   95.03  5452.3   95.03  5622.4   96.46  6149.6   99.15
  6265.8  100.52  6301.5   98.26  6310.1  100.18  6315.9  100.09  6344.4  100.45
#Mann= 15 ,-1 , 0
  3640.8     .05       0  3877.8    .033       0  3999.7      .1       0
  4090.6     .05       0  4107.7     .12       0  4593.8      .1       0
    4899     .12       0  4989.5     .05       0  5012.1     .12       0
  5122.8     .12       0  5420.2      .1       0  5452.3     .12       0
  5622.4     .05       0  6149.6    .035       0  6315.9     .12       0
Bank Sta=4989.5,5012.1
XS Rating Curve= 0 ,0
Exp/Cntr=0.3,0.1

Type RM Length L Ch R = 1 ,49881   ,700,700,700
BEGIN DESCRIPTION:
Mapping XS fac54a84
END DESCRIPTION:
XS GIS Cut Line= 4
       2579412.9     13477758.66      2579484.22     13476875.09
       2579373.1     13476402.87      2578749.06     13475577.74
#Sta/Elev= 30
  4010.6  101.12  4049.2     101  4240.7  100.69  4598.6   96.48  4739.4   92.25
  4776.7   91.54  4843.3   86.87  4961.5   82.52  4989.6   77.56  4992.5   76.09
    4993   75.59  5015.2   76.09  5020.4   79.73  5030.7   78.98  5061.5   83.87
  5112.9   83.89  5164.2   87.71  5222.3   89.79  5346.9   91.77  5539.7   94.24
  5550.7   94.52  5736.1   94.76    5836   95.56  5879.7   97.13  5906.8   96.14
    6207   97.12  6300.8   99.59  6370.8  100.29  6399.9   99.04  6416.7  100.65
#Mann= 11 ,-1 , 0
  4010.6     .07       0  4049.2     .05       0  4240.7     .12       0
  4739.4      .1       0  4992.5     .05       0  5015.2      .1       0
  5222.3     .12       0  5346.9     .05       0  5539.7     .12       0
  5550.7     .05       0  6300.8    .035       0
Bank Sta=4992.5,5015.2
XS Rating Curve= 0 ,0
Exp/Cntr=0.3,0.1

Type RM Length L Ch R = 1 ,49181   ,855,855,855
BEGIN DESCRIPTION:
Mapping XS cb3def4d
END DESCRIPTION:
XS GIS Cut Line= 3
       2579859.2     13478034.86      2580178.66     13476861.21
      2579317.54     13475500.08
#Sta/Elev= 30
  3394.6   98.58  3423.3   98.86  3532.6   97.69  4210.9   95.53  4237.2      92
    4277   96.78  4311.6   92.76  4608.7   93.03  4611.9   93.02  4704.6   93.44
    4741    94.8  4813.9   85.64  4871.5   87.81    4896   84.27  4921.9   82.84
  4959.7   80.61  4973.3   78.14  4975.4   74.93  4975.9   74.43  4998.2   74.93
  5002.1    80.6  5023.2   83.04  5126.7   83.63  5210.7    88.5  5294.2    88.2
  5451.3   90.32  5492.5    91.1  5668.6   94.51  6045.2   98.08  6221.6   99.14
#Mann= 17 ,-1 , 0
  3394.6     .05       0  3423.3     .07       0  3532.6     .12       0
  4210.9    .035       0  4608.7     .12       0  4611.9    .035       0
  4704.6     .12       0    4896      .1       0  4921.9     .12       0
  4975.4     .05       0  4998.2     .12       0  5210.7      .1       0
  5294.2     .12       0  5451.3     .07       0  5492.5     .12       0
  5668.6     .07       0  6045.2    .035       0
#XS Ineff= 1 ,-1
    3394    4372     100
Permanent Ineff=
       F
Bank Sta=4975.4,4998.2
XS Rating Curve= 0 ,0
Exp/Cntr=0.3,0.1

Type RM Length L Ch R = 1 ,48326   ,859,859,859
BEGIN DESCRIPTION:
Mapping XS 5f17a0ad
END DESCRIPTION:
XS GIS Cut Line= 4
      2580289.78     13477798.68      2580657.83     13476458.43
      2580657.83     13476041.76      2580463.37     13475472.28
#Sta/Elev= 30
  3377.2   96.62  3422.5    97.5  3534.5   95.98  3624.7   95.72  3635.9    95.8
  3712.8    95.9  3737.4   94.38  4044.7   95.04  4133.1   96.96  4177.4   95.59
  4346.4   95.47  4376.6   93.61  4450.6   93.03  4538.6   91.26  4548.2   89.93
  4677.3   86.67  4797.2   86.89  4840.5   86.53  4950.5   81.85  4960.5   80.45
  4978.9   72.71  4979.4   72.21    5002   72.71  5010.5   77.87  5040.5   82.45
  5066.8   84.56  5147.2   90.47  5275.4   96.24  5588.7      99  5785.5   100.4
#Mann= 15 ,-1 , 0
  3377.2     .05       0  3534.5     .12       0  3624.7     .05       0
  3635.9    .035       0  3737.4     .05       0  4177.4     .12       0
  4346.4     .07       0  4450.6     .12       0  4538.6     .07       0
  4797.2      .1       0  4978.9     .05       0    5002      .1       0
  5066.8     .12       0  5147.2     .07       0  5588.7    .035       0
Bank Sta=4978.9,5002
XS Rating Curve= 0 ,0
Exp/Cntr=0.3,0.1

Type RM Length L Ch R = 1 ,47467   ,721,721,721
BEGIN DESCRIPTION:
Mapping XS 0f11678b
END DESCRIPTION:
XS GIS Cut Line= 4
      2580581.44     13477569.54      2581470.33     13476375.09
      2581463.38     13476173.71      2581221.04     13475578.24
#Sta/Elev= 30
  3513.8   94.69    3633   95.15  3651.5   95.06  3771.9   95.62  3796.9   95.64
  4055.5   96.45  4374.1   93.32  4669.8   90.67  4734.5   88.97  4878.2   81.91
  4940.9   81.09  4955.5   79.42  4963.9   76.55  4970.2   77.56  4973.2   71.23
  4973.7   70.73  4996.3   71.23  5005.2   72.18    5010   76.18    5015   73.95
  5022.8   77.67  5052.8   82.72  5142.9    87.7  5229.2   90.78  5256.8    92.2
  5269.6   91.13  5385.6   92.88  5465.8   94.21  5662.6   95.59  5847.1   96.34
#Mann= 12 ,-1 , 0
  3513.8     .07       0    3633     .05       0  3651.5     .07       0
  3771.9     .05       0  3796.9     .12       0  4374.1     .07       0
  4973.2     .05       0  4996.3     .07       0  5229.2     .07       0
  5385.6     .12       0  5465.8     .07       0  5662.6    .035       0
Bank Sta=4973.2,4996.3
XS Rating Curve= 0 ,0
Exp/Cntr=0.3,0.1

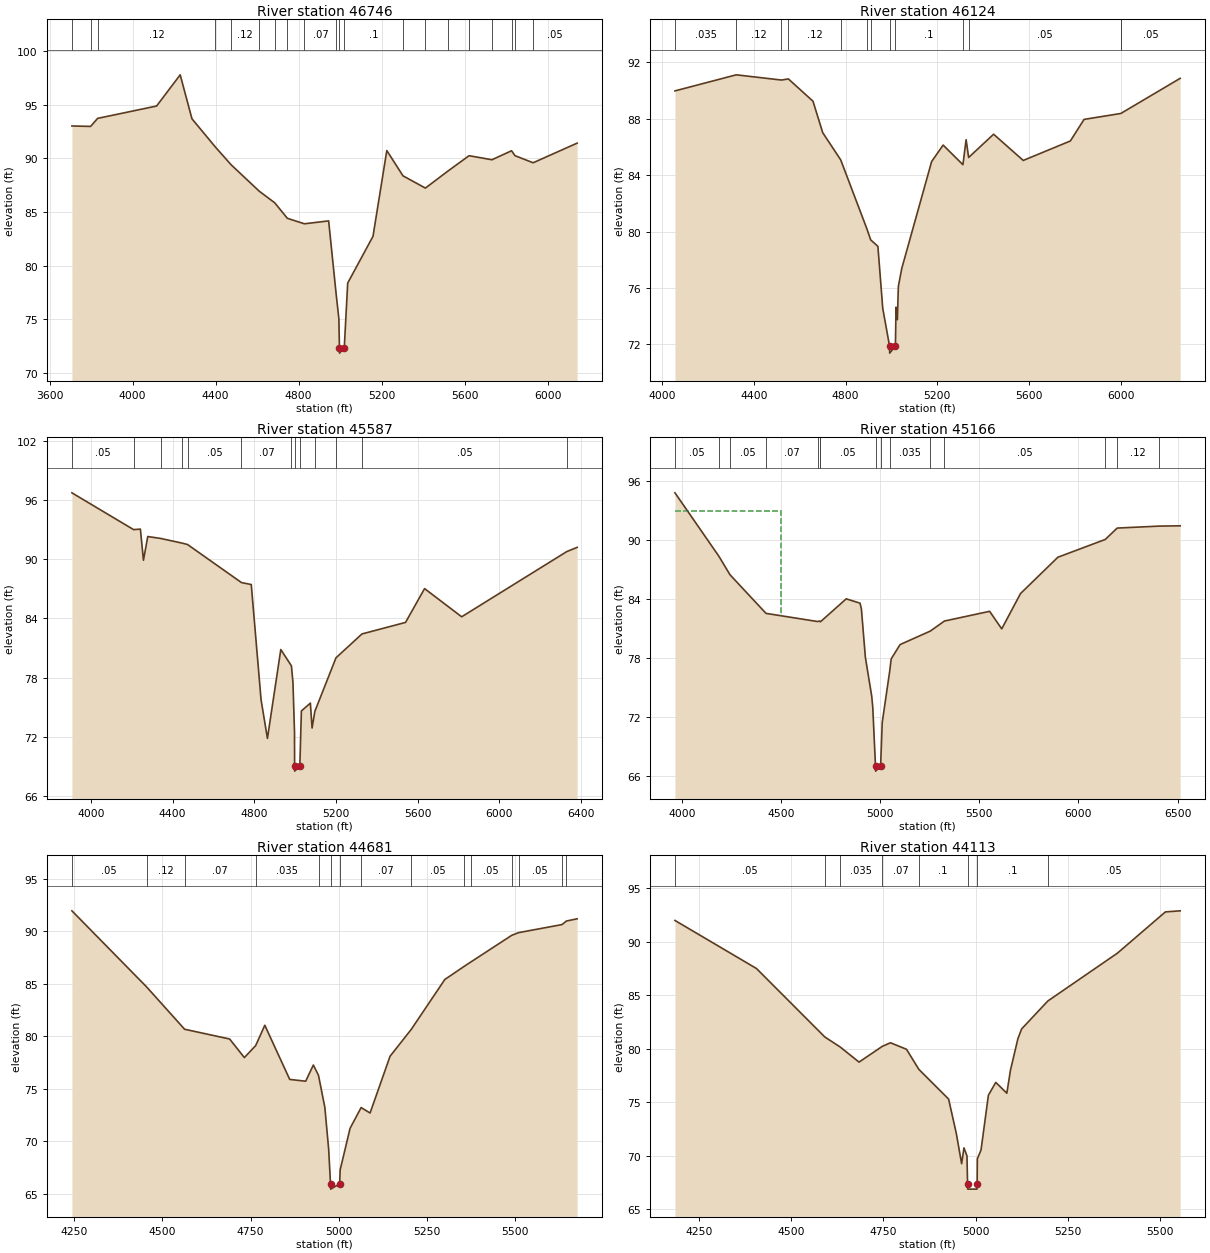
Type RM Length L Ch R = 1 ,46746   ,622,622,622
BEGIN DESCRIPTION:
Mapping XS 966a3bfd
END DESCRIPTION:
XS GIS Cut Line= 4
       2581073.8     13477650.27      2582037.34     13476785.69
      2582256.09     13476332.57      2582089.43       13475718.
#Sta/Elev= 30
  3707.6   93.03  3797.7   92.99  3831.6   93.74  4115.6   94.89  4229.3    97.8
  4286.1    93.7  4398.4   91.08  4474.9   89.41  4610.3   86.95  4684.8   85.87
  4745.8   84.42    4828   83.91  4944.7   84.18  4981.1   77.32    4994   75.06
  4996.7   72.35  4997.2   71.85    5020   72.35  5036.5   78.38  5158.4   82.74
    5225   90.74    5303   88.38    5411   87.24  5518.4   88.81  5621.4   90.26
  5731.6   89.88  5826.2   90.72  5842.8   90.26  5930.2    89.6  6142.1   91.43
#Mann= 20 ,-1 , 0
  3707.6     .12       0  3797.7      .1       0  3831.6     .12       0
  4398.4     .07       0  4474.9     .12       0  4610.3     .07       0
  4684.8     .12       0  4745.8      .1       0    4828     .07       0
  4981.1      .1       0  4996.7     .05       0    5020      .1       0
    5303     .07       0    5411     .12       0  5518.4     .07       0
  5621.4     .05       0  5731.6    .035       0  5826.2     .05       0
  5842.8    .035       0  5930.2     .05       0
Bank Sta=4996.7,5020
XS Rating Curve= 0 ,0
Exp/Cntr=0.3,0.1

Type RM Length L Ch R = 1 ,46124   ,537,537,537
BEGIN DESCRIPTION:
Mapping XS 4350baa3
END DESCRIPTION:
XS GIS Cut Line= 4
      2582079.03     13477827.32      2582594.63     13476999.23
      2582625.88     13476624.23        2582293.     13475838.85
#Sta/Elev= 30
  4055.2   89.97  4322.6   91.11  4520.1   90.74  4550.2   90.82  4657.6   89.24
  4700.1   87.01  4778.6   85.08  4892.7    80.2  4909.4   79.41  4940.9   78.95
  4962.1   74.55  4991.8   71.88  4992.3   71.38  5017.4   71.88    5020   74.64
  5025.9   73.75  5030.2   76.11    5045   77.38  5175.4   84.96  5225.6   86.13
  5311.9   84.74  5325.9   86.51  5336.9   85.25  5445.9    86.9  5575.2   85.04
  5780.8   86.42  5840.6   87.95  6000.9   88.37    6001   88.37    6260   90.86
#Mann= 13 ,-1 , 0
  4055.2    .035       0  4322.6     .12       0  4520.1     .05       0
  4550.2     .12       0  4778.6    .035       0  4892.7     .12       0
  4909.4      .1       0  4991.8     .05       0  5017.4      .1       0
  5311.9     .12       0  5336.9     .05       0  6000.9    .035       0
    6001     .05       0
Bank Sta=4991.8,5017.4
XS Rating Curve= 0 ,0
Exp/Cntr=0.3,0.1

Type RM Length L Ch R = 1 ,45587   ,421,421,421
BEGIN DESCRIPTION:
Mapping XS db38ef9c
END DESCRIPTION:
XS GIS Cut Line= 5
      2583563.38     13478082.57      2583162.34      13477478.4
      2583000.88     13476921.11      2582745.67     13476608.61
      2582495.69      13475884.7
#Sta/Elev= 30
  3906.5   96.74  4208.5   93.01  4241.9   93.06  4256.9    89.9    4278   92.31
  4342.3   92.11  4446.3   91.64  4472.8    91.5  4736.9   87.64    4785   87.44
    4833   75.76  4864.2   71.84  4929.7   80.85  4981.6    79.2  4989.2   77.53
  4996.9   72.42  4997.2   69.02  4997.7   68.52  5022.9   69.02  5030.5   74.62
  5074.5   75.42  5082.9   72.89  5096.5   74.58    5200   80.01  5327.2   82.43
  5540.7    83.6  5633.9   87.03  5815.7   84.17  6330.4   90.78  6381.2   91.21
#Mann= 13 ,-1 , 0
  3906.5     .05       0  4208.5    .035       0  4342.3     .05       0
  4446.3     .07       0  4472.8     .05       0  4736.9     .07       0
  4981.6      .1       0  4997.2     .05       0  5022.9      .1       0
  5096.5     .12       0    5200    .035       0  5327.2     .05       0
  6330.4     .12       0
Bank Sta=4997.2,5022.9
XS Rating Curve= 0 ,0
Exp/Cntr=0.3,0.1

Type RM Length L Ch R = 1 ,45166   ,485,485,485
BEGIN DESCRIPTION:
Mapping XS 3d966a00
END DESCRIPTION:
XS GIS Cut Line= 4
      2584310.57     13477173.69      2583289.77     13476847.32
       2582935.6     13476638.98      2582567.75     13475639.53
#Sta/Elev= 30
  3965.6   94.81  4186.8   88.36    4243   86.47  4424.8   82.53  4684.7    81.7
  4695.1   81.75  4699.1   81.67  4829.3   84.01  4898.9   83.57  4905.8   82.98
  4925.8   78.06  4957.9   74.09  4963.2   72.94  4976.9   66.96  4977.4   66.46
  5002.7   66.96  5010.8   71.41  5048.6   76.65    5056   77.89  5100.8   79.35
  5252.7   80.72  5324.7   81.75  5552.5   82.74  5613.4   80.95  5708.2   84.55
  5896.7   88.25  6135.4   90.06  6195.9   91.22  6408.2   91.42  6513.2   91.45
#Mann= 15 ,-1 , 0
  3965.6     .05       0  4186.8    .035       0    4243     .05       0
  4424.8     .07       0  4684.7     .05       0  4695.1     .07       0
  4699.1     .05       0  4976.9     .05       0  5002.7     .05       0
  5048.6    .035       0  5252.7     .07       0  5324.7     .05       0
  6135.4     .07       0  6195.9     .12       0  6408.2     .05       0
#XS Ineff= 1 ,-1
    3965    4500      93
Permanent Ineff=
       F
Bank Sta=4976.9,5002.7
XS Rating Curve= 0 ,0
Exp/Cntr=0.3,0.1

Type RM Length L Ch R = 1 ,44681   ,568,568,568
BEGIN DESCRIPTION:
DRY CREEK 61.0
END DESCRIPTION:
XS GIS Cut Line= 3
      2584174.97     13476724.99        2583475.       13476425.
      2583025.01     13475925.02
#Sta/Elev= 30
    4243   91.94  4455.1   84.69  4562.9   80.66  4690.8   79.73  4732.5   77.96
  4764.6    79.1  4790.6   81.04  4861.3   75.88  4906.6   75.71  4928.4   77.25
    4943   76.27    4961   73.22  4971.9   69.21  4977.1   65.93  4977.6   65.43
    5003   65.93  5004.5   67.26  5032.6   71.22    5064    73.2  5089.4   72.68
  5146.2   78.09  5206.6   80.66  5301.6    85.4  5356.6   86.65  5374.7   87.05
  5491.7   89.61  5510.8   89.86  5634.2   90.63  5646.9   90.97  5677.2   91.18
#Mann= 15 ,-1 , 0
    4243     .05       0  4455.1     .12       0  4562.9     .07       0
  4764.6    .035       0    4943     .12       0  4977.1     .05       0
    5003     .12       0    5064     .07       0  5206.6     .05       0
  5356.6    .035       0  5374.7     .05       0  5491.7    .035       0
  5510.8     .05       0  5634.2    .035       0  5646.9     .05       0
Bank Sta=4977.1,5003
XS Rating Curve= 0 ,0
Exp/Cntr=0.3,0.1

Type RM Length L Ch R = 1 ,44113   ,486,486,486
BEGIN DESCRIPTION:
DRY CREEK 60.0
END DESCRIPTION:
XS GIS Cut Line= 3
      2584274.97     13476624.96        2583775.       13475975.
        2583775.     13475425.02
#Sta/Elev= 30
  4184.5   92.01  4405.6   87.51    4591    81.1  4632.3   80.17  4683.7   78.75
  4746.6   80.22  4768.9   80.56  4812.4   79.95  4845.9   78.07  4926.6   75.29
  4947.4   72.09  4961.9   69.24  4968.2   70.72  4976.4   69.97    4978   67.36
  4978.5   66.86  5003.5   66.86    5004   67.36  5004.5    69.7  5014.5   70.52
  5034.5   75.65  5054.5   76.85  5084.5   75.84  5094.5   78.02  5114.5   80.94
  5124.5   81.85  5195.7   84.47  5384.5   88.95  5514.5   92.81  5554.5   92.91
#Mann= 8 ,-1 , 0
  4184.5     .05       0    4591     .07       0  4632.3    .035       0
  4746.6     .07       0  4845.9      .1       0    4978     .05       0
    5004      .1       0  5195.7     .05       0
Bank Sta=4978,5004
XS Rating Curve= 0 ,0
Exp/Cntr=0.3,0.1

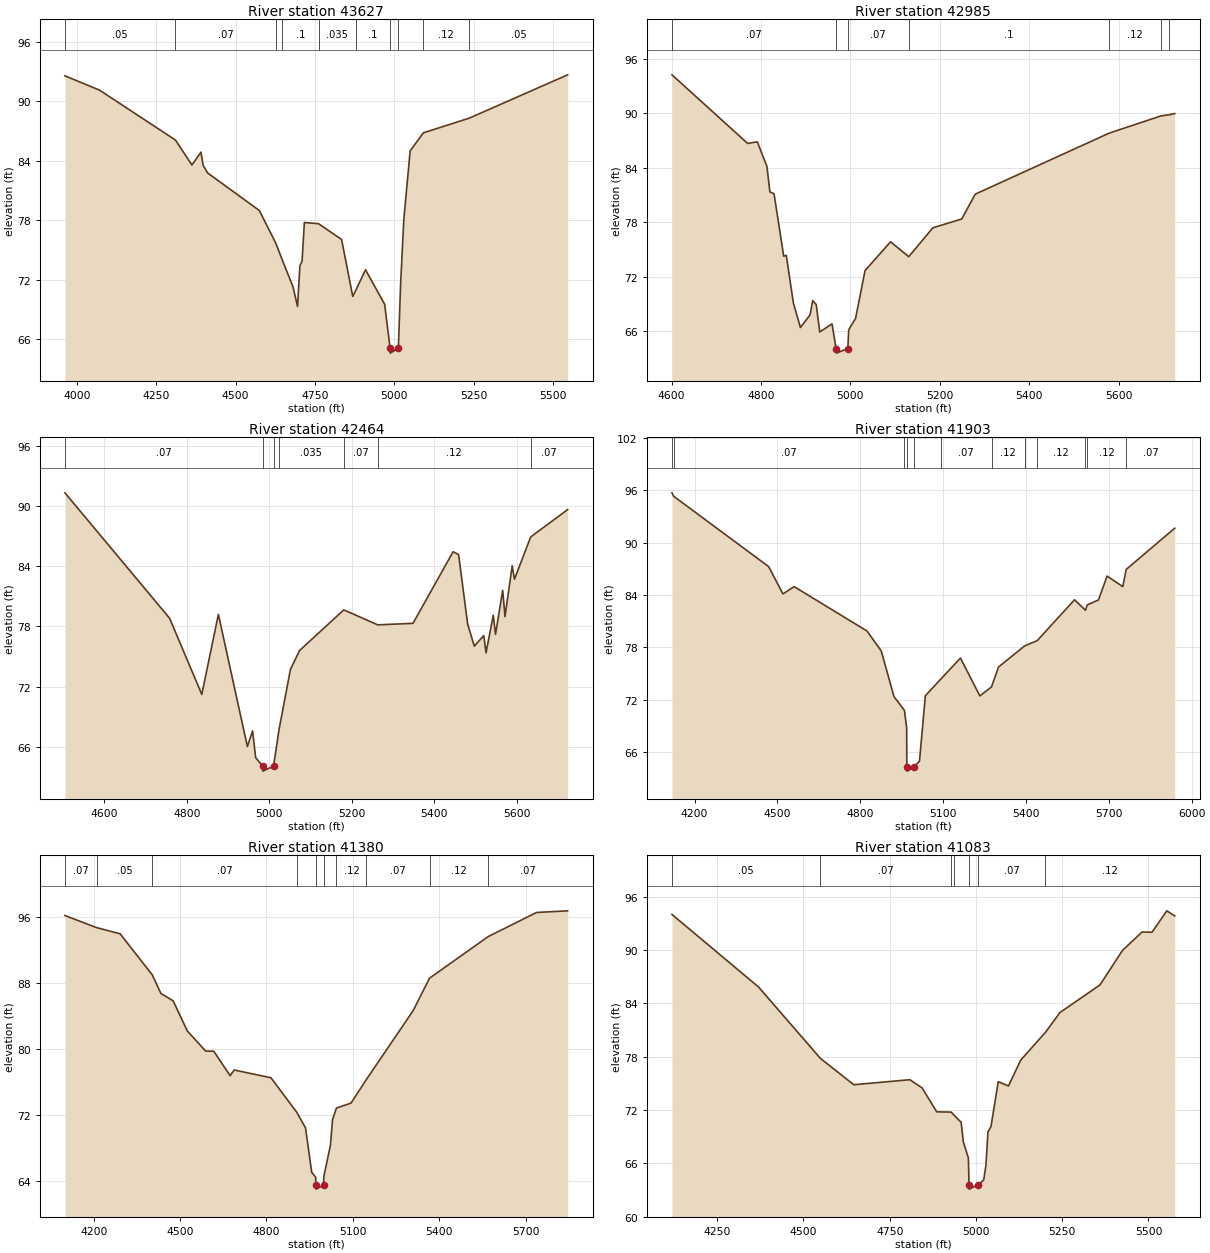
Type RM Length L Ch R = 1 ,43627   ,642,642,642
BEGIN DESCRIPTION:
Mapping XS 6edd3f6f
END DESCRIPTION:
XS GIS Cut Line= 4
       2584823.8      13476540.9      2584214.42     13475988.82
      2584177.96     13475587.78      2583943.61     13475316.97
#Sta/Elev= 30
  3962.6   92.58  4071.9   91.13  4310.6    86.1  4362.6   83.58  4390.9   84.88
  4397.7   83.56  4411.9   82.78  4574.8   78.99  4626.6    75.7  4646.8   74.02
  4680.9   71.28  4695.1   69.31  4702.5   73.41  4709.3   73.86  4716.6   77.78
  4761.2   77.66  4833.8   76.07    4869   70.32  4878.2   70.92  4909.2   73.01
  4969.4   69.53  4986.6    65.1  4987.1    64.6  5012.6    65.1  5019.7   71.58
  5029.7   78.06  5049.7      85  5091.5   86.83    5236   88.31  5545.7   92.68
#Mann= 10 ,-1 , 0
  3962.6     .05       0  4310.6     .07       0  4626.6     .05       0
  4646.8      .1       0  4761.2    .035       0  4878.2      .1       0
  4986.6     .05       0  5012.6      .1       0  5091.5     .12       0
    5236     .05       0
Bank Sta=4986.6,5012.6
XS Rating Curve= 0 ,0
Exp/Cntr=0.3,0.1

Type RM Length L Ch R = 1 ,42985   ,521,521,521
BEGIN DESCRIPTION:
DRY CREEK 58.0
END DESCRIPTION:
XS GIS Cut Line= 3
      2584925.01     13476125.02        2584725.       13475775.
      2584125.03     13475375.02
#Sta/Elev= 30
    4601   94.23  4770.2   86.68  4791.8   86.86  4813.4   84.14  4819.9   81.35
  4829.2   81.15  4850.8   74.28  4856.6   74.36  4872.4   69.14  4888.2   66.43
  4909.8   67.82  4915.6   69.39  4923.5   68.96  4931.4   65.94  4958.8   66.83
    4968   64.11  4968.5   63.61  4994.2   64.11  4996.2   66.18  5011.6   67.44
  5032.7   72.69  5089.8   75.86  5130.4   74.22  5184.4    77.4    5249   78.37
  5279.1    81.1  5578.4   87.81  5694.4   89.71  5713.5   89.84  5725.2   89.97
#Mann= 7 ,-1 , 0
    4601     .07       0    4968     .05       0  4994.2     .07       0
  5130.4      .1       0  5578.4     .12       0  5694.4     .05       0
  5713.5     .07       0
Bank Sta=4968,4994.2
XS Rating Curve= 0 ,0
Exp/Cntr=0.3,0.1

Type RM Length L Ch R = 1 ,42464   ,561,561,561
BEGIN DESCRIPTION:
DRY CREEK 57.0
END DESCRIPTION:
XS GIS Cut Line= 3
      2585375.04       13475525.        2584875.       13475475.
      2584225.02     13475175.01
#Sta/Elev= 30
  4504.7    91.3  4758.5    78.8  4836.4   71.22  4876.6   79.19  4946.9   66.03
  4959.5   67.59    4967   64.92    4984   64.08  4984.5   63.58  5010.3   64.08
  5023.6   67.72  5051.3   73.72  5073.3   75.59  5180.5   79.64  5262.9   78.15
  5348.2    78.3  5445.5   85.43  5458.8   85.15  5480.8   78.21  5496.9   76.03
  5519.8   77.08  5525.3   75.36  5542.8    79.1  5548.3   77.21  5565.7   81.59
  5571.2   78.97  5588.7   84.03  5594.2   82.69  5633.4    86.9  5723.1   89.63
#Mann= 7 ,-1 , 0
  4504.7     .07       0    4984     .05       0  5010.3     .07       0
  5023.6    .035       0  5180.5     .07       0  5262.9     .12       0
  5633.4     .07       0
Bank Sta=4984,5010.3
XS Rating Curve= 0 ,0
Exp/Cntr=0.3,0.1

Type RM Length L Ch R = 1 ,41903   ,523,523,523
BEGIN DESCRIPTION:
Mapping XS 045739ce
END DESCRIPTION:
XS GIS Cut Line= 3
      2585980.05     13475395.07      2585172.75     13475025.28
      2584292.52     13474717.97
#Sta/Elev= 30
  4118.4   95.72  4124.8   95.32  4468.6   87.25  4520.1   84.12  4560.6   84.96
  4824.7   79.86  4876.2   77.57  4922.2   72.34    4960   70.76  4968.2   68.72
  4968.7   64.29  4969.2   63.79    4995   64.29  5014.6   64.95  5035.8   72.44
    5092   74.36  5162.9   76.76  5233.2   72.42  5275.3   73.45  5300.6   75.73
  5394.9   78.15  5440.8   78.76  5575.9   83.45  5615.4   82.25    5622   82.86
  5662.7   83.43  5693.8   86.17  5750.6   84.96    5763   86.93  5938.7   91.66
#Mann= 12 ,-1 , 0
  4118.4     .05       0  4124.8     .07       0    4960      .1       0
  4968.7     .05       0    4995      .1       0    5092     .07       0
  5275.3     .12       0  5394.9     .07       0  5440.8     .12       0
  5615.4     .07       0    5622     .12       0    5763     .07       0
Bank Sta=4968.7,4995
XS Rating Curve= 0 ,0
Exp/Cntr=0.3,0.1

Type RM Length L Ch R = 1 ,41380   ,297,297,297
BEGIN DESCRIPTION:
Mapping XS f1706846
END DESCRIPTION:
XS GIS Cut Line= 3
      2586052.97     13475217.99      2585396.71     13474608.61
      2584599.96     13474311.78
#Sta/Elev= 30
  4100.2   96.16  4209.9    94.7  4291.8   93.95  4403.6   88.97  4433.5   86.72
    4476   85.83  4525.4   82.17  4588.9   79.74  4617.2   79.72  4673.9   76.76
  4688.1   77.45  4815.6   76.51  4905.3   72.33  4935.8   70.43  4957.2   65.05
    4971   64.47  4971.9   63.52  4972.4   63.02  4998.3   63.52  4999.3   64.54
  5022.3   68.35  5029.6   71.45    5043   72.84  5093.6   73.44  5146.9   76.29
  5309.6   84.65  5366.3   88.57  5570.1   93.61  5737.9   96.53    5846   96.73
#Mann= 10 ,-1 , 0
  4100.2     .07       0  4209.9     .05       0  4403.6     .07       0
  4905.3      .1       0  4971.9     .05       0  4998.3      .1       0
    5043     .12       0  5146.9     .07       0  5366.3     .12       0
  5570.1     .07       0
Bank Sta=4971.9,4998.3
XS Rating Curve= 0 ,0
Exp/Cntr=0.3,0.1

Type RM Length L Ch R = 1 ,41083   ,336,336,336
BEGIN DESCRIPTION:
Mapping XS b7f9dba0
END DESCRIPTION:
XS GIS Cut Line= 3
      2586240.49     13475004.47      2585631.09      13474415.9
      2585131.05     13474066.92
#Sta/Elev= 30
    4119   93.98    4370   85.82  4548.9   77.81  4645.8   74.84  4808.4    75.4
  4843.9   74.48  4886.3   71.79  4928.1   71.76  4937.7   71.37  4957.1   70.61
  4963.3   68.43  4978.1   66.58  4979.8    63.6  4980.3    63.1  5006.2    63.6
  5022.4   64.13  5028.7   65.75  5034.8   69.53  5043.6   70.15  5064.5   75.18
  5094.2    74.7  5129.9   77.62  5201.4   80.73  5243.3   82.95  5359.4   86.06
  5424.8   89.95  5481.5   92.01  5510.2   91.98    5553   94.39    5576   93.82
#Mann= 7 ,-1 , 0
    4119     .05       0  4548.9     .07       0  4928.1      .1       0
  4937.7     .07       0  4979.8     .05       0  5006.2     .07       0
  5201.4     .12       0
Bank Sta=4979.8,5006.2
XS Rating Curve= 0 ,0
Exp/Cntr=0.3,0.1

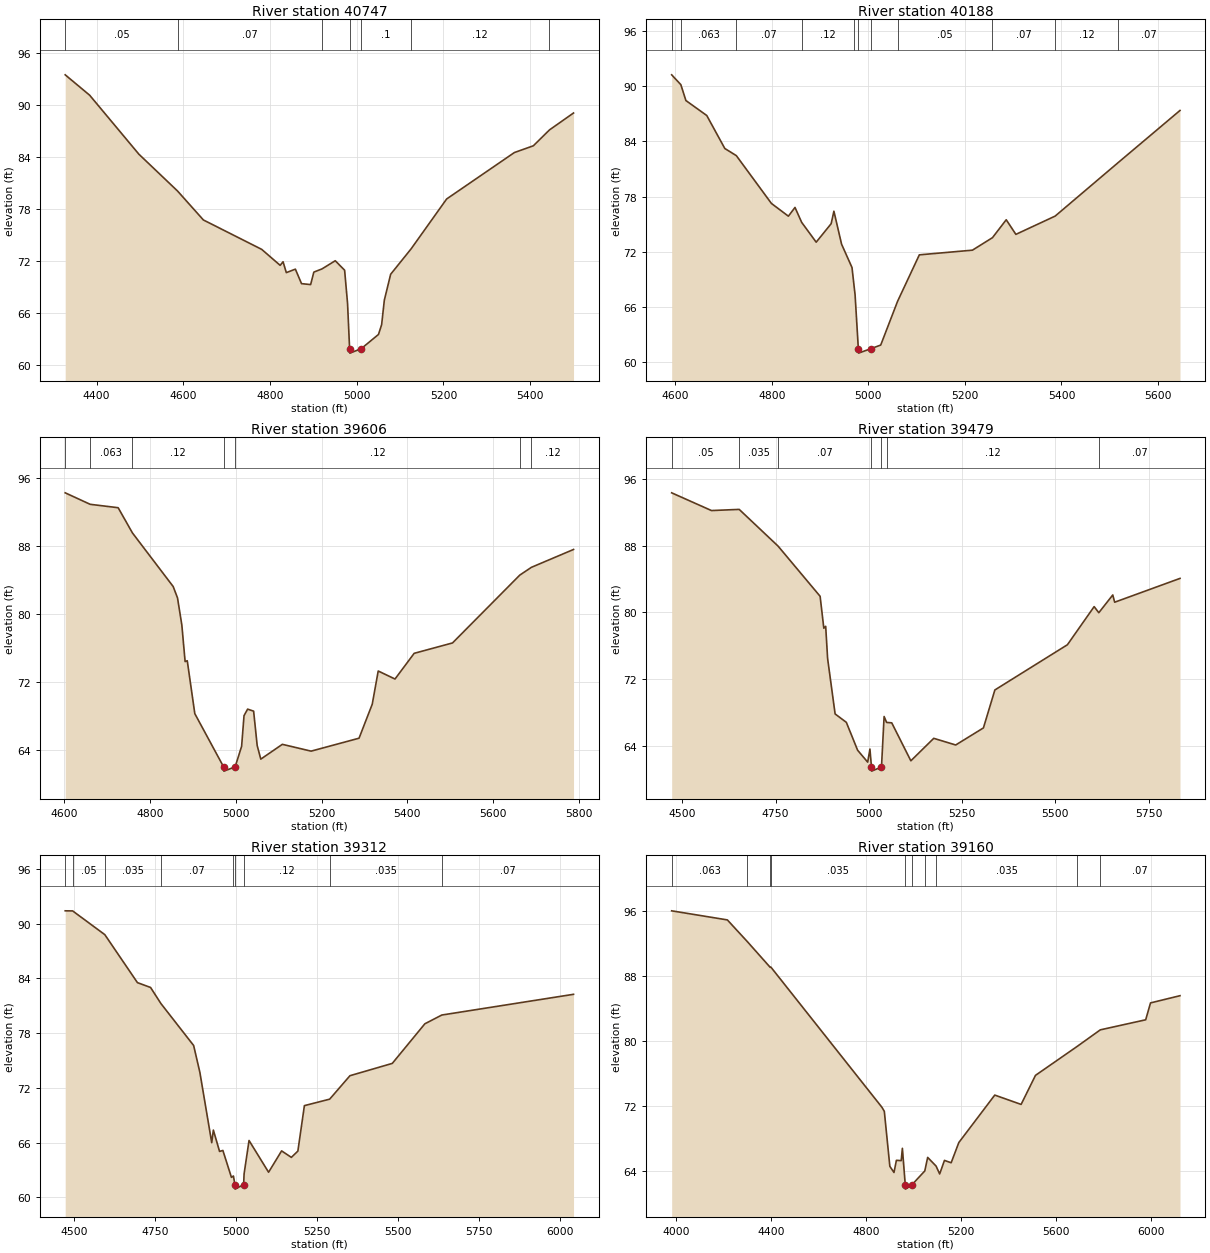
Type RM Length L Ch R = 1 ,40747   ,559,559,559
BEGIN DESCRIPTION:
DRY CREEK 54.0
END DESCRIPTION:
XS GIS Cut Line= 3
      2586374.99       13474675.        2585875.       13474225.
      2585474.98     13473924.98
#Sta/Elev= 30
  4327.4   93.48  4383.8   91.13  4497.4   84.33  4586.5   80.09  4646.2   76.75
  4780.7   73.36  4823.3   71.52    4830   71.93  4837.5   70.68  4858.4   71.08
  4872.6   69.41  4893.6    69.3    4901   70.74  4919.9   71.11  4950.4   72.05
    4972   70.96  4978.8   67.12  4983.5    61.9    4984    61.4    5010    61.9
  5050.1   63.55  5057.4   64.68  5063.6    67.5  5078.2   70.49  5125.4   73.42
  5207.4   79.17  5363.6   84.52  5407.4    85.3  5444.6   87.13  5500.1   89.08
#Mann= 7 ,-1 , 0
  4327.4     .05       0  4586.5     .07       0  4919.9      .1       0
  4983.5     .05       0    5010      .1       0  5125.4     .12       0
  5444.6     .07       0
Bank Sta=4983.5,5010
XS Rating Curve= 0 ,0
Exp/Cntr=0.3,0.1

Type RM Length L Ch R = 1 ,40188   ,582,582,582
BEGIN DESCRIPTION:
DRY CREEK 53.0
END DESCRIPTION:
XS GIS Cut Line= 3
      2586574.96     13473625.02        2586225.       13473825.
      2585574.97       13473825.
#Sta/Elev= 30
  4592.4   91.25  4611.4   90.18  4621.9   88.45  4665.1   86.82  4702.5   83.23
  4726.4   82.45    4799   77.25  4834.2   75.86  4847.9   76.81  4861.7   75.19
  4891.8   73.03  4922.8   75.04  4928.5    76.4  4944.4   72.81    4966   70.27
  4969.3   68.73  4972.4   67.28  4979.1   61.45  4979.6   60.95    5006   61.45
  5025.5   61.83  5060.4   66.59  5105.5   71.65  5215.5   72.16    5257   73.52
  5285.5   75.47  5305.5   73.88  5386.9   75.87  5517.1   81.68  5645.5   87.37
#Mann= 11 ,-1 , 0
  4592.4     .05       0  4611.4    .063       0  4726.4     .07       0
  4861.7     .12       0  4969.3     .07       0  4979.1     .05       0
    5006     .07       0  5060.4     .05       0    5257     .07       0
  5386.9     .12       0  5517.1     .07       0
Bank Sta=4979.1,5006
XS Rating Curve= 0 ,0
Exp/Cntr=0.3,0.1

Type RM Length L Ch R = 1 ,39606   ,127,127,127
BEGIN DESCRIPTION:
DRY CREEK 52.0
END DESCRIPTION:
XS GIS Cut Line= 3
        2586625.       13473325.        2586225.       13473275.
      2585525.04     13473624.98
#Sta/Elev= 30
  4601.8   94.21    4660   92.86  4725.3   92.46  4758.7   89.49  4853.7   83.19
  4863.8   81.85  4873.9   78.65  4881.5   74.37  4886.5   74.47  4904.1   68.25
  4971.3   61.99  4971.8   61.49  4998.2   61.99  5013.3   64.41  5018.9   68.01
  5027.3   68.78  5041.3   68.54  5049.6    64.5    5058    62.9  5108.3   64.64
  5175.4   63.84  5287.2   65.36    5318   69.36  5331.9   73.26  5371.1   72.32
  5415.8   75.34  5505.2   76.56    5662   84.53  5689.2   85.45  5787.5   87.55
#Mann= 7 ,-1 , 0
  4601.8     .05       0    4660    .063       0  4758.7     .12       0
  4971.3     .05       0  4998.2     .12       0    5662     .07       0
  5689.2     .12       0
Bank Sta=4971.3,4998.2
XS Rating Curve= 0 ,0
Exp/Cntr=0.3,0.1

Type RM Length L Ch R = 1 ,39479   ,167,167,167
BEGIN DESCRIPTION:
Mapping XS d591c988
END DESCRIPTION:
XS GIS Cut Line= 3
      2586751.31     13473197.36      2586226.14     13473149.61
      2585410.16     13473327.57
#Sta/Elev= 30
  4471.7   94.36  4578.4   92.23  4652.7   92.37  4756.9   87.96  4869.6   81.93
  4879.5    78.1  4884.5   78.32  4889.7   74.45  4909.8    67.8  4939.9   66.79
  4970.1   63.44  4997.1   62.01  5003.1   63.58  5007.2   61.43  5007.7   60.93
  5034.1   61.43  5041.1   67.49  5047.8   66.78  5061.6   66.73  5112.8   62.17
  5174.2   64.87    5233   64.07  5307.3   66.12    5338   70.68  5532.4   76.11
  5604.1   80.69  5616.6   79.96    5654   82.09  5659.1   81.22  5834.2   84.08
#Mann= 7 ,-1 , 0
  4471.7     .05       0  4652.7    .035       0  4756.9     .07       0
  5007.2     .05       0  5034.1     .07       0  5047.8     .12       0
  5616.6     .07       0
Bank Sta=5007.2,5034.1
XS Rating Curve= 0 ,0
Exp/Cntr=0.3,0.1

Type RM Length L Ch R = 1 ,39312   ,152,152,152
BEGIN DESCRIPTION:
Mapping XS fefb6661
END DESCRIPTION:
XS GIS Cut Line= 3
      2586694.84      13473084.5      2586174.05      13472997.7
      2585138.41     13473097.37
#Sta/Elev= 30
  4472.9   91.41  4495.9    91.4  4595.1    88.8  4695.8   83.54  4736.3   83.01
  4768.2   81.25  4869.2   76.65  4888.4   73.71    4925      66    4930   67.38
  4949.2   65.04  4959.4   65.15  4985.8    62.2  4991.9   62.35  4996.5   61.41
    4997   60.91  5023.4   61.41  5024.9    62.6  5040.1   66.24  5100.4   62.76
  5140.6    65.1  5170.7   64.39  5190.8   65.08  5210.9   70.06  5288.9   70.77
  5351.5   73.34  5482.1   74.69  5582.6   79.03  5634.9   79.99  6041.3   82.26
#Mann= 9 ,-1 , 0
  4472.9    .035       0  4495.9     .05       0  4595.1    .035       0
  4768.2     .07       0  4991.9     .12       0  4996.5     .05       0
  5023.4     .12       0  5288.9    .035       0  5634.9     .07       0
Bank Sta=4996.5,5023.4
XS Rating Curve= 0 ,0
Exp/Cntr=0.3,0.1

Type RM Length L Ch R = 1 ,39160   ,114,114,114
BEGIN DESCRIPTION:
DRY CREEK 51.0
END DESCRIPTION:
XS GIS Cut Line= 3
      2587085.53     13473067.15      2586082.83     13472881.19
      2584971.77     13472732.94
#Sta/Elev= 30
  3980.2   96.07  4214.7   94.95  4298.7   92.28    4395   89.11  4398.1   89.13
  4865.6   71.86  4875.7   71.36    4899   64.58  4916.4   63.82  4926.6   65.32
  4946.8   65.28  4951.8    66.8    4964   62.27  4964.5   61.77  4990.9   62.27
  5046.1   64.01  5058.3   65.68  5093.7   64.61  5108.8   63.64    5129   65.31
  5157.2   65.02  5189.5   67.51  5340.8   73.36  5451.8   72.21  5512.3   75.79
  5686.5   79.33  5785.3    81.4  5976.4   82.64  5996.8   84.72  6120.9   85.61
#Mann= 10 ,-1 , 0
  3980.2    .063       0  4298.7    .035       0    4395     .07       0
  4398.1    .035       0    4964    .035       0  4990.9    .035       0
  5046.1      .1       0  5093.7    .035       0  5686.5     .05       0
  5785.3     .07       0
Bank Sta=4964,4990.9
XS Rating Curve= 0 ,0
Exp/Cntr=0.3,0.1