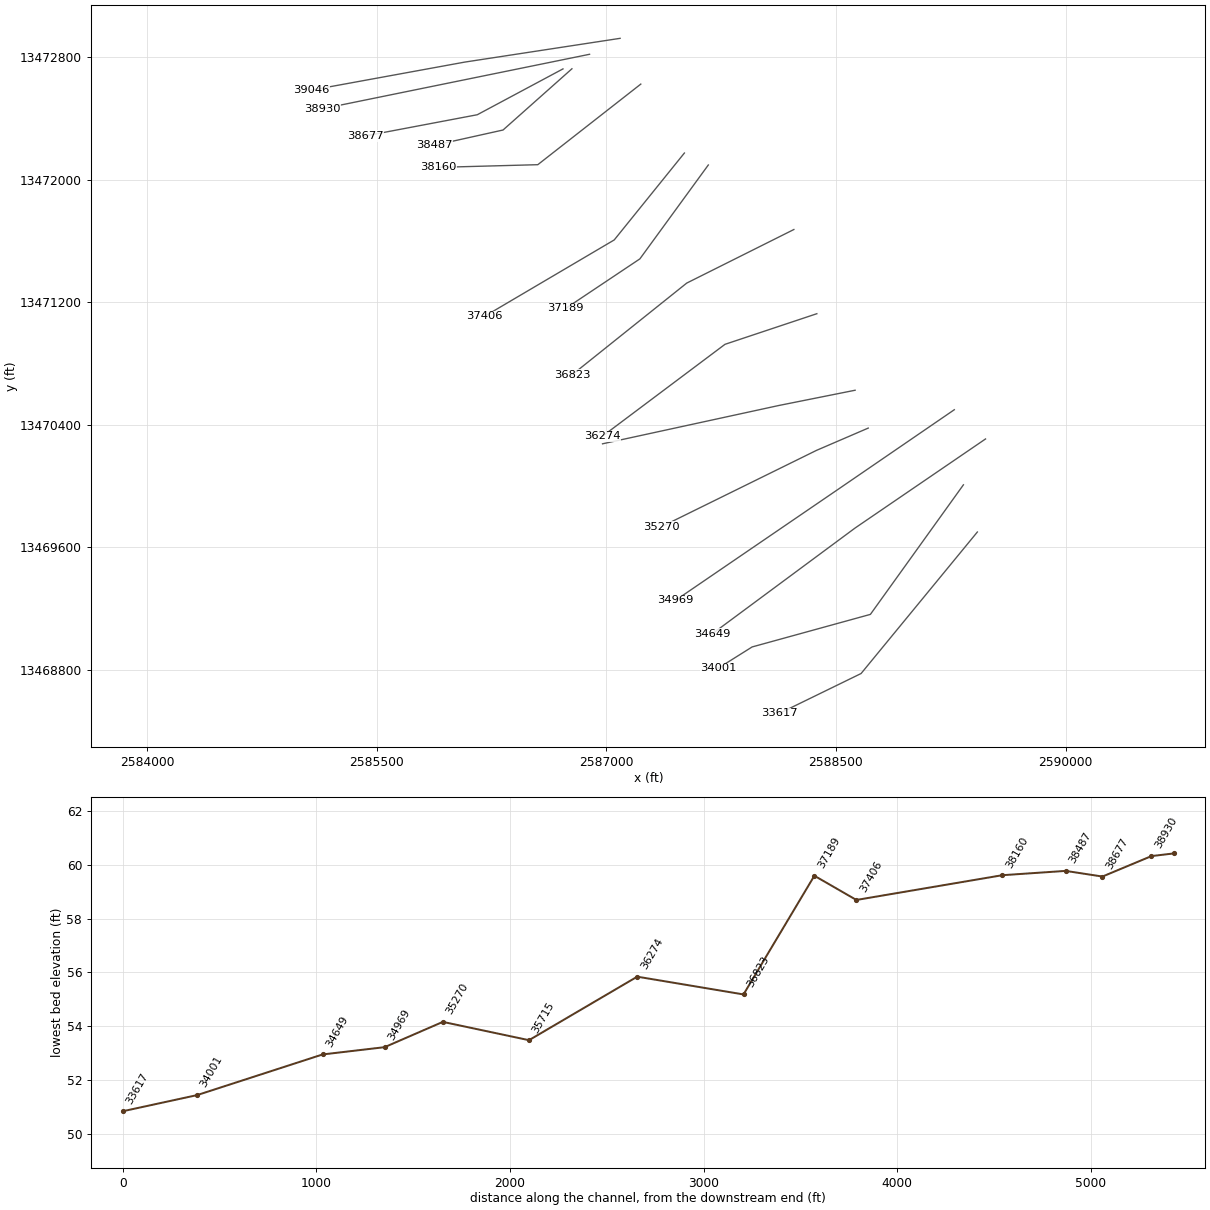
HEC-RAS study DRY CREEK.prj: DRY CREEK Base Level Engineering

--- DRY CREEK.g01 (geometry) --- (continued)

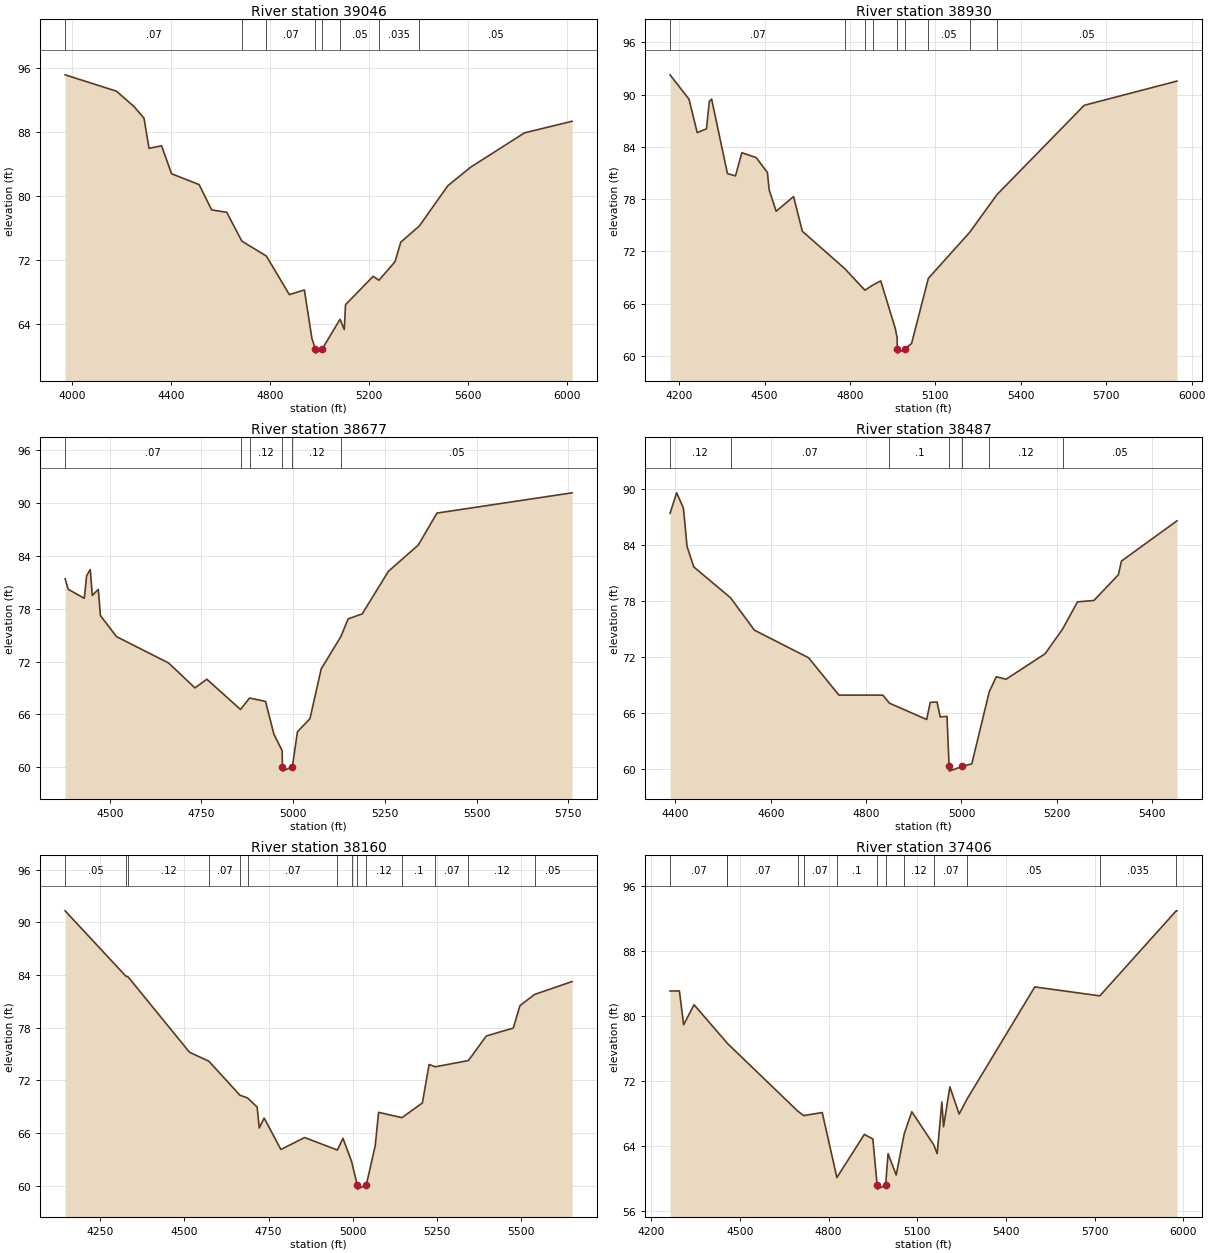
Type RM Length L Ch R = 1 ,39046   ,116,116,116
BEGIN DESCRIPTION:
Mapping XS d97f16c3
END DESCRIPTION:
XS GIS Cut Line= 3
      2587089.82     13472923.91        2586075.     13472768.71
      2585071.63     13472585.38
#Sta/Elev= 30
  3973.3   95.13  4180.5   93.09  4251.3   91.18  4291.8   89.72    4312   85.96
  4362.6   86.28  4403.1   82.79  4514.3   81.44  4564.9   78.28  4625.6   77.99
  4686.7   74.39  4785.7   72.53  4878.5   67.72  4939.2    68.3  4969.6   62.25
  4983.8   60.92  4984.3   60.42  5010.9   60.92  5083.1   64.64  5100.3   63.37
  5105.3   66.46  5216.9      70  5240.2   69.51  5304.9   71.81  5328.4   74.26
  5403.4   76.28  5518.4    81.3  5609.9    83.6  5827.8   87.89  6019.9   89.34
#Mann= 8 ,-1 , 0
  3973.3     .07       0  4686.7      .1       0  4785.7     .07       0
  4983.8     .05       0  5010.9     .07       0  5083.1     .05       0
  5240.2    .035       0  5403.4     .05       0
Bank Sta=4983.8,5010.9
XS Rating Curve= 0 ,0
Exp/Cntr=0.3,0.1

Type RM Length L Ch R = 1 ,38930   ,253,253,253
BEGIN DESCRIPTION:
Mapping XS a25b6dab
END DESCRIPTION:
XS GIS Cut Line= 2
       2586890.2     13472819.75      2585145.43     13472463.85
#Sta/Elev= 30
  4167.8   92.26  4234.3   89.46  4263.2   85.63  4295.6   86.06  4305.8   89.21
  4313.8   89.47  4369.4   80.93  4397.6   80.66  4419.9   83.32  4470.5   82.76
  4509.9   81.04  4515.9   79.07  4540.5    76.6  4601.8   78.29  4632.4   74.31
  4780.8   70.04  4852.4   67.54  4880.5   68.14  4907.9   68.61    4959   63.15
  4965.6   62.04  4965.8   60.82  4966.3   60.32  4992.9   60.82  5016.1   61.42
  5075.1    68.9  5220.2   74.18  5316.7   78.53  5622.5   88.76  5948.5   91.54
#Mann= 9 ,-1 , 0
  4167.8     .07       0  4780.8      .1       0  4852.4     .07       0
  4880.5      .1       0  4965.8     .05       0  4992.9      .1       0
  5075.1     .05       0  5220.2    .035       0  5316.7     .05       0
Bank Sta=4965.8,4992.9
XS Rating Curve= 0 ,0
Exp/Cntr=0.3,0.1

Type RM Length L Ch R = 1 ,38677   ,190,190,190
BEGIN DESCRIPTION:
Mapping XS c390117c
END DESCRIPTION:
XS GIS Cut Line= 3
      2586716.62     13472724.28      2586156.69     13472424.79
      2585423.22      13472285.9
#Sta/Elev= 30
  4378.4   81.39  4386.7    80.2  4430.6   79.18  4436.9   81.74  4446.8   82.44
  4452.5    79.5  4468.8    80.2  4474.5   77.23  4518.3   74.83  4660.6   71.83
  4732.1   69.01  4764.6   69.99  4856.4   66.56  4881.1   67.86  4924.6   67.47
  4947.3   63.76  4969.9   61.88  4970.5   60.06    4971   59.56  4997.6   60.06
  5011.5   64.03  5045.6   65.51  5076.2   71.16  5130.1   74.85  5149.6   76.84
  5188.1   77.41  5259.4   82.24  5340.8   85.22  5391.7   88.85  5759.9   91.15
#Mann= 6 ,-1 , 0
  4378.4     .07       0  4856.4      .1       0  4881.1     .12       0
  4970.5     .05       0  4997.6     .12       0  5130.1     .05       0
Bank Sta=4970.5,4997.6
XS Rating Curve= 0 ,0
Exp/Cntr=0.3,0.1

Type RM Length L Ch R = 1 ,38487   ,327,327,327
BEGIN DESCRIPTION:
DRY CREEK 50.0
END DESCRIPTION:
XS GIS Cut Line= 3
      2586775.02     13472725.02        2586325.       13472325.
      2585874.99       13472225.
#Sta/Elev= 30
  4388.9   87.39  4402.7   89.58  4416.9   87.95  4424.5   83.85  4438.7   81.64
  4515.7   78.34  4565.8   74.87  4679.5   71.91  4743.1   67.91  4835.1   67.91
    4849   67.05    4927    65.3  4934.6   67.14  4948.8   67.17  4955.5   65.58
  4969.7   65.63  4974.1   60.27  4974.6   59.77  5001.2   60.27  5021.7   60.55
  5058.3   68.27    5073   69.88  5093.5   69.61  5175.4   72.34  5212.2   74.99
  5243.3    77.9  5277.8   78.05  5329.1    80.8  5335.5   82.27    5452   86.58
#Mann= 7 ,-1 , 0
  4388.9     .12       0  4515.7     .07       0    4849      .1       0
  4974.1     .05       0  5001.2      .1       0  5058.3     .12       0
  5212.2     .05       0
Bank Sta=4974.1,5001.2
XS Rating Curve= 0 ,0
Exp/Cntr=0.3,0.1

Type RM Length L Ch R = 1 ,38160   ,754,754,754
BEGIN DESCRIPTION:
DRY CREEK 49.0
END DESCRIPTION:
XS GIS Cut Line= 3
        2587225.       13472625.      2586551.99     13472098.47
      2585900.33     13472080.86
#Sta/Elev= 30
  4145.5   91.32  4325.6   83.89  4332.9   83.78  4515.3    75.2  4572.5   74.19
  4664.7   70.32    4688   69.99  4716.1   68.96  4722.4   66.58  4736.9   67.71
  4786.6   64.13  4857.2   65.49  4954.5   64.06  4971.1    65.4  4996.6   62.78
  5013.5   60.11    5014   59.61  5040.6   60.11    5067   64.56    5077   68.36
  5146.3   67.75  5207.1   69.43  5227.1   73.81  5245.7   73.55  5343.9   74.26
  5397.1   77.06  5477.2   77.96  5497.2   80.52  5540.4   81.79  5651.9   83.26
#Mann= 14 ,-1 , 0
  4145.5     .05       0  4325.6     .07       0  4332.9     .12       0
  4572.5     .07       0  4664.7     .12       0    4688     .07       0
  4954.5      .1       0  4996.6     .12       0  5013.5     .05       0
  5040.6     .12       0  5146.3      .1       0  5245.7     .07       0
  5343.9     .12       0  5540.4     .05       0
Bank Sta=5013.5,5040.6
XS Rating Curve= 0 ,0
Exp/Cntr=0.3,0.1

Type RM Length L Ch R = 1 ,37406   ,217,217,217
BEGIN DESCRIPTION:
Mapping XS bdb065d6
END DESCRIPTION:
XS GIS Cut Line= 3
      2587509.75     13472174.65      2587051.39      13471606.9
       2586203.5     13471107.33
#Sta/Elev= 30
  4264.3   83.04  4295.9   83.04  4310.2   78.89  4345.4   81.35  4455.8   76.71
  4456.5   76.66  4696.2   68.27    4716   67.73  4778.8    68.1  4828.3   60.11
  4921.2   65.42  4949.9   64.85  4964.4   59.19  4964.9   58.69  4993.1   59.19
  5001.4   63.05  5028.8   60.43    5056   65.49  5081.6    68.2  5155.9   64.13
  5167.4   63.05  5183.1    69.4  5188.9   66.36  5210.3   71.26  5241.7   67.92
  5268.2   69.75  5497.4   83.54  5717.2   82.44  5975.5   92.89  5978.1   92.89
#Mann= 13 ,-1 , 0
  4264.3     .07       0  4455.8     .05       0  4456.5     .07       0
  4696.2      .1       0    4716     .07       0  4828.3      .1       0
  4964.4     .05       0  4993.1      .1       0    5056     .12       0
  5155.9     .07       0  5268.2     .05       0  5717.2    .035       0
  5975.5     .05       0
Bank Sta=4964.4,4993.1
XS Rating Curve= 0 ,0
Exp/Cntr=0.3,0.1

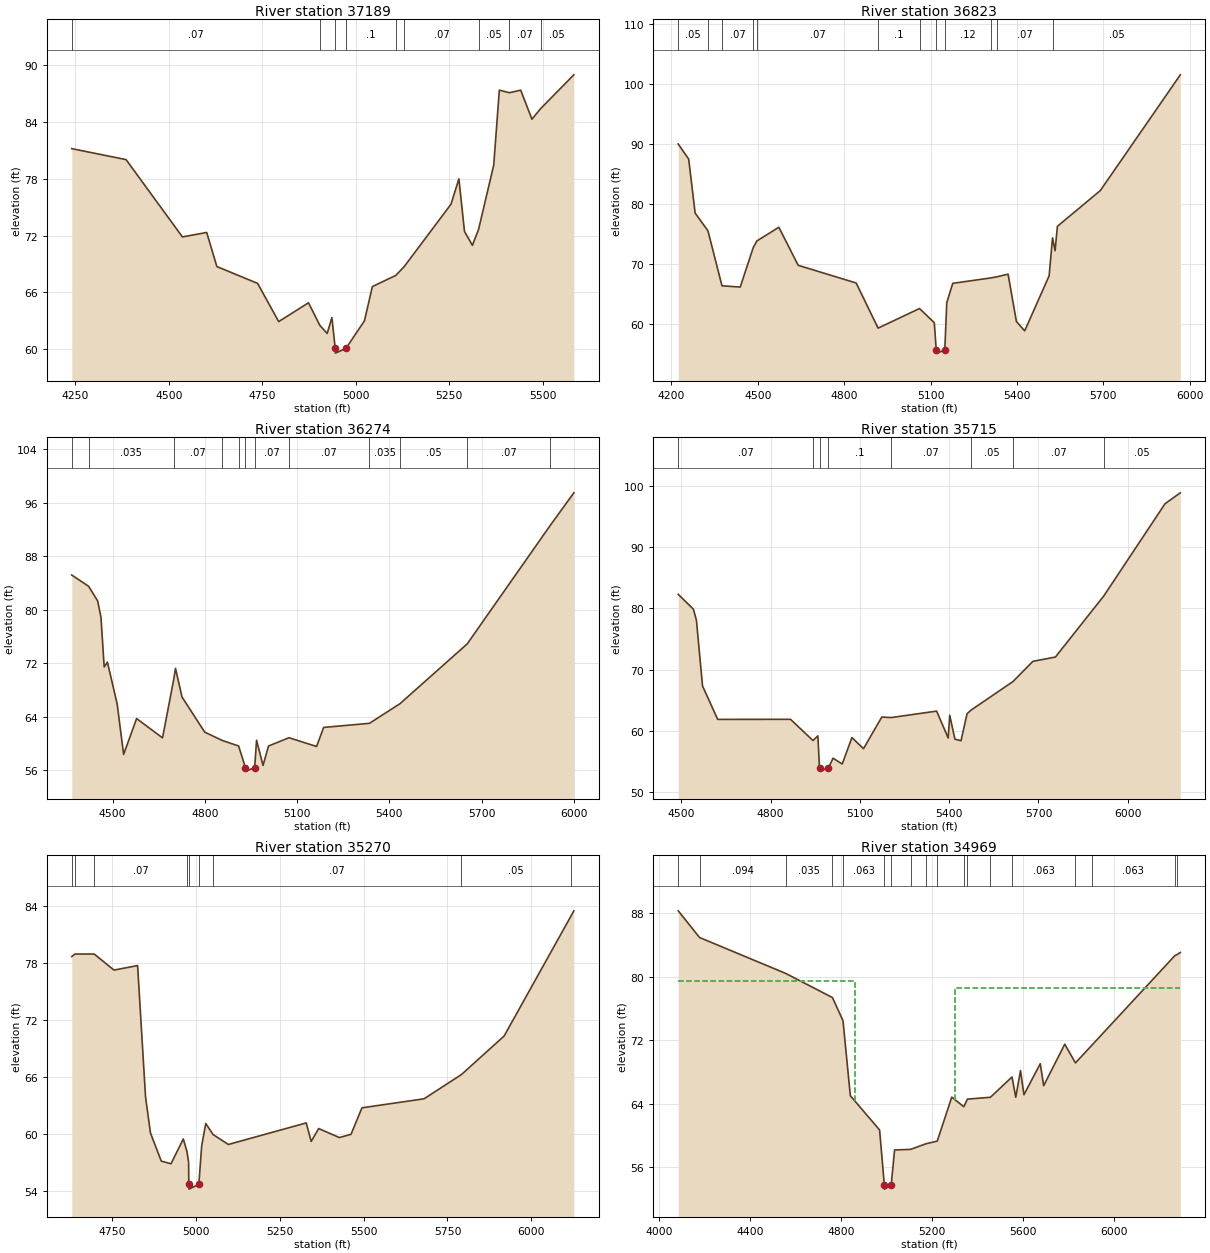
Type RM Length L Ch R = 1 ,37189   ,366,366,366
BEGIN DESCRIPTION:
DRY CREEK 48.0
END DESCRIPTION:
XS GIS Cut Line= 3
        2587666.     13472096.52      2587218.95     13471483.15
      2586734.41     13471159.47
#Sta/Elev= 30
    4241    81.2  4386.1   80.04  4536.7   71.87  4601.6   72.34  4628.7   68.74
  4737.6   66.96    4794   62.92  4873.6   64.91  4903.8   62.53  4923.5   61.67
  4936.2   63.35    4945   60.09  4945.5   59.59  4973.7   60.09  5023.2   63.01
  5044.3   66.62  5106.8    67.8  5129.1   68.72  5254.5   75.33  5275.5   78.01
  5290.5   72.45  5311.6   70.98  5328.2   72.68  5368.6   79.46  5383.6   87.38
  5410.5   87.11  5440.7   87.38  5470.7   84.31    5494   85.43  5582.7      89
#Mann= 9 ,-1 , 0
    4241     .07       0  4903.8      .1       0    4945     .05       0
  4973.7      .1       0  5106.8     .12       0  5129.1     .07       0
  5328.2     .05       0  5410.5     .07       0    5494     .05       0
Bank Sta=4945,4973.7
XS Rating Curve= 0 ,0
Exp/Cntr=0.3,0.1

Type RM Length L Ch R = 1 ,36823   ,549,549,549
BEGIN DESCRIPTION:
DRY CREEK 47.0
END DESCRIPTION:
XS GIS Cut Line= 3
      2588224.96     13471674.98        2587525.       13471325.
      2586774.96     13470724.97
#Sta/Elev= 30
  4223.8   89.97  4260.1   87.46  4282.5   78.47  4326.9   75.54  4375.7   66.38
    4439   66.17  4484.1   72.72  4496.7   73.84  4573.1   76.12  4640.2   69.79
  4841.5   66.85  4917.7   59.34  5061.5    62.6  5112.8   60.24  5119.6   55.68
  5120.1   55.18  5149.2   55.68  5156.1   63.57  5176.9   66.79  5309.2   67.69
  5329.9   67.87    5369   68.32  5397.8   60.45  5426.6   58.88  5511.4   68.03
  5523.3   74.36  5532.2   72.22  5540.2   76.28  5689.1   82.22  5966.9  101.48
#Mann= 12 ,-1 , 0
  4223.8     .05       0  4326.9    .035       0  4375.7     .07       0
  4484.1    .035       0  4496.7     .07       0  4917.7      .1       0
  5061.5     .12       0  5119.6     .05       0  5149.2     .12       0
  5309.2     .12       0  5329.9     .07       0  5523.3     .05       0
Bank Sta=5119.6,5149.2
XS Rating Curve= 0 ,0
Exp/Cntr=0.3,0.1

Type RM Length L Ch R = 1 ,36274   ,559,559,559
BEGIN DESCRIPTION:
DRY CREEK 46.0
END DESCRIPTION:
XS GIS Cut Line= 3
      2588374.99       13471125.        2587775.       13470925.
      2586975.03     13470325.02
#Sta/Elev= 30
  4367.3    85.2  4422.2   83.51  4451.6   81.31  4462.2   78.89  4472.7   71.44
  4483.2   72.16  4514.9    65.9  4535.9   58.34  4578.1   63.71  4662.4   60.82
  4698.7   69.54  4704.6   71.23  4725.7   66.94  4799.5   61.68  4857.3   60.42
  4909.8    59.6  4932.1   56.34  4932.6   55.84  4961.9   56.34  4968.1   60.47
  4989.2   56.69    5007    59.6  5073.4   60.84  5163.3   59.53  5186.2   62.38
  5335.2      63  5434.5   65.94  5653.2    74.9  5921.9   92.56  5999.7   97.51
#Mann= 12 ,-1 , 0
  4367.3     .07       0  4422.2    .035       0  4698.7     .07       0
  4857.3     .12       0  4909.8     .07       0  4932.1     .05       0
  4961.9     .07       0  5073.4     .07       0  5335.2    .035       0
  5434.5     .05       0  5653.2     .07       0  5921.9     .05       0
Bank Sta=4932.1,4961.9
XS Rating Curve= 0 ,0
Exp/Cntr=0.3,0.1

Type RM Length L Ch R = 1 ,35715   ,445,445,445
BEGIN DESCRIPTION:
DRY CREEK 45.0
END DESCRIPTION:
XS GIS Cut Line= 3
      2588625.03     13470625.01        2588125.       13470525.
        2586975.       13470275.
#Sta/Elev= 30
  4489.8   82.29  4540.8   79.86    4551   78.05  4571.4   67.36  4622.4   61.91
  4867.2   61.92  4942.5   58.46  4958.9   59.23  4964.4   53.98  4964.9   53.48
  4994.2   53.98    5010   55.59  5040.7   54.64  5073.4   58.95  5112.3   57.14
  5173.7   62.29  5205.7   62.21  5357.9   63.26  5396.8   58.88  5401.9   62.58
  5419.3   58.69  5439.8   58.43  5460.2   62.83  5473.5   63.42    5614   68.06
  5681.3   71.37    5757   72.07  5919.6   82.03  6125.4   97.06  6176.6   98.83
#Mann= 8 ,-1 , 0
  4489.8     .07       0  4942.5      .1       0  4964.4     .05       0
  4994.2      .1       0  5205.7     .07       0  5473.5     .05       0
    5614     .07       0  5919.6     .05       0
Bank Sta=4964.4,4994.2
XS Rating Curve= 0 ,0
Exp/Cntr=0.3,0.1

Type RM Length L Ch R = 1 ,35270   ,301,301,301
BEGIN DESCRIPTION:
Mapping XS 33ff992a
END DESCRIPTION:
XS GIS Cut Line= 3
      2588710.74     13470377.73      2588372.22      13470231.9
      2587358.32     13469732.75
#Sta/Elev= 30
  4628.5   78.65    4638   78.91  4695.5   78.91  4754.6   77.22    4825    77.7
  4848.7   63.87  4863.4   60.07  4895.7   57.11  4924.7   56.83  4961.4   59.44
  4972.3   58.13  4977.2   57.02  4977.9   54.66  4978.4   54.16  5007.8   54.66
  5016.3   58.72  5028.5   61.07  5050.3   59.91  5095.9   58.86  5328.4   61.13
  5343.1   59.18  5365.5   60.54  5427.3   59.59  5462.1   59.93  5494.7   62.72
  5680.1   63.67  5791.6   66.22  5919.1   70.28  6119.2   82.94  6127.2   83.46
#Mann= 9 ,-1 , 0
  4628.5     .07       0    4638    .035       0  4695.5     .07       0
  4972.3      .1       0  4977.9     .05       0  5007.8      .1       0
  5050.3     .07       0  5791.6     .05       0  6119.2     .07       0
Bank Sta=4977.9,5007.8
XS Rating Curve= 0 ,0
Exp/Cntr=0.3,0.1

Type RM Length L Ch R = 1 ,34969   ,320,320,320
BEGIN DESCRIPTION:
Mapping XS ec319c5f
END DESCRIPTION:
XS GIS Cut Line= 3
      2589273.04     13470497.72      2588520.14      13469981.9
      2587452.41     13469252.73
#Sta/Elev= 30
  4083.8   88.28  4177.4   84.92    4557   80.38  4761.4   77.35  4807.7   74.43
  4839.8   64.99  4968.4   60.67  4989.3   53.72  4989.8   53.22  5019.3   53.72
  5034.1   58.15  5104.7   58.23  5171.9   58.93  5221.6   59.27  5285.4   64.81
  5338.4    63.6  5354.2   64.56  5455.2   64.79    5550   67.35  5566.5   64.79
  5587.5   68.15  5602.4   65.11  5674.2   69.02  5689.1   66.25  5781.9   71.48
  5828.7   69.12    5901   71.35  6265.6   82.64  6272.9   82.73  6289.4   83.03
#Mann= 18 ,-1 , 0
  4083.8     .05       0  4177.4    .094       0    4557    .035       0
  4761.4     .07       0  4807.7    .063       0  4989.3     .05       0
  5019.3    .063       0  5104.7     .07       0  5171.9    .094       0
  5221.6    .063       0  5338.4     .07       0  5354.2    .063       0
  5455.2     .07       0    5550    .063       0  5828.7     .07       0
    5901    .063       0  6265.6    .094       0  6272.9    .063       0
#XS Ineff= 2 ,-1
    4084    4860    79.5    5299    6289    78.5
Permanent Ineff=
       F       F
Bank Sta=4989.3,5019.3
XS Rating Curve= 0 ,0
Exp/Cntr=0.3,0.1

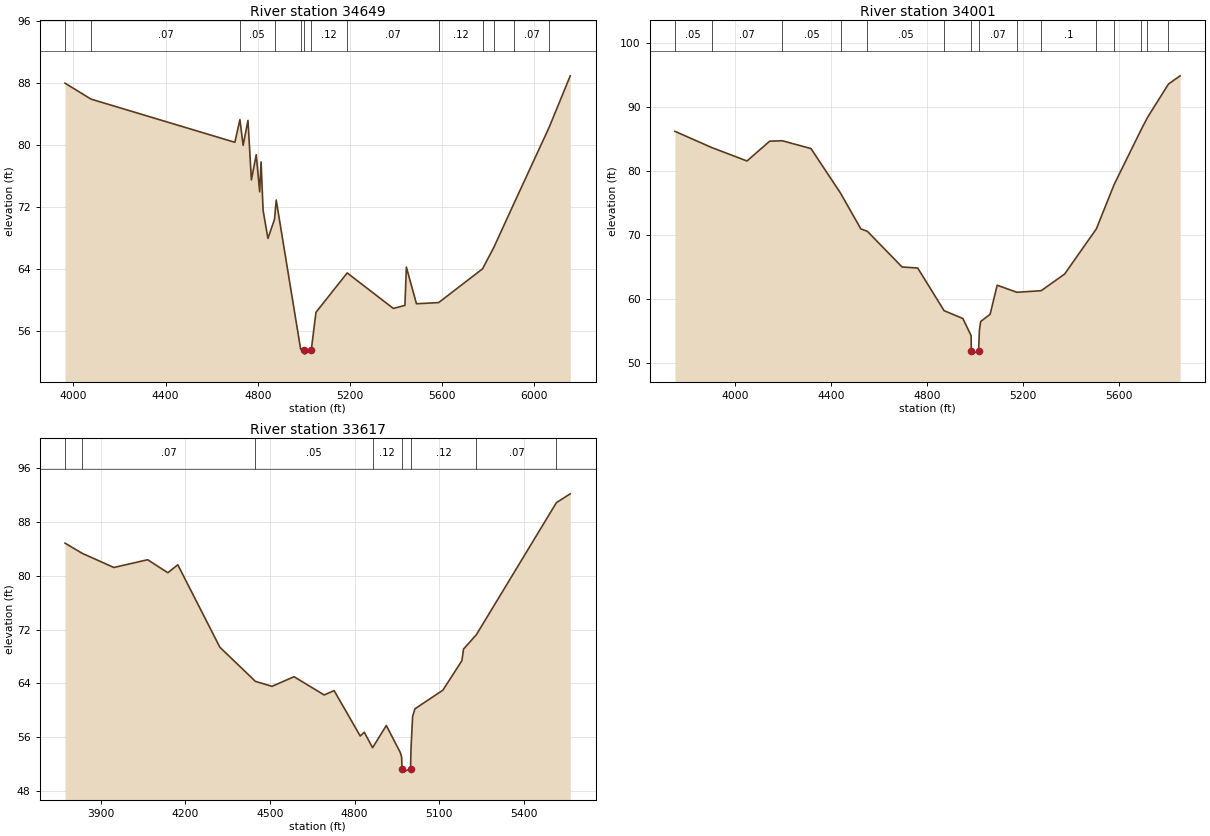
Type RM Length L Ch R = 1 ,34649   ,648,648,648
BEGIN DESCRIPTION:
DRY CREEK 43.0
END DESCRIPTION:
XS GIS Cut Line= 3
      2589476.99     13470306.72        2588625.       13469725.
      2587691.98     13469033.96
#Sta/Elev= 30
  3963.9   87.96  4076.6    85.9  4700.9   80.32  4722.9   83.25  4736.8   79.93
  4757.8   83.15  4772.7   75.47  4793.7   78.72  4808.6   73.93  4814.7   77.79
  4823.5   71.52  4844.5    67.9    4873   70.37  4880.4   72.86  4986.4    53.6
  5002.5   53.45    5003   52.95  5032.5   53.45  5052.9   58.35  5188.5   63.44
    5389   58.85    5439   59.25  5445.3    64.2  5489.1   59.46  5585.4   59.61
  5775.9   63.97  5825.1   66.75  5912.8   72.45  6064.8   82.24  6156.6   88.91
#Mann= 13 ,-1 , 0
  3963.9     .05       0  4076.6     .07       0  4722.9     .05       0
    4873     .07       0  4986.4     .12       0  5002.5     .05       0
  5032.5     .12       0  5188.5     .07       0  5585.4     .12       0
  5775.9      .1       0  5825.1     .12       0  5912.8     .07       0
  6064.8     .12       0
Bank Sta=5002.5,5032.5
XS Rating Curve= 0 ,0
Exp/Cntr=0.3,0.1

Type RM Length L Ch R = 1 ,34001   ,384,384,384
BEGIN DESCRIPTION:
Mapping XS 9996710e
END DESCRIPTION:
XS GIS Cut Line= 4
       2589332.5     13470007.07      2588724.84     13469160.69
      2587952.27     13468948.02      2587731.64     13468809.58
#Sta/Elev= 30
  3750.6   86.24    3903   83.72  4050.6   81.61  4145.1    84.7  4197.3   84.77
    4317   83.55  4440.5   76.56  4524.5   71.01    4552   70.62  4696.4   65.05
  4761.5   64.89  4871.3   58.23  4949.5      57  4983.9   54.32  4984.7   51.94
  4985.2   51.44  5014.9   51.94  5018.3   55.15  5023.5   56.53    5063   57.66
  5092.3    62.2  5174.8    61.1  5275.9   61.35  5373.2   63.95  5505.5   71.01
  5579.5   77.94  5691.7   86.49  5717.9   88.38  5805.7   93.63  5854.3   94.91
#Mann= 15 ,-1 , 0
  3750.6     .05       0    3903     .07       0  4197.3     .05       0
  4440.5     .07       0    4552     .05       0  4871.3     .07       0
  4984.7     .05       0  5014.9     .07       0  5174.8     .12       0
  5275.9      .1       0  5505.5     .07       0  5579.5      .1       0
  5691.7     .12       0  5717.9     .07       0  5805.7     .05       0
Bank Sta=4984.7,5014.9
XS Rating Curve= 0 ,0
Exp/Cntr=0.3,0.1

Type RM Length L Ch R = 1 ,33617   ,651,651,651
BEGIN DESCRIPTION:
Mapping XS 36ee6b91
END DESCRIPTION:
XS GIS Cut Line= 3
       2589423.6     13469698.86      2588664.07     13468774.41
      2588130.25       13468514.
#Sta/Elev= 30
  3774.2   84.82  3835.1   83.31  3947.1   81.21  4066.9   82.36  4138.6   80.43
  4173.8   81.61  4322.8   69.38  4448.8   64.31  4507.5   63.57  4585.7      65
  4692.6   62.29  4727.7   62.94  4820.3    56.2  4834.6   56.76  4864.1   54.47
  4912.8   57.76  4962.4   53.74    4967   53.07  4968.4   51.34  4968.9   50.84
  4998.6   51.34  5000.5   54.62    5006    59.1  5014.1   60.23  5113.1      63
  5180.7   67.38  5186.3    69.1    5232   71.24  5515.7   90.84  5564.6   92.14
#Mann= 8 ,-1 , 0
  3774.2     .05       0  3835.1     .07       0  4448.8     .05       0
  4864.1     .12       0  4968.4     .05       0  4998.6     .12       0
    5232     .07       0  5515.7      .1       0
Bank Sta=4968.4,4998.6
XS Rating Curve= 0 ,0
Exp/Cntr=0.3,0.1