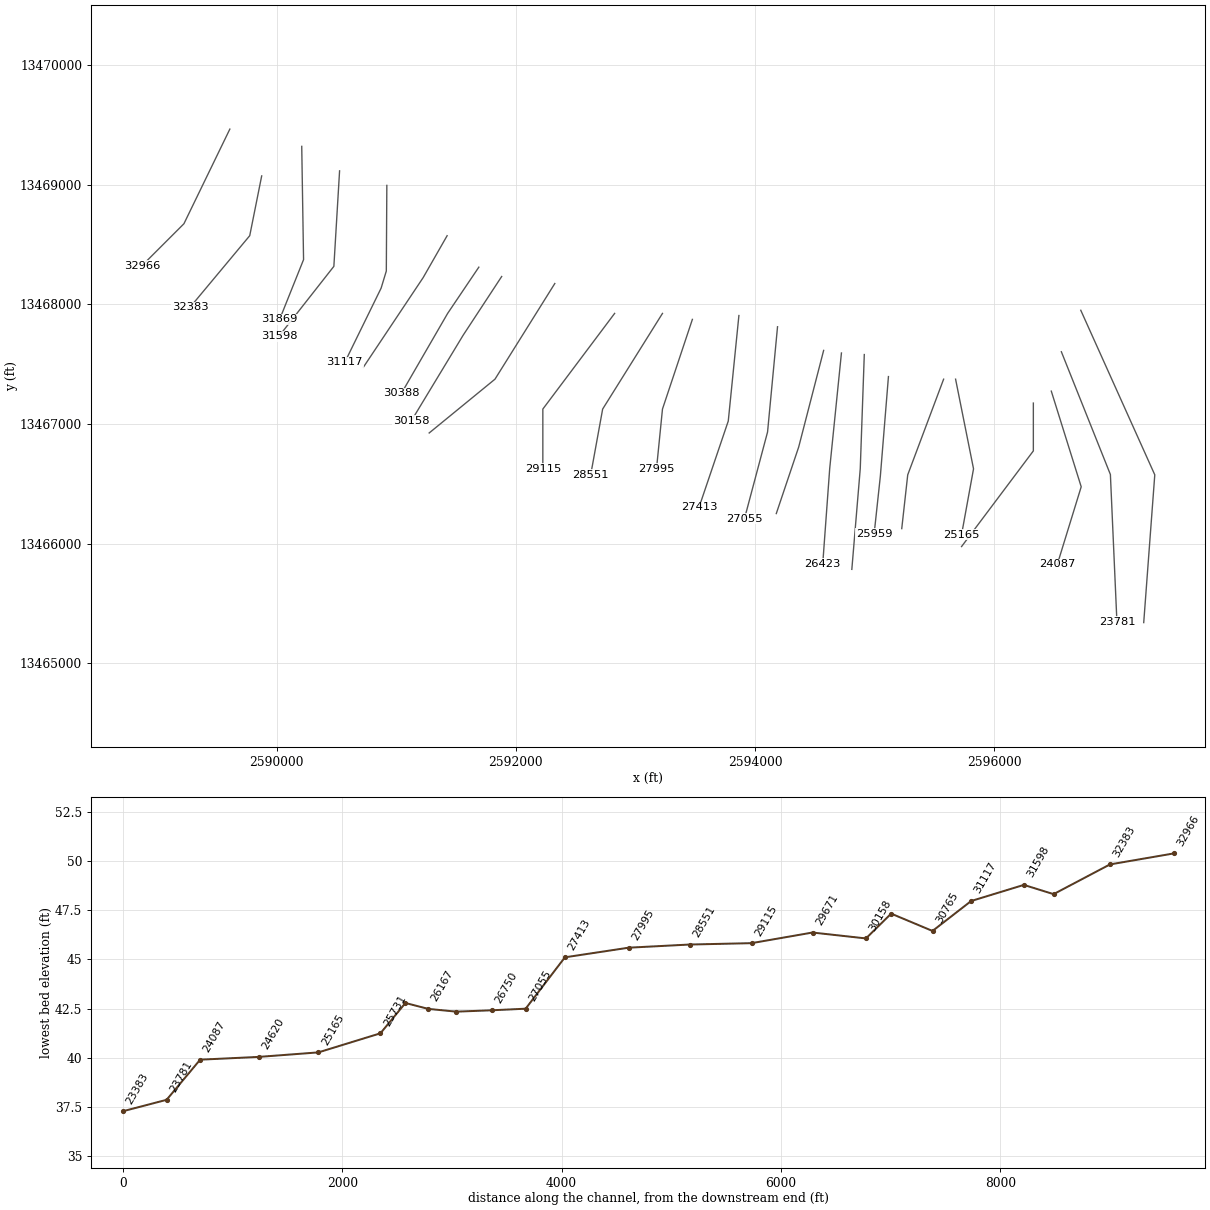
HEC-RAS study DRY CREEK.prj: DRY CREEK Base Level Engineering

--- DRY CREEK.g01 (geometry) --- (continued)

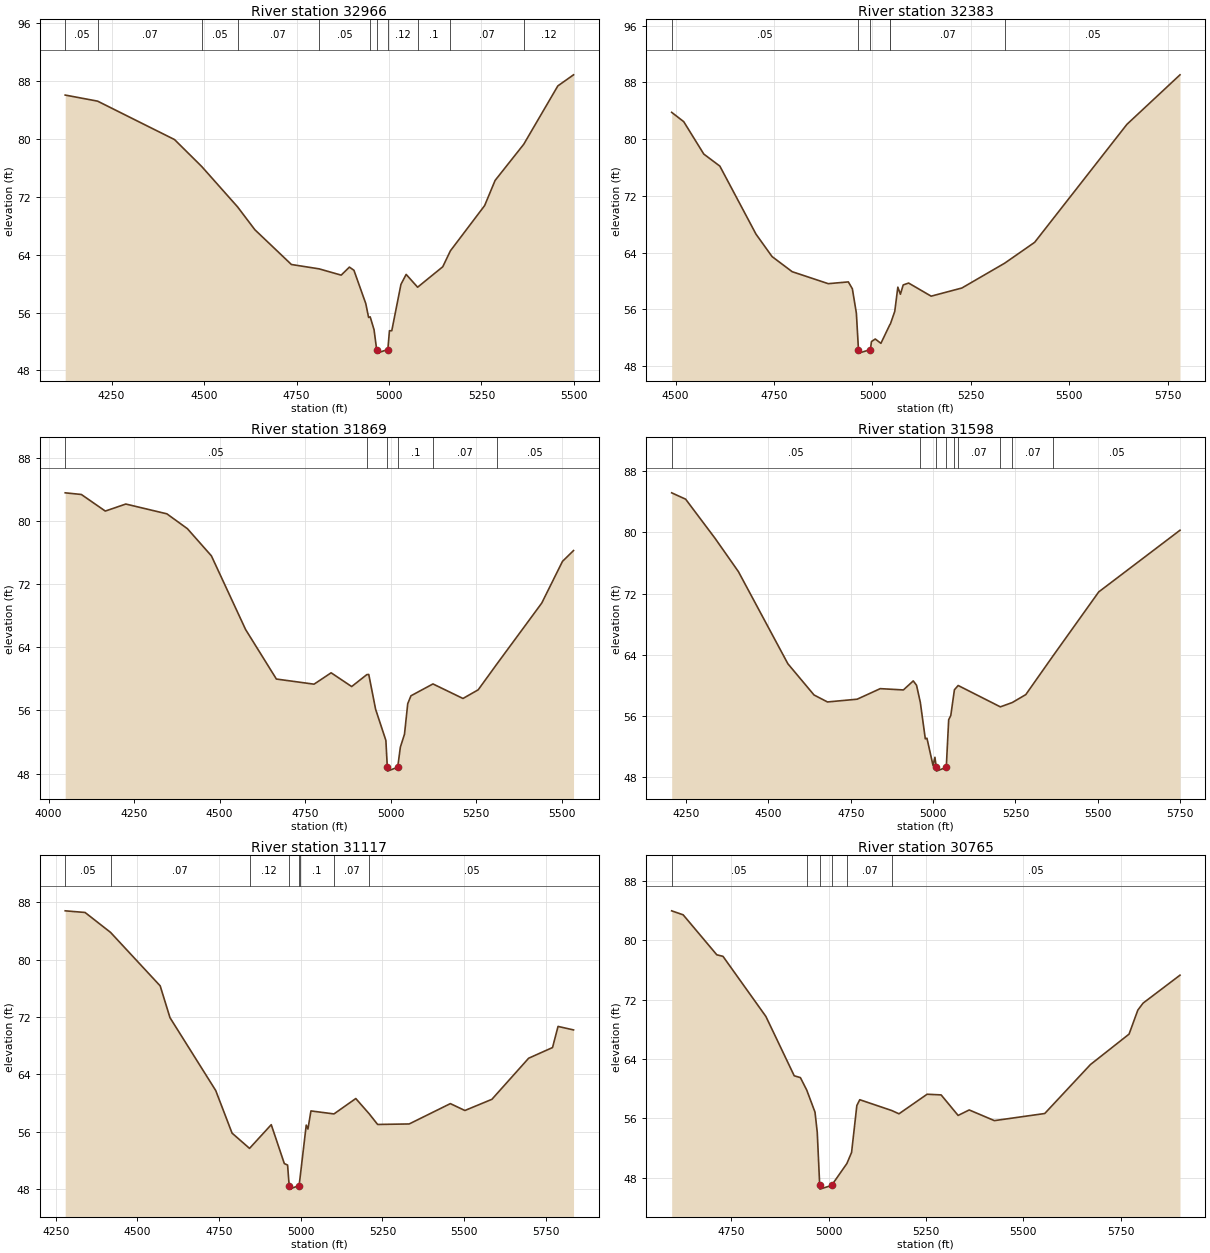
Type RM Length L Ch R = 1 ,32966   ,583,583,583
BEGIN DESCRIPTION:
DRY CREEK 40.0
END DESCRIPTION:
XS GIS Cut Line= 3
      2589608.78     13469466.47        2589225.       13468675.
      2588874.99     13468324.99
#Sta/Elev= 30
  4124.5   86.09    4212   85.25  4420.2   79.93  4493.6   76.21  4590.5   70.63
  4637.4   67.46  4736.2   62.65  4810.9   62.05  4870.8   61.18    4893   62.29
  4905.3   61.85  4937.4   57.23  4944.9   55.33  4949.2   55.41  4959.7   53.62
  4966.7   50.89  4967.2   50.39    4997   50.89  5001.3   53.49  5007.6   53.49
  5032.4    59.9  5046.5   61.28  5077.5   59.51  5145.5   62.34  5166.1   64.54
  5258.7    70.8    5287   74.28  5364.4   79.28  5456.7   87.36  5499.1   88.89
#Mann= 11 ,-1 , 0
  4124.5     .05       0    4212     .07       0  4493.6     .05       0
  4590.5     .07       0  4810.9     .05       0  4949.2     .12       0
  4966.7     .05       0    4997     .12       0  5077.5      .1       0
  5166.1     .07       0  5364.4     .12       0
Bank Sta=4966.7,4997
XS Rating Curve= 0 ,0
Exp/Cntr=0.3,0.1

Type RM Length L Ch R = 1 ,32383   ,514,514,514
BEGIN DESCRIPTION:
DRY CREEK 39.0
END DESCRIPTION:
XS GIS Cut Line= 3
      2589875.01     13469075.03        2589775.       13468575.
      2589274.97     13467974.96
#Sta/Elev= 30
  4490.1   83.77  4520.7   82.46  4571.7   77.89  4612.5   76.19  4704.3    66.6
  4745.1   63.44  4796.1   61.31  4887.8   59.62  4938.8   59.87    4949    58.9
  4959.2   55.46  4964.5   50.33    4965   49.83  4994.8   50.33  4997.5   51.46
  5007.2   51.82  5021.5   51.21  5044.2   53.84  5045.6   53.94  5056.7   55.72
  5064.5   59.13    5071   58.13  5078.1   59.44  5091.8   59.71  5149.1   57.86
  5227.2   59.01  5335.9   62.51    5412   65.45  5646.3   82.08  5781.1   89.06
#Mann= 6 ,-1 , 0
  4490.1     .05       0  4964.5     .05       0  4994.8     .05       0
  5044.2      .1       0  5045.6     .07       0  5335.9     .05       0
Bank Sta=4964.5,4994.8
XS Rating Curve= 0 ,0
Exp/Cntr=0.3,0.1

Type RM Length L Ch R = 1 ,31869   ,271,271,271
BEGIN DESCRIPTION:
DRY CREEK 38.0
END DESCRIPTION:
XS GIS Cut Line= 3
      2590209.72      13469322.2        2590225.       13468375.
      2590025.01     13467875.04
#Sta/Elev= 30
  4048.5   83.56  4095.7   83.35  4165.7   81.25  4225.7   82.14  4345.7    80.9
  4405.7   79.02  4475.8   75.58  4575.8   66.25  4665.8   59.98  4775.8   59.33
  4825.8   60.77  4885.8   59.03  4930.1   60.54  4935.8   60.56  4955.8   56.15
  4985.8   52.21    4990   48.82  4990.5   48.32  5020.4   48.82  5028.1   51.35
  5040.2   52.99  5049.7   56.86  5059.1   57.86  5123.4   59.36  5211.2   57.52
  5255.7   58.62  5309.9   61.86  5441.4    69.6    5502   74.88  5534.3   76.25
#Mann= 6 ,-1 , 0
  4048.5     .05       0  4930.1      .1       0    4990     .05       0
  5020.4      .1       0  5123.4     .07       0  5309.9     .05       0
Bank Sta=4990,5020.4
XS Rating Curve= 0 ,0
Exp/Cntr=0.3,0.1

Type RM Length L Ch R = 1 ,31598   ,481,481,481
BEGIN DESCRIPTION:
DRY CREEK 37.0
END DESCRIPTION:
XS GIS Cut Line= 3
      2590526.05      13469117.3      2590478.31     13468318.68
      2590019.12     13467733.86
#Sta/Elev= 30
  4206.3   85.16  4248.7   84.33  4338.8   79.17    4409   74.86  4559.2   62.82
  4638.6   58.74  4679.4   57.83  4769.6   58.19  4839.7   59.57  4909.9    59.4
  4939.9   60.58  4949.9   60.01  4961.4   57.77  4976.5   53.01  4981.5   53.09
    5000   49.52  5005.7    50.6  5009.8   49.29  5010.3   48.79  5040.2   49.29
  5047.5   55.51  5053.9   56.06  5064.9   59.42  5076.3   59.98  5204.4   57.19
  5240.4   57.75  5281.6   58.79    5364   63.83  5503.1   72.21  5749.9   80.27
#Mann= 9 ,-1 , 0
  4206.3     .05       0  4961.4     .12       0  5009.8     .05       0
  5040.2     .12       0  5064.9      .1       0  5076.3     .07       0
  5204.4     .05       0  5240.4     .07       0    5364     .05       0
Bank Sta=5009.8,5040.2
XS Rating Curve= 0 ,0
Exp/Cntr=0.3,0.1

Type RM Length L Ch R = 1 ,31117   ,352,352,352
BEGIN DESCRIPTION:
Mapping XS c7183a8c
END DESCRIPTION:
XS GIS Cut Line= 4
      2590921.02     13468995.75      2590916.68     13468279.62
      2590873.28     13468136.39      2590569.74     13467516.31
#Sta/Elev= 30
  4278.9   86.83  4339.7    86.6  4417.7   83.82  4569.7   76.35  4599.7   71.91
  4739.7   61.74  4789.7   55.79  4843.2   53.66  4909.7   56.97  4949.7   51.54
  4959.7   51.33  4964.5   48.47    4965   47.97  4994.9   48.47  4997.7   49.49
  5016.8   56.91    5022   56.36  5031.2   58.89  5101.7   58.47  5168.5   60.62
  5209.9   58.47  5235.3      57    5332   57.07    5458   59.91  5502.5   58.95
  5585.2   60.51  5697.7   66.25  5770.8   67.74  5787.7   70.69  5835.1    70.2
#Mann= 8 ,-1 , 0
  4278.9     .05       0  4417.7     .07       0  4843.2     .12       0
  4964.5     .05       0  4994.9     .12       0  4997.7      .1       0
  5101.7     .07       0  5209.9     .05       0
Bank Sta=4964.5,4994.9
XS Rating Curve= 0 ,0
Exp/Cntr=0.3,0.1

Type RM Length L Ch R = 1 ,30765   ,377,377,377
BEGIN DESCRIPTION:
DRY CREEK 36.0
END DESCRIPTION:
XS GIS Cut Line= 3
      2591424.98     13468574.96        2591225.       13468225.
      2590724.97     13467474.96
#Sta/Elev= 30
  4597.3   83.99  4626.8   83.45  4713.1   78.06    4729   77.85  4839.1   69.74
  4911.8   61.74  4927.7   61.49    4944    59.8  4965.1   56.84  4970.9   54.12
  4977.2   46.95  4977.7   46.45  5007.7   46.95  5046.9    49.9    5059    51.4
  5072.5   57.73    5080   58.51  5162.2   57.05  5180.6   56.61  5252.8   59.25
  5288.8   59.16  5332.4   56.39  5360.9   57.13  5425.5   55.69  5554.7   56.65
  5671.9   63.25  5771.1   67.36  5793.6    70.6  5807.1   71.54  5901.8   75.31
#Mann= 6 ,-1 , 0
  4597.3     .05       0    4944     .07       0  4977.2     .05       0
  5007.7     .07       0  5046.9     .07       0  5162.2     .05       0
Bank Sta=4977.2,5007.7
XS Rating Curve= 0 ,0
Exp/Cntr=0.3,0.1

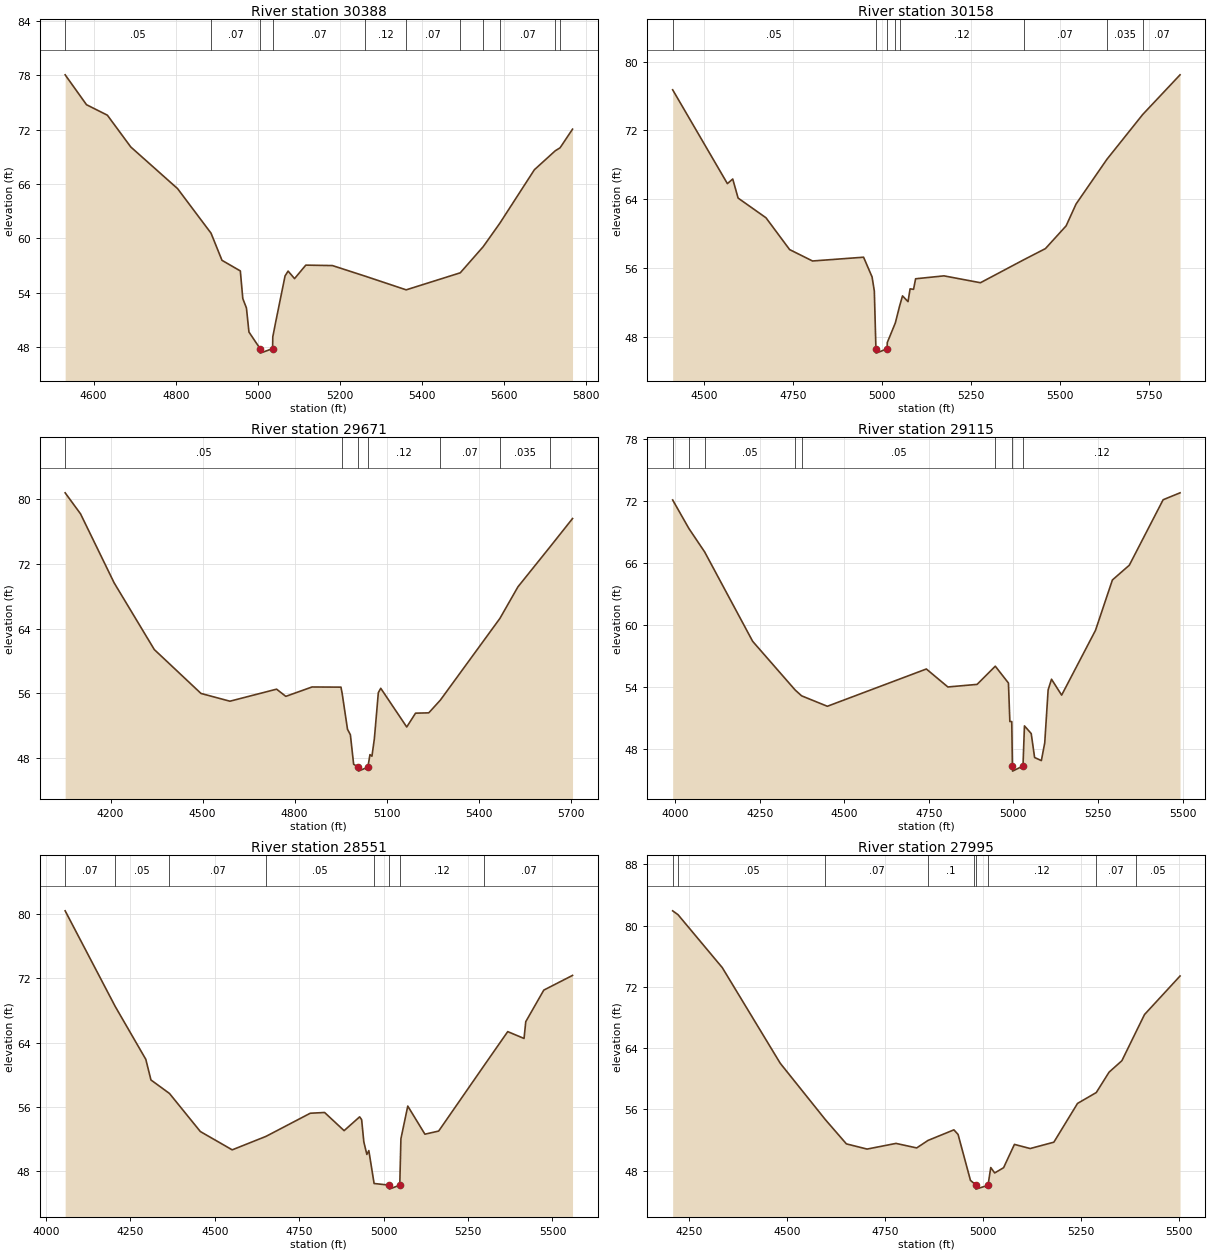
Type RM Length L Ch R = 1 ,30388   ,230,230,230
BEGIN DESCRIPTION:
Mapping XS 0bd2df6d
END DESCRIPTION:
XS GIS Cut Line= 3
      2591689.95     13468311.79      2591429.52     13467925.48
      2591044.08     13467258.54
#Sta/Elev= 30
  4530.5   78.07  4582.5   74.77  4633.4   73.61  4690.4    70.1  4804.4    65.5
  4885.9   60.58  4912.6   57.58  4957.3   56.41  4963.3   53.36  4972.2   52.31
  4978.3   49.66  5005.4   47.83  5005.9   47.33  5035.9   47.83  5036.4   49.13
  5043.2   50.71  5066.3   55.86  5073.7   56.39  5089.4   55.56  5116.8   57.05
  5181.8      57  5261.5   55.83  5361.4   54.32  5493.1    56.2  5548.9   59.08
    5589   61.64  5673.8   67.59  5724.6   69.68  5736.3   70.01  5766.7   72.07
#Mann= 11 ,-1 , 0
  4530.5     .05       0  4885.9     .07       0  5005.4     .05       0
  5035.9     .07       0  5261.5     .12       0  5361.4     .07       0
  5493.1    .035       0  5548.9     .05       0    5589     .07       0
  5724.6    .035       0  5736.3     .05       0
Bank Sta=5005.4,5035.9
XS Rating Curve= 0 ,0
Exp/Cntr=0.3,0.1

Type RM Length L Ch R = 1 ,30158   ,487,487,487
BEGIN DESCRIPTION:
DRY CREEK 35.0
END DESCRIPTION:
XS GIS Cut Line= 3
       2591880.9     13468233.64      2591558.33     13467741.66
      2591124.99     13467024.99
#Sta/Elev= 30
  4411.7   76.71  4565.5   65.79  4580.5   66.33  4595.6   64.11  4673.9   61.82
  4740.3   58.12  4804.7   56.79  4948.2   57.23  4972.1   54.93  4978.4   53.29
  4982.9   46.57  4983.4   46.07  5014.1   46.57  5014.9   47.31  5037.4   49.58
  5049.7   51.59  5057.6   52.73  5073.1   52.06  5078.9   53.55  5088.6   53.49
  5094.4   54.72    5174   55.06  5276.6   54.26  5398.2   56.93  5459.2   58.23
  5517.4   60.88  5545.3   63.42  5631.8   68.61  5732.5   73.83  5837.5   78.45
#Mann= 8 ,-1 , 0
  4411.7     .05       0  4982.9     .05       0  5014.1     .05       0
  5037.4    .035       0  5049.7     .12       0  5398.2     .07       0
  5631.8    .035       0  5732.5     .07       0
Bank Sta=4982.9,5014.1
XS Rating Curve= 0 ,0
Exp/Cntr=0.3,0.1

Type RM Length L Ch R = 1 ,29671   ,556,556,556
BEGIN DESCRIPTION:
DRY CREEK 34.0
END DESCRIPTION:
XS GIS Cut Line= 3
      2592324.98     13468174.96        2591825.       13467375.
      2591274.99     13466924.99
#Sta/Elev= 30
  4052.2    80.8  4102.3    78.2  4211.9   69.66  4342.8   61.41    4495   55.98
  4589.3   55.02  4741.4   56.51  4771.5   55.62    4857   56.78  4951.3   56.76
  4955.2   55.98  4972.6   51.55    4982   50.87  4992.6   47.22  5007.9   46.87
  5008.4   46.37  5039.1   46.87  5045.8   48.41  5052.3   48.22  5060.2   50.38
  5073.1   56.08    5081   56.62  5165.7   51.83  5194.4   53.54  5237.5   53.58
  5275.2   55.15  5469.4   65.26  5528.2   69.17  5631.3   74.04  5706.2   77.62
#Mann= 7 ,-1 , 0
  4052.2     .05       0  4955.2     .12       0  5007.9     .05       0
  5039.1     .12       0  5275.2     .07       0  5469.4    .035       0
  5631.3     .07       0
Bank Sta=5007.9,5039.1
XS Rating Curve= 0 ,0
Exp/Cntr=0.3,0.1

Type RM Length L Ch R = 1 ,29115   ,564,564,564
BEGIN DESCRIPTION:
DRY CREEK 33.0
END DESCRIPTION:
XS GIS Cut Line= 3
      2592825.01     13467925.01        2592225.       13467125.
        2592225.     13466625.01
#Sta/Elev= 30
  3992.6   72.09  4040.5   69.33  4087.3   67.05  4229.1    58.4  4354.6   53.69
  4373.9   53.12  4449.9   52.11  4742.6   55.72  4806.2   53.98  4892.6   54.23
  4946.4   55.99  4985.3   54.36  4989.5   50.63  4995.1   50.63    4997   46.33
  4997.5   45.83  5028.3   46.33  5032.6   50.21  5052.6   49.47  5062.6   47.15
  5082.6   46.85  5092.6   48.57  5102.6   53.69  5112.6   54.73  5142.6   53.19
  5242.6   59.46  5292.6   64.34  5342.6   65.77  5442.6   72.11  5492.6   72.78
#Mann= 8 ,-1 , 0
  3992.6     .05       0  4040.5     .07       0  4087.3     .05       0
  4354.6     .07       0  4373.9     .05       0  4946.4     .12       0
    4997     .05       0  5028.3     .12       0
Bank Sta=4997,5028.3
XS Rating Curve= 0 ,0
Exp/Cntr=0.3,0.1

Type RM Length L Ch R = 1 ,28551   ,556,556,556
BEGIN DESCRIPTION:
DRY CREEK 32.0
END DESCRIPTION:
XS GIS Cut Line= 3
      2593224.99     13467924.98        2592725.       13467125.
        2592625.     13466574.99
#Sta/Elev= 30
    4057   80.41    4205   68.52  4295.8   61.92  4311.1   59.35  4365.9   57.67
  4457.3   52.93  4551.7   50.65  4651.8   52.33  4782.8   55.21  4825.3    55.3
    4883   53.04    4929   54.76  4934.9   54.41  4941.4   51.64  4950.3   50.08
  4956.2   50.56  4971.8   46.46  5016.4   46.26  5016.9   45.76  5047.8   46.26
  5051.2   52.03  5071.5    56.1  5122.3    52.6    5163   52.99  5298.2   61.19
  5367.5   65.37  5415.8   64.52  5420.9   66.61  5474.3   70.54  5559.4   72.37
#Mann= 8 ,-1 , 0
    4057     .07       0    4205     .05       0  4365.9     .07       0
  4651.8     .05       0  4971.8     .12       0  5016.4     .05       0
  5047.8     .12       0  5298.2     .07       0
Bank Sta=5016.4,5047.8
XS Rating Curve= 0 ,0
Exp/Cntr=0.3,0.1

Type RM Length L Ch R = 1 ,27995   ,582,582,582
BEGIN DESCRIPTION:
DRY CREEK 31.0
END DESCRIPTION:
XS GIS Cut Line= 3
      2593475.01     13467875.03        2593225.       13467125.
        2593175.     13466624.99
#Sta/Elev= 30
  4209.1   81.94  4222.7   81.44  4335.6   74.52  4483.2   62.04    4598   54.69
  4651.8   51.51  4704.6   50.83  4778.3   51.57    4831   50.98  4859.9   51.96
  4925.9   53.34  4936.5   52.74  4968.1   46.74  4977.1   46.35  4981.4    46.1
  4981.9    45.6  5012.8    46.1  5019.8   48.42  5029.8   47.71  5052.5    48.4
  5080.1   51.44  5120.3    50.9  5180.6   51.73  5240.9   56.79  5288.7   58.21
  5321.3   60.87    5354   62.37  5390.2   66.16  5411.7    68.4  5502.2   73.43
#Mann= 9 ,-1 , 0
  4209.1     .07       0  4222.7     .05       0    4598     .07       0
  4859.9      .1       0  4977.1     .12       0  4981.4     .05       0
  5012.8     .12       0  5288.7     .07       0  5390.2     .05       0
Bank Sta=4981.4,5012.8
XS Rating Curve= 0 ,0
Exp/Cntr=0.3,0.1

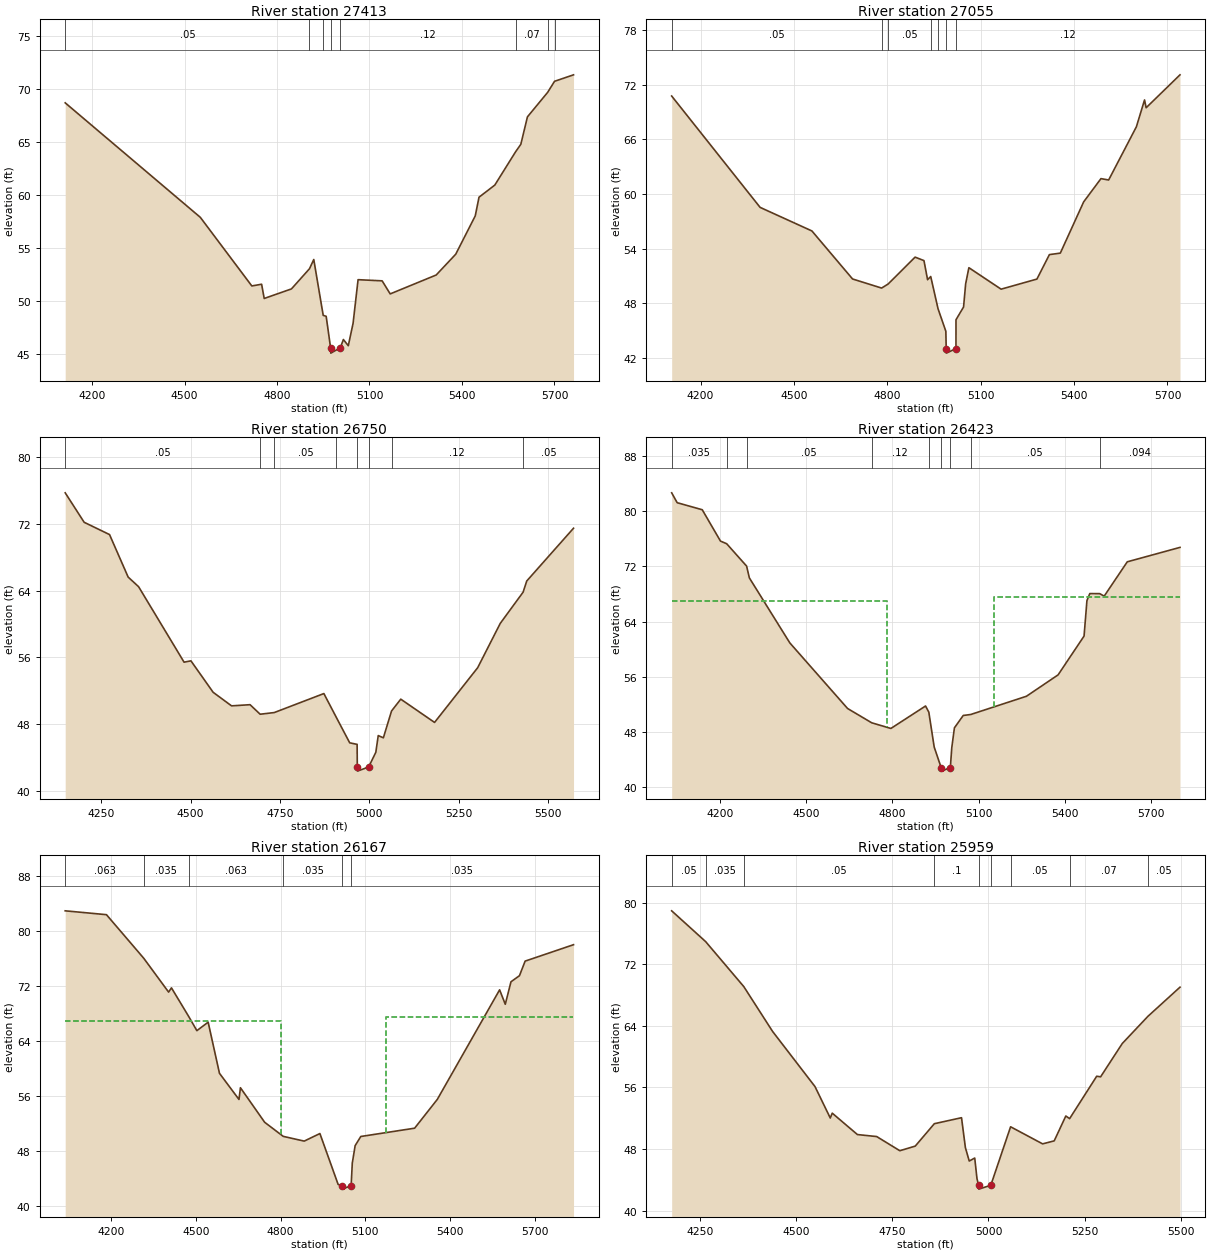
Type RM Length L Ch R = 1 ,27413   ,358,358,358
BEGIN DESCRIPTION:
DRY CREEK 30.0
END DESCRIPTION:
XS GIS Cut Line= 3
      2593863.81     13467907.21        2593775.       13467025.
      2593530.48     13466303.05
#Sta/Elev= 30
    4113   68.69  4551.4    57.9  4718.3   51.44  4750.1    51.6  4758.5   50.26
  4846.9   51.16  4905.4   53.06  4919.3   53.93  4949.9   48.67  4959.5   48.58
  4973.9   45.61  4974.4   45.11  5005.3   45.61  5015.4   46.39  5031.3   45.81
  5046.8   47.92    5063   52.03  5141.1   51.92  5167.2   50.69  5316.4   52.47
  5379.8   54.43  5443.1   58.04  5455.3    59.8  5506.5   60.94  5574.2   64.09
  5590.9   64.78  5612.4   67.37    5678   69.68  5700.3   70.72  5761.9   71.33
#Mann= 8 ,-1 , 0
    4113     .05       0  4905.4      .1       0  4949.9     .12       0
  4973.9     .05       0  5005.3     .12       0  5574.2     .07       0
    5678     .12       0  5700.3     .07       0
Bank Sta=4973.9,5005.3
XS Rating Curve= 0 ,0
Exp/Cntr=0.3,0.1

Type RM Length L Ch R = 1 ,27055   ,305,305,305
BEGIN DESCRIPTION:
Mapping XS 823d8e56
END DESCRIPTION:
XS GIS Cut Line= 3
      2594186.72     13467813.47      2594103.39     13466933.24
      2593910.77      13466209.6
#Sta/Elev= 30
  4107.3   70.76  4391.4   58.52  4557.8   55.93  4688.4   50.65  4781.8   49.65
  4802.8    50.1  4889.3   53.05  4917.8   52.67  4929.4   50.57  4939.5   50.92
  4963.1   47.37  4988.1    44.9  4989.2      43  4989.7    42.5  5020.6      43
  5020.7   46.17    5045   47.57  5051.7   50.11  5062.1   51.89  5165.6   49.53
  5280.7   50.64  5320.8   53.33  5355.8   53.49  5430.9   59.13  5486.4   61.68
  5511.1   61.53  5600.2   67.38  5626.4   70.33  5631.5   69.47  5740.3   73.09
#Mann= 7 ,-1 , 0
  4107.3     .05       0  4781.8     .07       0  4802.8     .05       0
  4939.5      .1       0  4963.1     .12       0  4989.2     .05       0
  5020.6     .12       0
Bank Sta=4989.2,5020.6
XS Rating Curve= 0 ,0
Exp/Cntr=0.3,0.1

Type RM Length L Ch R = 1 ,26750   ,327,327,327
BEGIN DESCRIPTION:
Mapping XS abae3c11
END DESCRIPTION:
XS GIS Cut Line= 3
      2594572.15     13467615.56       2594363.8     13466808.24
      2594176.29      13466250.9
#Sta/Elev= 30
  4149.3   75.68  4202.3   72.16  4273.3   70.69  4325.4   65.61  4354.6   64.46
  4481.8   55.44    4501    55.6  4563.1   51.84  4614.6   50.22  4666.3   50.36
  4694.6   49.22  4734.1   49.42  4872.8   51.69  4907.9   48.82  4945.1    45.8
  4965.8   45.62  4966.3   42.92  4966.8   42.42  4998.1   42.92  5018.1   44.67
  5024.9   46.67  5039.2    46.4  5062.1   49.61  5087.9   51.02  5182.4   48.24
    5303   54.78  5366.2   60.08  5430.1   63.81  5440.2   65.14  5571.1   71.45
#Mann= 8 ,-1 , 0
  4149.3     .05       0  4694.6     .07       0  4734.1     .05       0
  4907.9      .1       0  4966.3     .05       0  4998.1      .1       0
  5062.1     .12       0  5430.1     .05       0
Bank Sta=4966.3,4998.1
XS Rating Curve= 0 ,0
Exp/Cntr=0.3,0.1

Type RM Length L Ch R = 1 ,26423   ,256,256,256
BEGIN DESCRIPTION:
Mapping XS 489dee56
END DESCRIPTION:
XS GIS Cut Line= 3
      2594720.93     13467594.06      2594622.92     13466628.55
      2594564.68     13465831.95
#Sta/Elev= 30
  4031.5   82.65  4050.7   81.22  4137.9    80.2  4201.4   75.66  4222.9   75.28
  4292.3   72.04  4301.9   70.33  4442.7   60.92  4643.7   51.42  4727.7   49.35
  4794.5   48.53  4915.1   51.78  4926.5   50.89  4945.2   45.84  4969.5   42.85
    4970   42.35  5001.4   42.85  5006.3   45.71  5015.6   48.62  5046.3   50.41
  5072.3   50.55  5266.2   53.19  5376.5   56.29  5466.8   61.91  5476.8   67.05
  5486.8   68.06  5521.2   68.05  5536.9   67.69  5617.2   72.66  5800.7   74.75
#Mann= 9 ,-1 , 0
  4031.5    .035       0  4222.9    .063       0  4292.3     .05       0
  4727.7     .12       0  4926.5    .094       0  4969.5     .05       0
  5001.4    .094       0  5072.3     .05       0  5521.2    .094       0
#XS Ineff= 2 ,-1
    4032    4782      67    5153    5801    67.6
Permanent Ineff=
       F       F
Bank Sta=4969.5,5001.4
XS Rating Curve= 0 ,0
Exp/Cntr=0.3,0.1

Type RM Length L Ch R = 1 ,26167   ,208,208,208
BEGIN DESCRIPTION:
Mapping XS 4ab9c6af
END DESCRIPTION:
XS GIS Cut Line= 3
       2594911.9     13467581.02      2594878.13     13466625.94
      2594807.73     13465784.15
#Sta/Elev= 30
  4037.3      83  4183.4   82.44  4315.6   76.09  4403.5   71.17  4413.6   71.79
  4474.6   67.63  4503.6   65.56  4543.6   66.79  4583.7   59.35  4652.8   55.54
  4657.9   57.25  4743.8   52.22  4809.5   50.17  4883.8   49.48  4939.4   50.58
    5004   43.17  5018.1   42.99  5018.6   42.49    5050   42.99  5054.1   46.27
  5064.2   48.82  5084.2   50.15  5274.9   51.36  5355.2   55.55  5575.9    71.5
    5596    69.4  5616.1   72.67  5646.2   73.56  5666.3   75.68  5837.7   78.07
#Mann= 6 ,-1 , 0
  4037.3    .063       0  4315.6    .035       0  4474.6    .063       0
  4809.5    .035       0  5018.1    .035       0    5050    .035       0
#XS Ineff= 2 ,-1
    4037    4803      67    5175    5837    67.6
Permanent Ineff=
       F       F
Bank Sta=5018.1,5050
XS Rating Curve= 0 ,0
Exp/Cntr=0.3,0.1

Type RM Length L Ch R = 1 ,25959   ,228,228,228
BEGIN DESCRIPTION:
Mapping XS a767787a
END DESCRIPTION:
XS GIS Cut Line= 3
       2595113.8     13467396.75       2595046.1     13466563.44
      2594994.07     13466079.58
#Sta/Elev= 30
  4175.6   78.95    4264   74.95  4363.2   69.11  4438.2   63.28  4548.6   56.11
  4588.3   52.03  4593.4   52.66  4658.9   49.88  4709.1   49.62  4769.3   47.78
  4809.4   48.38  4859.1   51.29  4929.8   52.07  4939.9   48.18  4949.9   46.44
  4964.2   46.83    4970   44.18  4974.1   43.29  4974.6   42.79    5006   43.29
  5057.5   50.89  5140.8   48.67    5171   49.06  5201.2   52.29  5211.1   51.95
  5281.6   57.46  5291.7   57.38  5348.1   61.71  5414.8   65.24  5498.3   69.03
#Mann= 9 ,-1 , 0
  4175.6     .05       0    4264    .035       0  4363.2     .05       0
  4859.1      .1       0  4974.1     .05       0    5006      .1       0
  5057.5     .05       0  5211.1     .07       0  5414.8     .05       0
Bank Sta=4974.1,5006
XS Rating Curve= 0 ,0
Exp/Cntr=0.3,0.1

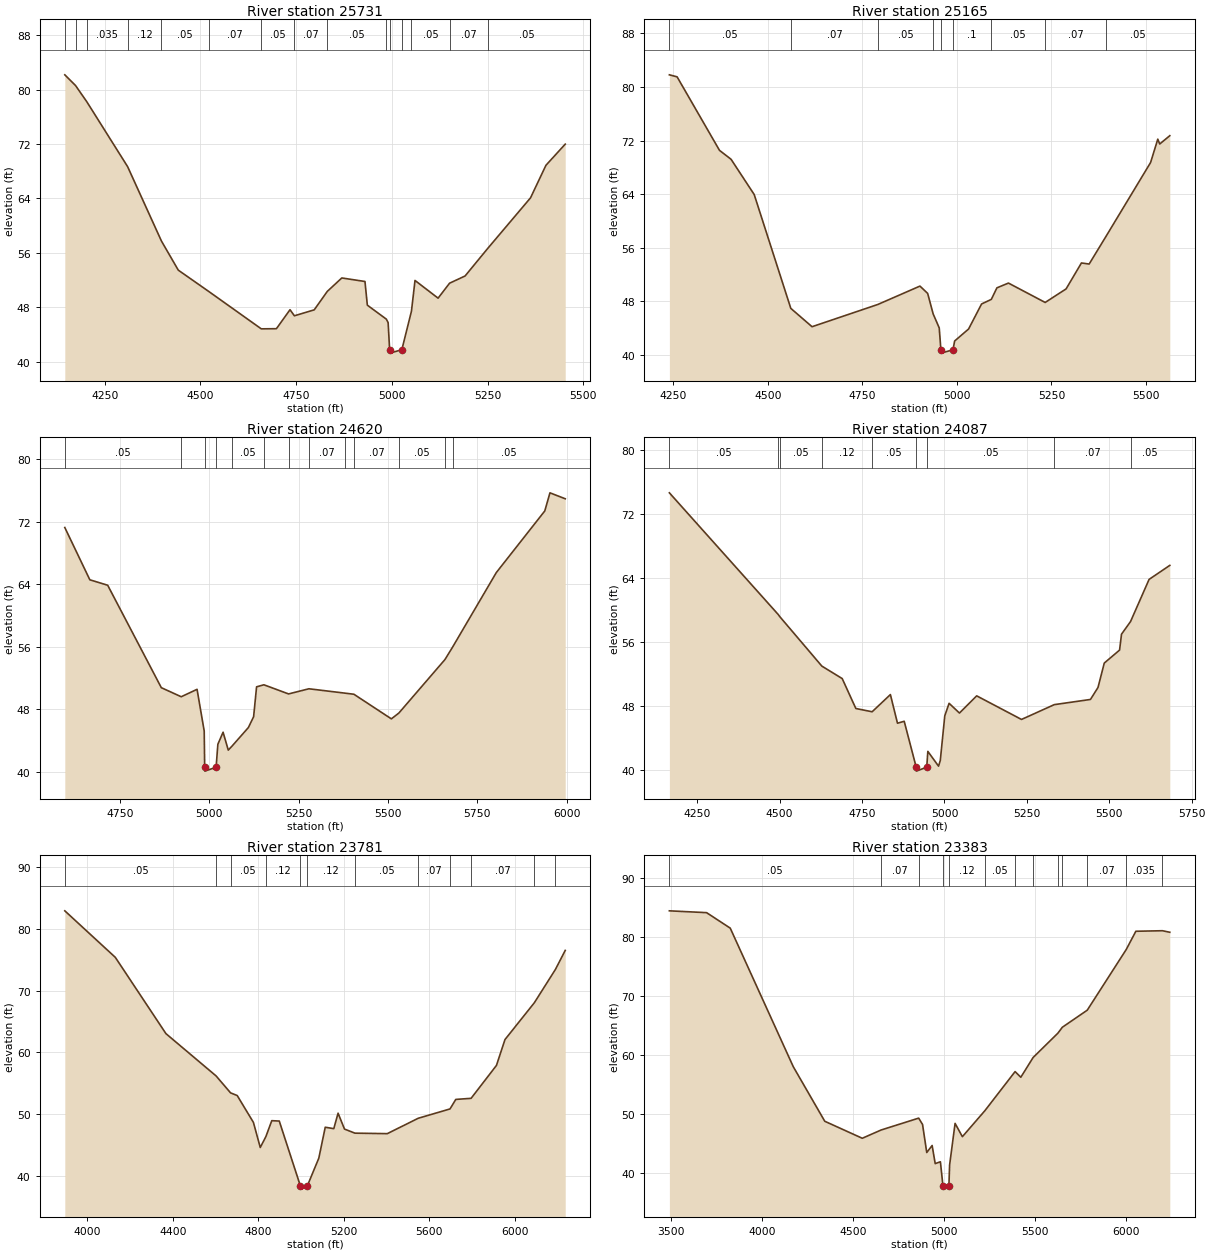
Type RM Length L Ch R = 1 ,25731   ,566,566,566
BEGIN DESCRIPTION:
DRY CREEK 27.0
END DESCRIPTION:
XS GIS Cut Line= 3
        2595575.     13467374.99        2595275.       13466575.
        2595225.     13466124.96
#Sta/Elev= 30
  4145.6   82.16  4173.6   80.59  4203.2   78.19  4309.7   68.66  4398.1   57.72
    4442   53.45  4522.5   50.28  4658.8   44.82  4698.3   44.84  4733.9   47.63
  4745.3   46.74  4797.1   47.61  4831.2   50.32  4869.2    52.3  4929.7   51.78
  4935.9    48.3  4985.6   46.24  4990.2   45.73  4994.1   41.75  4994.6   41.25
    5026   41.75  5051.1   47.41  5060.4   51.93  5120.7   49.33  5150.7   51.53
  5191.2   52.59  5250.2   56.63  5362.2   64.08  5402.4   68.86  5452.8   71.97
#Mann= 15 ,-1 , 0
  4145.6     .12       0  4173.6     .05       0  4203.2    .035       0
  4309.7     .12       0  4398.1     .05       0  4522.5     .07       0
  4658.8     .05       0  4745.3     .07       0  4831.2     .05       0
  4985.6      .1       0  4994.1     .05       0    5026      .1       0
  5051.1     .05       0  5150.7     .07       0  5250.2     .05       0
Bank Sta=4994.1,5026
XS Rating Curve= 0 ,0
Exp/Cntr=0.3,0.1

Type RM Length L Ch R = 1 ,25165   ,545,545,545
BEGIN DESCRIPTION:
DRY CREEK 26.0
END DESCRIPTION:
XS GIS Cut Line= 3
      2595674.99     13467375.03        2595825.       13466625.
        2595725.       13466075.
#Sta/Elev= 30
  4239.4    81.8  4259.8    81.5    4372   70.53  4402.6    69.2  4463.8   63.94
  4560.6   46.96  4616.8   44.22  4790.9   47.54  4902.3   50.28  4922.7   49.19
  4937.1   46.15  4953.3   44.04  4957.7   40.78  4958.2   40.28  4989.6   40.78
  4994.1   42.09    5031   43.88  5065.3   47.61  5091.1    48.3  5105.9   50.02
  5136.4   50.73  5233.6   47.84  5288.9   49.86  5329.5   53.73  5349.9   53.57
  5393.8   57.63  5512.5   68.72  5531.5    72.2  5536.6   71.48  5563.3   72.72
#Mann= 9 ,-1 , 0
  4239.4     .05       0  4560.6     .07       0  4790.9     .05       0
  4937.1      .1       0  4957.7     .05       0  4989.6      .1       0
  5091.1     .05       0  5233.6     .07       0  5393.8     .05       0
Bank Sta=4957.7,4989.6
XS Rating Curve= 0 ,0
Exp/Cntr=0.3,0.1

Type RM Length L Ch R = 1 ,24620   ,533,533,533
BEGIN DESCRIPTION:
DRY CREEK 25.0
END DESCRIPTION:
XS GIS Cut Line= 3
        2596325.     13467175.05        2596325.       13466775.
      2595725.03     13465975.04
#Sta/Elev= 30
  4595.7   71.23  4665.7   64.54  4715.7   63.84  4865.7   50.73  4921.4   49.57
  4965.7   50.52  4985.7   45.18    4987   40.55  4987.5   40.05    5019   40.55
  5023.9   43.49  5038.5   45.03    5053   42.74  5063.7   43.26  5109.3   45.63
  5123.9   47.01  5132.2   50.84  5152.7    51.1  5221.7   49.93  5278.6   50.59
  5379.7   50.03  5404.5   49.89  5509.3   46.74  5530.4   47.49  5659.2   54.33
  5680.4   55.91    5803   65.47  5938.5   73.35    5953   75.67  5995.7   74.91
#Mann= 13 ,-1 , 0
  4595.7     .05       0  4921.4     .12       0    4987     .05       0
    5019     .12       0  5063.7     .05       0  5152.7     .12       0
  5221.7     .05       0  5278.6     .07       0  5379.7     .05       0
  5404.5     .07       0  5530.4     .05       0  5659.2     .07       0
  5680.4     .05       0
Bank Sta=4987,5019
XS Rating Curve= 0 ,0
Exp/Cntr=0.3,0.1

Type RM Length L Ch R = 1 ,24087   ,306,306,306
BEGIN DESCRIPTION:
DRY CREEK 24.0
END DESCRIPTION:
XS GIS Cut Line= 3
      2596475.01     13467274.95        2596725.       13466475.
      2596524.99     13465824.98
#Sta/Elev= 30
  4165.5    74.7  4495.9   59.48  4500.9    59.2    4628   53.04  4689.8   51.48
  4731.2   47.74  4780.6   47.33    4836   49.48  4857.5    45.9  4877.9   46.14
  4914.3   40.41  4914.8   39.91  4946.3   40.41  4949.6   42.38  4982.1   40.53
  4987.4   41.24    5001   46.82  5014.1   48.39  5045.5   47.17  5097.8   49.32
  5233.8   46.37  5333.1   48.22    5443   48.87  5465.9   50.37  5484.9   53.42
  5531.3   55.04  5537.2   57.03  5564.5    58.6  5620.9   63.88  5683.7   65.63
#Mann= 9 ,-1 , 0
  4165.5     .05       0  4495.9     .12       0  4500.9     .05       0
    4628     .12       0  4780.6     .05       0  4914.3     .05       0
  4946.3     .05       0  5333.1     .07       0  5564.5     .05       0
Bank Sta=4914.3,4946.3
XS Rating Curve= 0 ,0
Exp/Cntr=0.3,0.1

Type RM Length L Ch R = 1 ,23781   ,398,398,398
BEGIN DESCRIPTION:
DRY CREEK 23.0
END DESCRIPTION:
XS GIS Cut Line= 3
      2596559.13     13467604.38      2596968.95     13466577.86
      2597023.62     13465343.47
#Sta/Elev= 30
  3894.7   82.92  4130.9   75.39  4367.8   63.04  4602.5   56.19  4670.2   53.45
  4701.2   53.02    4777   48.67    4809   44.61  4835.4   46.38  4862.9   48.95
  4897.9   48.89  4996.9   38.37  4997.4   37.87  5028.9   38.37  5082.9   42.88
    5113   47.89    5153   47.66    5173   50.16  5203.1   47.59  5251.9   46.93
  5403.3   46.85  5547.9   49.34  5696.7   50.85  5723.6   52.39  5795.3   52.57
  5913.8   57.89  5953.8   62.08  6091.1   68.04  6189.7   73.43  6235.6   76.51
#Mann= 12 ,-1 , 0
  3894.7     .05       0  4602.5     .12       0  4670.2     .05       0
  4835.4     .12       0  4996.9     .05       0  5028.9     .12       0
  5251.9     .05       0  5547.9     .07       0  5696.7     .12       0
  5795.3     .07       0  6091.1     .05       0  6189.7    .035       0
Bank Sta=4996.9,5028.9
XS Rating Curve= 0 ,0
Exp/Cntr=0.3,0.1

Type RM Length L Ch R = 1 ,23383   ,0,0,0
BEGIN DESCRIPTION:
DRY CREEK 22.0
END DESCRIPTION:
XS GIS Cut Line= 3
      2596721.43     13467951.31      2597339.99     13466575.02
      2597247.54     13465338.97
#Sta/Elev= 30
  3491.1   84.41  3695.4    84.1  3825.3   81.48  4171.5   58.02  4344.5   48.78
  4550.5    45.9  4653.8    47.3  4860.2   49.31  4881.5   48.24  4904.6   43.49
  4934.2   44.68    4951   41.61  4979.6   41.92  4993.8   37.79  4994.3   37.29
  5026.3   37.79  5030.1   41.37  5060.2   48.42  5100.3   46.17  5223.6   50.56
  5389.8   57.19  5421.2   56.23  5488.9   59.58  5624.7   63.69  5649.4    64.7
  5786.2   67.59  6000.2   77.86    6053   80.95  6199.3   81.04  6239.5   80.78
#Mann= 13 ,-1 , 0
  3491.1     .05       0  4653.8     .07       0  4860.2     .12       0
  4993.8     .05       0  5026.3     .12       0  5223.6     .05       0
  5389.8     .07       0  5488.9     .05       0  5624.7     .07       0
  5649.4     .05       0  5786.2     .07       0  6000.2    .035       0
  6199.3     .05       0
Bank Sta=4993.8,5026.3
XS Rating Curve= 0 ,0
Exp/Cntr=0.3,0.1

Chan Stop Cuts=-1
Use User Specified Reach Order=0
Composite Channel Slope=5