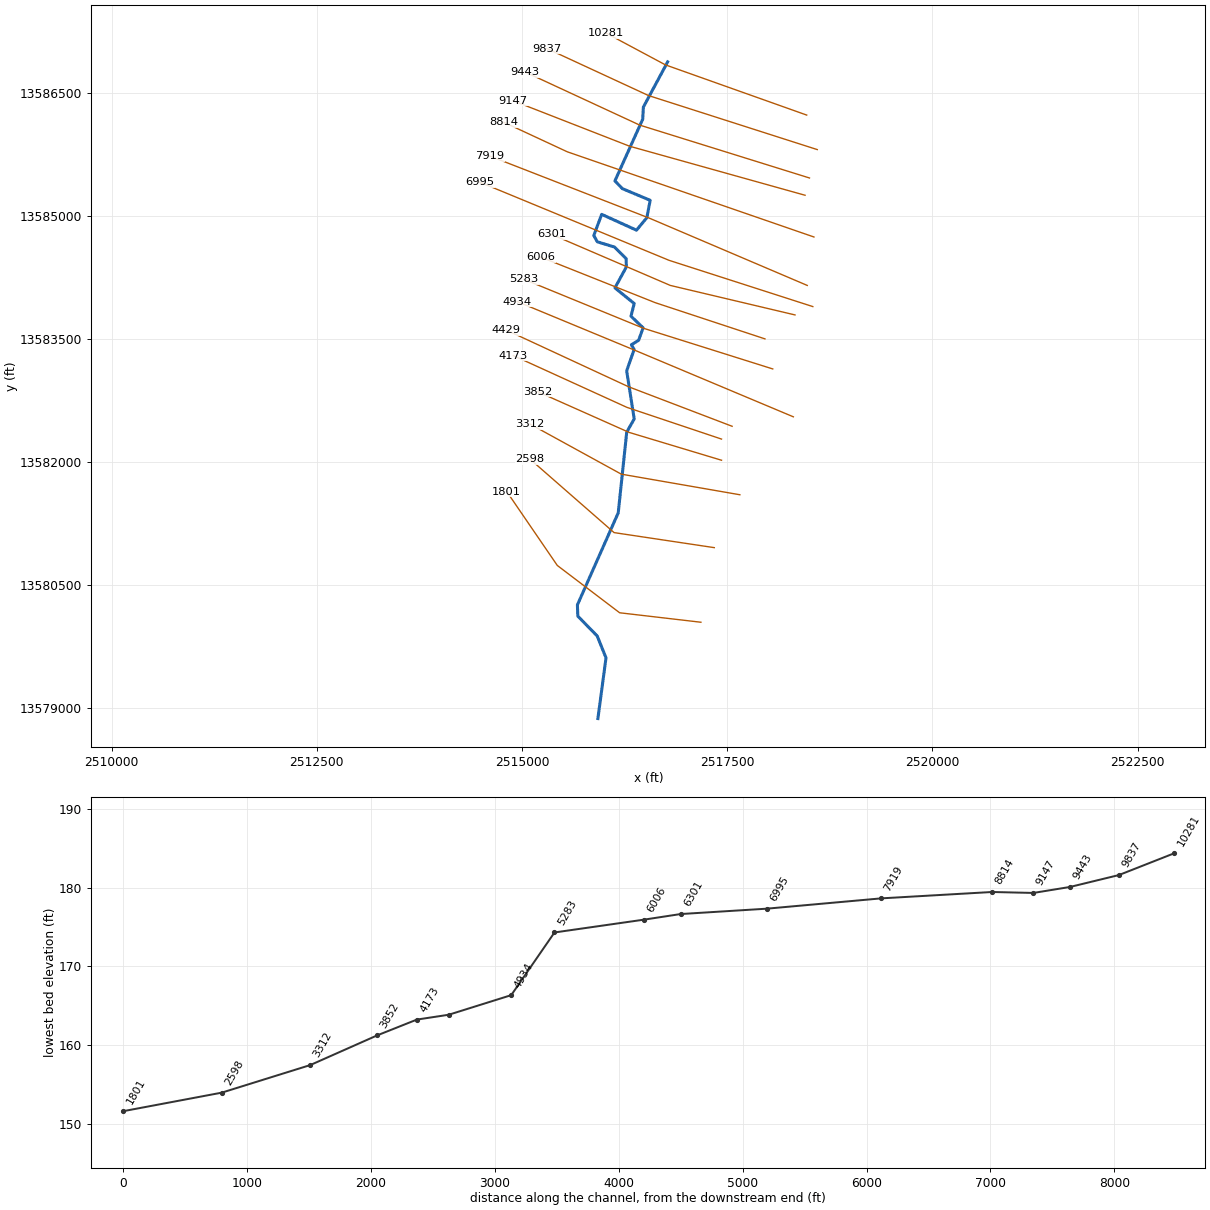
--- GOHLKE CREEK TRIBUTARY.prj (project) ---

Proj Title=GOHLKE CREEK TRIBUTARY Base Level Engineering
Current Plan=p01
Default Exp/Contr=0.3,0.1
English Units
Geom File=g01
Flow File=f01
Plan File=p01
Y Axis Title=Elevation
X Axis Title(PF)=Main Channel Distance
X Axis Title(XS)=Station
BEGIN DESCRIPTION:
GOHLKE CREEK TRIBUTARY
END DESCRIPTION:
DSS Export Rating Curves= 0
DSS Export Rating Curve Sorted= 0
DSS Export Volume Flow Curves= 0
DXF OffsetX= 0
DXF OffsetY= 0
DXF ScaleX= 1
DXF ScaleY= 10

--- GOHLKE CREEK TRIBUTARY.p01 (plan) ---

Plan Title=Multiple Run
Short Identifier=Multiple
Geom File=g01
Flow File=f01
Subcritical Flow
K Sum by GR= 0
Std Step Tol= 0.01
Critical Tol= 0.01
Num of Std Step Trials= 20
Max Error Tol= 0.3
Flow Tol Ratio= 0.001
Split Flow NTrial= 30
Split Flow Tol= 0.02
Split Flow Ratio= 0.02
Log Output Level= 0
Friction Slope Method= 1
Unsteady Friction Slope Method= 2
Unsteady Bridges Friction Slope Method= 1
Parabolic Critical Depth
Global Vel Dist=  1 , 1 , 1
Global Log Level= 0
CheckData=True
Encroach Param= -1, 0, 0, 0
BEGIN DESCRIPTION:
Multiple Run
END DESCRIPTION:

--- GOHLKE CREEK TRIBUTARY.f01 (steady flow) ---

Flow Title=Multiple
Number of Profiles=7
Profile Names=10-year,25-year,50-year,1pct_min,100-year,1pct_plu,500-year
River Rch & RM= GOHLKE CREEK TRI,Reach-1,10281
     425     666     878     561    1120    2234    1802
River Rch & RM= GOHLKE CREEK TRI,Reach-1,9443
     642    1031    1380     895    1786    3563    2960
River Rch & RM= GOHLKE CREEK TRI,Reach-1,7919
     831    1352    1827    1194    2382    4752    4011
River Rch & RM= GOHLKE CREEK TRI,Reach-1,2598
     870    1420    1921    1257    2507    5003    4234
Boundary for River Rch & Prof#=GOHLKE CREEK TRI,Reach-1,1
Up Type=0
Dn Type=3
Dn Slope=0.005
Boundary for River Rch & Prof#=GOHLKE CREEK TRI,Reach-1,2
Up Type=0
Dn Type=3
Dn Slope=0.005
Boundary for River Rch & Prof#=GOHLKE CREEK TRI,Reach-1,3
Up Type=0
Dn Type=3
Dn Slope=0.005
Boundary for River Rch & Prof#=GOHLKE CREEK TRI,Reach-1,4
Up Type=0
Dn Type=3
Dn Slope=0.005
Boundary for River Rch & Prof#=GOHLKE CREEK TRI,Reach-1,5
Up Type=0
Dn Type=3
Dn Slope=0.005
Boundary for River Rch & Prof#=GOHLKE CREEK TRI,Reach-1,6
Up Type=0
Dn Type=3
Dn Slope=0.005
Boundary for River Rch & Prof#=GOHLKE CREEK TRI,Reach-1,7
Up Type=0
Dn Type=3
Dn Slope=0.005

--- GOHLKE CREEK TRIBUTARY.g01 (geometry) ---

Geom Title=Existing Conditions

River Reach=GOHLKE CREEK TRI,Reach-1
Reach XY= 30
      2516775.00     13586875.00      2516478.76     13586323.44
      2516471.24     13586176.56      2516132.31     13585424.89
      2516222.67     13585330.83      2516562.05     13585188.63
      2516521.18     13584976.58      2516395.27     13584824.60
      2515971.30     13585017.33      2515875.01     13584759.52
      2515918.45     13584682.74      2516127.30     13584619.17
      2516269.60     13584477.43      2516271.53     13584376.50
      2516132.69     13584121.33      2516367.52     13583931.06
      2516328.13     13583776.62      2516475.98     13583635.45
      2516421.28     13583483.19      2516332.93     13583428.57
      2516366.71     13583371.79      2516275.55     13583111.03
      2516367.47     13582524.99      2516276.20     13582364.50
      2516172.76     13581380.93      2515675.50     13580259.78
      2515680.45     13580122.55      2515916.86     13579881.06
      2516023.78     13579614.50      2515925.00     13578875.00

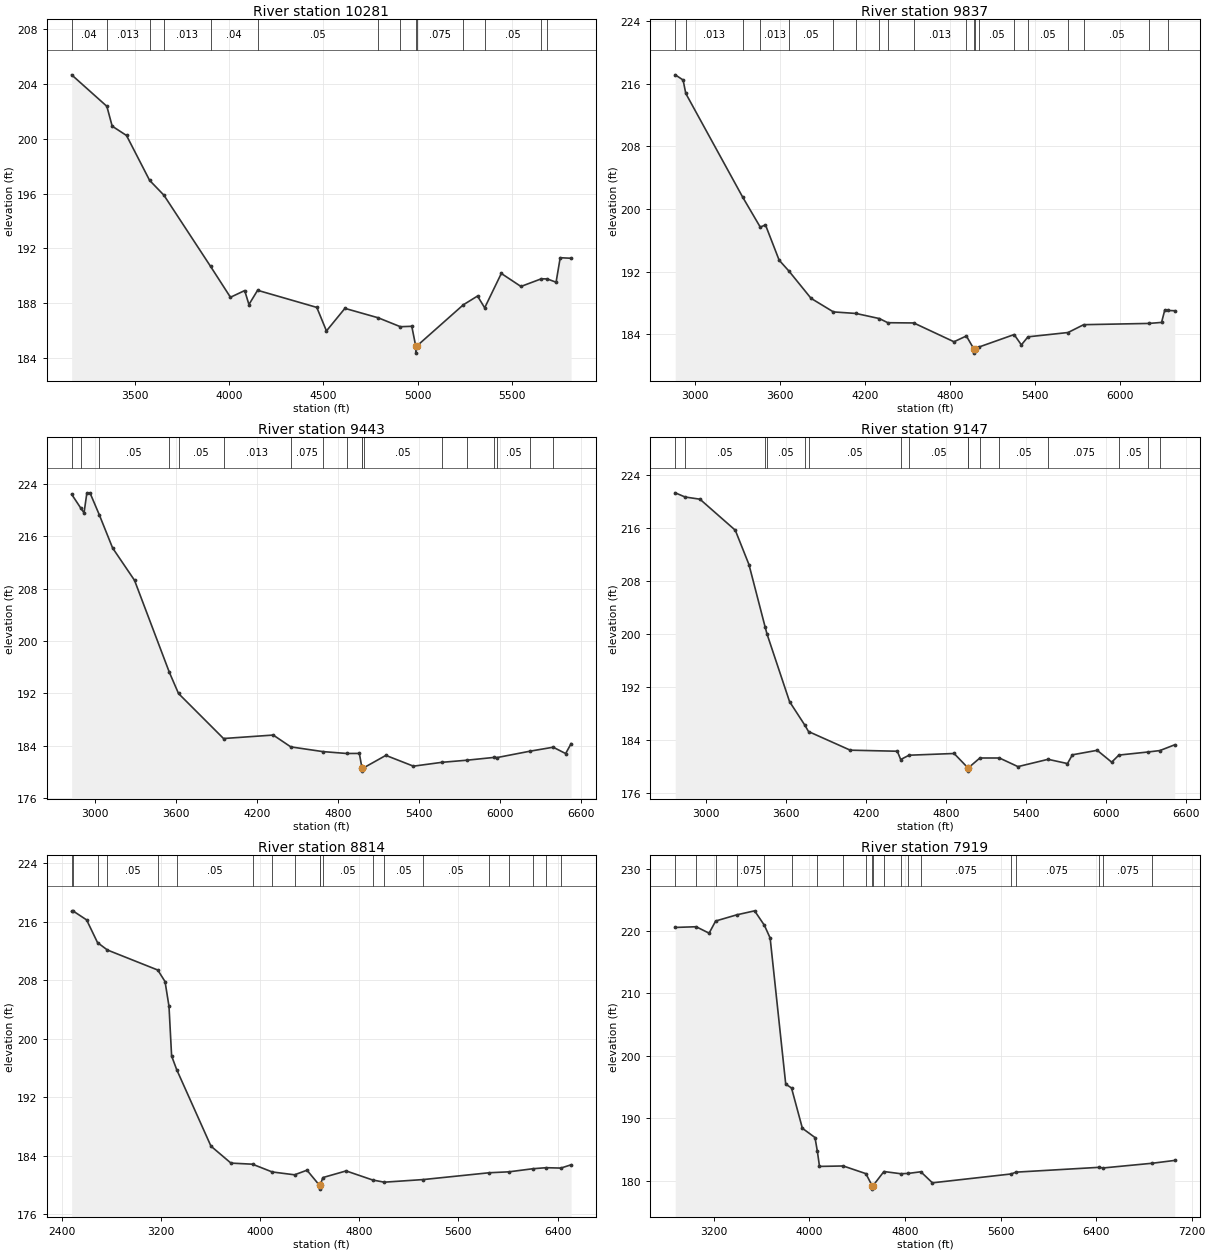
Type RM Length L Ch R = 1,10281,444,444,444
BEGIN DESCRIPTION:
GOHLKE CREEK TRIBUTARY 15.0
END DESCRIPTION:
XS GIS Cut Line= 3
      2518468.88     13586226.83      2516748.09     13586838.34
      2516024.99     13587225.00
#Sta/Elev= 30
  3166.2  204.68  3352.8  202.38  3381.0  200.93  3456.9  200.25  3579.3  196.97
  3654.9  195.89  3902.5  190.68  4007.6  188.43  4083.0  188.92  4105.5  187.90
  4151.4  188.94  4465.1  187.69  4516.2  185.97  4614.0  187.62  4790.7  186.93
  4907.8  186.28  4968.3  186.31  4989.4  184.85  4989.7  184.35  4993.4  184.85
  5241.3  187.88  5316.6  188.52  5354.5  187.66  5442.6  190.17  5546.6  189.22
  5654.8  189.78  5686.1  189.77  5732.8  189.53  5754.7  191.32  5812.4  191.28
#Mann=14,-1,0
  3166.2    0.04       0  3352.8   0.013       0  3579.3    0.05       0
  3654.9   0.013       0  3902.5    0.04       0  4151.4    0.05       0
  4790.7   0.013       0  4907.8   0.075       0  4989.4    0.05       0
  4993.4   0.075       0  5241.3   0.075       0  5354.5    0.05       0
  5654.8   0.075       0  5686.1    0.05       0
Bank Sta=4989.4,4993.4
Exp/Cntr=0.3,0.1

Type RM Length L Ch R = 1,9837,394,394,394
BEGIN DESCRIPTION:
Mapping XS b21c596d
END DESCRIPTION:
XS GIS Cut Line= 3
      2518597.69     13585806.36      2516542.78     13586464.20
      2515303.16     13587037.70
#Sta/Elev= 30
  2859.1  217.11  2914.4  216.45  2933.6  214.73  3334.1  201.53  3458.8  197.68
  3495.7  197.96  3592.1  193.46  3662.2  192.05  3817.2  188.59  3974.9  186.86
  4134.6  186.66  4299.0  186.01  4358.8  185.48  4541.7  185.45  4825.4  183.05
  4912.9  183.79  4966.7  182.10  4966.9  181.60  4970.7  182.10  5005.1  182.40
  5249.9  183.97  5300.8  182.65  5347.5  183.68  5630.2  184.23  5740.5  185.23
  6201.2  185.39  6289.9  185.52  6312.8  187.12  6334.8  187.04  6382.6  187.01
#Mann=20,-1,0
  2859.1    0.04       0  2933.6   0.013       0  3334.1    0.05       0
  3458.8   0.013       0  3662.2    0.05       0  3974.9   0.013       0
  4134.6    0.05       0  4299.0   0.013       0  4358.8    0.05       0
  4541.7   0.013       0  4912.9   0.075       0  4966.7    0.05       0
  4970.7   0.075       0  5005.1    0.05       0  5249.9   0.075       0
  5347.5    0.05       0  5630.2   0.075       0  5740.5    0.05       0
  6201.2   0.075       0  6334.8     0.1       0
Bank Sta=4966.7,4970.7
Exp/Cntr=0.3,0.1

Type RM Length L Ch R = 1,9443,296,296,296
BEGIN DESCRIPTION:
Mapping XS adaf88b2
END DESCRIPTION:
XS GIS Cut Line= 3
      2518502.78     13585460.47      2516434.27     13586104.76
      2515038.17     13586751.61
#Sta/Elev= 30
  2824.2  222.46  2891.0  220.37  2916.1  219.61  2937.1  222.64  2960.2  222.68
  3028.5  219.36  3128.1  214.24  3290.7  209.29  3548.9  195.22  3617.0  191.97
  3950.9  185.08  4319.6  185.61  4450.0  183.80  4687.4  183.08  4864.7  182.79
  4958.5  182.80  4977.7  180.59  4978.0  180.09  4981.7  180.59  4994.4  180.64
  5155.2  182.50  5359.6  180.85  5572.0  181.44  5755.5  181.76  5953.8  182.18
  5981.1  182.17  6226.6  183.15  6396.4  183.75  6488.8  182.78  6529.4  184.30
#Mann=18,-1,0
  2824.2    0.04       0  2891.0   0.013       0  3028.5    0.05       0
  3548.9   0.013       0  3617.0    0.05       0  3950.9   0.013       0
  4450.0   0.075       0  4687.4    0.05       0  4864.7   0.075       0
  4977.7    0.05       0  4981.7   0.075       0  4994.4    0.05       0
  5572.0   0.075       0  5755.5    0.05       0  5953.8   0.075       0
  5981.1    0.05       0  6226.6   0.075       0  6396.4     0.1       0
Bank Sta=4977.7,4981.7
Exp/Cntr=0.3,0.1

Type RM Length L Ch R = 1,9147,333,333,333
BEGIN DESCRIPTION:
Mapping XS 9114c47a
END DESCRIPTION:
XS GIS Cut Line= 3
      2518448.53     13585250.23      2516312.20     13585847.05
      2514890.27     13586401.95
#Sta/Elev= 30
  2770.0  221.30  2843.7  220.67  2955.2  220.34  3220.2  215.66  3322.7  210.48
  3443.2  201.12  3457.7  200.03  3627.1  189.81  3742.2  186.24  3769.2  185.30
  4081.9  182.49  4434.9  182.33  4460.1  181.08  4523.1  181.73  4860.6  181.99
  4963.8  179.83  4964.0  179.33  4967.8  179.83  5053.9  181.31  5200.3  181.31
  5339.4  180.01  5565.0  181.11  5710.6  180.47  5747.3  181.79  5933.3  182.47
  6042.0  180.68  6095.9  181.75  6315.9  182.22  6403.0  182.43  6514.5  183.30
#Mann=16,-1,0
  2770.0   0.013       0  2843.7    0.05       0  3443.2   0.013       0
  3457.7    0.05       0  3742.2   0.013       0  3769.2    0.05       0
  4460.1   0.075       0  4523.1    0.05       0  4963.8    0.05       0
  4967.8    0.05       0  5053.9   0.075       0  5200.3    0.05       0
  5565.0   0.075       0  6095.9    0.05       0  6315.9   0.075       0
  6403.0     0.1       0
Bank Sta=4963.8,4967.8
Exp/Cntr=0.3,0.1

Type RM Length L Ch R = 1,8814,895,895,895
BEGIN DESCRIPTION:
Mapping XS 89f57aa5
END DESCRIPTION:
XS GIS Cut Line= 3
      2518556.98     13584741.61      2515552.62     13585779.23
      2514782.80     13586137.24
#Sta/Elev= 30
  2481.1  217.44  2490.7  217.52  2601.8  216.28  2690.0  213.17  2769.7  212.16
  3175.8  209.42  3234.3  207.84  3266.1  204.46  3287.2  197.67  3327.9  195.81
  3604.5  185.33  3765.7  183.01  3939.5  182.86  4098.2  181.80  4278.6  181.41
  4378.8  182.04  4480.7  179.95  4480.9  179.45  4484.8  179.95  4506.5  181.03
  4694.3  181.94  4908.2  180.70  5001.8  180.40  5317.1  180.76  5848.2  181.69
  6009.4  181.82  6199.9  182.24  6306.4  182.38  6426.0  182.33  6508.6  182.78
#Mann=20,-1,0
  2481.1    0.05       0  2490.7   0.075       0  2690.0   0.013       0
  2769.7    0.05       0  3175.8   0.013       0  3327.9    0.05       0
  3939.5   0.075       0  4098.2    0.05       0  4278.6   0.075       0
  4480.7    0.05       0  4484.8   0.075       0  4506.5    0.05       0
  4908.2   0.075       0  5001.8    0.05       0  5317.1    0.05       0
  5848.2   0.075       0  6009.4    0.05       0  6199.9   0.075       0
  6306.4     0.1       0  6426.0   0.075       0
Bank Sta=4480.7,4484.8
Exp/Cntr=0.3,0.1

Type RM Length L Ch R = 1,7919,924,924,924
BEGIN DESCRIPTION:
Mapping XS 5c6b2144
END DESCRIPTION:
XS GIS Cut Line= 3
      2518475.65     13584151.56      2516549.56     13584972.18
      2514605.38     13585728.98
#Sta/Elev= 30
  2877.9  220.57  3053.1  220.68  3161.2  219.65  3216.2  221.60  3393.3  222.59
  3542.2  223.23  3624.0  220.91  3672.1  218.87  3802.5  195.46  3850.9  194.85
  3941.9  188.39  4047.3  186.91  4067.4  184.69  4085.1  182.28  4283.8  182.35
  4473.3  181.12  4526.7  179.14  4527.0  178.64  4531.0  179.14  4624.2  181.46
  4764.0  181.11  4824.9  181.15  4933.1  181.42  5030.1  179.65  5689.2  181.07
  5729.3  181.36  6422.9  182.13  6457.6  182.03  6871.6  182.79  7057.8  183.24
#Mann=20,-1,0
  2877.9   0.013       0  3053.1   0.075       0  3216.2     0.1       0
  3393.3   0.075       0  3624.0   0.013       0  3850.9     0.1       0
  4067.4     0.1       0  4283.8    0.05       0  4473.3   0.075       0
  4526.7    0.05       0  4531.0   0.075       0  4624.2    0.05       0
  4764.0   0.075       0  4824.9     0.1       0  4933.1   0.075       0
  5689.2    0.05       0  5729.3   0.075       0  6422.9     0.1       0
  6457.6   0.075       0  6871.6     0.1       0
Bank Sta=4526.7,4531
Exp/Cntr=0.3,0.1

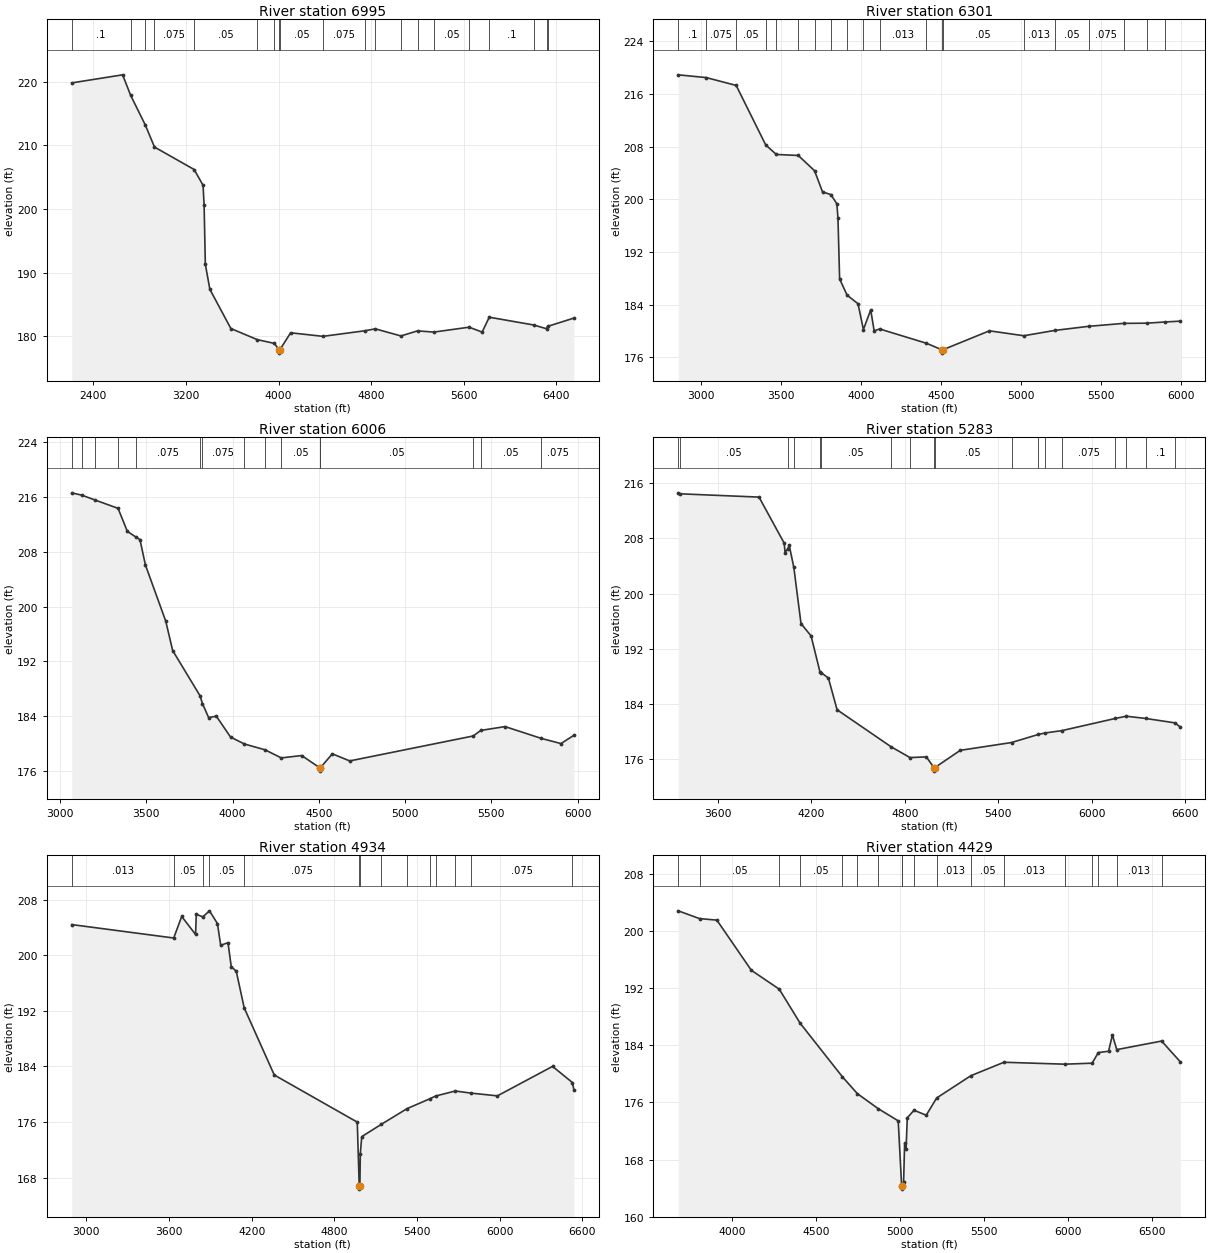
Type RM Length L Ch R = 1,6995,694,694,694
BEGIN DESCRIPTION:
Mapping XS b5cec9ba
END DESCRIPTION:
XS GIS Cut Line= 3
      2518543.41     13583893.87      2516793.71     13584456.76
      2514483.28     13585410.62
#Sta/Elev= 30
  2213.2  219.83  2652.6  221.10  2721.5  217.89  2849.0  213.19  2927.9  209.74
  3270.4  206.21  3347.4  203.73  3356.5  200.66  3367.1  191.31  3406.3  187.36
  3587.7  181.20  3814.9  179.46  3963.2  178.86  4005.6  177.83  4005.9  177.33
  4010.0  177.83  4103.9  180.53  4382.9  179.97  4746.9  180.85  4835.8  181.15
  5057.0  180.03  5200.1  180.83  5341.0  180.64  5646.1  181.41  5758.4  180.64
  5820.1  182.98  6202.3  181.76  6314.6  181.17  6323.4  181.53  6550.8  182.84
#Mann=20,-1,0
  2213.2     0.1       0  2721.5   0.075       0  2849.0    0.05       0
  2927.9   0.075       0  3270.4    0.05       0  3814.9   0.013       0
  3963.2    0.05       0  4005.6    0.05       0  4010.0    0.05       0
  4382.9   0.075       0  4746.9    0.05       0  4835.8   0.075       0
  5057.0    0.05       0  5200.1   0.075       0  5341.0    0.05       0
  5646.1   0.075       0  5820.1     0.1       0  6202.3   0.075       0
  6314.6     0.1       0  6323.4   0.075       0
Bank Sta=4005.6,4010
Exp/Cntr=0.3,0.1

Type RM Length L Ch R = 1,6301,295,295,295
BEGIN DESCRIPTION:
Mapping XS 81ee45d0
END DESCRIPTION:
XS GIS Cut Line= 3
      2518326.40     13583792.14      2516807.28     13584151.57
      2515359.03     13584773.98
#Sta/Elev= 30
  2857.5  218.93  3032.8  218.51  3219.6  217.32  3404.1  208.28  3470.7  206.83
  3607.6  206.68  3709.3  204.36  3759.2  201.14  3811.1  200.74  3848.9  199.33
  3855.7  197.11  3866.0  187.92  3912.8  185.45  3980.8  184.16  4014.6  180.23
  4060.2  183.22  4081.8  180.04  4116.4  180.32  4408.5  178.15  4505.9  177.15
  4506.2  176.65  4510.3  177.15  4802.0  180.04  5016.7  179.29  5210.4  180.10
  5421.2  180.72  5640.7  181.17  5783.8  181.20  5897.7  181.38  5994.9  181.51
#Mann=20,-1,0
  2857.5     0.1       0  3032.8   0.075       0  3219.6    0.05       0
  3404.1   0.075       0  3470.7     0.1       0  3607.6    0.05       0
  3709.3     0.1       0  3811.1   0.075       0  3912.8    0.05       0
  4014.6   0.075       0  4116.4   0.013       0  4408.5    0.05       0
  4505.9    0.05       0  4510.3    0.05       0  5016.7   0.013       0
  5210.4    0.05       0  5421.2   0.075       0  5640.7    0.05       0
  5783.8   0.075       0  5897.7    0.05       0
Bank Sta=4505.9,4510.3
Exp/Cntr=0.3,0.1

Type RM Length L Ch R = 1,6006,723,723,723
BEGIN DESCRIPTION:
Mapping XS 7a850961
END DESCRIPTION:
XS GIS Cut Line= 3
      2517960.20     13583500.51      2516624.16     13583941.33
      2515228.56     13584496.87
#Sta/Elev= 30
  3068.5  216.62  3127.6  216.27  3201.2  215.59  3336.7  214.35  3390.6  210.98
  3441.2  210.14  3463.6  209.79  3495.2  206.07  3612.9  197.87  3653.1  193.57
  3812.0  186.94  3825.5  185.82  3861.6  183.76  3905.9  183.98  3988.6  180.92
  4068.5  179.91  4188.9  179.05  4282.4  177.87  4400.8  178.22  4504.6  176.44
  4504.9  175.94  4509.0  176.44  4578.3  178.47  4679.0  177.43  5394.6  181.08
  5438.3  181.89  5579.0  182.45  5789.5  180.72  5902.7  179.97  5977.5  181.17
#Mann=15,-1,0
  3068.5   0.075       0  3127.6   0.013       0  3201.2    0.05       0
  3336.7   0.013       0  3441.2   0.075       0  3812.0    0.05       0
  3825.5   0.075       0  4068.5    0.05       0  4188.9   0.013       0
  4282.4    0.05       0  4504.6    0.05       0  4509.0    0.05       0
  5394.6   0.075       0  5438.3    0.05       0  5789.5   0.075       0
Bank Sta=4504.6,4509
Exp/Cntr=0.3,0.1

Type RM Length L Ch R = 1,5283,349,349,349
BEGIN DESCRIPTION:
Mapping XS 45dafa98
END DESCRIPTION:
XS GIS Cut Line= 3
      2518055.17     13583134.28      2516481.74     13583629.36
      2515023.63     13584226.17
#Sta/Elev= 30
  3344.3  214.59  3353.1  214.45  3863.3  213.97  4025.2  207.29  4030.4  205.95
  4048.1  206.52  4057.3  206.98  4086.8  203.80  4132.8  195.67  4197.6  193.88
  4255.3  188.61  4263.6  188.55  4308.9  187.78  4364.7  183.19  4710.4  177.85
  4833.0  176.27  4937.9  176.37  4987.1  174.81  4987.4  174.31  4991.8  174.81
  5155.8  177.32  5485.2  178.45  5657.5  179.62  5700.3  179.83  5807.8  180.17
  6152.7  181.94  6222.2  182.26  6348.1  181.93  6536.1  181.29  6569.3  180.68
#Mann=18,-1,0
  3344.3   0.013       0  3353.1    0.05       0  4048.1   0.075       0
  4086.8    0.05       0  4255.3   0.075       0  4263.6    0.05       0
  4710.4   0.013       0  4833.0    0.05       0  4987.1    0.05       0
  4991.8    0.05       0  5485.2   0.013       0  5657.5    0.05       0
  5700.3   0.013       0  5807.8   0.075       0  6152.7    0.05       0
  6222.2   0.075       0  6348.1     0.1       0  6536.1   0.075       0
Bank Sta=4987.1,4991.8
Exp/Cntr=0.3,0.1

Type RM Length L Ch R = 1,4934,505,505,505
BEGIN DESCRIPTION:
Mapping XS cdef66c9
END DESCRIPTION:
XS GIS Cut Line= 3
      2518306.08     13582551.04      2516400.36     13583351.31
      2514942.28     13583954.88
#Sta/Elev= 30
  2893.8  204.41  3633.8  202.48  3692.0  205.58  3792.4  202.99  3797.9  205.90
  3844.9  205.52  3893.6  206.39  3951.3  204.56  3975.0  201.43  4028.0  201.81
  4051.7  198.35  4088.0  197.70  4145.4  192.44  4364.0  182.77  4966.5  175.99
  4980.7  166.85  4981.1  166.35  4985.5  166.85  4988.5  171.43  4999.0  173.90
  5139.9  175.66  5328.7  177.94  5491.4  179.33  5534.8  179.74  5678.5  180.47
  5793.6  180.16  5983.9  179.77  6384.3  184.01  6528.0  181.69  6538.8  180.68
#Mann=14,-1,0
  2893.8   0.013       0  3633.8    0.05       0  3844.9   0.013       0
  3893.6    0.05       0  4145.4   0.075       0  4980.7    0.05       0
  4985.5   0.075       0  5139.9    0.05       0  5328.7   0.075       0
  5491.4    0.05       0  5534.8   0.075       0  5678.5    0.05       0
  5793.6   0.075       0  6528.0     0.1       0
Bank Sta=4980.7,4985.5
Exp/Cntr=0.3,0.1

Type RM Length L Ch R = 1,4429,256,256,256
BEGIN DESCRIPTION:
Mapping XS 6f9932e4
END DESCRIPTION:
XS GIS Cut Line= 3
      2517560.08     13582435.74      2516298.63     13582917.26
      2514808.34     13583608.22
#Sta/Elev= 30
  3678.3  202.86  3805.2  201.77  3908.5  201.56  4114.0  194.53  4280.5  191.88
  4405.3  187.10  4656.6  179.61  4745.8  177.25  4869.4  175.15  4989.6  173.43
  5009.9  164.36  5010.2  163.86  5014.7  164.36  5021.7  164.83  5027.8  170.26
  5036.5  169.47  5043.6  173.86  5084.0  174.91  5156.6  174.22  5219.1  176.64
  5422.4  179.75  5619.8  181.64  5981.6  181.37  6145.5  181.51  6182.6  183.00
  6243.5  183.18  6266.4  185.47  6292.4  183.41  6559.8  184.61  6671.2  181.70
#Mann=18,-1,0
  3678.3   0.075       0  3805.2    0.05       0  4280.5   0.013       0
  4405.3    0.05       0  4656.6   0.013       0  4745.8    0.05       0
  4869.4   0.013       0  5009.9    0.03       0  5014.7   0.013       0
  5084.0    0.05       0  5219.1   0.013       0  5422.4    0.05       0
  5619.8   0.013       0  5981.6    0.05       0  6145.5   0.075       0
  6182.6    0.05       0  6292.4   0.013       0  6559.8   0.075       0
Bank Sta=5009.9,5014.7
Exp/Cntr=0.3,0.1

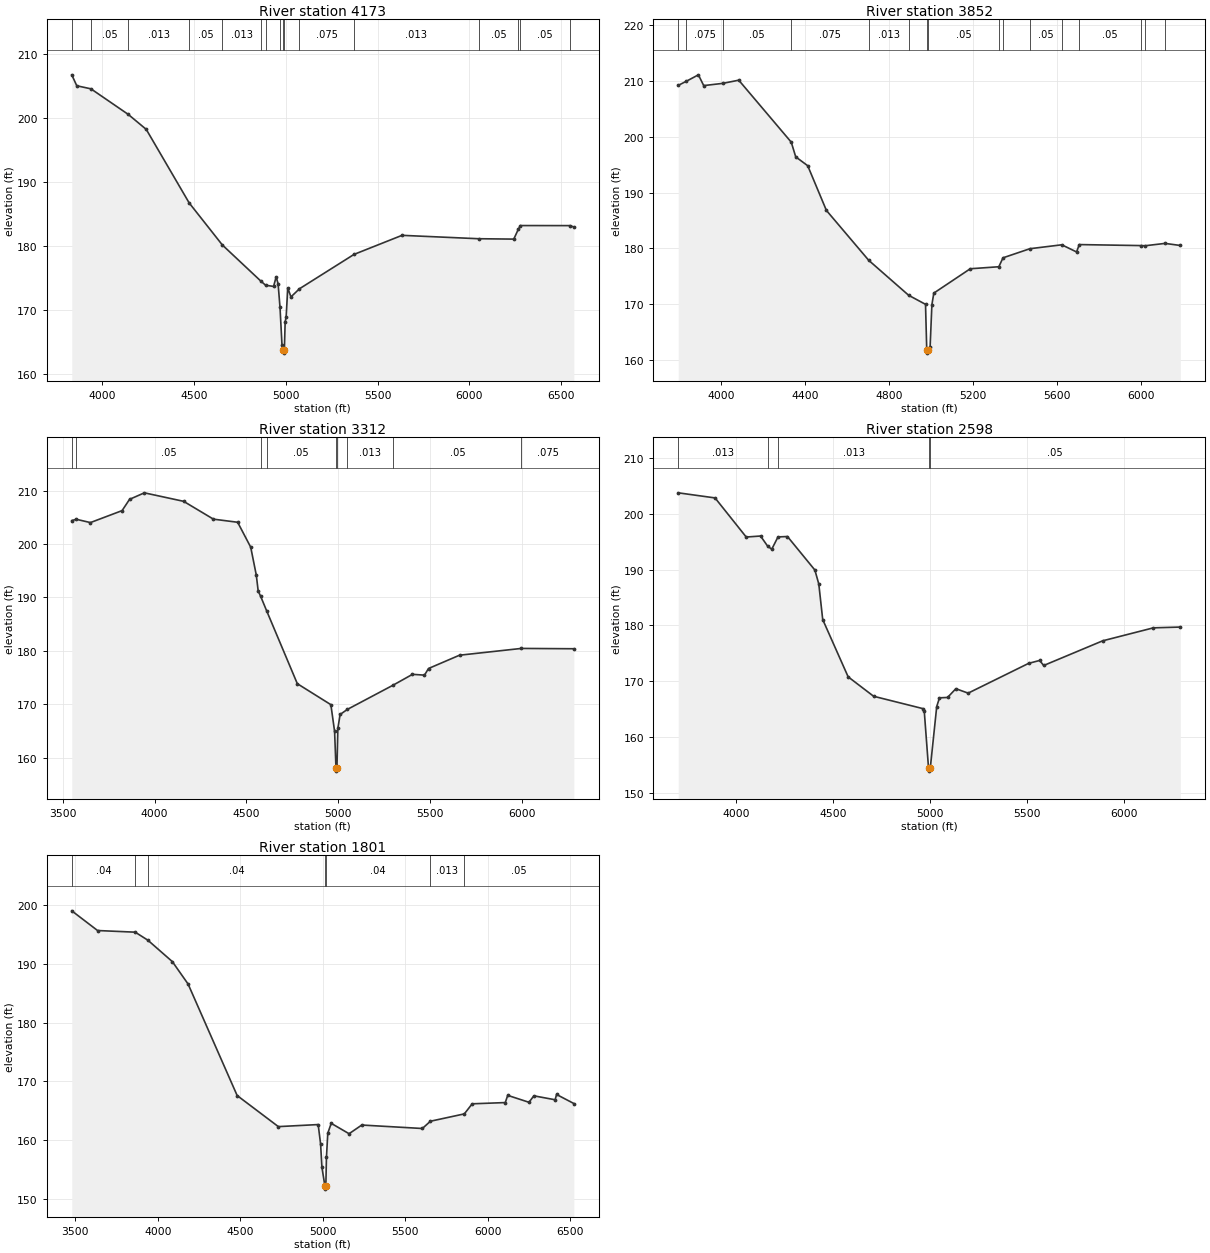
Type RM Length L Ch R = 1,4173,321,321,321
BEGIN DESCRIPTION:
Mapping XS 346f2829
END DESCRIPTION:
XS GIS Cut Line= 3
      2517431.23     13582279.76      2516278.29     13582666.33
      2514894.80     13583297.04
#Sta/Elev= 30
  3833.0  206.77  3860.3  205.06  3937.5  204.58  4140.4  200.59  4238.9  198.24
  4472.6  186.75  4653.8  180.16  4863.3  174.52  4889.4  173.87  4933.0  173.68
  4947.0  175.18  4957.6  174.09  4968.0  170.39  4978.7  164.58  4986.7  163.75
  4987.1  163.25  4991.7  163.75  4996.1  168.18  5001.3  168.84  5010.3  173.45
  5027.6  172.04  5073.8  173.31  5371.5  178.69  5633.0  181.67  6050.1  181.14
  6242.1  181.08  6266.4  182.59  6278.4  183.20  6549.0  183.19  6569.5  182.97
#Mann=16,-1,0
  3833.0   0.075       0  3937.5    0.05       0  4140.4   0.013       0
  4472.6    0.05       0  4653.8   0.013       0  4863.3    0.05       0
  4889.4   0.013       0  4968.0    0.05       0  4986.7    0.05       0
  4991.7    0.05       0  5073.8   0.075       0  5371.5   0.013       0
  6050.1    0.05       0  6266.4   0.075       0  6278.4    0.05       0
  6549.0   0.013       0
Bank Sta=4986.7,4991.7
Exp/Cntr=0.3,0.1

Type RM Length L Ch R = 1,3852,540,540,540
BEGIN DESCRIPTION:
Mapping XS cb838b5f
END DESCRIPTION:
XS GIS Cut Line= 3
      2517431.23     13582022.05      2516305.41     13582361.15
      2515193.20     13582856.22
#Sta/Elev= 30
  3794.9  209.19  3834.2  209.94  3891.0  211.08  3916.3  209.15  4006.8  209.55
  4083.4  210.12  4333.6  199.02  4354.9  196.39  4412.1  194.80  4501.1  186.80
  4702.9  177.86  4893.2  171.60  4973.6  169.98  4979.5  161.74  4979.9  161.24
  4984.6  161.74  4995.5  162.34  5004.0  169.93  5013.2  171.99  5186.9  176.35
  5323.1  176.71  5343.0  178.31  5471.3  179.94  5623.1  180.64  5693.6  179.36
  5706.5  180.68  5999.4  180.50  6020.2  180.47  6115.4  180.89  6188.1  180.52
#Mann=16,-1,0
  3794.9    0.05       0  3834.2   0.075       0  4006.8    0.05       0
  4333.6   0.075       0  4702.9   0.013       0  4893.2    0.05       0
  4979.5    0.05       0  4984.6    0.05       0  5323.1   0.075       0
  5343.0   0.013       0  5471.3    0.05       0  5623.1   0.075       0
  5706.5    0.05       0  5999.4   0.075       0  6020.2    0.05       0
  6115.4   0.075       0
Bank Sta=4979.5,4984.6
Exp/Cntr=0.3,0.1

Type RM Length L Ch R = 1,3312,714,714,714
BEGIN DESCRIPTION:
Mapping XS a82a6b4b
END DESCRIPTION:
XS GIS Cut Line= 3
      2517654.98     13581601.58      2516210.47     13581852.50
      2515099.16     13582462.37
#Sta/Elev= 30
  3548.8  204.37  3573.2  204.62  3650.3  204.00  3822.8  206.24  3863.4  208.35
  3944.1  209.57  4157.8  207.98  4320.2  204.64  4452.1  204.06  4523.2  199.39
  4553.6  194.16  4563.8  191.20  4577.6  190.17  4609.2  187.54  4776.9  173.84
  4959.6  169.91  4979.9  164.91  4987.5  157.97  4987.9  157.47  4992.6  157.97
  4997.7  165.49  5010.1  168.08  5049.2  169.02  5299.9  173.59  5404.0  175.59
  5469.4  175.44  5491.2  176.68  5660.0  179.17  5996.8  180.44  6282.6  180.38
#Mann=9,-1,0
  3548.8   0.013       0  3573.2    0.05       0  4577.6   0.013       0
  4609.2    0.05       0  4987.5    0.05       0  4992.6    0.05       0
  5049.2   0.013       0  5299.9    0.05       0  5996.8   0.075       0
Bank Sta=4987.5,4992.6
Exp/Cntr=0.3,0.1

Type RM Length L Ch R = 1,2598,797,797,797
BEGIN DESCRIPTION:
Mapping XS d886657d
END DESCRIPTION:
XS GIS Cut Line= 3
      2517343.00     13580957.30      2516122.30     13581140.40
      2515099.10     13582034.86
#Sta/Elev= 30
  3700.0  203.71  3890.1  202.80  4051.1  195.81  4125.2  195.99  4163.0  194.12
  4183.3  193.65  4215.3  195.83  4264.2  195.90  4405.8  189.91  4426.0  187.42
  4446.3  181.06  4577.7  170.82  4709.2  167.35  4964.1  165.14  4970.7  164.76
  4992.5  154.68  4996.6  154.47  4997.0  153.97  5001.8  154.47  5035.2  165.52
  5049.5  167.07  5091.2  167.14  5134.0  168.70  5197.6  167.91  5509.8  173.23
  5566.8  173.75  5587.7  172.85  5892.4  177.26  6154.3  179.58  6293.4  179.72
#Mann=5,-1,0
  3700.0   0.013       0  4163.0    0.05       0  4215.3   0.013       0
  4996.6    0.03       0  5001.8    0.05       0
Bank Sta=4996.6,5001.8
Exp/Cntr=0.3,0.1

Type RM Length L Ch R = 1,1801,0,0,0
BEGIN DESCRIPTION:
Mapping XS 4ec33286
END DESCRIPTION:
XS GIS Cut Line= 4
      2517180.24     13580048.52      2516190.12     13580163.81
      2515430.55     13580740.27      2514814.17     13581641.13
#Sta/Elev= 30
  3478.6  199.07  3634.9  195.71  3862.9  195.43  3939.7  194.06  4087.9  190.41
  4183.3  186.59  4480.6  167.57  4730.2  162.27  4971.5  162.62  4986.1  159.32
  4994.3  155.30  5012.5  152.11  5012.9  151.61  5017.9  152.11  5021.6  157.01
  5029.7  161.14  5050.5  162.83  5158.7  161.06  5235.7  162.54  5602.6  161.95
  5651.7  163.19  5856.9  164.44  5904.6  166.16  6105.0  166.37  6119.9  167.60
  6248.6  166.42  6278.4  167.52  6407.0  166.85  6415.9  167.75  6520.5  166.21
#Mann=7,-1,0
  3478.6    0.04       0  3862.9   0.013       0  3939.7    0.04       0
  5012.5    0.04       0  5017.9    0.04       0  5651.7   0.013       0
  5856.9    0.05       0
Bank Sta=5012.5,5017.9
Exp/Cntr=0.3,0.1

Chan Stop Cuts=-1