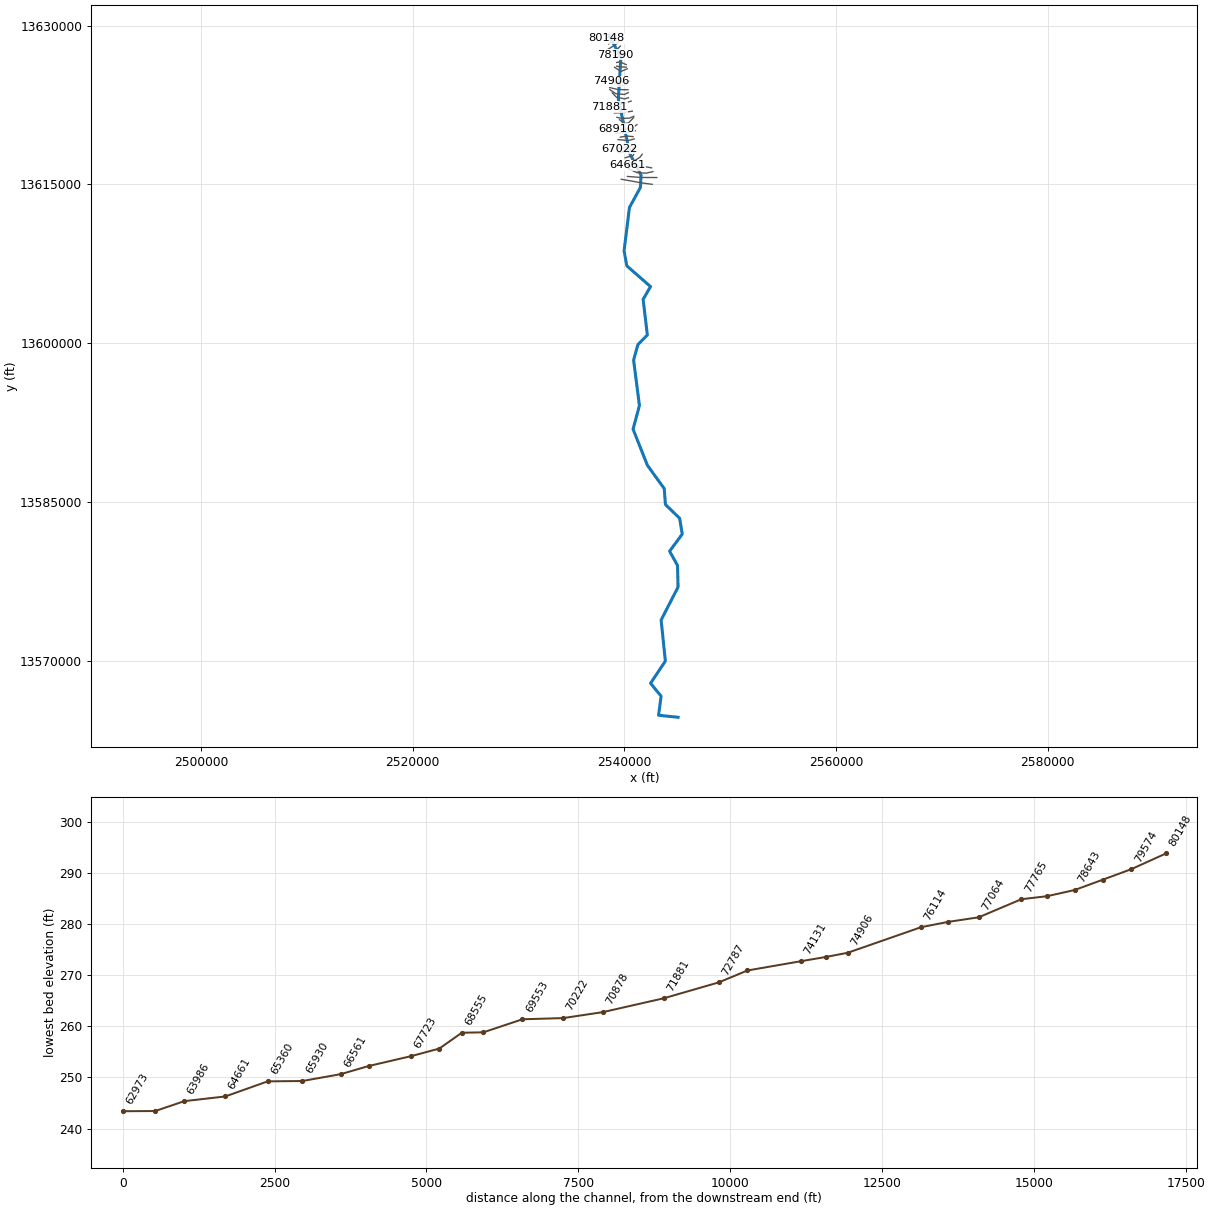
--- IRISH CREEK.prj (project) ---

Proj Title=IRISH CREEK Base Level Engineering
Current Plan=p01
Default Exp/Contr=0.3,0.1
English Units
Geom File=g01
Flow File=f01
Plan File=p01
Y Axis Title=Elevation
X Axis Title(PF)=Main Channel Distance
X Axis Title(XS)=Station
BEGIN DESCRIPTION:
IRISH CREEK
END DESCRIPTION:
DSS Export Rating Curves= 0
DSS Export Rating Curve Sorted= 0
DSS Export Volume Flow Curves= 0
DXF OffsetX= 0
DXF OffsetY= 0
DXF ScaleX= 1
DXF ScaleY= 10

--- IRISH CREEK.p01 (plan) ---

Plan Title=Multiple Run
Short Identifier=Multiple
Geom File=g01
Flow File=f01
Subcritical Flow
K Sum by GR= 0
Std Step Tol= 0.01
Critical Tol= 0.01
Num of Std Step Trials= 20
Max Error Tol= 0.3
Flow Tol Ratio= 0.001
Split Flow NTrial= 30
Split Flow Tol= 0.02
Split Flow Ratio= 0.02
Log Output Level= 0
Friction Slope Method= 1
Unsteady Friction Slope Method= 2
Unsteady Bridges Friction Slope Method= 1
Parabolic Critical Depth
Global Vel Dist=  1 , 1 , 1
Global Log Level= 0
CheckData=True
Encroach Param= -1, 0, 0, 0
BEGIN DESCRIPTION:
Multiple Run
END DESCRIPTION:

--- IRISH CREEK.f01 (steady flow) ---

Flow Title=Multiple
Number of Profiles=7
Profile Names=10-year,25-year,50-year,1pct_min,100-year,1pct_plu,500-year
River Rch & RM= IRISH CREEK,Reach-1,80148
     494     774    1020     652    1300    2595    2090
River Rch & RM= IRISH CREEK,Reach-1,77765
     711    1136    1516     980    1956    3902    3218
River Rch & RM= IRISH CREEK,Reach-1,74906
    1003    1630    2201    1437    2867    5720    4813
River Rch & RM= IRISH CREEK,Reach-1,71881
    1484    2459    3363    2222    4433    8844    7623
River Rch & RM= IRISH CREEK,Reach-1,68910
    1608    2670    3656    2417    4822    9621    8306
River Rch & RM= IRISH CREEK,Reach-1,65360
    1681    2796    3835    2538    5064   10104    8745
River Rch & RM= IRISH CREEK,Reach-1,64661
    1857    3099    4259    2823    5633   11239    9760
River Rch & RM= IRISH CREEK,Reach-1,59579
    1982    3326    4586    3050    6085   12141   10614
River Rch & RM= IRISH CREEK,Reach-1,57962
    2772    4716    6565    4402    8784   17525   15581
River Rch & RM= IRISH CREEK,Reach-1,52982
    3157    5390    7521    5053   10082   20116   17953
River Rch & RM= IRISH CREEK,Reach-1,50369
    3425    5866    8202    5521   11016   21981   19691
River Rch & RM= IRISH CREEK,Reach-1,47773
    4059    6983    9792    6608   13185   26308   23685
River Rch & RM= IRISH CREEK,Reach-1,43562
    4172    7184   10080    6805   13578   27092   24412
River Rch & RM= IRISH CREEK,Reach-1,42746
    4285    7382   10363    6999   13965   27865   25127
River Rch & RM= IRISH CREEK,Reach-1,40546
    4375    7560   10632    7192   14350   28633   25912
River Rch & RM= IRISH CREEK,Reach-1,37137
    4595    7955   11202    7587   15138   30205   27402
River Rch & RM= IRISH CREEK,Reach-1,33848
    4677    8098   11404    7724   15411   30750   27894
River Rch & RM= IRISH CREEK,Reach-1,32658
    4735    8200   11548    7822   15606   31138   28249
River Rch & RM= IRISH CREEK,Reach-1,30074
    5770   10025   14154    9609   19172   38253   34842
River Rch & RM= IRISH CREEK,Reach-1,27099
    5936   10316   14567    9889   19732   39370   35860
River Rch & RM= IRISH CREEK,Reach-1,23135
    6620   11537   16325   11103   22154   44204   40407
River Rch & RM= IRISH CREEK,Reach-1,20519
    7378   12933   18370   12539   25018   49917   45968
River Rch & RM= IRISH CREEK,Reach-1,17929
    7706   13481   19126   13039   26016   51909   47666
River Rch & RM= IRISH CREEK,Reach-1,12150
    7474   13097   18599   12691   25323   50525   46501
River Rch & RM= IRISH CREEK,Reach-1,10761
    8142   14302   20344   13903   27740   55350   51091
River Rch & RM= IRISH CREEK,Reach-1,7090
    8145   14302   20340   13897   27728   55326   51044
Boundary for River Rch & Prof#=IRISH CREEK,Reach-1,1
Up Type=0
Dn Type=3
Dn Slope=0.002
Boundary for River Rch & Prof#=IRISH CREEK,Reach-1,2
Up Type=0
Dn Type=3
Dn Slope=0.002
Boundary for River Rch & Prof#=IRISH CREEK,Reach-1,3
Up Type=0
Dn Type=3
Dn Slope=0.002
Boundary for River Rch & Prof#=IRISH CREEK,Reach-1,4
Up Type=0
Dn Type=3
Dn Slope=0.002
Boundary for River Rch & Prof#=IRISH CREEK,Reach-1,5
Up Type=0
Dn Type=3
Dn Slope=0.002
Boundary for River Rch & Prof#=IRISH CREEK,Reach-1,6
Up Type=0
Dn Type=3
Dn Slope=0.002
Boundary for River Rch & Prof#=IRISH CREEK,Reach-1,7
Up Type=0
Dn Type=3
Dn Slope=0.002

--- IRISH CREEK.g01 (geometry) ---

Geom Title=Existing Conditions

River Reach=IRISH CREEK,Reach-1
Reach XY= 30
      2538525.00     13629125.00      2539672.77     13627019.07
      2539432.73     13623071.35      2540532.59     13617871.67
      2541575.04     13615905.02      2541521.46     13614726.46
      2540483.05     13612828.29      2539976.20     13608735.50
      2540232.81     13607318.81      2542474.94     13605354.98
      2541774.79     13604154.95      2542173.79     13600784.59
      2541280.83     13599877.30      2540875.35     13598411.22
      2541425.84     13594119.98      2540825.37     13591890.55
      2542180.46     13588472.55      2543771.39     13586273.50
      2543880.47     13584772.55      2545221.25     13583473.45
      2545467.44     13581975.00      2544275.45     13580359.82
      2545022.74     13579019.06      2545075.00     13576975.00
      2543476.05     13573864.57      2543873.80     13569985.50
      2542475.51     13567890.21      2543472.76     13566669.07
      2543235.43     13564865.21      2545075.00     13564675.00

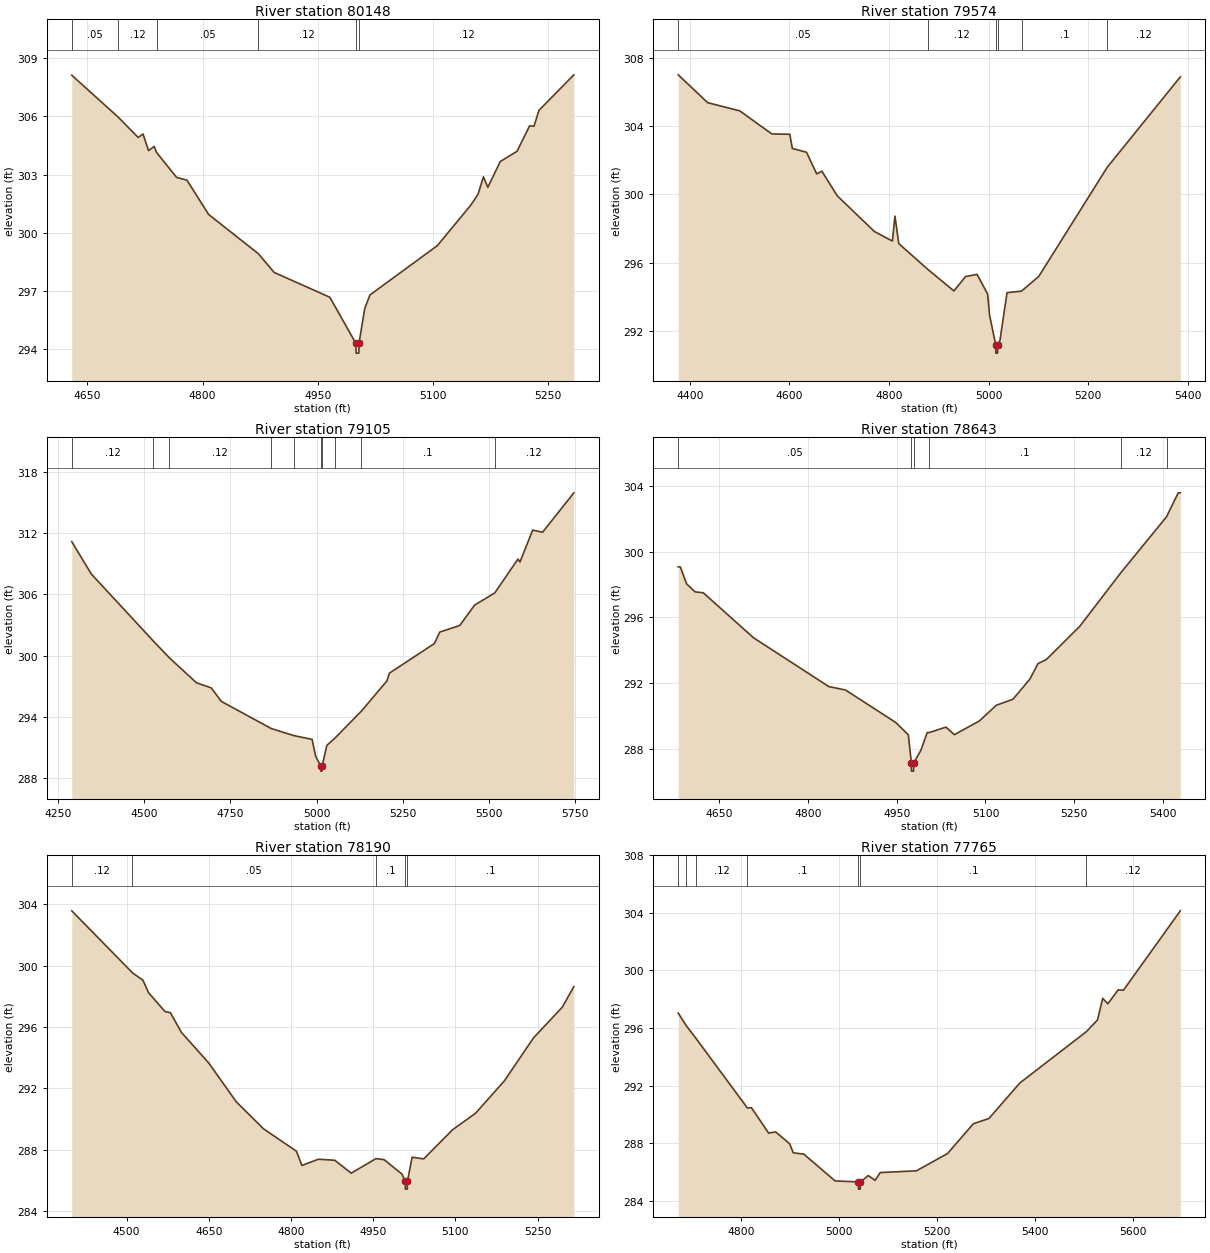
Type RM Length L Ch R = 1,80148,574,574,574
BEGIN DESCRIPTION:
IRISH CREEK 152.0
END DESCRIPTION:
XS GIS Cut Line= 3
      2538875.04     13629175.03      2538617.58     13628981.96
      2538325.03     13628825.01
#Sta/Elev= 30
  4629.7  308.12  4690.4  305.95  4716.2  304.91  4722.5  305.09  4729.7  304.23
  4737.0  304.45  4740.1  304.14  4766.2  302.85  4779.7  302.71  4807.9  300.94
  4872.6  298.92  4893.3  297.95  4965.8  296.67  4999.7  294.29  5000.0  293.79
  5003.5  293.79  5003.7  294.29  5011.2  296.09  5018.0  296.79  5105.7  299.33
  5149.5  301.43  5158.7  301.98  5165.8  302.88  5171.5  302.34  5187.7  303.67
  5209.6  304.20  5225.9  305.51  5231.6  305.49  5238.1  306.31  5283.5  308.14
#Mann=6,-1,0
  4629.7    0.05       0  4690.4    0.12       0  4740.1    0.05       0
  4872.6    0.12       0  4999.7    0.05       0  5003.7    0.12       0
Bank Sta=4999.7,5003.7
Exp/Cntr=0.3,0.1

Type RM Length L Ch R = 1,79574,469,469,469
BEGIN DESCRIPTION:
IRISH CREEK 151.0
END DESCRIPTION:
XS GIS Cut Line= 3
      2538974.99     13629124.97      2538825.00     13628525.00
      2538525.04     13628275.03
#Sta/Elev= 30
  4376.5  306.99  4435.7  305.36  4500.2  304.88  4564.6  303.53  4600.7  303.51
  4605.8  302.68  4634.2  302.46  4654.8  301.19  4665.1  301.35  4696.0  299.91
  4770.7  297.82  4806.8  297.26  4812.0  298.72  4819.7  297.11  4878.9  295.58
  4930.5  294.34  4953.7  295.18  4976.9  295.31  4998.2  294.16  5002.1  292.92
  5014.4  291.20  5014.7  290.70  5018.2  290.70  5018.4  291.20  5022.9  291.43
  5037.2  294.24  5066.4  294.33  5101.0  295.19  5238.6  301.58  5385.4  306.87
#Mann=6,-1,0
  4376.5    0.05       0  4878.9    0.12       0  5014.4    0.05       0
  5018.4    0.12       0  5066.4     0.1       0  5238.6    0.12       0
Bank Sta=5014.4,5018.4
Exp/Cntr=0.3,0.1

Type RM Length L Ch R = 1,79105,462,462,462
BEGIN DESCRIPTION:
IRISH CREEK 150.0
END DESCRIPTION:
XS GIS Cut Line= 3
      2539675.00     13628625.00      2539125.00     13628175.00
      2538487.38     13627788.39
#Sta/Elev= 30
  4289.6  311.18  4346.3  308.00  4526.3  301.42  4572.5  299.78  4651.4  297.32
  4694.4  296.82  4723.2  295.50  4868.3  292.83  4934.5  292.13  4986.6  291.77
  4997.0  290.12  5011.8  289.15  5012.1  288.65  5015.6  288.65  5015.8  289.15
  5029.3  291.17  5053.5  291.91  5129.9  294.55  5203.8  297.51  5210.7  298.26
  5341.5  301.18  5357.0  302.30  5415.1  302.95  5457.8  304.94  5516.7  306.15
  5583.8  309.47  5589.7  309.18  5626.5  312.31  5655.1  312.10  5745.9  315.97
#Mann=10,-1,0
  4289.6    0.12       0  4526.3    0.05       0  4572.5    0.12       0
  4868.3    0.05       0  4934.5    0.12       0  5011.8    0.05       0
  5015.8    0.12       0  5053.5    0.05       0  5129.9     0.1       0
  5516.7    0.12       0
Bank Sta=5011.8,5015.8
Exp/Cntr=0.3,0.1

Type RM Length L Ch R = 1,78643,453,453,453
BEGIN DESCRIPTION:
IRISH CREEK 149.0
END DESCRIPTION:
XS GIS Cut Line= 3
      2539624.99     13628074.99      2539325.00     13627775.00
      2539025.01     13627475.01
#Sta/Elev= 30
  4580.8  299.07  4584.3  299.07  4594.9  298.04  4609.1  297.55  4623.2  297.49
  4708.1  294.75  4835.3  291.78  4863.6  291.57  4948.5  289.59  4969.7  288.84
  4974.8  287.13  4975.0  286.63  4978.5  286.63  4978.8  287.13  4990.9  287.90
  5001.5  288.98  5005.0  288.98  5033.3  289.31  5047.5  288.85  5089.9  289.69
  5118.2  290.64  5146.5  291.01  5174.8  292.22  5188.9  293.18  5203.0  293.43
  5259.6  295.46  5328.5  298.70  5406.0  302.12  5425.8  303.58  5429.3  303.58
#Mann=6,-1,0
  4580.8    0.05       0  4974.8    0.05       0  4978.8    0.05       0
  5005.0     0.1       0  5328.5    0.12       0  5406.0     0.1       0
Bank Sta=4974.8,4978.8
Exp/Cntr=0.3,0.1

Type RM Length L Ch R = 1,78190,425,425,425
BEGIN DESCRIPTION:
IRISH CREEK 148.0
END DESCRIPTION:
XS GIS Cut Line= 3
      2540075.00     13627375.00      2539475.00     13627375.00
      2539175.03     13627275.01
#Sta/Elev= 30
  4400.0  303.57  4510.8  299.53  4530.0  299.04  4540.0  298.24  4570.0  297.01
  4580.0  296.93  4600.0  295.65  4650.0  293.65  4700.0  291.13  4750.0  289.36
  4810.0  287.90  4820.0  286.97  4850.0  287.38  4880.0  287.31  4910.0  286.47
  4955.1  287.42  4970.0  287.35  5002.6  286.41  5008.5  285.93  5008.8  285.43
  5012.3  285.43  5012.5  285.93  5021.1  287.51  5042.2  287.40  5094.9  289.30
  5137.0  290.38  5189.7  292.50  5242.4  295.28  5295.1  297.29  5316.2  298.63
#Mann=5,-1,0
  4400.0    0.12       0  4510.8    0.05       0  4955.1     0.1       0
  5008.5    0.05       0  5012.5     0.1       0
Bank Sta=5008.5,5012.5
Exp/Cntr=0.3,0.1

Type RM Length L Ch R = 1,77765,701,701,701
BEGIN DESCRIPTION:
IRISH CREEK 147.0
END DESCRIPTION:
XS GIS Cut Line= 3
      2539925.03     13627225.02      2539625.00     13626975.00
      2539025.00     13627175.00
#Sta/Elev= 30
  4672.7  297.05  4688.8  296.18  4708.0  295.33  4813.6  290.46  4821.8  290.48
  4856.9  288.72  4871.2  288.80  4899.9  287.97  4907.0  287.35  4928.5  287.26
  4992.3  285.40  5039.8  285.33  5040.0  284.83  5043.5  284.83  5043.8  285.33
  5060.0  285.77  5073.8  285.44  5084.3  285.98  5158.1  286.10  5221.4  287.30
  5274.1  289.37  5305.7  289.73  5368.9  292.20  5504.1  295.75  5527.0  296.57
  5537.6  298.07  5548.1  297.69  5569.2  298.66  5579.8  298.63  5695.7  304.14
#Mann=7,-1,0
  4672.7    0.12       0  4688.8    0.05       0  4708.0    0.12       0
  4813.6     0.1       0  5039.8    0.05       0  5043.8     0.1       0
  5504.1    0.12       0
Bank Sta=5039.8,5043.8
Exp/Cntr=0.3,0.1

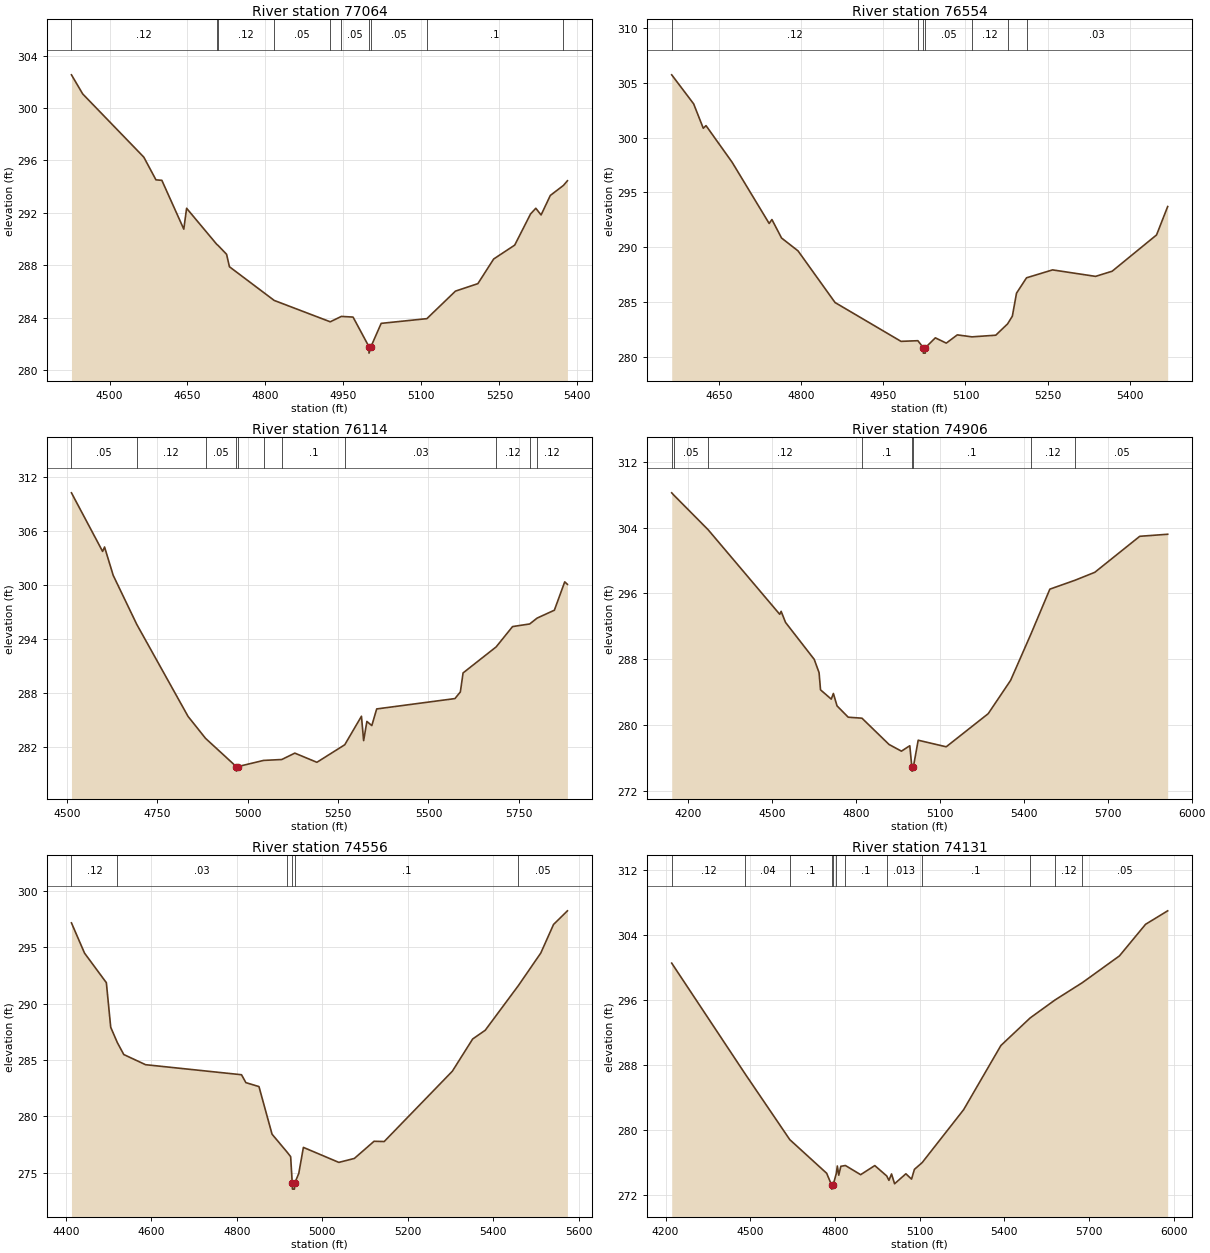
Type RM Length L Ch R = 1,77064,510,510,510
BEGIN DESCRIPTION:
IRISH CREEK 146.0
END DESCRIPTION:
XS GIS Cut Line= 3
      2540174.99     13626325.00      2539575.00     13626575.00
      2539275.03     13626525.00
#Sta/Elev= 30
  4426.8  302.53  4448.5  301.07  4566.0  296.25  4589.3  294.52  4600.7  294.48
  4642.9  290.76  4648.3  292.35  4706.5  289.59  4709.0  289.51  4725.2  288.84
  4730.7  287.89  4816.8  285.32  4924.6  283.69  4946.0  284.10  4968.5  284.05
  4999.0  281.80  4999.2  281.30  5003.0  281.80  5022.6  283.57  5110.5  283.93
  5165.5  286.03  5208.6  286.60  5239.0  288.48  5279.5  289.54  5310.0  291.92
  5320.1  292.35  5330.2  291.84  5348.0  293.33  5373.1  294.09  5380.9  294.45
#Mann=10,-1,0
  4426.8    0.12       0  4706.5     0.1       0  4709.0    0.12       0
  4816.8    0.05       0  4924.6    0.12       0  4946.0    0.05       0
  4999.0    0.05       0  5003.0    0.05       0  5110.5     0.1       0
  5373.1    0.12       0
Bank Sta=4999,5003
Exp/Cntr=0.3,0.1

Type RM Length L Ch R = 1,76554,440,440,440
BEGIN DESCRIPTION:
IRISH CREEK 145.0
END DESCRIPTION:
XS GIS Cut Line= 3
      2540175.01     13626075.00      2539575.00     13626125.00
      2539275.02     13626175.00
#Sta/Elev= 30
  4563.2  305.70  4603.3  303.06  4620.9  300.84  4625.9  301.08  4673.6  297.75
  4741.3  292.18  4746.3  292.54  4763.9  290.86  4794.0  289.69  4861.7  284.99
  4982.2  281.46  5013.0  281.52  5022.8  280.89  5023.0  280.39  5026.5  280.39
  5026.8  280.89  5044.9  281.78  5064.9  281.30  5085.0  282.05  5111.9  281.87
  5155.3  282.02  5176.9  283.05  5185.6  283.75  5193.2  285.84  5211.5  287.24
  5259.1  287.96  5337.6  287.37  5368.0  287.84  5449.1  291.14  5469.4  293.72
#Mann=7,-1,0
  4563.2    0.12       0  5013.0    0.05       0  5022.8    0.05       0
  5026.8    0.05       0  5111.9    0.12       0  5176.9    0.05       0
  5211.5    0.03       0
Bank Sta=5022.8,5026.8
Exp/Cntr=0.3,0.1

Type RM Length L Ch R = 1,76114,1208,1208,1208
BEGIN DESCRIPTION:
IRISH CREEK 144.0
END DESCRIPTION:
XS GIS Cut Line= 3
      2540274.98     13625924.99      2539675.00     13625675.00
      2539074.99     13626075.01
#Sta/Elev= 30
  4513.0  310.28  4599.1  303.77  4604.5  304.26  4628.4  301.11  4693.6  295.66
  4835.3  285.44  4883.7  283.00  4968.7  279.86  4968.9  279.36  4972.7  279.86
  5044.1  280.55  5094.4  280.65  5130.5  281.36  5191.5  280.34  5268.5  282.29
  5314.7  285.46  5320.7  282.75  5329.7  284.88  5343.3  284.42  5356.8  286.27
  5573.1  287.42  5588.1  288.16  5595.6  290.27  5687.0  293.16  5732.4  295.42
  5779.8  295.71  5800.2  296.36  5848.0  297.24  5876.6  300.39  5884.1  300.11
#Mann=11,-1,0
  4513.0    0.05       0  4693.6    0.12       0  4883.7    0.05       0
  4968.7    0.05       0  4972.7    0.05       0  5044.1    0.12       0
  5094.4     0.1       0  5268.5    0.03       0  5687.0    0.12       0
  5779.8    0.03       0  5800.2    0.12       0
Bank Sta=4968.7,4972.7
Exp/Cntr=0.3,0.1

Type RM Length L Ch R = 1,74906,350,350,350
BEGIN DESCRIPTION:
Mapping XS 6ec81bc2
END DESCRIPTION:
XS GIS Cut Line= 4
      2540482.53     13624774.81      2539919.99     13624649.80
      2539232.49     13624684.52      2538725.55     13624733.13
#Sta/Elev= 30
  4140.3  308.22  4147.3  307.96  4270.6  303.73  4526.6  293.44  4531.7  293.80
  4547.5  292.45  4650.0  287.96  4667.4  286.34  4672.6  284.25  4711.0  283.12
  4718.6  283.81  4731.6  282.30  4771.6  280.92  4820.8  280.80  4917.8  277.60
  4961.9  276.79  4991.9  277.45  4999.2  274.86  4999.7  274.36  5004.6  274.86
  5021.9  278.12  5122.1  277.32  5272.3  281.35  5352.4  285.40  5425.4  291.06
  5492.8  296.50  5583.3  297.59  5653.6  298.55  5814.3  302.93  5914.2  303.18
#Mann=8,-1,0
  4140.3    0.04       0  4147.3    0.05       0  4270.6    0.12       0
  4820.8     0.1       0  4999.2    0.05       0  5004.6     0.1       0
  5425.4    0.12       0  5583.3    0.05       0
Bank Sta=4999.2,5004.6
Exp/Cntr=0.3,0.1

Type RM Length L Ch R = 1,74556,425,425,425
BEGIN DESCRIPTION:
IRISH CREEK 141.0
END DESCRIPTION:
XS GIS Cut Line= 3
      2540174.98     13624425.00      2539675.00     13624325.00
      2539074.99     13624575.01
#Sta/Elev= 30
  4413.2  297.16  4443.8  294.48  4494.8  291.86  4505.0  287.91  4520.5  286.55
  4535.6  285.49  4586.5  284.59  4810.9  283.70  4821.1  283.00  4851.7  282.65
  4882.3  278.43  4916.6  276.88  4925.8  276.44  4929.6  274.06  4930.0  273.56
  4934.6  273.56  4935.0  274.06  4944.8  274.95  4955.6  277.26  5038.5  275.93
  5074.8  276.28  5120.8  277.80  5144.6  277.78  5303.9  284.01  5351.5  286.87
  5380.8  287.64  5458.5  291.61  5510.8  294.49  5540.6  297.02  5573.1  298.23
#Mann=6,-1,0
  4413.2    0.12       0  4520.5    0.03       0  4916.6     0.1       0
  4929.6    0.05       0  4935.0     0.1       0  5458.5    0.05       0
Bank Sta=4929.6,4935
Exp/Cntr=0.3,0.1

Type RM Length L Ch R = 1,74131,875,875,875
BEGIN DESCRIPTION:
Mapping XS 60145e79
END DESCRIPTION:
XS GIS Cut Line= 4
      2540343.61     13623955.35      2539942.45     13623950.30
      2539352.83     13623980.79      2538608.78     13624156.44
#Sta/Elev= 30
  4221.9  300.53  4483.1  286.83  4640.1  278.79  4770.7  274.65  4788.0  273.20
  4788.5  272.70  4793.5  273.20  4804.8  274.64  4808.4  275.55  4813.4  274.42
  4820.8  275.51  4836.9  275.61  4890.9  274.48  4941.0  275.60  4983.3  274.32
  4991.0  273.78  5000.3  274.57  5011.1  273.36  5051.1  274.59  5071.1  273.93
  5081.2  275.13  5108.8  275.97  5255.5  282.48  5387.6  290.39  5491.1  293.78
  5579.0  295.99  5676.1  298.13  5807.2  301.42  5899.7  305.31  5978.0  306.97
#Mann=12,-1,0
  4221.9    0.12       0  4483.1    0.04       0  4640.1     0.1       0
  4788.0    0.03       0  4793.5     0.1       0  4804.8   0.013       0
  4836.9     0.1       0  4983.3   0.013       0  5108.8     0.1       0
  5491.1    0.05       0  5579.0    0.12       0  5676.1    0.05       0
Bank Sta=4788,4793.5
Exp/Cntr=0.3,0.1

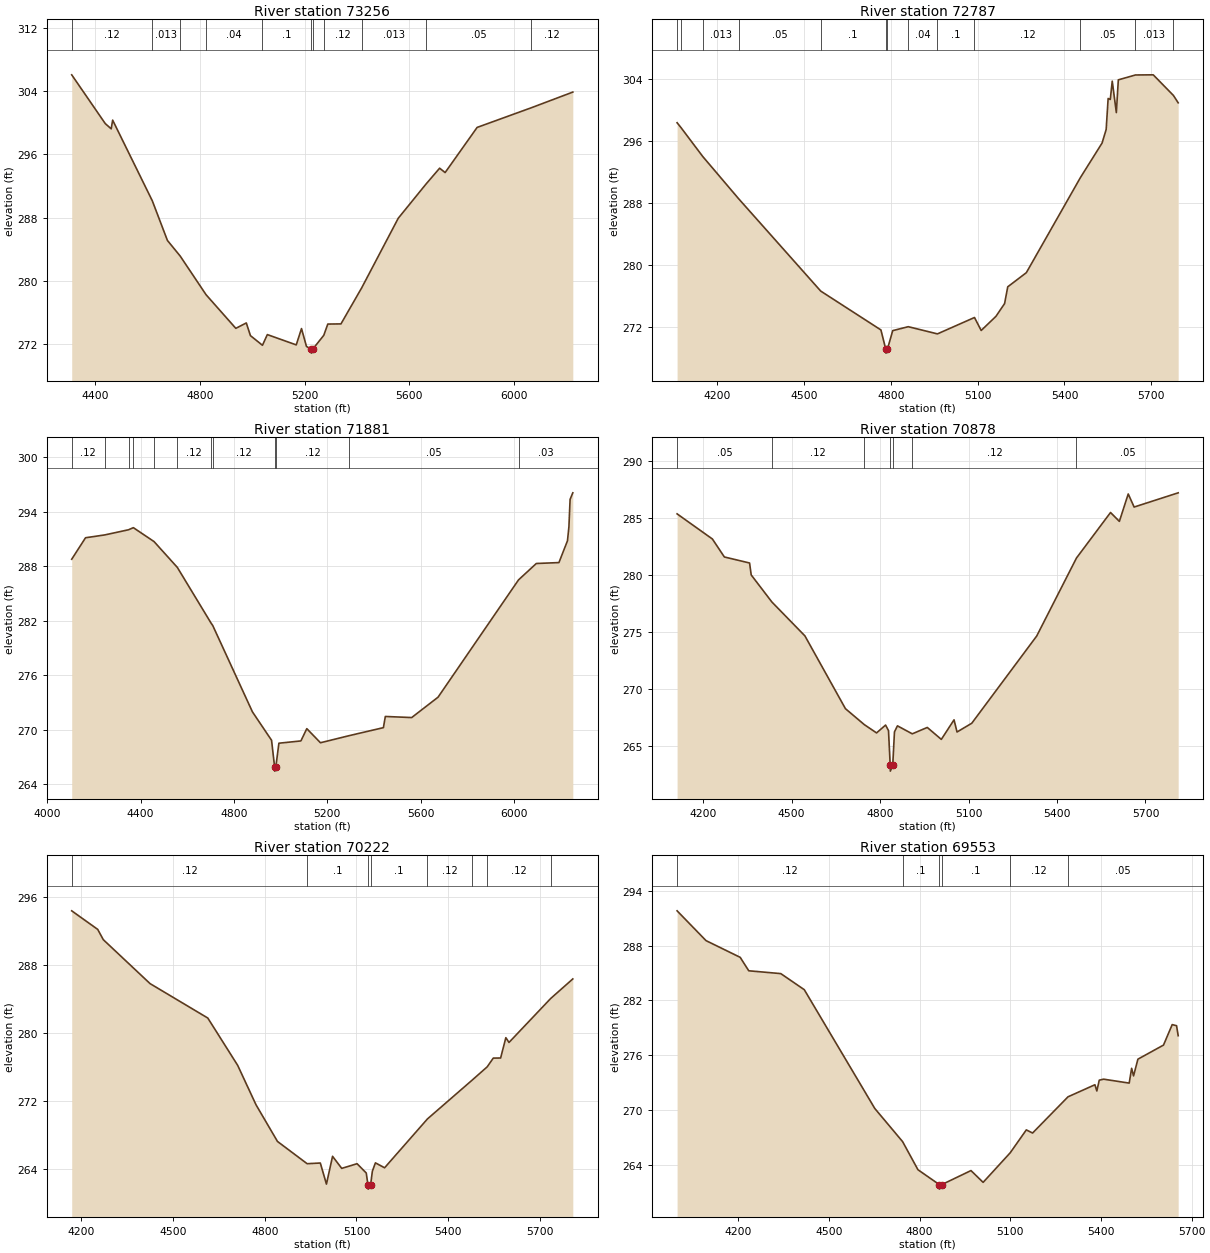
Type RM Length L Ch R = 1,73256,469,469,469
BEGIN DESCRIPTION:
Mapping XS 5b5c4a04
END DESCRIPTION:
XS GIS Cut Line= 4
      2540371.34     13623677.55      2540010.27     13623503.96
      2539183.88     13623580.35      2538621.37     13623969.25
#Sta/Elev= 30
  4310.5  306.04  4438.7  299.88  4461.3  299.22  4466.9  300.32  4618.3  290.14
  4676.1  285.13  4724.8  283.16  4823.9  278.27  4937.4  274.03  4977.5  274.71
  4993.3  273.11  5039.2  271.89  5057.9  273.24  5168.3  271.94  5188.4  274.00
  5207.4  271.74  5225.8  271.40  5226.2  270.90  5231.3  271.40  5273.5  273.15
  5288.9  274.57  5339.1  274.59  5418.3  279.14  5558.0  287.93  5664.4  292.26
  5716.1  294.25  5737.1  293.70  5859.4  299.40  6066.3  301.88  6224.9  303.86
#Mann=11,-1,0
  4310.5    0.12       0  4618.3   0.013       0  4724.8    0.12       0
  4823.9    0.04       0  5039.2     0.1       0  5225.8    0.04       0
  5231.3     0.1       0  5273.5    0.12       0  5418.3   0.013       0
  5664.4    0.05       0  6066.3    0.12       0
Bank Sta=5225.8,5231.3
Exp/Cntr=0.3,0.1

Type RM Length L Ch R = 1,72787,906,906,906
BEGIN DESCRIPTION:
Mapping XS 5e72d2c8
END DESCRIPTION:
XS GIS Cut Line= 4
      2540385.28     13623198.41      2540044.99     13623087.30
      2539246.38     13623247.02      2538864.46     13623656.71
#Sta/Elev= 30
  4060.8  298.39  4074.7  297.74  4149.3  294.03  4273.7  288.55  4557.3  276.61
  4765.5  271.58  4782.3  269.08  4782.8  268.58  4787.9  269.08  4806.3  271.49
  4860.0  272.00  4960.9  271.07  5089.0  273.19  5112.2  271.51  5163.2  273.34
  5193.1  274.99  5204.0  277.16  5268.3  278.99  5455.0  291.28  5530.1  295.76
  5544.3  297.52  5551.1  301.53  5558.5  301.40  5565.3  303.77  5579.5  299.70
  5586.3  303.94  5645.6  304.57  5707.0  304.59  5776.9  301.92  5793.3  300.97
#Mann=13,-1,0
  4060.8    0.05       0  4074.7    0.12       0  4149.3   0.013       0
  4273.7    0.05       0  4557.3     0.1       0  4782.3    0.05       0
  4787.9     0.1       0  4860.0    0.04       0  4960.9     0.1       0
  5089.0    0.12       0  5455.0    0.05       0  5645.6   0.013       0
  5776.9    0.05       0
Bank Sta=4782.3,4787.9
Exp/Cntr=0.3,0.1

Type RM Length L Ch R = 1,71881,1003,1003,1003
BEGIN DESCRIPTION:
Mapping XS 8a4c5dec
END DESCRIPTION:
XS GIS Cut Line= 3
      2540642.20     13622878.96      2539593.60     13622552.57
      2538572.77     13622316.46
#Sta/Elev= 30
  4105.4  288.77  4164.6  291.13  4246.7  291.44  4348.9  292.01  4369.3  292.24
  4458.0  290.71  4557.7  287.87  4702.6  281.73  4709.4  281.48  4879.3  271.99
  4961.3  268.86  4974.1  265.97  4974.5  265.47  4979.7  265.97  4992.7  268.54
  5086.9  268.79  5112.2  270.14  5170.7  268.59  5293.6  269.37  5440.2  270.25
  5448.5  271.48  5561.4  271.36  5674.3  273.60  6019.0  286.50  6095.2  288.30
  6192.0  288.40  6228.6  290.80  6234.7  292.33  6239.8  295.35  6251.4  296.07
#Mann=12,-1,0
  4105.4    0.12       0  4246.7   0.013       0  4348.9    0.05       0
  4369.3    0.12       0  4458.0    0.05       0  4557.7    0.12       0
  4702.6    0.05       0  4709.4    0.12       0  4974.1    0.05       0
  4979.7    0.12       0  5293.6    0.05       0  6019.0    0.03       0
Bank Sta=4974.1,4979.7
Exp/Cntr=0.3,0.1

Type RM Length L Ch R = 1,70878,656,656,656
BEGIN DESCRIPTION:
Mapping XS 3dbf5db0
END DESCRIPTION:
XS GIS Cut Line= 3
      2540753.31     13621927.57      2539857.49     13621788.69
      2539065.78     13621753.96
#Sta/Elev= 30
  4111.9  285.38  4231.6  283.17  4272.1  281.59  4357.6  281.06  4363.2  280.01
  4433.3  277.63  4545.3  274.65  4682.7  268.25  4746.6  266.85  4788.2  266.12
  4818.8  266.81  4828.7  266.32  4834.5  263.26  4835.0  262.76  4843.0  263.26
  4848.9  266.21  4859.0  266.74  4909.3  266.04  4960.2  266.60  5007.8  265.55
  5050.9  267.27  5061.0  266.20  5111.0  266.97  5331.2  274.64  5466.1  281.50
  5581.5  285.50  5611.5  284.72  5641.5  287.13  5661.5  285.98  5810.9  287.23
#Mann=7,-1,0
  4111.9    0.05       0  4433.3    0.12       0  4746.6     0.1       0
  4834.5    0.05       0  4843.0     0.1       0  4909.3    0.12       0
  5466.1    0.05       0
Bank Sta=4834.5,4843
Exp/Cntr=0.3,0.1

Type RM Length L Ch R = 1,70222,669,669,669
BEGIN DESCRIPTION:
Mapping XS defde69a
END DESCRIPTION:
XS GIS Cut Line= 4
      2540892.17     13621441.45      2540482.49     13621267.85
      2539746.38     13621240.07      2539301.90     13621344.25
#Sta/Elev= 30
  4169.1  294.32  4254.0  292.14  4272.3  290.93  4425.2  285.76  4614.0  281.71
  4711.6  276.15  4771.6  271.51  4841.7  267.20  4938.7  264.58  4981.8  264.66
  5001.8  262.18  5021.8  265.45  5051.8  264.03  5101.9  264.58  5131.9  263.49
  5137.6  262.09  5138.1  261.59  5146.2  262.09  5151.9  263.69  5161.9  264.68
  5191.9  264.10  5332.1  269.85  5476.9  274.37  5527.3  275.97  5547.2  277.00
  5571.2  277.01  5588.3  279.40  5598.6  278.84  5734.9  284.01  5807.2  286.31
#Mann=8,-1,0
  4169.1    0.12       0  4938.7     0.1       0  5137.6    0.05       0
  5146.2     0.1       0  5332.1    0.12       0  5476.9    0.05       0
  5527.3    0.12       0  5734.9    0.05       0
Bank Sta=5137.6,5146.2
Exp/Cntr=0.3,0.1

Type RM Length L Ch R = 1,69553,643,643,643
BEGIN DESCRIPTION:
LGII4317
END DESCRIPTION:
XS GIS Cut Line= 4
      2540871.71     13621303.58      2540378.65     13620810.52
      2539982.81     13620768.85      2539545.32     13621123.02
#Sta/Elev= 30
  3997.3  291.81  4093.0  288.55  4206.1  286.72  4234.4  285.25  4340.5  284.94
  4418.2  283.18  4651.6  270.18  4743.5  266.56  4794.4  263.48  4864.9  261.86
  4865.4  261.36  4873.5  261.86  4969.8  263.39  5010.0  262.10  5099.7  265.34
  5152.9  267.84  5173.7  267.50  5290.9  271.46  5379.9  272.78  5386.3  272.10
  5394.3  273.28  5408.7  273.39  5493.4  272.96  5501.4  274.58  5507.8  273.75
  5522.2  275.58  5606.9  277.12  5635.7  279.36  5650.1  279.24  5655.5  278.15
#Mann=6,-1,0
  3997.3    0.12       0  4743.5     0.1       0  4864.9    0.05       0
  4873.5     0.1       0  5099.7    0.12       0  5290.9    0.05       0
Bank Sta=4864.9,4873.5
Exp/Cntr=0.3,0.1

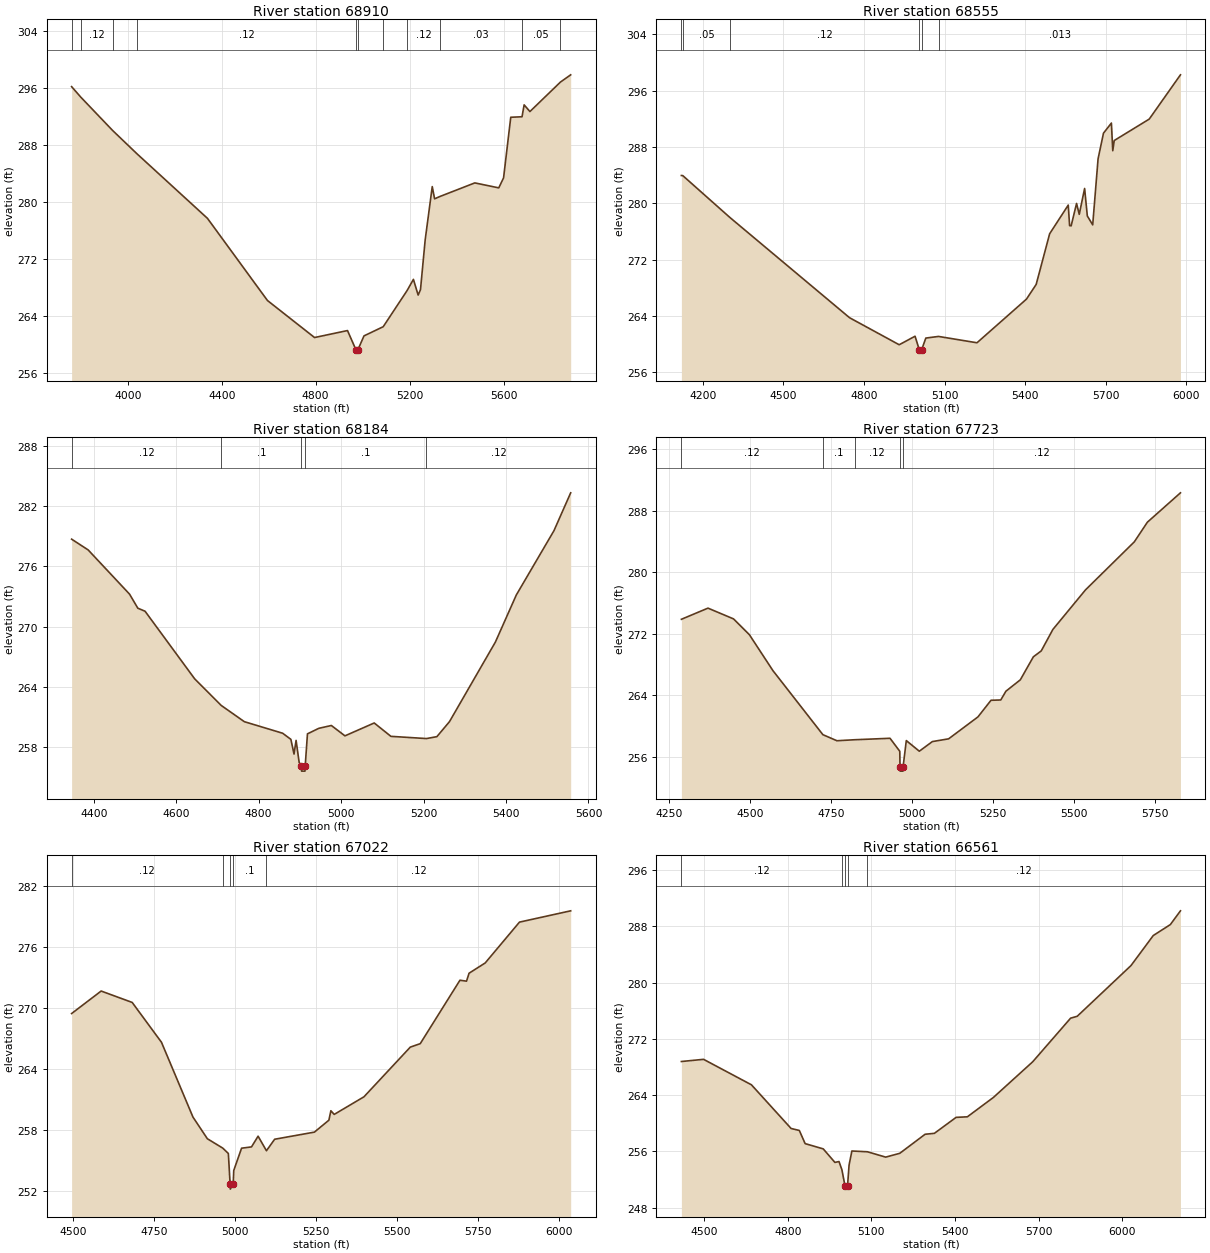
Type RM Length L Ch R = 1,68910,355,355,355
BEGIN DESCRIPTION:
Mapping XS bcf5e7a9
END DESCRIPTION:
XS GIS Cut Line= 4
      2541190.82     13620656.74      2540663.05     13620267.85
      2539656.10     13620198.41      2539204.75     13620288.68
#Sta/Elev= 30
  3760.7  296.24  3799.9  294.76  3935.4  290.08  4039.3  286.80  4339.2  277.74
  4594.7  266.20  4795.2  261.00  4935.5  261.98  4971.1  259.31  4971.6  258.81
  4980.2  259.31  5005.7  261.23  5087.6  262.52  5189.1  267.59  5216.2  269.17
  5236.3  266.97  5246.3  267.72  5266.3  274.72  5296.4  282.20  5306.4  280.48
  5329.0  280.81  5477.7  282.72  5579.7  282.02  5600.1  283.43  5630.7  291.94
  5678.7  292.01  5687.7  293.68  5712.3  292.74  5842.2  296.88  5885.9  297.90
#Mann=11,-1,0
  3760.7    0.03       0  3799.9    0.12       0  3935.4    0.03       0
  4039.3    0.12       0  4971.1    0.05       0  4980.2    0.12       0
  5087.6     0.1       0  5189.1    0.12       0  5329.0    0.03       0
  5678.7    0.05       0  5842.2    0.03       0
Bank Sta=4971.1,4980.2
Exp/Cntr=0.3,0.1

Type RM Length L Ch R = 1,68555,371,371,371
BEGIN DESCRIPTION:
Mapping XS 3cf0259e
END DESCRIPTION:
XS GIS Cut Line= 3
      2541038.06     13620073.41      2540242.08     13619909.24
      2539198.93     13619844.31
#Sta/Elev= 30
  4119.9  283.96  4125.2  283.94  4300.4  278.00  4745.9  263.76  4930.7  259.92
  4989.8  261.13  5005.3  259.23  5005.8  258.73  5014.5  259.23  5029.9  260.87
  5077.3  261.10  5220.3  260.20  5404.5  266.40  5440.7  268.49  5490.8  275.68
  5560.1  279.76  5565.1  276.84  5570.9  276.81  5591.0  279.99  5601.0  278.44
  5621.0  282.12  5631.1  278.21  5651.1  276.95  5671.1  286.33  5691.2  289.97
  5720.7  291.41  5725.8  287.48  5731.3  288.93  5861.5  291.97  5977.8  298.26
#Mann=6,-1,0
  4119.9    0.12       0  4125.2    0.05       0  4300.4    0.12       0
  5005.3    0.05       0  5014.5    0.12       0  5077.3   0.013       0
Bank Sta=5005.3,5014.5
Exp/Cntr=0.3,0.1

Type RM Length L Ch R = 1,68184,461,461,461
BEGIN DESCRIPTION:
IRISH CREEK 130.0
END DESCRIPTION:
XS GIS Cut Line= 3
      2540825.00     13619525.00      2540225.00     13619575.00
      2539624.96     13619474.99
#Sta/Elev= 30
  4346.4  278.71  4386.5  277.64  4486.9  273.24  4507.0  271.84  4524.5  271.54
  4644.9  264.81  4709.1  262.17  4765.3  260.55  4858.2  259.40  4878.2  258.79
  4885.8  257.33  4890.8  258.69  4898.3  256.49  4903.7  256.13  4904.2  255.63
  4912.4  255.63  4912.9  256.13  4918.4  259.34  4946.0  259.89  4976.4  260.17
  5009.3  259.14  5080.3  260.42  5120.8  259.09  5207.0  258.87  5232.3  259.06
  5262.8  260.55  5374.3  268.48  5425.0  273.16  5516.2  279.55  5556.8  283.32
#Mann=5,-1,0
  4346.4    0.12       0  4709.1     0.1       0  4903.7    0.05       0
  4912.9     0.1       0  5207.0    0.12       0
Bank Sta=4903.7,4912.9
Exp/Cntr=0.3,0.1

Type RM Length L Ch R = 1,67723,701,701,701
BEGIN DESCRIPTION:
Mapping XS b2cf7c14
END DESCRIPTION:
XS GIS Cut Line= 3
      2540926.96     13619302.58      2540378.33     13619149.80
      2539413.44     13619240.04
#Sta/Elev= 30
  4288.7  273.90  4370.7  275.35  4449.5  273.95  4498.3  271.90  4571.0  267.22
  4724.9  258.90  4768.2  258.11  4822.6  258.24  4931.9  258.43  4962.0  256.74
  4962.7  254.66  4963.2  254.16  4971.5  254.16  4972.0  254.66  4982.1  258.13
  5022.2  256.75  5062.4  258.00  5112.6  258.36  5203.0  261.21  5243.2  263.37
  5273.3  263.41  5289.2  264.55  5333.6  266.03  5373.8  269.02  5398.1  269.79
  5434.0  272.58  5534.5  277.72  5685.1  283.97  5725.3  286.52  5827.3  290.34
#Mann=5,-1,0
  4288.7    0.12       0  4724.9     0.1       0  4822.6    0.12       0
  4962.7    0.05       0  4972.0    0.12       0
Bank Sta=4962.7,4972
Exp/Cntr=0.3,0.1

Type RM Length L Ch R = 1,67022,461,461,461
BEGIN DESCRIPTION:
Mapping XS 1fe04091
END DESCRIPTION:
XS GIS Cut Line= 3
      2540982.48     13618809.51      2540565.83     13618608.13
      2539510.23     13618385.90
#Sta/Elev= 30
  4495.5  269.47  4586.7  271.68  4682.6  270.56  4773.0  266.65  4870.3  259.30
  4914.8  257.17  4962.3  256.25  4979.6  255.72  4985.1  252.72  4985.6  252.22
  4994.5  252.72  4996.3  254.05  5020.4  256.24  5051.2  256.37  5071.5  257.42
  5097.3  255.99  5122.6  257.12  5245.4  257.82  5290.1  258.99  5296.3  259.92
  5306.6  259.56  5398.5  261.29  5541.6  266.17  5572.3  266.51  5694.9  272.74
  5715.3  272.65  5723.1  273.43  5773.0  274.44  5878.8  278.45  6037.0  279.56
#Mann=5,-1,0
  4495.5    0.12       0  4962.3     0.1       0  4985.1    0.05       0
  4994.5     0.1       0  5097.3    0.12       0
Bank Sta=4985.1,4994.5
Exp/Cntr=0.3,0.1

Type RM Length L Ch R = 1,66561,631,631,631
BEGIN DESCRIPTION:
Mapping XS 78bf9d29
END DESCRIPTION:
XS GIS Cut Line= 3
      2540969.56     13618640.25      2540635.27     13618177.57
      2539428.47     13618004.18
#Sta/Elev= 30
  4418.5  268.77  4498.0  269.08  4669.7  265.46  4812.0  259.25  4841.5  258.97
  4862.3  257.10  4927.3  256.35  4969.1  254.43  4983.8  254.55  4994.2  253.39
  5005.1  251.13  5005.6  250.63  5014.5  251.13  5019.9  254.05  5030.0  256.05
  5085.7  255.94  5151.2  255.18  5201.7  255.72  5292.7  258.43  5325.9  258.56
  5403.8  260.83  5444.2  260.91  5537.5  263.66  5678.5  268.73  5814.5  274.93
  5838.2  275.20  6031.1  282.41  6111.0  286.68  6172.1  288.23  6208.5  290.19
#Mann=5,-1,0
  4418.5    0.12       0  4994.2     0.1       0  5005.1    0.05       0
  5014.5     0.1       0  5085.7    0.12       0
Bank Sta=5005.1,5014.5
Exp/Cntr=0.3,0.1

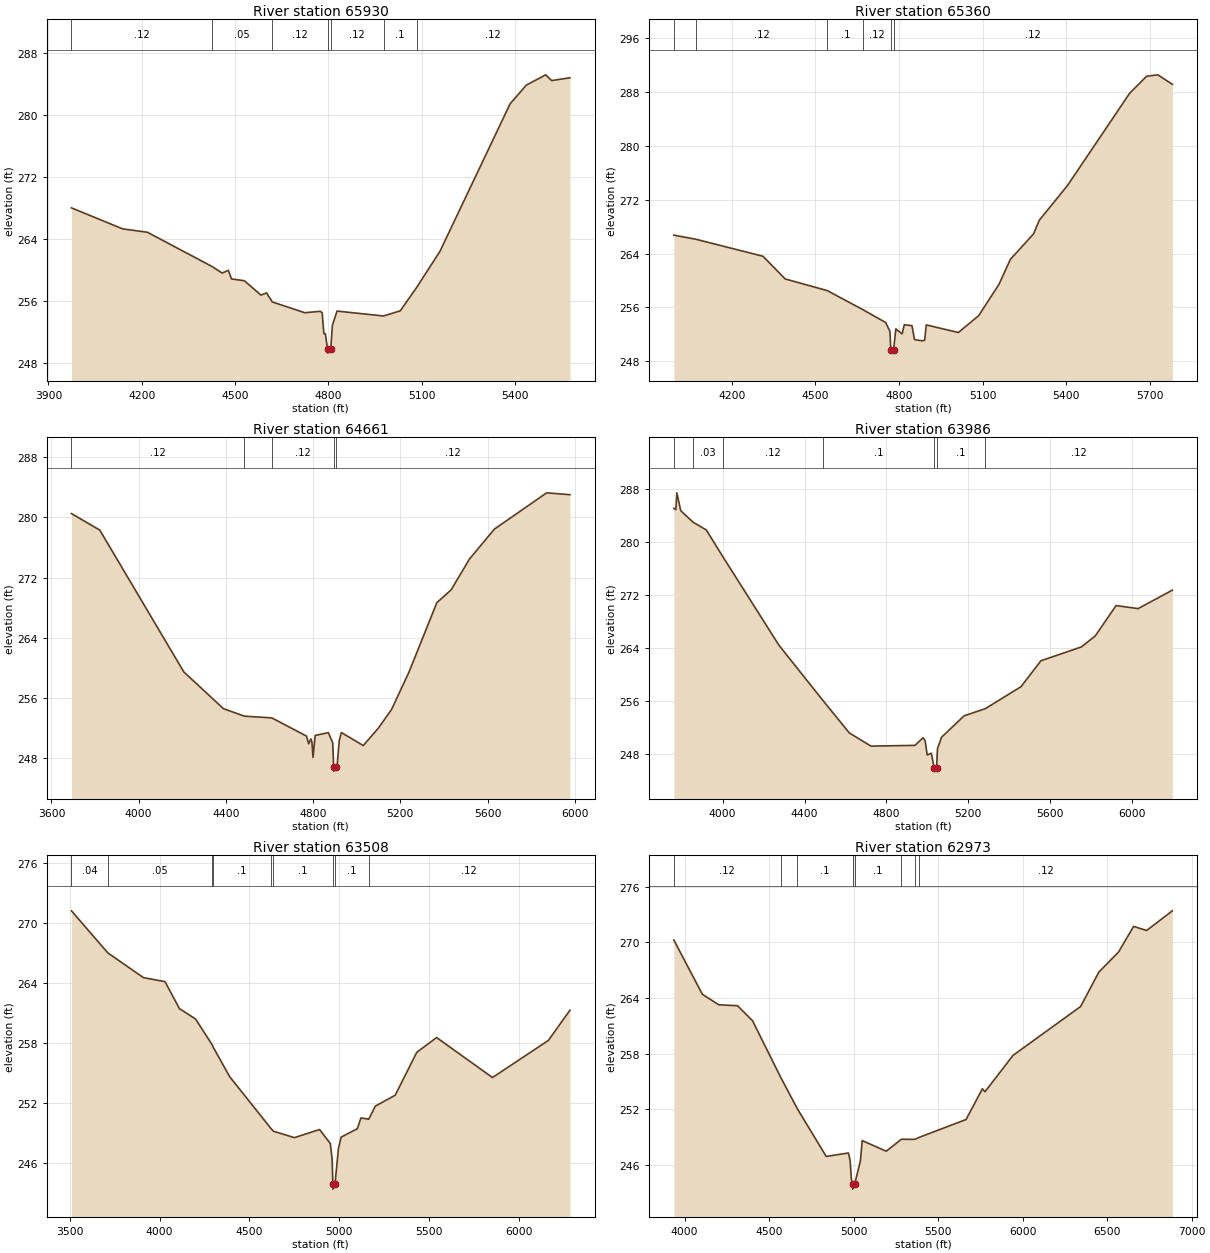
Type RM Length L Ch R = 1,65930,570,570,570
BEGIN DESCRIPTION:
Mapping XS efa3068e
END DESCRIPTION:
XS GIS Cut Line= 4
      2540953.44     13618539.38      2540934.21     13618010.69
      2540836.66     13617740.07      2540079.87     13617524.84
#Sta/Elev= 30
  3974.0  268.02  4138.5  265.31  4218.5  264.87  4426.7  260.45  4458.7  259.61
  4478.7  259.97  4488.7  258.86  4530.3  258.62  4583.5  256.77  4601.7  257.05
  4620.0  255.89  4724.4  254.50  4774.8  254.68  4780.5  254.47  4785.8  251.80
  4790.7  251.80  4797.8  249.79  4798.3  249.29  4807.9  249.79  4813.2  252.85
  4828.2  254.71  4978.0  254.08  5031.5  254.74  5084.6  257.77  5159.0  262.39
  5385.0  281.43  5437.0  283.84  5499.4  285.17  5518.5  284.43  5577.5  284.79
#Mann=7,-1,0
  3974.0    0.12       0  4426.7    0.05       0  4620.0    0.12       0
  4797.8    0.05       0  4807.9    0.12       0  4978.0     0.1       0
  5084.6    0.12       0
Bank Sta=4797.8,4807.9
Exp/Cntr=0.3,0.1

Type RM Length L Ch R = 1,65360,699,699,699
BEGIN DESCRIPTION:
Mapping XS c8c329dc
END DESCRIPTION:
XS GIS Cut Line= 4
      2541690.82     13617858.13      2541475.55     13617573.41
      2540753.33     13617115.07      2540183.89     13617017.85
#Sta/Elev= 30
  3991.7  266.73  4070.2  266.13  4311.7  263.60  4391.5  260.23  4542.6  258.50
  4671.9  255.64  4752.4  253.76  4767.7  252.43  4770.6  249.72  4771.1  249.22
  4780.7  249.72  4788.8  252.82  4811.2  252.08  4819.3  253.44  4846.7  253.29
  4855.8  251.23  4882.9  251.05  4892.2  251.13  4898.1  253.41  5013.3  252.28
  5086.2  254.78  5159.0  259.42  5200.1  263.14  5283.5  266.93  5303.8  268.94
  5405.2  274.10  5628.4  287.80  5689.3  290.32  5729.8  290.53  5781.7  289.12
#Mann=6,-1,0
  3991.7    0.05       0  4070.2    0.12       0  4542.6     0.1       0
  4671.9    0.12       0  4770.6    0.05       0  4780.7    0.12       0
Bank Sta=4770.6,4780.7
Exp/Cntr=0.3,0.1

Type RM Length L Ch R = 1,64661,675,675,675
BEGIN DESCRIPTION:
Mapping XS b68cf9a6
END DESCRIPTION:
XS GIS Cut Line= 4
      2542572.77     13616573.41      2541933.88     13616684.52
      2540906.10     13616628.96      2540322.75     13616802.58
#Sta/Elev= 30
  3691.7  280.52  3821.4  278.33  4207.1  259.46  4389.1  254.57  4485.0  253.58
  4610.6  253.35  4769.7  250.93  4779.7  249.90  4789.6  250.56  4794.6  250.14
  4799.7  248.09  4809.7  251.02  4869.8  251.39  4889.9  250.05  4894.5  246.77
  4895.0  246.27  4905.2  246.77  4909.9  246.89  4919.9  250.34  4929.9  251.40
  5030.1  249.67  5100.2  252.02  5160.1  254.48  5240.4  259.48  5367.5  268.67
  5433.2  270.38  5517.6  274.49  5631.4  278.45  5871.4  283.28  5978.1  283.03
#Mann=5,-1,0
  3691.7    0.12       0  4485.0     0.1       0  4610.6    0.12       0
  4894.5    0.05       0  4905.2    0.12       0
Bank Sta=4894.5,4905.2
Exp/Cntr=0.3,0.1

Type RM Length L Ch R = 1,63986,478,478,478
BEGIN DESCRIPTION:
Mapping XS a7ec643a
END DESCRIPTION:
XS GIS Cut Line= 4
      2542697.81     13616212.30      2542044.99     13616073.41
      2541176.94     13616122.02      2540365.35     13616510.47
#Sta/Elev= 30
  3761.4  285.05  3770.9  284.85  3776.0  287.39  3794.9  284.69  3856.0  282.94
  3919.7  281.79  3999.3  277.82  4275.5  264.35  4489.6  256.04  4619.1  251.12
  4724.9  249.13  4939.6  249.24  4979.7  250.40  4989.7  249.93  4999.7  247.79
  5019.7  248.06  5033.9  245.85  5034.4  245.35  5045.6  245.85  5049.8  248.72
  5069.8  250.47  5180.0  253.70  5284.0  254.79  5458.4  258.11  5555.4  262.02
  5753.1  264.11  5821.1  265.77  5922.9  270.36  6030.7  269.90  6198.0  272.69
#Mann=7,-1,0
  3761.4    0.12       0  3856.0    0.03       0  3999.3    0.12       0
  4489.6     0.1       0  5033.9    0.05       0  5045.6     0.1       0
  5284.0    0.12       0
Bank Sta=5033.9,5045.6
Exp/Cntr=0.3,0.1

Type RM Length L Ch R = 1,63508,535,535,535
BEGIN DESCRIPTION:
Mapping XS 80593e79
END DESCRIPTION:
XS GIS Cut Line= 3
      2543065.81     13615656.74      2541579.71     13615663.69
      2540295.00     13615760.91
#Sta/Elev= 30
  3509.6  271.20  3712.1  267.00  3910.4  264.53  4030.4  264.13  4110.4  261.44
  4200.4  260.40  4293.0  257.82  4298.4  257.59  4390.4  254.64  4618.4  249.51
  4633.6  249.20  4750.4  248.56  4890.4  249.37  4950.4  247.97  4960.4  246.41
  4964.6  243.92  4965.1  243.42  4976.3  243.92  4995.6  247.49  5010.5  248.61
  5100.7  249.45  5120.8  250.53  5164.1  250.40  5201.0  251.71  5311.3  252.79
  5431.7  257.08  5542.0  258.55  5852.9  254.56  6163.8  258.26  6284.1  261.28
#Mann=9,-1,0
  3509.6    0.04       0  3712.1    0.05       0  4293.0    0.12       0
  4298.4     0.1       0  4618.4    0.12       0  4633.6     0.1       0
  4964.6    0.05       0  4976.3     0.1       0  5164.1    0.12       0
Bank Sta=4964.6,4976.3
Exp/Cntr=0.3,0.1

Type RM Length L Ch R = 1,62973,505,505,505
BEGIN DESCRIPTION:
Mapping XS c348bf38
END DESCRIPTION:
XS GIS Cut Line= 3
      2542628.36     13615017.85      2541642.21     13615149.80
      2539719.32     13615496.89
#Sta/Elev= 30
  3936.9  270.26  4105.3  264.41  4202.6  263.27  4313.6  263.17  4402.4  261.55
  4567.9  255.48  4667.5  252.05  4838.2  246.91  4969.6  247.28  4979.8  246.45
  4987.1  244.45  4994.3  243.88  4994.8  243.38  5006.0  243.88  5040.6  246.44
  5050.9  248.62  5193.2  247.47  5282.7  248.76  5362.7  248.75  5388.6  248.97
  5665.3  250.89  5762.3  254.21  5777.5  253.89  5943.2  257.81  6343.5  263.09
  6450.6  266.79  6567.8  268.97  6656.5  271.73  6733.6  271.29  6885.8  273.41
#Mann=8,-1,0
  3936.9    0.12       0  4567.9    0.05       0  4667.5     0.1       0
  4994.3    0.05       0  5006.0     0.1       0  5282.7    0.12       0
  5362.7     0.1       0  5388.6    0.12       0
Bank Sta=4994.3,5006
Exp/Cntr=0.3,0.1