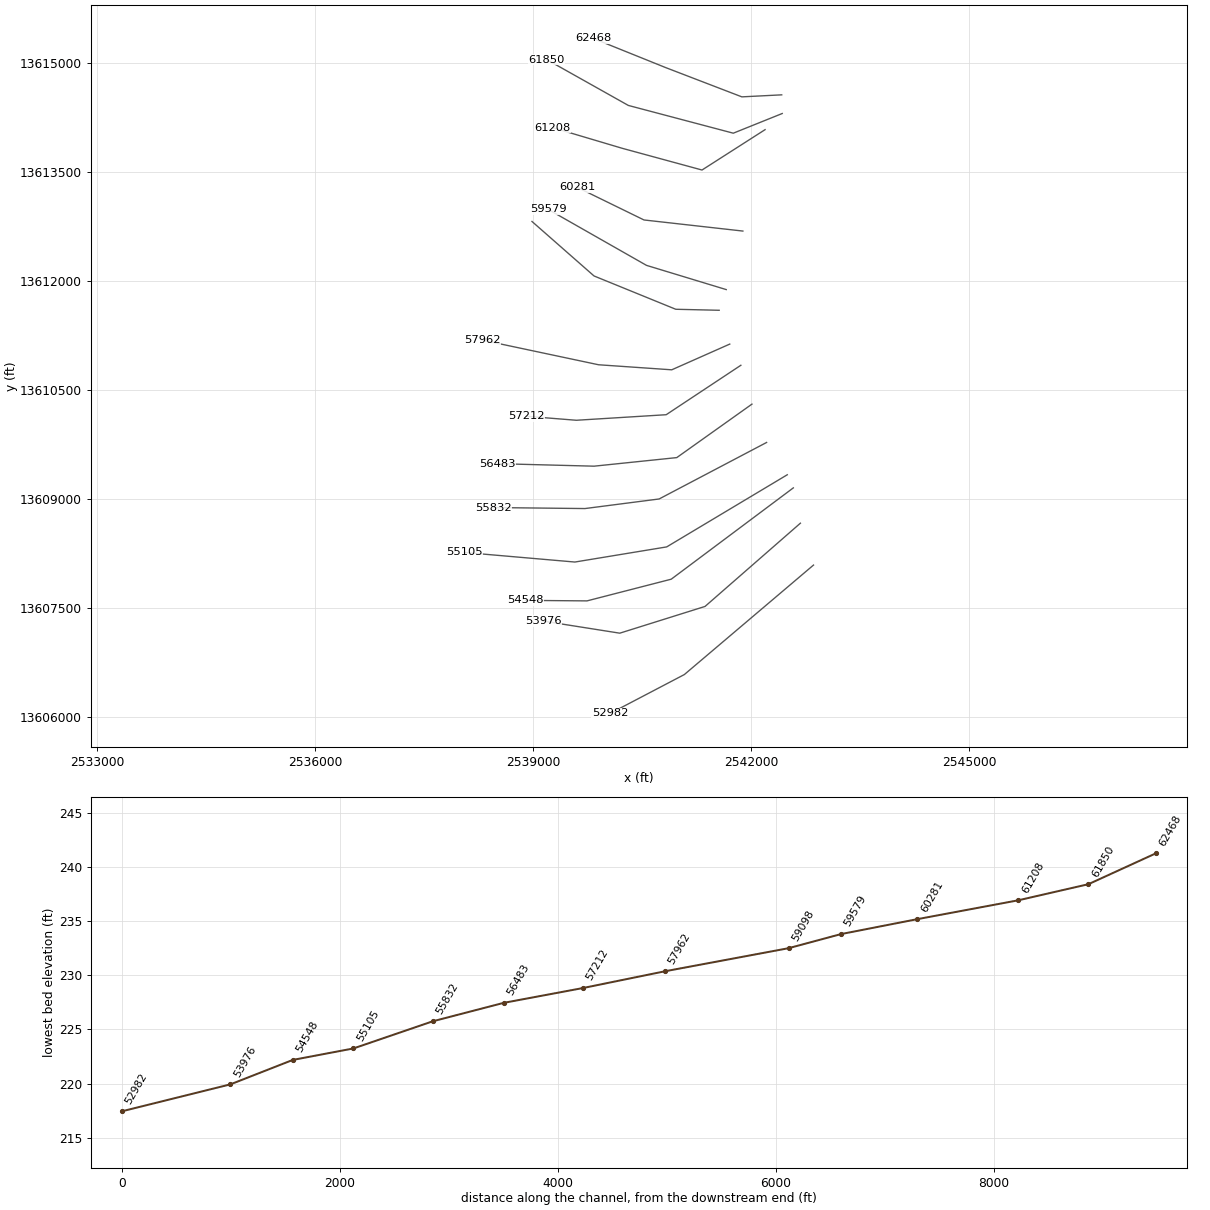
HEC-RAS study IRISH CREEK.prj: IRISH CREEK Base Level Engineering

--- IRISH CREEK.g01 (geometry) --- (continued)

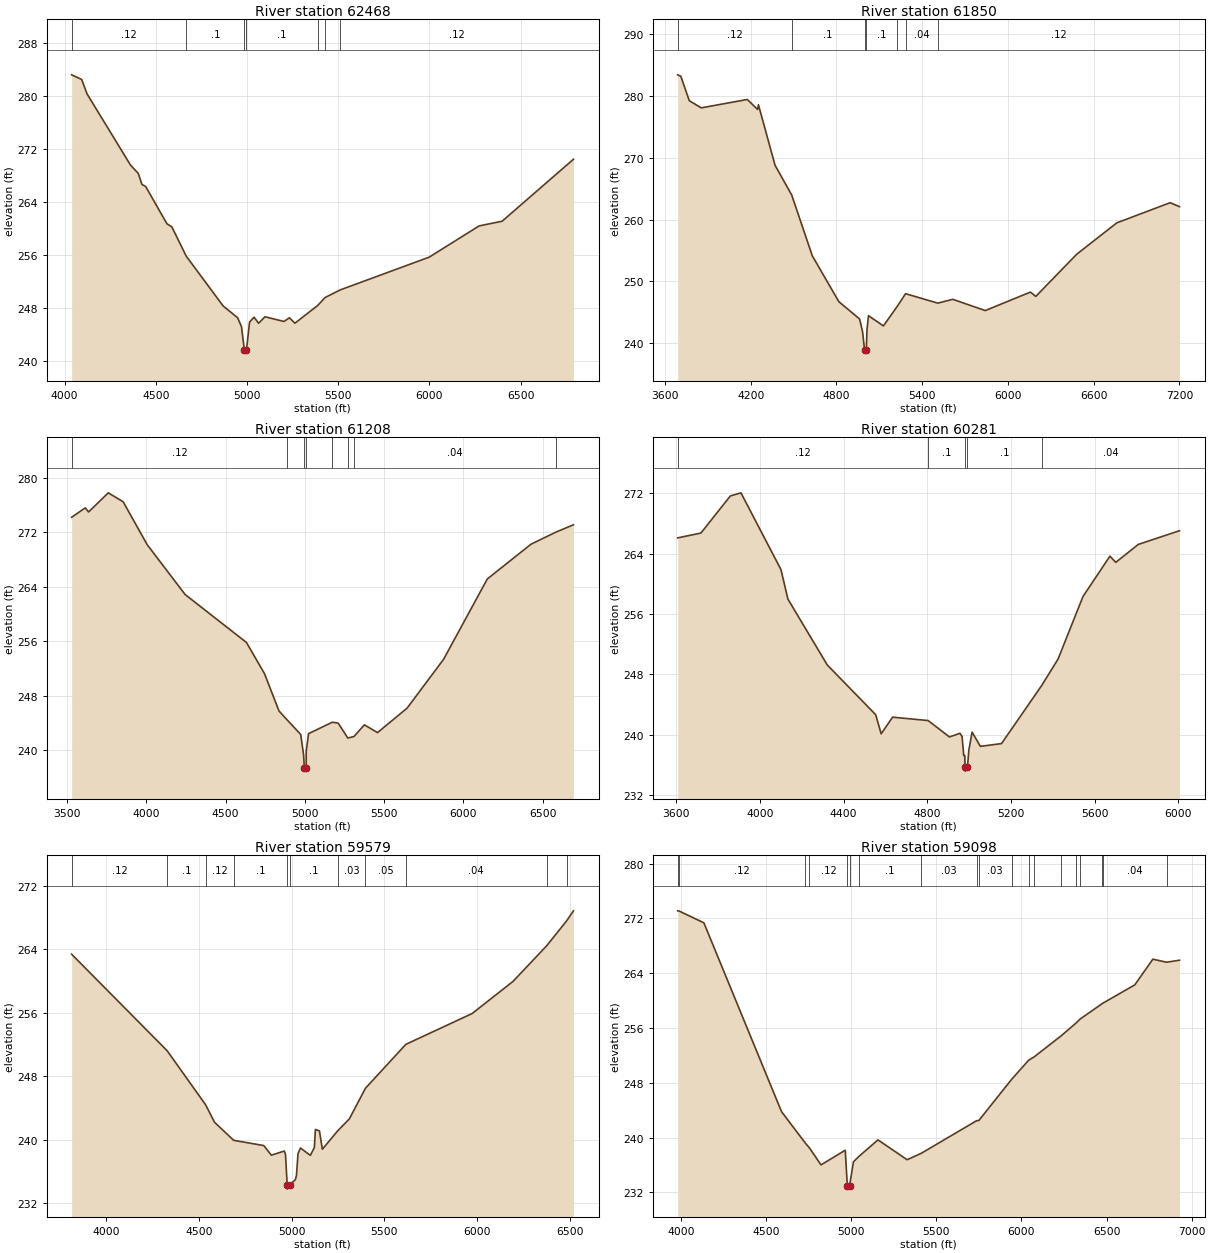
Type RM Length L Ch R = 1,62468,618,618,618
BEGIN DESCRIPTION:
Mapping XS 9f92ccd4
END DESCRIPTION:
XS GIS Cut Line= 4
      2542420.03     13614566.47      2541871.38     13614538.69
      2540822.77     13614941.46      2539822.79     13615344.23
#Sta/Elev= 30
  4038.8  283.26  4093.9  282.56  4123.9  280.35  4361.8  269.62  4404.3  268.36
  4424.3  266.70  4444.4  266.41  4560.8  260.78  4588.2  260.29  4667.3  255.86
  4869.4  248.35  4948.5  246.58  4969.9  245.22  4985.4  241.73  4985.9  241.23
  4997.3  241.73  5014.1  245.92  5038.8  246.66  5063.5  245.74  5098.8  246.72
  5202.8  246.01  5232.8  246.57  5262.8  245.75  5387.4  248.42  5428.3  249.63
  5511.2  250.78  5998.4  255.72  6272.3  260.44  6398.5  261.15  6789.5  270.51
#Mann=7,-1,0
  4038.8    0.12       0  4667.3     0.1       0  4985.4    0.05       0
  4997.3     0.1       0  5387.4    0.05       0  5428.3     0.1       0
  5511.2    0.12       0
Bank Sta=4985.4,4997.3
Exp/Cntr=0.3,0.1

Type RM Length L Ch R = 1,61850,642,642,642
BEGIN DESCRIPTION:
Mapping XS 791f7186
END DESCRIPTION:
XS GIS Cut Line= 4
      2542426.96     13614309.53      2541753.33     13614038.69
      2540308.88     13614420.63      2539183.86     13615052.59
#Sta/Elev= 30
  3689.7  283.44  3711.6  283.21  3770.8  279.25  3854.1  278.09  4176.8  279.45
  4249.1  277.83  4254.5  278.60  4370.8  268.80  4487.6  263.97  4631.2  254.15
  4817.4  246.71  4962.2  243.92  4982.9  241.87  4997.0  238.89  4997.5  238.39
  5009.0  238.89  5013.9  242.17  5024.3  244.45  5129.0  242.80  5225.0  245.94
  5284.0  248.01  5509.4  246.48  5613.9  247.10  5841.4  245.28  6157.2  248.27
  6194.8  247.57  6481.1  254.40  6761.7  259.48  7134.7  262.74  7200.2  262.10
#Mann=7,-1,0
  3689.7    0.12       0  4487.6     0.1       0  4997.0    0.05       0
  5009.0     0.1       0  5225.0    0.05       0  5284.0    0.04       0
  5509.4    0.12       0
Bank Sta=4997,5009
Exp/Cntr=0.3,0.1

Type RM Length L Ch R = 1,61208,927,927,927
BEGIN DESCRIPTION:
Mapping XS 180f489e
END DESCRIPTION:
XS GIS Cut Line= 4
      2542190.80     13614087.28      2541322.77     13613531.74
      2540225.55     13613830.35      2539268.61     13614114.66
#Sta/Elev= 30
  3528.8  274.19  3614.7  275.57  3635.8  274.97  3760.1  277.78  3854.0  276.46
  4005.4  270.17  4244.7  262.85  4631.9  255.80  4746.0  251.21  4836.9  245.75
  4889.8  244.40  4974.2  242.29  4992.4  239.27  4996.7  237.41  4997.2  236.91
  5008.7  237.41  5008.8  239.81  5023.4  242.41  5173.2  244.09  5210.0  243.97
  5271.5  241.77  5309.7  241.99  5375.8  243.71  5458.7  242.57  5645.3  246.16
  5875.2  253.32  6151.3  265.13  6427.3  270.24  6583.5  272.00  6694.8  273.09
#Mann=8,-1,0
  3528.8    0.12       0  4889.8     0.1       0  4996.7    0.05       0
  5008.7     0.1       0  5173.2    0.04       0  5271.5     0.1       0
  5309.7    0.04       0  6583.5   0.013       0
Bank Sta=4996.7,5008.7
Exp/Cntr=0.3,0.1

Type RM Length L Ch R = 1,60281,702,702,702
BEGIN DESCRIPTION:
Mapping XS 0521ba06
END DESCRIPTION:
XS GIS Cut Line= 3
      2541885.31     13612691.46      2540524.16     13612844.24
      2539600.56     13613295.63
#Sta/Elev= 30
  3607.6  266.07  3718.6  266.71  3859.0  271.62  3909.8  272.04  4101.0  261.87
  4134.3  257.96  4322.4  249.23  4553.8  242.64  4579.8  240.11  4634.3  242.32
  4804.2  241.87  4906.0  239.70  4956.3  240.18  4966.4  239.75  4974.4  237.23
  4979.6  237.23  4980.2  235.67  4980.7  235.17  4992.2  235.67  4998.6  237.94
  5014.3  240.34  5053.7  238.45  5154.9  238.82  5346.5  246.50  5425.1  250.02
  5544.0  258.30  5672.8  263.65  5700.9  262.83  5807.9  265.20  6005.3  267.02
#Mann=5,-1,0
  3607.6    0.12       0  4804.2     0.1       0  4980.2    0.05       0
  4992.2     0.1       0  5346.5    0.04       0
Bank Sta=4980.2,4992.2
Exp/Cntr=0.3,0.1

Type RM Length L Ch R = 1,59579,481,481,481
BEGIN DESCRIPTION:
Mapping XS 2d972f29
END DESCRIPTION:
XS GIS Cut Line= 3
      2541656.14     13611885.90      2540558.88     13612219.24
      2539204.77     13612990.04
#Sta/Elev= 30
  3814.2  263.40  4328.9  251.24  4536.5  244.42  4584.4  242.22  4687.8  239.94
  4850.1  239.28  4890.7  238.07  4960.4  238.59  4966.9  238.19  4976.2  234.29
  4976.7  233.79  4989.3  234.29  5020.2  234.99  5025.9  235.48  5034.5  238.27
  5047.6  238.97  5100.9  238.05  5122.5  239.03  5128.3  241.31  5149.9  241.13
  5165.7  238.82  5248.6  241.14  5311.3  242.65  5397.8  246.50  5615.7  252.04
  5972.8  255.92  6193.2  259.97  6374.9  264.47  6481.8  267.59  6519.1  268.87
#Mann=11,-1,0
  3814.2    0.12       0  4328.9     0.1       0  4536.5    0.12       0
  4687.8     0.1       0  4976.2    0.05       0  4989.3     0.1       0
  5248.6    0.03       0  5397.8    0.05       0  5615.7    0.04       0
  6374.9    0.12       0  6481.8    0.05       0
Bank Sta=4976.2,4989.3
Exp/Cntr=0.3,0.1

Type RM Length L Ch R = 1,59098,1136,1136,1136
BEGIN DESCRIPTION:
Mapping XS a0eceb9b
END DESCRIPTION:
XS GIS Cut Line= 4
      2541558.90     13611601.19      2540961.66     13611615.07
      2539836.66     13612073.41      2538982.49     13612823.41
#Sta/Elev= 30
  3979.9  273.11  3985.4  273.12  4133.8  271.37  4590.1  243.80  4730.2  239.21
  4754.3  238.50  4822.1  236.03  4964.6  238.17  4976.7  232.99  4977.2  232.49
  4989.9  232.99  5012.7  236.47  5042.8  237.22  5156.8  239.68  5328.3  236.78
  5411.2  237.72  5736.1  242.47  5749.6  242.51  5942.1  248.51  6041.5  251.29
  6076.3  251.83  6233.2  254.87  6320.9  256.74  6344.8  257.32  6475.6  259.59
  6478.1  259.63  6666.0  262.31  6772.2  266.06  6852.4  265.62  6928.8  265.91
#Mann=19,-1,0
  3979.9    0.05       0  3985.4    0.12       0  4730.2     0.1       0
  4754.3    0.12       0  4976.7    0.05       0  4989.9    0.12       0
  5042.8     0.1       0  5411.2    0.03       0  5736.1   0.013       0
  5749.6    0.03       0  5942.1    0.05       0  6041.5    0.04       0
  6076.3    0.05       0  6233.2    0.12       0  6320.9    0.05       0
  6344.8    0.04       0  6475.6    0.05       0  6478.1    0.04       0
  6852.4    0.12       0
Bank Sta=4976.7,4989.9
Exp/Cntr=0.3,0.1

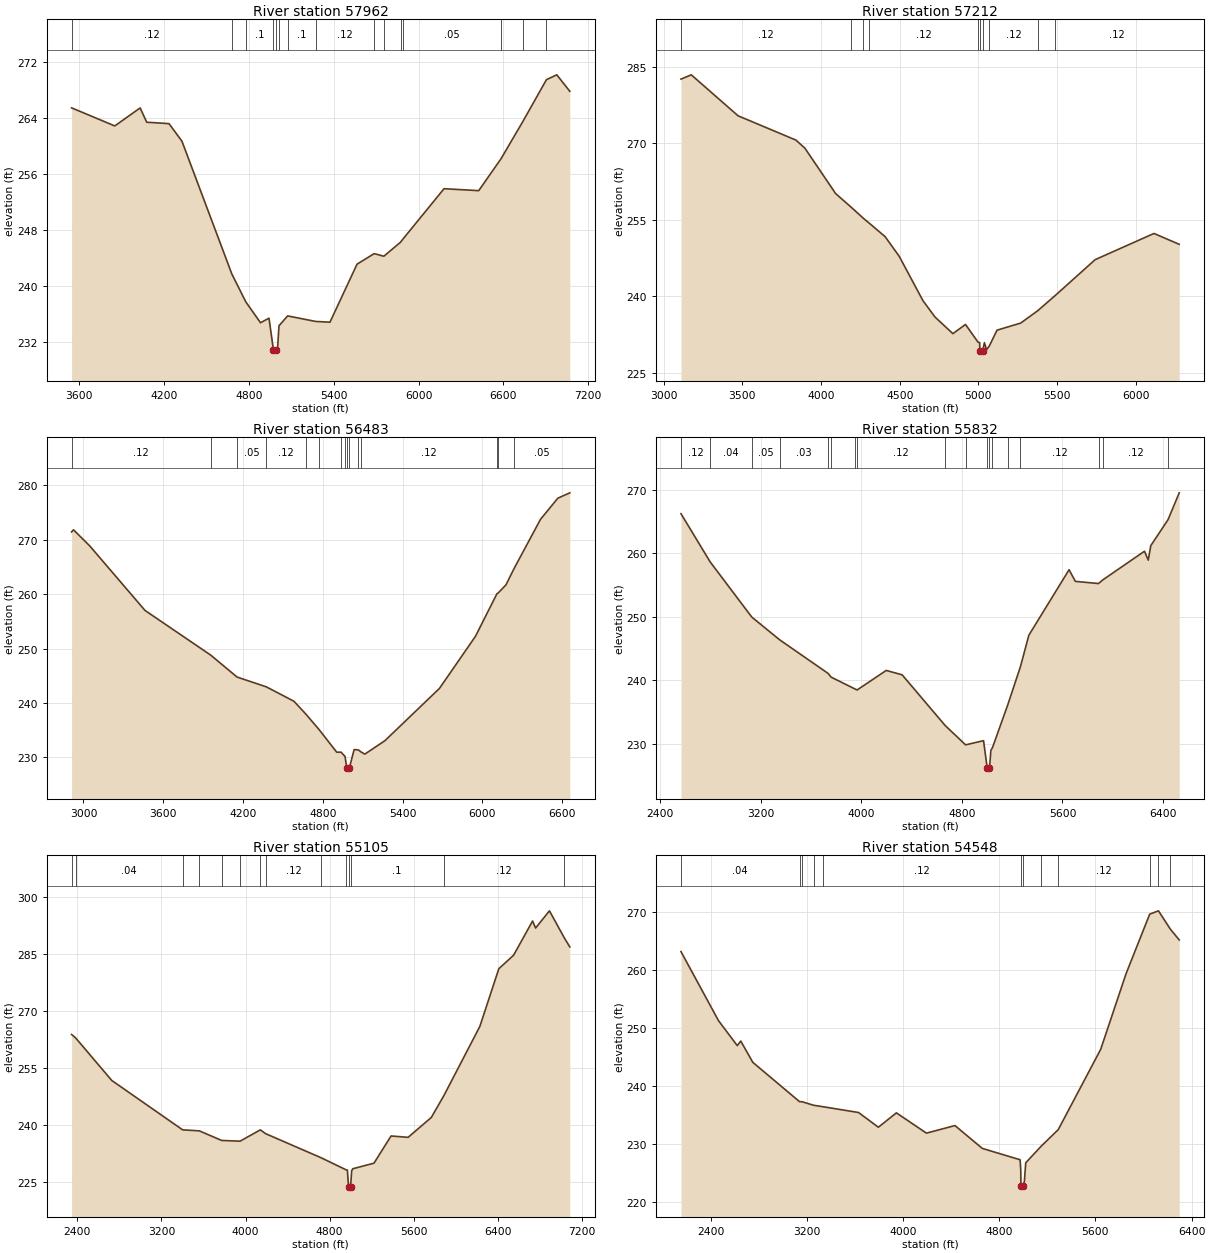
Type RM Length L Ch R = 1,57962,750,750,750
BEGIN DESCRIPTION:
Mapping XS d92ce640
END DESCRIPTION:
XS GIS Cut Line= 4
      2541704.68     13611135.89      2540906.10     13610781.74
      2539899.16     13610851.19      2538294.97     13611191.47
#Sta/Elev= 30
  3546.6  265.49  3852.1  262.90  4031.4  265.48  4078.0  263.43  4235.4  263.23
  4327.1  260.71  4679.1  241.73  4777.9  237.72  4882.4  234.71  4942.5  235.37
  4973.6  230.86  4974.1  230.36  4991.7  230.86  5002.7  230.92  5013.1  234.28
  5074.3  235.69  5271.9  234.90  5373.5  234.79  5565.0  243.10  5686.1  244.61
  5754.7  244.24  5872.6  246.25  5886.5  246.62  6180.0  253.91  6425.3  253.63
  6583.3  258.21  6736.0  263.49  6904.3  269.53  6977.4  270.22  7069.4  267.86
#Mann=15,-1,0
  3546.6    0.12       0  4679.1    0.05       0  4777.9     0.1       0
  4973.6    0.05       0  4991.7     0.1       0  5013.1    0.12       0
  5074.3     0.1       0  5271.9    0.12       0  5686.1    0.04       0
  5754.7    0.05       0  5872.6    0.04       0  5886.5    0.05       0
  6583.3   0.013       0  6736.0    0.12       0  6904.3    0.05       0
Bank Sta=4973.6,4991.7
Exp/Cntr=0.3,0.1

Type RM Length L Ch R = 1,57212,729,729,729
BEGIN DESCRIPTION:
Mapping XS 02b167dc
END DESCRIPTION:
XS GIS Cut Line= 4
      2541857.47     13610844.22      2540829.71     13610163.69
      2539593.60     13610087.30      2538900.03     13610142.78
#Sta/Elev= 30
  3109.8  282.54  3175.3  283.38  3472.6  275.35  3840.2  270.59  3897.3  269.01
  4092.9  260.10  4188.2  257.52  4269.8  255.24  4304.0  254.36  4407.3  251.66
  4497.5  247.78  4647.7  239.11  4724.7  235.89  4838.1  232.64  4918.3  234.44
  4998.5  230.95  5008.4  230.90  5009.3  229.32  5009.8  228.82  5027.6  229.32
  5038.5  230.88  5052.1  229.49  5069.7  230.22  5118.6  233.32  5268.9  234.71
  5377.7  237.14  5489.0  240.13  5742.6  247.15  6116.3  252.28  6276.7  250.15
#Mann=10,-1,0
  3109.8    0.12       0  4188.2    0.03       0  4269.8    0.05       0
  4304.0    0.12       0  4998.5     0.1       0  5009.3    0.05       0
  5027.6     0.1       0  5069.7    0.12       0  5377.7    0.05       0
  5489.0    0.12       0
Bank Sta=5009.3,5027.6
Exp/Cntr=0.3,0.1

Type RM Length L Ch R = 1,56483,651,651,651
BEGIN DESCRIPTION:
Mapping XS dc387a4b
END DESCRIPTION:
XS GIS Cut Line= 4
      2542010.24     13610309.50      2540975.55     13609573.41
      2539836.66     13609455.35      2538504.81     13609490.04
#Sta/Elev= 30
  2910.8  271.44  2925.3  271.83  3047.0  268.88  3462.7  257.01  3956.9  248.79
  4154.7  244.76  4376.1  242.94  4583.3  240.30  4671.9  237.96  4770.6  235.14
  4905.0  230.93  4937.5  230.94  4967.4  230.15  4980.9  227.95  4981.4  227.45
  4999.2  227.95  5035.7  231.42  5068.4  231.34  5089.4  230.95  5116.1  230.58
  5266.9  233.04  5677.4  242.66  5947.5  252.21  6110.2  260.09  6119.4  260.22
  6177.5  261.70  6240.7  264.80  6437.6  273.76  6567.7  277.64  6657.9  278.63
#Mann=15,-1,0
  2910.8    0.12       0  3956.9    0.03       0  4154.7    0.05       0
  4376.1    0.12       0  4671.9    0.05       0  4770.6     0.1       0
  4937.5    0.05       0  4967.4    0.12       0  4980.9    0.05       0
  4999.2    0.12       0  5068.4    0.05       0  5089.4    0.12       0
  6110.2    0.05       0  6119.4    0.12       0  6240.7    0.05       0
Bank Sta=4980.9,4999.2
Exp/Cntr=0.3,0.1

Type RM Length L Ch R = 1,55832,727,727,727
BEGIN DESCRIPTION:
Mapping XS 1bd4c12a
END DESCRIPTION:
XS GIS Cut Line= 4
      2542211.65     13609781.74      2540732.49     13609003.96
      2539711.66     13608872.02      2538448.84     13608885.90
#Sta/Elev= 30
  2565.2  266.22  2797.8  258.63  3128.4  249.97  3349.8  246.40  3734.9  241.12
  3759.4  240.53  3946.1  238.70  3966.6  238.51  4198.0  241.58  4324.6  240.89
  4666.3  232.93  4829.3  229.88  4972.2  230.54  5001.1  226.25  5001.6  225.75
  5019.4  226.25  5030.4  229.02  5042.6  229.42  5164.3  236.14  5265.8  242.19
  5332.4  247.11  5652.4  257.41  5702.4  255.58  5886.5  255.24  5922.7  255.84
  6252.4  260.32  6282.4  258.92  6302.4  261.19  6440.2  265.30  6528.6  269.50
#Mann=18,-1,0
  2565.2    0.12       0  2797.8    0.04       0  3128.4    0.05       0
  3349.8    0.03       0  3734.9    0.05       0  3759.4    0.12       0
  3946.1    0.05       0  3966.6    0.12       0  4666.3     0.1       0
  4829.3    0.12       0  5001.1    0.05       0  5019.4    0.12       0
  5042.6     0.1       0  5164.3    0.05       0  5265.8    0.12       0
  5886.5    0.05       0  5922.7    0.12       0  6440.2    0.05       0
Bank Sta=5001.1,5019.4
Exp/Cntr=0.3,0.1

Type RM Length L Ch R = 1,55105,557,557,557
BEGIN DESCRIPTION:
Mapping XS 77eafc42
END DESCRIPTION:
XS GIS Cut Line= 4
      2542496.42     13609337.32      2540836.66     13608344.24
      2539572.77     13608135.91      2538051.89     13608267.86
#Sta/Elev= 30
  2344.5  263.89  2383.4  262.98  2726.8  251.81  3401.5  238.83  3560.9  238.56
  3772.6  236.04  3948.0  235.85  4140.7  238.82  4190.8  237.83  4720.5  231.48
  4956.4  228.33  4969.5  228.25  4980.6  223.75  4981.1  223.25  4999.0  223.75
  5010.1  228.06  5020.2  228.60  5222.4  230.07  5385.1  237.22  5547.2  236.86
  5768.2  242.09  5887.6  247.82  6229.9  266.00  6410.6  281.17  6551.1  284.71
  6731.8  293.71  6760.4  291.85  6892.4  296.38  7035.5  289.19  7086.2  286.90
#Mann=14,-1,0
  2344.5    0.05       0  2383.4    0.04       0  3401.5    0.03       0
  3560.9    0.12       0  3772.6    0.05       0  3948.0    0.12       0
  4140.7    0.05       0  4190.8    0.12       0  4720.5    0.05       0
  4956.4     0.1       0  4980.6    0.05       0  4999.0     0.1       0
  5887.6    0.12       0  7035.5    0.05       0
Bank Sta=4980.6,4999
Exp/Cntr=0.3,0.1

Type RM Length L Ch R = 1,54548,572,572,572
BEGIN DESCRIPTION:
Mapping XS 1d0908a0
END DESCRIPTION:
XS GIS Cut Line= 4
      2542579.70     13609156.73      2540899.16     13607899.80
      2539739.44     13607601.19      2538892.22     13607608.13
#Sta/Elev= 30
  2153.5  263.18  2465.3  251.27  2621.6  246.95  2650.8  247.74  2750.8  244.07
  3139.6  237.28  3160.5  237.27  3256.9  236.66  3331.4  236.42  3630.3  235.41
  3795.0  232.87  3945.0  235.35  4194.9  231.85  4431.9  233.16  4659.1  229.22
  4973.6  227.26  4979.2  225.50  4980.3  222.69  4980.8  222.19  4998.8  222.69
  5009.2  223.51  5020.5  226.73  5150.9  229.64  5290.7  232.45  5644.1  246.32
  5854.1  259.32  6051.5  269.64  6124.2  270.21  6222.6  267.07  6296.9  265.19
#Mann=12,-1,0
  2153.5    0.04       0  3139.6    0.03       0  3160.5    0.04       0
  3256.9    0.03       0  3331.4    0.12       0  4980.3    0.05       0
  4998.8    0.12       0  5150.9     0.1       0  5290.7    0.12       0
  6051.5    0.05       0  6124.2    0.12       0  6222.6    0.05       0
Bank Sta=4980.3,4998.8
Exp/Cntr=0.3,0.1

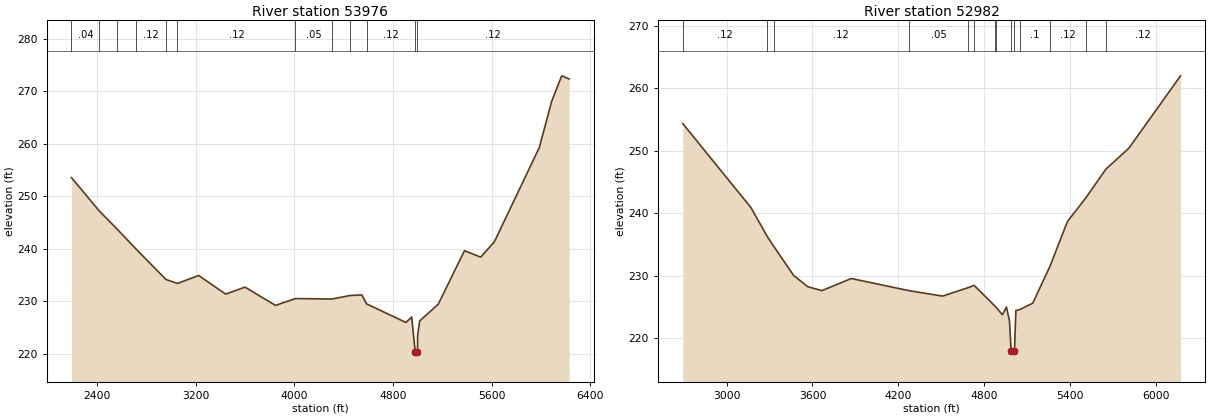
Type RM Length L Ch R = 1,53976,994,994,994
BEGIN DESCRIPTION:
Mapping XS 6f057f31
END DESCRIPTION:
XS GIS Cut Line= 4
      2542676.95     13608670.64      2541364.44     13607524.80
      2540190.83     13607156.74      2539135.28     13607323.41
#Sta/Elev= 30
  2189.2  253.55  2416.7  247.17  2555.2  243.87  2713.5  239.96  2956.6  234.15
  3049.9  233.40  3222.4  234.91  3441.6  231.37  3598.3  232.70  3846.0  229.22
  4008.0  230.52  4304.6  230.43  4453.1  231.11  4546.5  231.21  4585.2  229.52
  4905.6  225.96  4951.4  227.01  4980.2  220.44  4980.7  219.94  4998.7  220.44
  4999.9  223.41  5016.3  226.26  5167.4  229.45  5380.0  239.63  5511.6  238.41
  5623.0  241.33  5987.4  259.26  6088.7  268.12  6169.6  272.93  6230.1  272.34
#Mann=12,-1,0
  2189.2    0.04       0  2416.7    0.12       0  2555.2    0.04       0
  2713.5    0.12       0  2956.6   0.013       0  3049.9    0.12       0
  4008.0    0.05       0  4304.6    0.12       0  4453.1    0.05       0
  4585.2    0.12       0  4980.2    0.05       0  4998.7    0.12       0
Bank Sta=4980.2,4998.7
Exp/Cntr=0.3,0.1

Type RM Length L Ch R = 1,52982,733,733,733
BEGIN DESCRIPTION:
Mapping XS bd579a4e
END DESCRIPTION:
XS GIS Cut Line= 3
      2542857.51     13608094.25      2541079.71     13606587.30
      2540059.46     13606052.88
#Sta/Elev= 30
  2692.8  254.37  3169.0  240.94  3283.8  236.30  3327.7  234.77  3467.8  230.08
  3566.6  228.26  3666.2  227.63  3872.1  229.57  4273.3  227.63  4510.3  226.75
  4691.3  228.12  4731.0  228.47  4874.2  225.21  4881.0  225.05  4928.8  223.77
  4957.4  224.99  4978.2  222.82  4990.1  217.96  4990.6  217.46  5010.3  217.96
  5014.5  218.65  5023.2  224.44  5050.8  224.60  5141.4  225.62  5263.1  231.60
  5384.1  238.70  5510.4  242.41  5653.0  247.08  5814.1  250.44  6175.1  262.02
#Mann=14,-1,0
  2692.8    0.12       0  3283.8   0.013       0  3327.7    0.12       0
  4273.3    0.05       0  4691.3     0.1       0  4731.0    0.12       0
  4874.2     0.1       0  4881.0    0.12       0  4990.1    0.05       0
  5010.3    0.12       0  5050.8     0.1       0  5263.1    0.12       0
  5510.4    0.05       0  5653.0    0.12       0
Bank Sta=4990.1,5010.3
Exp/Cntr=0.3,0.1