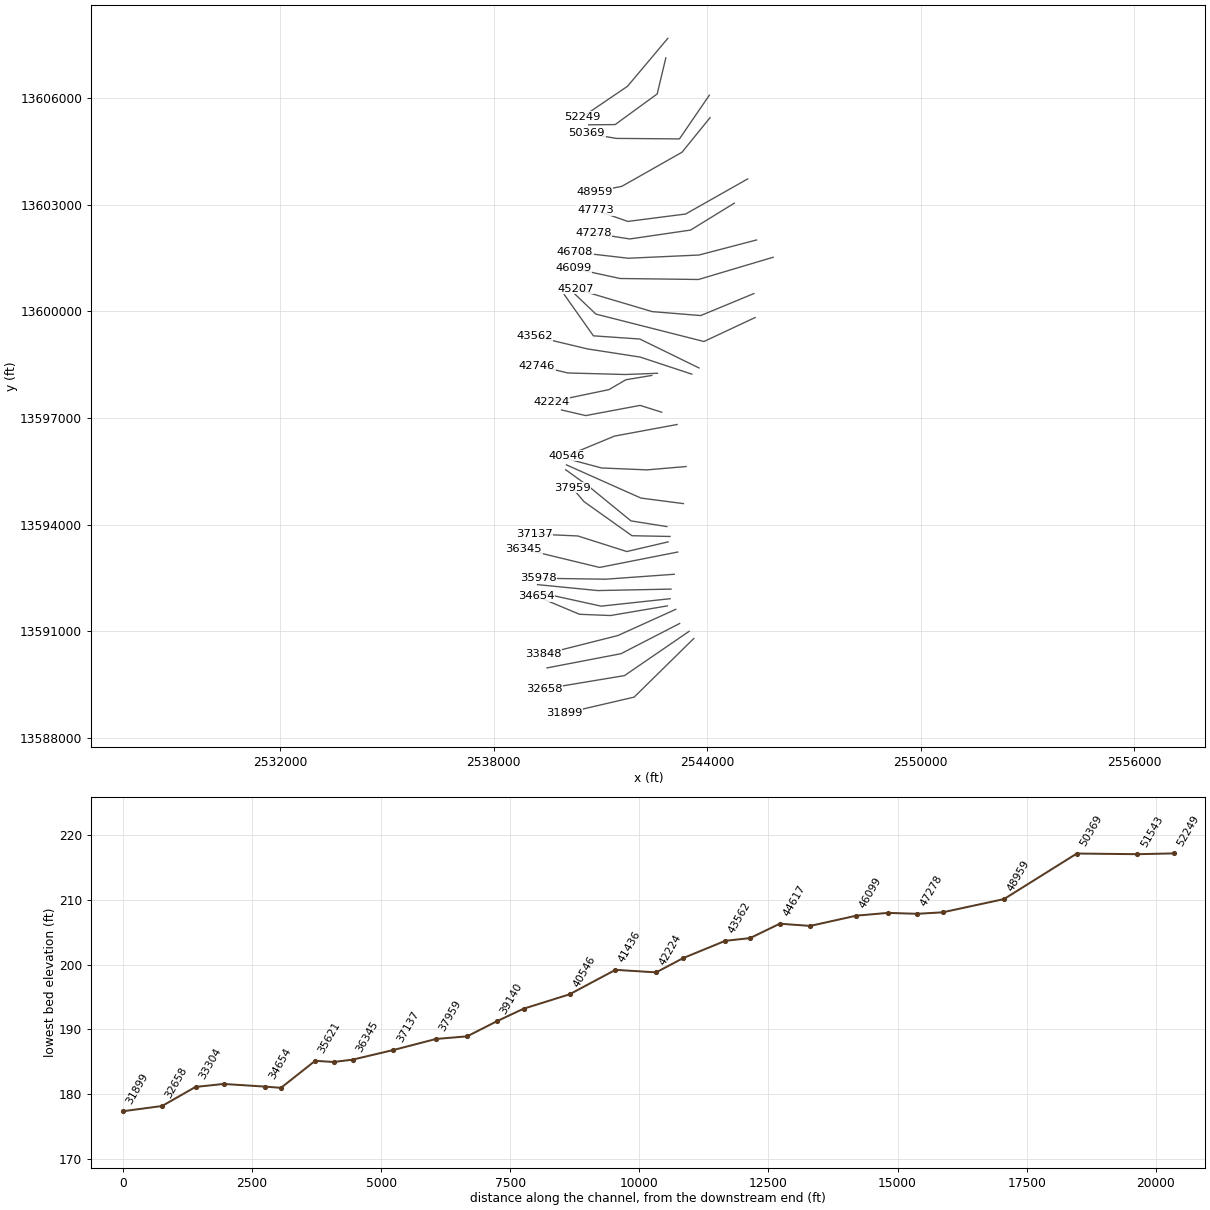
HEC-RAS study IRISH CREEK.prj: IRISH CREEK Base Level Engineering

--- IRISH CREEK.g01 (geometry) --- (continued)

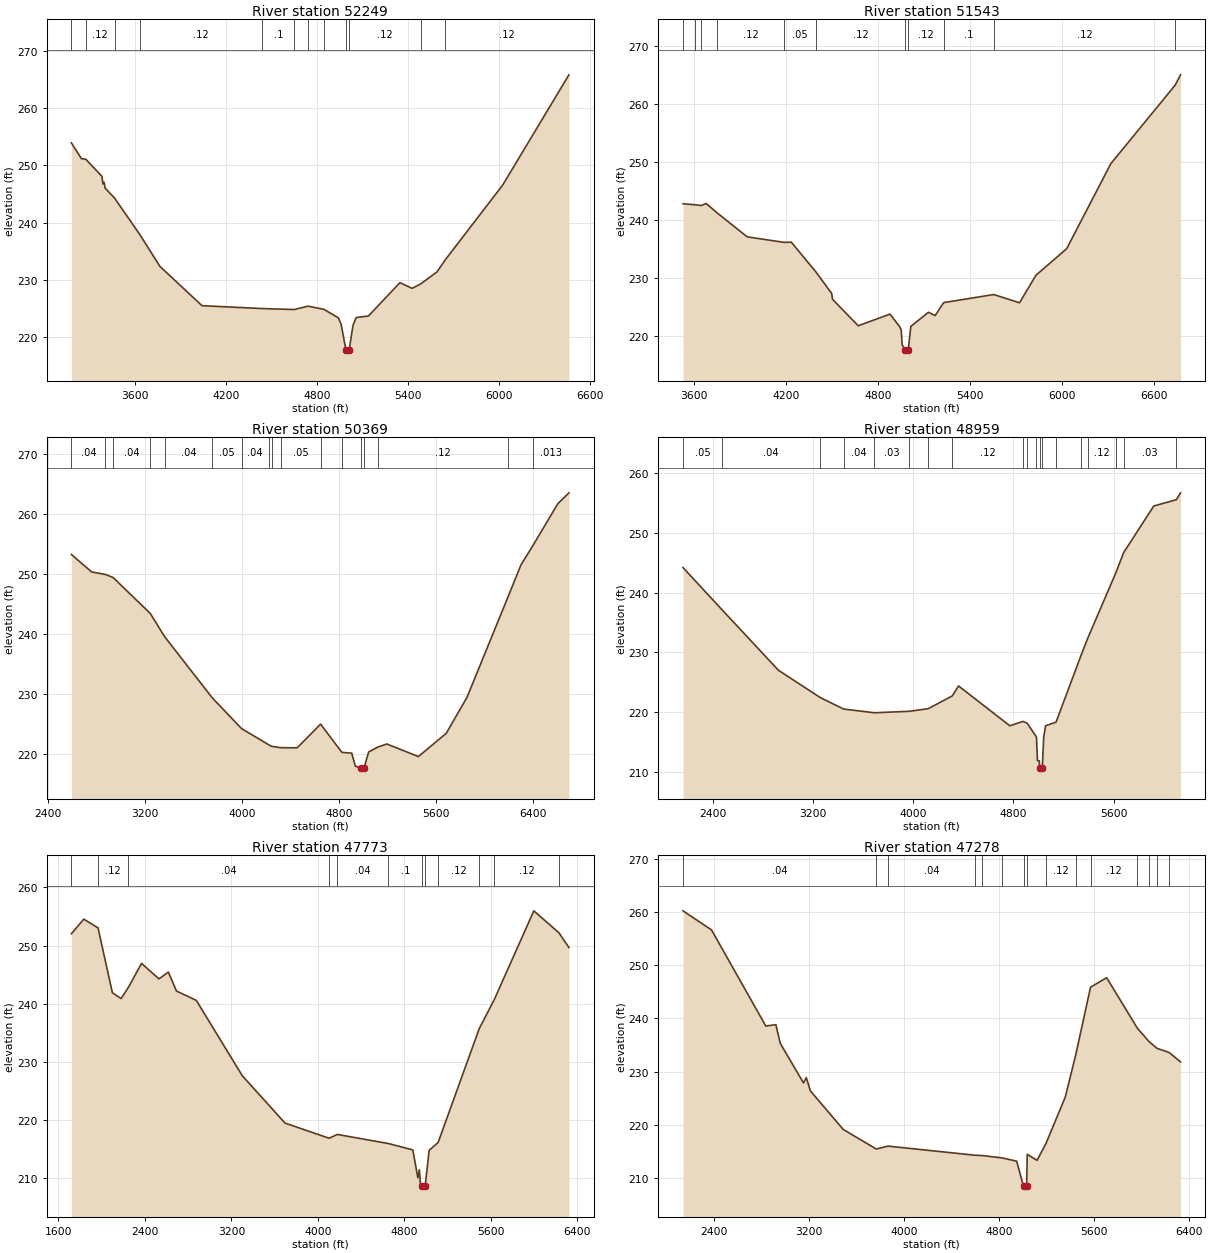
Type RM Length L Ch R = 1,52249,706,706,706
BEGIN DESCRIPTION:
Mapping XS a87090cb
END DESCRIPTION:
XS GIS Cut Line= 3
      2542892.23     13607670.65      2541760.27     13606323.41
      2540503.88     13605469.62
#Sta/Elev= 30
  3180.3  253.91  3246.2  251.16  3275.2  251.05  3381.5  248.07  3388.0  246.74
  3395.8  247.05  3402.3  246.02  3465.0  244.26  3633.7  237.79  3763.9  232.32
  4041.0  225.46  4439.1  224.96  4649.0  224.79  4739.1  225.38  4843.7  224.83
  4940.0  223.33  4958.1  222.17  4990.0  217.67  4990.5  217.17  5010.2  217.67
  5036.0  222.02  5057.0  223.39  5137.7  223.66  5345.3  229.49  5425.2  228.49
  5484.0  229.30  5589.8  231.38  5645.3  233.52  6022.4  246.54  6459.0  265.81
#Mann=12,-1,0
  3180.3    0.05       0  3275.2    0.12       0  3465.0   0.013       0
  3633.7    0.12       0  4439.1     0.1       0  4649.0    0.12       0
  4739.1     0.1       0  4843.7    0.12       0  4990.0    0.05       0
  5010.2    0.12       0  5484.0     0.1       0  5645.3    0.12       0
Bank Sta=4990,5010.2
Exp/Cntr=0.3,0.1

Type RM Length L Ch R = 1,51543,1174,1174,1174
BEGIN DESCRIPTION:
Mapping XS b46fd1be
END DESCRIPTION:
XS GIS Cut Line= 4
      2542836.65     13607122.00      2542593.60     13606108.13
      2541413.05     13605247.02      2540670.02     13605240.08
#Sta/Elev= 30
  3526.8  242.77  3603.5  242.60  3645.9  242.47  3678.0  242.81  3747.9  241.23
  3945.9  237.07  4186.6  236.12  4233.3  236.16  4392.6  231.08  4497.3  227.32
  4502.4  226.32  4670.5  221.76  4877.5  223.77  4942.4  221.54  4950.9  220.96
  4957.0  218.50  4976.3  217.55  4976.8  217.05  4996.5  217.55  5013.4  221.65
  5128.5  224.08  5172.6  223.52  5227.9  225.75  5554.9  227.14  5722.6  225.72
  5830.2  230.46  6030.6  235.03  6318.7  249.67  6738.5  263.19  6773.7  264.97
#Mann=11,-1,0
  3526.8    0.05       0  3603.5   0.013       0  3645.9    0.05       0
  3747.9    0.12       0  4186.6    0.05       0  4392.6    0.12       0
  4976.3    0.05       0  4996.5    0.12       0  5227.9     0.1       0
  5554.9    0.12       0  6738.5    0.05       0
Bank Sta=4976.3,4996.5
Exp/Cntr=0.3,0.1

Type RM Length L Ch R = 1,50369,1410,1410,1410
BEGIN DESCRIPTION:
Mapping XS c1e67dea
END DESCRIPTION:
XS GIS Cut Line= 4
      2544058.86     13606073.37      2543218.60     13604844.24
      2541447.77     13604858.13      2540614.44     13604997.02
#Sta/Elev= 30
  2593.4  253.29  2761.0  250.37  2872.4  249.97  2937.0  249.46  3245.1  243.43
  3363.0  239.57  3755.8  229.37  3997.3  224.24  4223.7  221.52  4245.2  221.29
  4322.1  221.06  4455.9  221.04  4649.1  224.99  4825.0  220.28  4905.9  220.15
  4935.9  217.98  4985.0  217.65  4985.5  217.15  5006.9  217.65  5045.9  220.35
  5121.1  221.16  5195.9  221.68  5455.9  219.58  5685.9  223.46  5857.1  229.46
  6197.8  246.33  6302.1  251.55  6398.2  254.69  6606.2  261.76  6698.0  263.58
#Mann=17,-1,0
  2593.4    0.04       0  2872.4    0.05       0  2937.0    0.04       0
  3245.1    0.05       0  3363.0    0.04       0  3755.8    0.05       0
  3997.3    0.04       0  4223.7    0.05       0  4245.2   0.013       0
  4322.1    0.05       0  4649.1    0.03       0  4825.0     0.1       0
  4985.0    0.05       0  5006.9     0.1       0  5121.1    0.12       0
  6197.8    0.05       0  6398.2   0.013       0
Bank Sta=4985,5006.9
Exp/Cntr=0.3,0.1

Type RM Length L Ch R = 1,48959,1186,1186,1186
BEGIN DESCRIPTION:
Mapping XS 5a4d812b
END DESCRIPTION:
XS GIS Cut Line= 4
      2544079.59     13605442.44      2543291.09     13604469.80
      2541600.55     13603510.91      2540838.30     13603358.46
#Sta/Elev= 30
  2161.9  244.19  2471.6  237.17  2924.0  227.00  3258.3  222.43  3444.2  220.51
  3689.2  219.89  3967.2  220.13  4120.0  220.57  4312.1  222.71  4362.1  224.38
  4771.7  217.71  4875.8  218.44  4909.8  218.15  4980.1  215.97  4984.5  215.80
  4992.4  211.88  5007.5  211.85  5008.8  210.62  5009.3  210.12  5030.9  210.62
  5042.0  215.78  5057.3  217.72  5140.8  218.32  5343.3  229.65  5393.8  232.35
  5617.8  243.29  5680.3  246.68  5921.0  254.49  6101.4  255.55  6134.9  256.70
#Mann=19,-1,0
  2161.9    0.05       0  2471.6    0.04       0  3258.3    0.05       0
  3444.2    0.04       0  3689.2    0.03       0  3967.2   0.013       0
  4120.0    0.03       0  4312.1    0.12       0  4875.8     0.1       0
  4909.8    0.12       0  4980.1    0.03       0  5008.8    0.03       0
  5030.9    0.03       0  5140.8    0.12       0  5343.3     0.1       0
  5393.8    0.12       0  5617.8    0.05       0  5680.3    0.03       0
  6101.4    0.12       0
Bank Sta=5008.8,5030.9
Exp/Cntr=0.3,0.1

Type RM Length L Ch R = 1,47773,495,495,495
BEGIN DESCRIPTION:
Mapping XS 017e96a5
END DESCRIPTION:
XS GIS Cut Line= 4
      2545135.23     13603719.22      2543392.21     13602733.13
      2541767.21     13602524.80      2540858.71     13602843.81
#Sta/Elev= 30
  1719.8  252.03  1834.6  254.54  1966.2  253.03  2098.8  241.88  2179.6  240.87
  2245.0  242.74  2368.7  246.92  2530.3  244.26  2616.9  245.43  2692.0  242.17
  2875.3  240.56  3301.1  227.59  3696.2  219.45  4103.9  216.84  4180.7  217.49
  4652.3  215.93  4879.0  214.83  4925.5  210.02  4939.5  211.42  4949.6  208.94
  4966.8  208.58  4967.3  208.08  4992.9  208.58  5030.2  214.75  5113.3  216.11
  5493.2  235.68  5632.5  240.69  5999.0  255.97  6230.6  252.20  6323.6  249.65
#Mann=12,-1,0
  1719.8    0.05       0  1966.2    0.12       0  2245.0    0.04       0
  4103.9   0.013       0  4180.7    0.04       0  4652.3     0.1       0
  4966.8    0.05       0  4992.9     0.1       0  5113.3    0.12       0
  5493.2    0.05       0  5632.5    0.12       0  6230.6    0.05       0
Bank Sta=4966.8,4992.9
Exp/Cntr=0.3,0.1

Type RM Length L Ch R = 1,47278,570,570,570
BEGIN DESCRIPTION:
Mapping XS 329934c1
END DESCRIPTION:
XS GIS Cut Line= 4
      2544760.25     13603038.67      2543531.10     13602281.74
      2541822.77     13602031.74      2540809.41     13602191.38
#Sta/Elev= 30
  2135.4  260.26  2375.7  256.67  2833.5  238.57  2918.7  238.82  2955.3  235.31
  3151.6  227.85  3175.0  228.85  3210.3  226.33  3486.6  219.09  3765.5  215.40
  3864.5  215.95  4594.6  214.24  4655.1  214.18  4824.1  213.74  4949.5  213.11
  5007.1  208.35  5007.6  207.85  5033.3  208.35  5038.3  214.40  5121.3  213.27
  5197.4  216.49  5358.7  225.15  5446.8  233.07  5572.3  245.87  5708.1  247.67
  5967.5  238.14  6065.0  235.66  6132.2  234.37  6235.7  233.58  6331.3  231.81
#Mann=15,-1,0
  2135.4    0.04       0  3765.5   0.013       0  3864.5    0.04       0
  4594.6    0.05       0  4655.1    0.04       0  4824.1     0.1       0
  5007.1    0.05       0  5033.3     0.1       0  5197.4    0.12       0
  5446.8    0.05       0  5572.3    0.12       0  5967.5    0.05       0
  6065.0    0.12       0  6132.2    0.05       0  6235.7    0.12       0
Bank Sta=5007.1,5033.3
Exp/Cntr=0.3,0.1

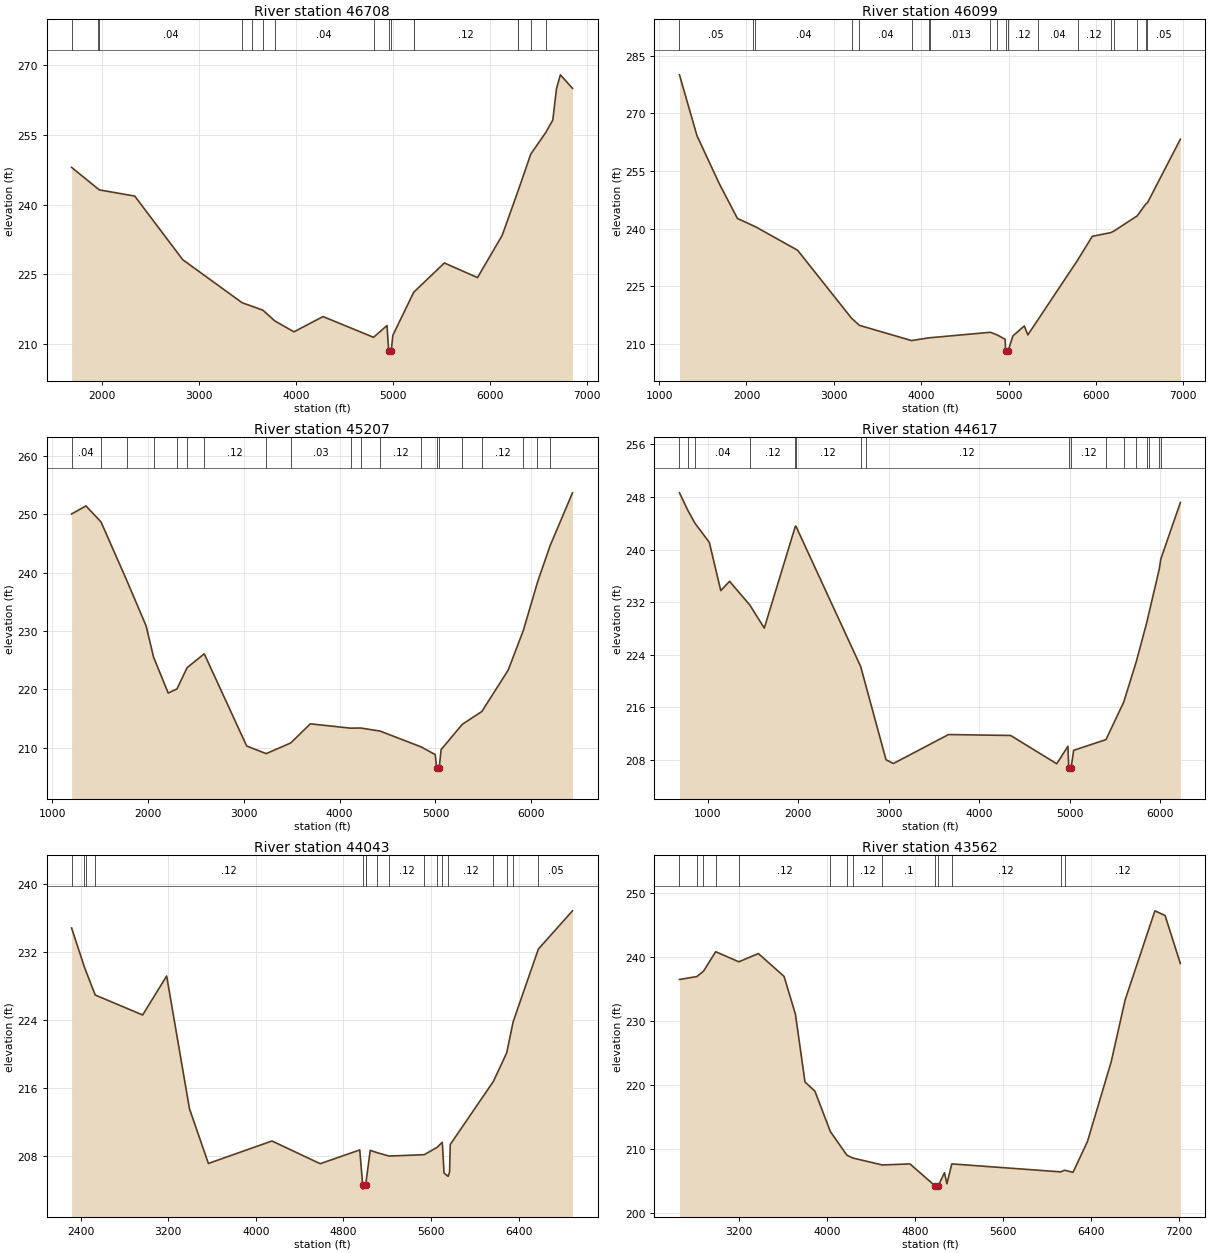
Type RM Length L Ch R = 1,46708,609,609,609
BEGIN DESCRIPTION:
Mapping XS 178efe29
END DESCRIPTION:
XS GIS Cut Line= 4
      2545385.27     13602003.96      2543767.21     13601580.35
      2541781.10     13601490.07      2540281.06     13601663.69
#Sta/Elev= 30
  1683.5  248.02  1954.5  243.43  1970.2  243.17  2335.5  241.84  2831.2  228.12
  3445.5  218.83  3541.0  218.14  3659.5  217.23  3782.1  214.92  3978.9  212.58
  4279.3  215.87  4800.4  211.40  4939.9  213.94  4956.9  208.49  4957.4  207.99
  4983.1  208.49  5000.0  211.83  5214.7  221.08  5215.8  221.12  5531.6  227.42
  5873.9  224.27  6128.5  233.36  6291.7  242.91  6292.5  242.95  6424.1  250.90
  6577.9  255.52  6651.1  258.21  6689.3  265.00  6729.5  267.97  6854.3  265.06
#Mann=16,-1,0
  1683.5    0.04       0  1954.5   0.013       0  1970.2    0.04       0
  3445.5    0.05       0  3541.0    0.04       0  3659.5   0.013       0
  3782.1    0.04       0  4800.4    0.12       0  4956.9    0.05       0
  4983.1    0.12       0  5214.7    0.05       0  5215.8    0.12       0
  6291.7    0.05       0  6292.5    0.12       0  6424.1    0.05       0
  6577.9    0.12       0
Bank Sta=4956.9,4983.1
Exp/Cntr=0.3,0.1

Type RM Length L Ch R = 1,46099,892,892,892
BEGIN DESCRIPTION:
Mapping XS 20644017
END DESCRIPTION:
XS GIS Cut Line= 4
      2545850.57     13601517.86      2543753.33     13600892.85
      2541551.94     13600920.63      2540239.71     13601205.29
#Sta/Elev= 30
  1233.2  280.05  1433.9  264.17  1687.7  251.75  1896.4  242.64  2072.6  240.80
  2102.9  240.48  2585.1  234.36  3202.7  216.65  3293.3  214.79  3888.9  210.83
  4085.7  211.54  4105.9  211.58  4791.1  212.99  4871.2  212.28  4960.0  211.17
  4966.9  208.06  4967.4  207.56  4993.1  208.06  5050.0  212.07  5180.1  214.64
  5220.1  212.31  5339.3  216.37  5790.3  231.79  5957.7  237.99  6167.7  238.94
  6201.9  239.30  6471.6  243.31  6572.8  246.48  6588.5  246.69  6965.9  263.28
#Mann=19,-1,0
  1233.2    0.05       0  2072.6    0.03       0  2102.9    0.04       0
  3202.7   0.013       0  3293.3    0.04       0  3888.9    0.05       0
  4085.7    0.12       0  4105.9   0.013       0  4791.1    0.04       0
  4871.2    0.12       0  4966.9    0.05       0  4993.1    0.12       0
  5339.3    0.04       0  5790.3    0.12       0  6167.7    0.04       0
  6201.9    0.12       0  6471.6    0.05       0  6572.8    0.12       0
  6588.5    0.05       0
Bank Sta=4966.9,4993.1
Exp/Cntr=0.3,0.1

Type RM Length L Ch R = 1,45207,590,590,590
BEGIN DESCRIPTION:
Mapping XS a79eac95
END DESCRIPTION:
XS GIS Cut Line= 4
      2545308.93     13600497.04      2543815.83     13599878.96
      2542454.71     13599990.07      2540301.93     13600628.97
#Sta/Elev= 30
  1202.5  250.05  1352.2  251.44  1509.4  248.70  1776.0  238.76  1979.9  230.89
  2058.4  225.50  2211.1  219.36  2302.2  220.07  2407.5  223.70  2586.9  226.09
  3030.0  210.28  3233.8  208.98  3489.4  210.81  3694.4  214.09  4113.8  213.34
  4218.1  213.37  4421.0  212.85  4850.9  210.13  4997.5  208.81  5012.2  206.48
  5012.7  205.98  5038.7  206.48  5058.7  209.67  5279.6  214.00  5483.8  216.20
  5758.9  223.30  5916.5  230.08  6064.3  238.34  6195.7  244.60  6429.7  253.68
#Mann=20,-1,0
  1202.5    0.04       0  1509.4   0.013       0  1776.0    0.04       0
  2058.4    0.04       0  2302.2    0.04       0  2407.5    0.05       0
  2586.9    0.12       0  3233.8    0.12       0  3489.4    0.03       0
  4113.8    0.05       0  4218.1    0.05       0  4421.0    0.12       0
  4850.9     0.1       0  5012.2    0.05       0  5038.7     0.1       0
  5279.6   0.013       0  5483.8    0.12       0  5916.5    0.05       0
  6064.3    0.12       0  6195.7    0.05       0
Bank Sta=5012.2,5038.7
Exp/Cntr=0.3,0.1

Type RM Length L Ch R = 1,44617,574,574,574
BEGIN DESCRIPTION:
Mapping XS 0238a417
END DESCRIPTION:
XS GIS Cut Line= 4
      2545343.64     13599823.43      2543906.10     13599149.80
      2540871.38     13599920.63      2540281.11     13600483.13
#Sta/Elev= 30
   689.7  248.62   783.3  245.93   862.4  243.97  1019.5  241.09  1146.0  233.76
  1242.9  235.17  1466.4  231.58  1626.9  228.06  1970.6  243.56  1976.9  243.53
  2692.0  222.21  2750.7  219.23  2971.7  208.05  3053.6  207.48  3662.6  211.88
  4348.4  211.74  4857.8  207.44  4981.6  210.10  4990.2  206.82  4990.7  206.32
  5016.7  206.82  5044.4  209.48  5401.9  211.11  5597.2  216.79  5736.0  222.93
  5851.5  228.86  5874.7  230.22  5991.1  237.06  6007.1  238.53  6223.7  247.15
#Mann=17,-1,0
   689.7    0.05       0   783.3    0.03       0   862.4    0.04       0
  1466.4    0.12       0  1970.6    0.05       0  1976.9    0.12       0
  2692.0    0.05       0  2750.7    0.12       0  4990.2    0.05       0
  5016.7    0.12       0  5401.9     0.1       0  5597.2   0.013       0
  5736.0    0.05       0  5851.5    0.12       0  5874.7    0.05       0
  5991.1    0.12       0  6007.1    0.05       0
Bank Sta=4990.2,5016.7
Exp/Cntr=0.3,0.1

Type RM Length L Ch R = 1,44043,481,481,481
BEGIN DESCRIPTION:
Mapping XS f242d962
END DESCRIPTION:
XS GIS Cut Line= 4
      2543767.23     13598406.73      2542107.49     13599219.24
      2540801.94     13599309.52      2539983.18     13600468.21
#Sta/Elev= 30
  2317.6  234.81  2434.2  230.24  2448.8  229.74  2533.6  226.93  2966.6  224.58
  3186.1  229.16  3394.3  213.56  3567.1  207.12  4148.1  209.76  4589.0  207.09
  4949.9  208.71  4976.8  204.60  4977.3  204.10  5003.3  204.60  5009.3  205.13
  5045.7  208.66  5108.1  208.39  5217.0  207.99  5538.6  208.15  5656.9  209.02
  5703.9  209.61  5719.9  205.99  5757.4  205.60  5770.4  206.12  5776.5  209.35
  6170.6  216.77  6292.3  220.13  6351.2  223.79  6581.3  232.33  6893.0  236.83
#Mann=17,-1,0
  2317.6    0.04       0  2434.2    0.12       0  2448.8    0.04       0
  2533.6    0.12       0  4976.8    0.05       0  5003.3    0.12       0
  5009.3     0.1       0  5108.1    0.05       0  5217.0    0.12       0
  5538.6     0.1       0  5656.9    0.05       0  5703.9     0.1       0
  5757.4    0.12       0  6170.6    0.05       0  6292.3   0.013       0
  6351.2    0.12       0  6581.3    0.05       0
Bank Sta=4976.8,5003.3
Exp/Cntr=0.3,0.1

Type RM Length L Ch R = 1,43562,816,816,816
BEGIN DESCRIPTION:
Mapping XS e7709f23
END DESCRIPTION:
XS GIS Cut Line= 4
      2543565.85     13598233.12      2542114.44     13598712.30
      2540635.27     13598941.46      2539149.94     13599296.29
#Sta/Elev= 30
  2660.0  236.50  2818.0  236.96  2878.0  237.79  2988.9  240.85  3199.9  239.27
  3377.0  240.56  3610.5  236.99  3714.0  231.06  3800.9  220.45  3890.9  219.02
  4031.8  212.68  4182.3  208.98  4235.1  208.55  4504.6  207.46  4754.6  207.63
  4983.8  204.18  4984.3  203.68  5011.1  204.18  5068.3  206.24  5090.7  204.51
  5134.9  207.63  6125.4  206.38  6160.3  206.64  6237.0  206.31  6368.4  211.16
  6584.0  223.63  6710.2  233.29  6981.0  247.25  7073.5  246.52  7212.4  238.99
#Mann=14,-1,0
  2660.0    0.04       0  2818.0    0.12       0  2878.0    0.05       0
  2988.9    0.04       0  3199.9    0.12       0  4031.8    0.05       0
  4182.3     0.1       0  4235.1    0.12       0  4504.6     0.1       0
  4983.8    0.05       0  5011.1     0.1       0  5134.9    0.12       0
  6125.4     0.1       0  6160.3    0.12       0
Bank Sta=4983.8,5011.1
Exp/Cntr=0.3,0.1

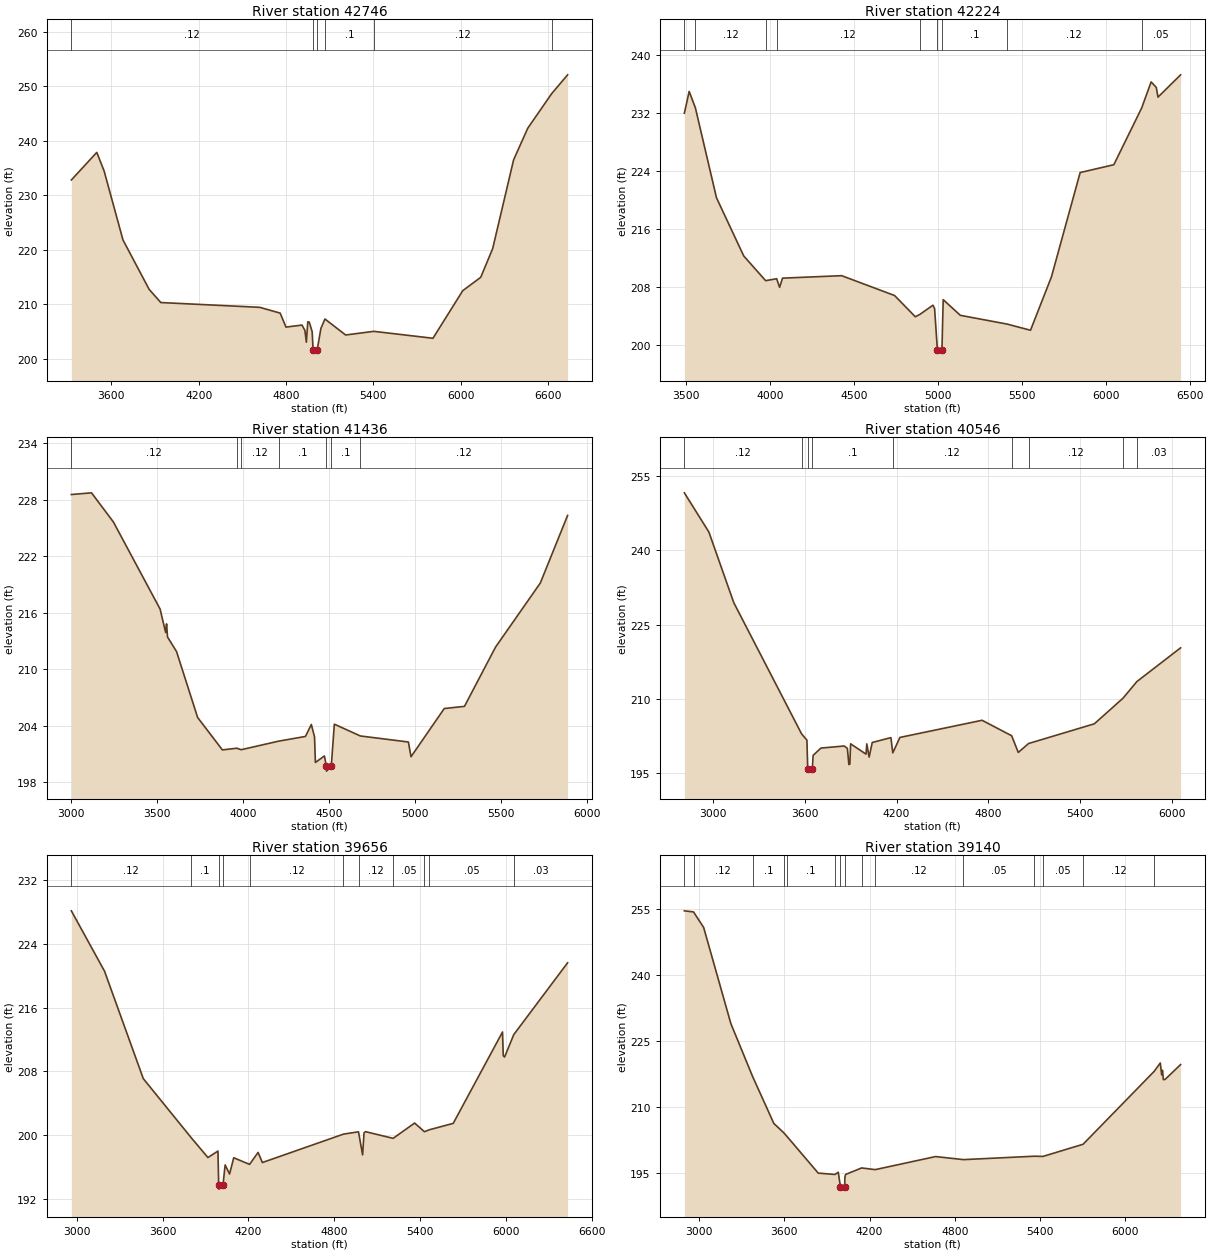
Type RM Length L Ch R = 1,42746,522,522,522
BEGIN DESCRIPTION:
Mapping XS 3ef9c985
END DESCRIPTION:
XS GIS Cut Line= 4
      2542599.56     13598257.13      2541696.79     13598222.41
      2540082.21     13598265.81      2539214.16     13598474.15
#Sta/Elev= 30
  3324.6  232.81  3499.3  237.87  3549.3  234.51  3679.4  221.80  3859.6  212.71
  3939.6  210.30  4620.0  209.42  4760.0  208.36  4800.0  205.79  4910.1  206.16
  4930.1  205.18  4940.1  203.02  4950.1  206.77  4960.1  206.70  4980.1  204.94
  4986.5  201.51  4987.0  201.01  5013.8  201.51  5040.1  205.55  5067.8  207.28
  5210.2  204.34  5403.6  205.01  5810.4  203.74  6015.2  212.48  6138.6  214.93
  6220.8  220.20  6364.8  236.51  6461.8  242.30  6625.4  248.63  6735.9  252.12
#Mann=6,-1,0
  3324.6    0.12       0  4986.5    0.05       0  5013.8    0.12       0
  5067.8     0.1       0  5403.6    0.12       0  6625.4    0.05       0
Bank Sta=4986.5,5013.8
Exp/Cntr=0.3,0.1

Type RM Length L Ch R = 1,42224,788,788,788
BEGIN DESCRIPTION:
IRISH CREEK 78.0
END DESCRIPTION:
XS GIS Cut Line= 4
      2542443.29     13598196.36      2541714.15     13598074.84
      2541236.72     13597797.06      2539613.50     13597458.53
#Sta/Elev= 30
  3491.9  231.95  3520.6  234.97  3557.7  232.68  3682.8  220.28  3845.0  212.23
  3975.1  208.82  4040.7  209.09  4057.9  207.90  4075.6  209.17  4426.8  209.51
  4741.4  206.77  4864.4  203.84  4891.1  204.15  4969.6  205.43  4979.3  204.98
  4995.8  199.31  4996.3  198.81  5023.1  199.31  5030.4  206.20  5132.5  204.03
  5408.8  202.83  5549.5  201.97  5673.9  209.35  5844.6  223.76  6044.7  224.84
  6210.4  232.69  6266.4  236.28  6297.1  235.52  6307.3  234.18  6441.6  237.26
#Mann=9,-1,0
  3491.9    0.05       0  3557.7    0.12       0  3975.1    0.05       0
  4040.7    0.12       0  4891.1     0.1       0  4995.8    0.05       0
  5023.1     0.1       0  5408.8    0.12       0  6210.4    0.05       0
Bank Sta=4995.8,5023.1
Exp/Cntr=0.3,0.1

Type RM Length L Ch R = 1,41436,890,890,890
BEGIN DESCRIPTION:
IRISH CREEK 77.0
END DESCRIPTION:
XS GIS Cut Line= 4
      2542718.58     13597163.69      2542113.46     13597354.36
      2540585.68     13597067.90      2539906.12     13597226.18
#Sta/Elev= 30
  3003.1  228.54  3120.4  228.72  3248.0  225.62  3519.3  216.39  3551.7  213.90
  3556.9  214.82  3562.5  213.43  3615.0  211.88  3737.7  204.89  3881.7  201.45
  3965.7  201.63  3990.6  201.47  4209.2  202.38  4365.0  202.88  4399.0  204.15
  4417.6  202.84  4422.7  200.12  4475.1  200.81  4486.7  199.70  4487.2  199.20
  4514.9  199.70  4532.9  204.18  4684.3  202.93  4963.6  202.29  4979.0  200.73
  5172.3  205.84  5289.8  206.07  5470.4  212.35  5730.9  219.15  5889.7  226.32
#Mann=7,-1,0
  3003.1    0.12       0  3965.7     0.1       0  3990.6    0.12       0
  4209.2     0.1       0  4486.7    0.05       0  4514.9     0.1       0
  4684.3    0.12       0
Bank Sta=4486.7,4514.9
Exp/Cntr=0.3,0.1

Type RM Length L Ch R = 1,40546,890,890,890
BEGIN DESCRIPTION:
IRISH CREEK 76.0
END DESCRIPTION:
XS GIS Cut Line= 3
      2543152.81     13596817.31      2541396.59     13596491.89
      2540049.20     13595934.35
#Sta/Elev= 30
  2812.9  251.58  2973.4  243.66  3136.1  229.41  3579.5  202.93  3614.1  201.68
  3619.5  195.92  3620.0  195.42  3649.4  195.92  3654.8  198.60  3705.7  200.07
  3858.2  200.49  3878.5  200.03  3888.7  196.74  3894.8  196.83  3899.9  200.93
  4000.6  198.85  4005.7  200.92  4020.9  198.26  4041.3  201.20  4163.3  202.18
  4175.6  199.11  4222.2  202.22  4759.3  205.68  4952.7  202.56  4996.0  199.19
  5063.3  200.99  5493.4  204.97  5680.2  210.12  5771.6  213.50  6057.2  220.30
#Mann=9,-1,0
  2812.9    0.12       0  3579.5     0.1       0  3619.5    0.05       0
  3649.4     0.1       0  4175.6    0.12       0  4952.7    0.05       0
  5063.3    0.12       0  5680.2    0.05       0  5771.6    0.03       0
Bank Sta=3619.5,3649.4
Exp/Cntr=0.3,0.1

Type RM Length L Ch R = 1,39656,516,516,516
BEGIN DESCRIPTION:
IRISH CREEK 75.0
END DESCRIPTION:
XS GIS Cut Line= 4
      2543406.09     13595635.91      2542308.39     13595542.10
      2541031.64     13595595.46      2539979.54     13595877.46
#Sta/Elev= 30
  2962.5  228.16  3194.4  220.58  3465.4  207.08  3800.8  199.65  3917.1  197.17
  3987.3  197.98  3992.4  193.70  3992.9  193.20  4022.3  193.70  4037.5  196.24
  4068.4  195.10  4097.6  197.14  4208.2  196.31  4267.8  197.81  4297.8  196.54
  4864.8  200.11  4969.7  200.40  4998.4  197.50  5008.4  200.27  5018.4  200.42
  5211.9  199.58  5362.0  201.50  5430.8  200.41  5463.4  200.65  5631.8  201.46
  5976.4  212.94  5981.6  209.95  5990.8  209.79  6055.0  212.61  6431.3  221.63
#Mann=11,-1,0
  2962.5    0.12       0  3800.8     0.1       0  3992.4    0.05       0
  4022.3     0.1       0  4208.2    0.12       0  4864.8    0.05       0
  4969.7    0.12       0  5211.9    0.05       0  5430.8    0.12       0
  5463.4    0.05       0  6055.0    0.03       0
Bank Sta=3992.4,4022.3
Exp/Cntr=0.3,0.1

Type RM Length L Ch R = 1,39140,575,575,575
BEGIN DESCRIPTION:
IRISH CREEK 73.0
END DESCRIPTION:
XS GIS Cut Line= 3
      2543329.72     13594594.24      2542138.41     13594749.10
      2540044.25     13595682.26
#Sta/Elev= 30
  2896.2  254.68  2960.8  254.43  3032.1  250.89  3223.7  228.98  3376.8  216.93
  3526.2  206.24  3597.1  204.08  3620.1  203.23  3838.8  194.92  3956.4  194.61
  3980.0  195.11  3995.2  191.77  3995.7  191.27  4025.2  191.77  4026.1  193.84
  4031.2  194.61  4144.7  196.10  4239.9  195.71  4665.0  198.69  4861.5  197.99
  5360.6  198.77  5420.9  198.72  5703.4  201.49  6204.3  218.11  6247.1  220.01
  6257.2  217.29  6262.6  218.35  6268.9  216.23  6279.9  216.23  6390.2  219.65
#Mann=15,-1,0
  2896.2   0.013       0  2960.8    0.12       0  3376.8     0.1       0
  3597.1    0.12       0  3620.1     0.1       0  3956.4   0.013       0
  3995.2    0.05       0  4025.2   0.013       0  4144.7     0.1       0
  4239.9    0.12       0  4861.5    0.05       0  5360.6    0.12       0
  5420.9    0.05       0  5703.4    0.12       0  6204.3    0.05       0
Bank Sta=3995.2,4025.2
Exp/Cntr=0.3,0.1

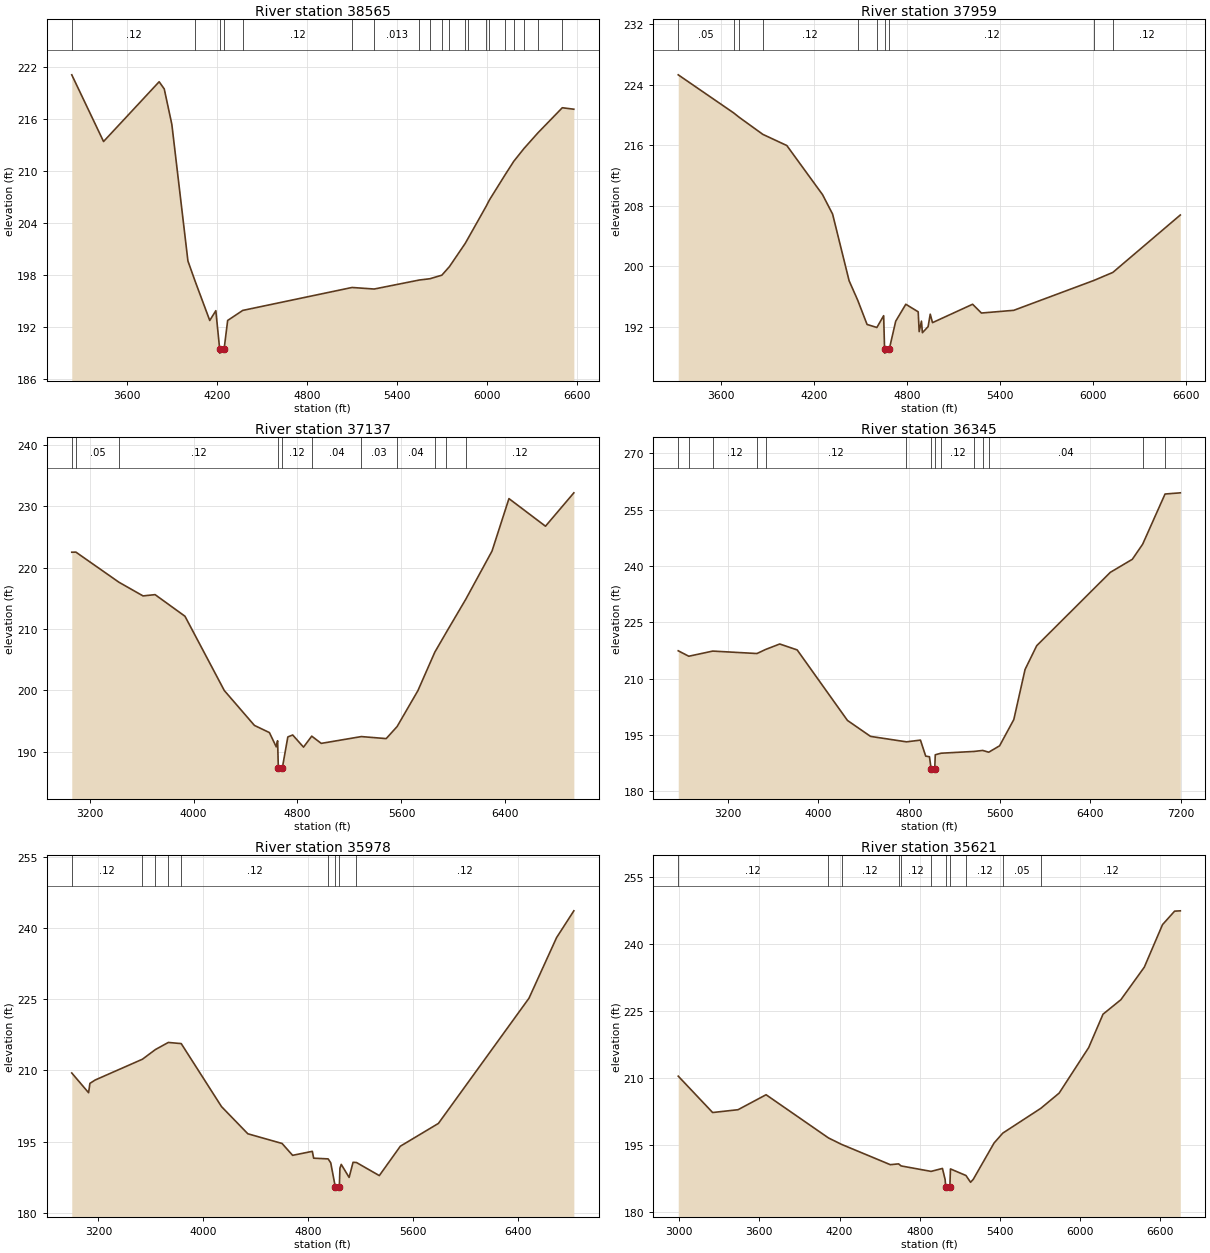
Type RM Length L Ch R = 1,38565,606,606,606
BEGIN DESCRIPTION:
Mapping XS a0a52335
END DESCRIPTION:
XS GIS Cut Line= 4
      2542864.44     13593948.41      2541857.49     13594108.13
      2540668.50     13595079.78      2540023.72     13595545.27
#Sta/Elev= 30
  3230.0  221.07  3442.1  213.37  3813.1  220.27  3847.1  219.44  3897.7  215.36
  4005.1  199.58  4052.8  197.26  4150.8  192.71  4191.3  193.84  4216.8  189.44
  4217.3  188.94  4246.8  189.44  4270.2  192.71  4370.7  193.87  5100.3  196.52
  5248.0  196.34  5549.1  197.38  5620.3  197.53  5699.6  197.94  5750.3  198.93
  5855.1  201.60  5875.8  202.23  5995.3  205.90  6017.2  206.63  6123.5  209.58
  6179.2  211.08  6247.3  212.56  6341.2  214.38  6503.3  217.27  6580.3  217.10
#Mann=20,-1,0
  3230.0    0.12       0  4052.8     0.1       0  4216.8    0.05       0
  4246.8    0.12       0  4370.7    0.12       0  5100.3    0.05       0
  5248.0   0.013       0  5549.1    0.12       0  5620.3   0.013       0
  5699.6    0.05       0  5750.3   0.013       0  5855.1    0.12       0
  5875.8   0.013       0  5995.3    0.12       0  6017.2   0.013       0
  6123.5    0.12       0  6179.2   0.013       0  6247.3    0.12       0
  6341.2   0.013       0  6503.3   0.013       0
Bank Sta=4216.8,4246.8
Exp/Cntr=0.3,0.1

Type RM Length L Ch R = 1,37959,822,822,822
BEGIN DESCRIPTION:
Mapping XS 866031ad
END DESCRIPTION:
XS GIS Cut Line= 4
      2542954.73     13593670.63      2541885.27     13593691.46
      2540538.05     13594649.80      2540204.69     13595038.72
#Sta/Elev= 30
  3325.7  225.32  3682.6  220.29  3720.1  219.68  3870.9  217.45  4025.6  215.97
  4255.6  209.48  4320.4  206.91  4426.9  198.09  4482.5  195.51  4542.5  192.32
  4605.6  191.92  4649.4  193.48  4655.3  189.03  4655.8  188.53  4685.3  189.03
  4727.0  192.75  4792.1  194.99  4872.0  193.99  4878.2  191.37  4892.9  192.76
  4899.1  191.23  4935.7  192.03  4949.5  193.68  4964.2  192.56  5222.5  194.99
  5279.3  193.83  5487.9  194.19  6004.2  198.14  6126.2  199.20  6560.9  206.79
#Mann=10,-1,0
  3325.7    0.05       0  3682.6    0.12       0  3720.1    0.05       0
  3870.9    0.12       0  4482.5     0.1       0  4605.6    0.12       0
  4655.3    0.05       0  4685.3    0.12       0  6004.2    0.05       0
  6126.2    0.12       0
Bank Sta=4655.3,4685.3
Exp/Cntr=0.3,0.1

Type RM Length L Ch R = 1,37137,792,792,792
BEGIN DESCRIPTION:
Mapping XS d7994ba6
END DESCRIPTION:
XS GIS Cut Line= 4
      2542899.20     13593517.86      2541739.44     13593247.02
      2540364.44     13593684.52      2539136.09     13593740.04
#Sta/Elev= 30
  3063.1  222.50  3094.8  222.52  3426.2  217.61  3611.7  215.38  3704.1  215.59
  3934.2  212.07  4237.0  199.96  4468.6  194.28  4584.0  193.11  4636.5  190.79
  4647.0  191.78  4652.7  187.33  4653.2  186.83  4683.2  187.33  4725.7  192.40
  4763.2  192.72  4846.4  190.74  4909.7  192.53  4982.8  191.35  5291.5  192.46
  5482.7  192.13  5566.8  194.10  5726.5  199.94  5856.6  206.21  5945.8  209.47
  6095.4  214.85  6297.0  222.69  6427.2  231.24  6708.4  226.74  6926.6  232.18
#Mann=11,-1,0
  3063.1    0.12       0  3094.8    0.05       0  3426.2    0.12       0
  4652.7    0.04       0  4683.2    0.12       0  4909.7    0.04       0
  5291.5    0.03       0  5566.8    0.04       0  5856.6    0.03       0
  5945.8    0.04       0  6095.4    0.12       0
Bank Sta=4652.7,4683.2
Exp/Cntr=0.3,0.1

Type RM Length L Ch R = 1,36345,367,367,367
BEGIN DESCRIPTION:
IRISH CREEK 66.0
END DESCRIPTION:
XS GIS Cut Line= 3
      2543169.97     13593233.13      2540974.60     13592800.00
      2538843.58     13593316.47
#Sta/Elev= 30
  2762.3  217.39  2855.5  215.94  3066.7  217.31  3457.0  216.66  3533.1  217.74
  3658.0  219.20  3811.9  217.62  4255.5  198.84  4459.4  194.59  4776.4  193.14
  4899.7  193.60  4945.9  189.34  4979.2  189.17  4994.3  185.84  4994.8  185.34
  5025.4  185.84  5030.4  189.69  5081.0  190.11  5374.6  190.59  5449.1  190.85
  5502.2  190.38  5597.9  192.08  5723.4  199.07  5822.7  212.41  5925.6  218.75
  6574.9  238.28  6769.4  241.76  6860.3  245.77  7058.0  259.14  7192.7  259.46
#Mann=14,-1,0
  2762.3    0.12       0  2855.5    0.05       0  3066.7    0.12       0
  3457.0    0.05       0  3533.1    0.12       0  4776.4     0.1       0
  4994.3    0.05       0  5025.4     0.1       0  5081.0    0.12       0
  5374.6    0.04       0  5449.1    0.05       0  5502.2    0.04       0
  6860.3    0.05       0  7058.0    0.12       0
Bank Sta=4994.3,5025.4
Exp/Cntr=0.3,0.1

Type RM Length L Ch R = 1,35978,357,357,357
BEGIN DESCRIPTION:
Mapping XS 763345e3
END DESCRIPTION:
XS GIS Cut Line= 3
      2543072.82     13592608.13      2541142.21     13592469.24
      2539253.31     13592497.02
#Sta/Elev= 30
  2997.3  209.45  3125.4  205.29  3135.5  207.26  3175.6  207.97  3535.8  212.35
  3634.2  214.38  3732.7  215.88  3831.1  215.64  4138.1  202.36  4338.6  196.64
  4599.2  194.60  4679.5  192.10  4829.8  192.94  4839.9  191.50  4950.3  191.35
  4970.1  190.52  5004.6  185.48  5005.1  184.98  5035.7  185.48  5040.1  189.38
  5050.1  190.19  5110.1  187.45  5140.1  190.63  5165.9  190.59  5340.1  187.83
  5500.2  194.02  5790.2  198.82  6480.3  225.20  6690.3  237.96  6822.0  243.61
#Mann=9,-1,0
  2997.3    0.12       0  3535.8    0.05       0  3634.2    0.12       0
  3732.7    0.05       0  3831.1    0.12       0  4950.3     0.1       0
  5004.6    0.05       0  5035.7     0.1       0  5165.9    0.12       0
Bank Sta=5004.6,5035.7
Exp/Cntr=0.3,0.1

Type RM Length L Ch R = 1,35621,662,662,662
BEGIN DESCRIPTION:
Mapping XS b7823cc9
END DESCRIPTION:
XS GIS Cut Line= 3
      2542982.48     13592191.46      2540926.94     13592149.80
      2539232.48     13592316.46
#Sta/Elev= 30
  2992.4  210.44  3249.9  202.30  3440.0  202.93  3650.0  206.28  4116.8  196.62
  4215.1  195.17  4580.2  190.63  4642.0  190.81  4661.0  190.35  4885.3  189.13
  4970.3  189.79  4990.3  187.32  4994.7  185.66  4995.2  185.16  5025.8  185.66
  5030.3  189.68  5146.3  188.21  5180.9  186.69  5201.0  187.35  5356.8  195.48
  5422.4  197.70  5706.9  203.24  5844.1  206.65  6065.2  216.84  6172.4  224.30
  6306.3  227.55  6481.4  234.82  6617.8  244.34  6708.3  247.36  6751.0  247.43
#Mann=11,-1,0
  2992.4    0.12       0  4116.8    0.05       0  4215.1    0.12       0
  4642.0    0.05       0  4661.0    0.12       0  4885.3     0.1       0
  4994.7    0.05       0  5025.8     0.1       0  5146.3    0.12       0
  5422.4    0.05       0  5706.9    0.12       0
Bank Sta=4994.7,5025.8
Exp/Cntr=0.3,0.1

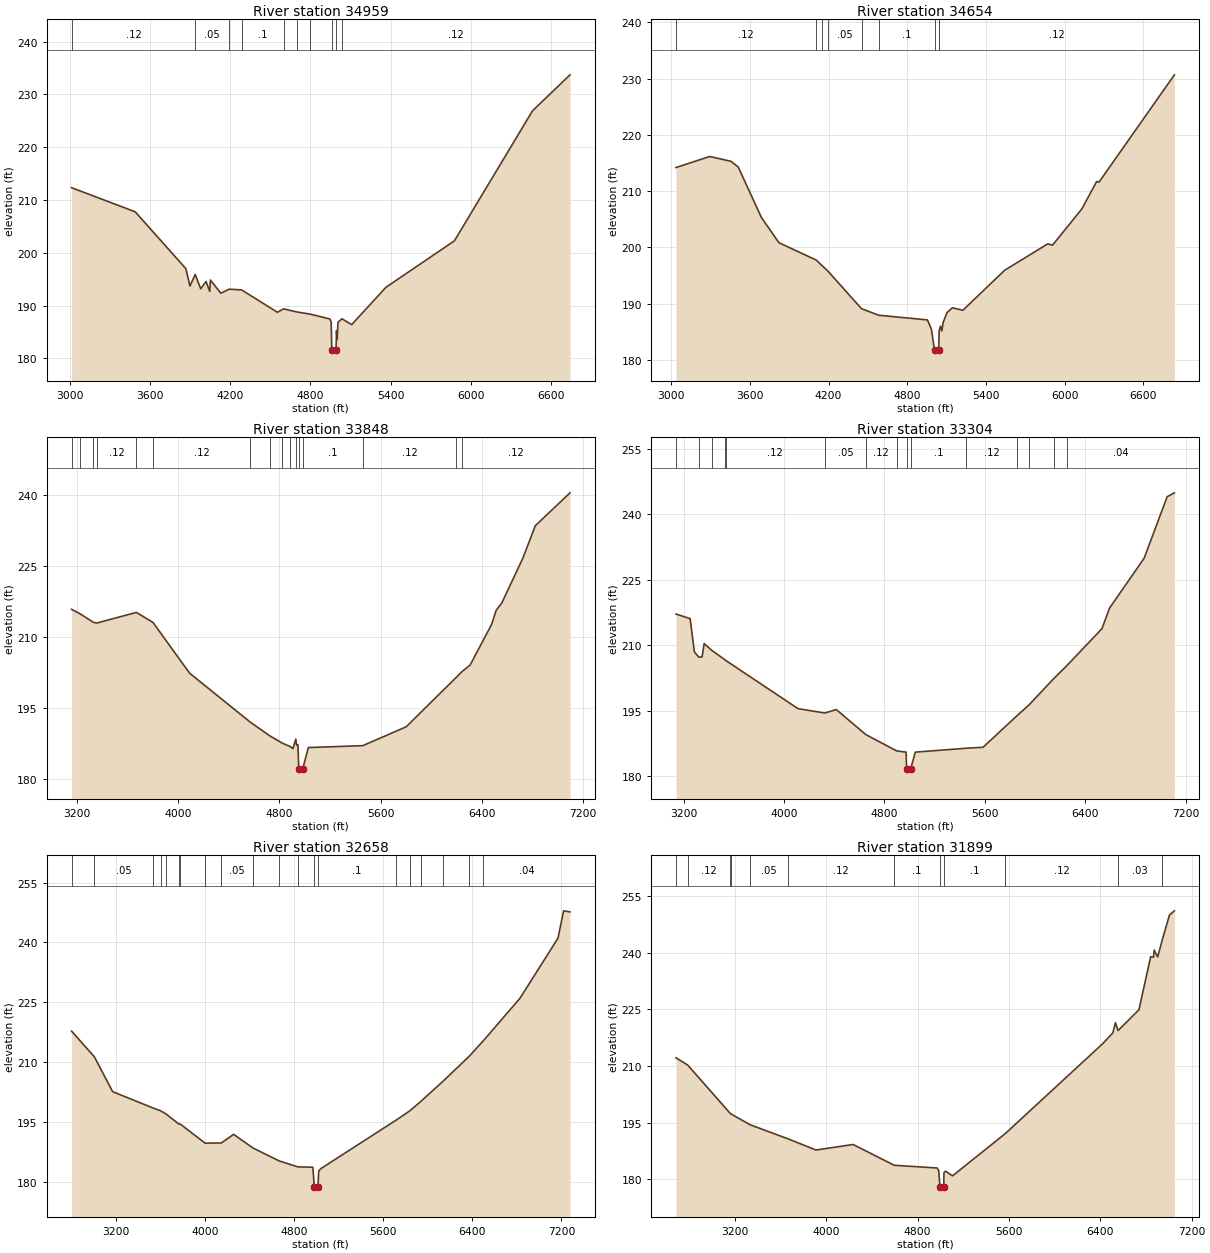
Type RM Length L Ch R = 1,34959,305,305,305
BEGIN DESCRIPTION:
Mapping XS 9ecffc53
END DESCRIPTION:
XS GIS Cut Line= 3
      2542954.68     13591920.63      2541017.21     13591712.30
      2539281.07     13592094.25
#Sta/Elev= 30
  3015.6  212.32  3491.1  207.76  3870.2  196.98  3900.4  193.70  3940.0  195.89
  3980.8  193.18  4021.0  194.55  4048.3  192.69  4053.3  194.83  4131.7  192.34
  4193.9  193.10  4286.3  192.97  4554.1  188.73  4601.1  189.37  4699.8  188.79
  4798.4  188.38  4946.3  187.46  4956.4  186.84  4961.0  181.49  4961.5  180.99
  4992.4  181.49  4996.1  185.25  5001.2  183.57  5007.5  186.84  5036.5  187.50
  5109.9  186.39  5365.8  193.46  5877.8  202.26  6461.4  226.88  6741.9  233.70
#Mann=10,-1,0
  3015.6    0.12       0  3940.0    0.05       0  4193.9    0.12       0
  4286.3     0.1       0  4601.1    0.12       0  4699.8    0.05       0
  4798.4     0.1       0  4961.0    0.05       0  4992.4     0.1       0
  5036.5    0.12       0
Bank Sta=4961,4992.4
Exp/Cntr=0.3,0.1

Type RM Length L Ch R = 1,34654,806,806,806
BEGIN DESCRIPTION:
Mapping XS 5989e870
END DESCRIPTION:
XS GIS Cut Line= 4
      2542878.37     13591719.25      2541281.10     13591448.41
      2540413.05     13591483.13      2539204.79     13591990.04
#Sta/Elev= 30
  3036.7  214.18  3293.7  216.15  3456.0  215.29  3511.3  214.27  3687.2  205.33
  3821.1  200.82  4107.2  197.71  4146.6  196.80  4192.4  195.83  4450.9  189.08
  4582.0  187.92  4953.1  187.09  4983.1  185.48  5007.4  181.68  5007.9  181.18
  5038.9  181.68  5042.9  185.16  5053.2  185.98  5063.2  185.12  5073.2  186.64
  5103.2  188.41  5143.3  189.24  5223.3  188.80  5541.5  195.91  5870.4  200.61
  5906.8  200.38  6130.7  206.84  6242.9  211.69  6260.8  211.58  6835.8  230.67
#Mann=9,-1,0
  3036.7    0.12       0  4107.2    0.05       0  4146.6    0.12       0
  4192.4    0.05       0  4450.9    0.12       0  4582.0     0.1       0
  5007.4    0.05       0  5038.9     0.1       0  5042.9    0.12       0
Bank Sta=5007.4,5038.9
Exp/Cntr=0.3,0.1

Type RM Length L Ch R = 1,33848,544,544,544
BEGIN DESCRIPTION:
Mapping XS c4197ed8
END DESCRIPTION:
XS GIS Cut Line= 3
      2543114.47     13591622.04      2541489.44     13590885.91
      2539399.62     13590358.25
#Sta/Elev= 30
  3156.8  215.83  3222.3  214.91  3328.9  213.08  3355.4  212.92  3668.6  215.18
  3800.1  213.06  4089.4  202.32  4568.1  191.98  4721.6  189.09  4821.8  187.52
  4882.8  186.81  4906.6  186.36  4928.4  188.36  4935.5  187.10  4945.7  187.17
  4952.2  182.09  4952.7  181.59  4983.9  182.09  5027.9  186.58  5458.6  186.98
  5801.4  190.97  6196.2  201.41  6238.7  202.56  6306.8  204.04  6476.6  212.64
  6512.5  215.60  6558.7  217.25  6723.0  226.63  6822.5  233.54  7096.2  240.48
#Mann=16,-1,0
  3156.8    0.05       0  3222.3    0.12       0  3328.9    0.05       0
  3355.4    0.12       0  3668.6    0.05       0  3800.1    0.12       0
  4568.1    0.05       0  4721.6    0.12       0  4821.8    0.05       0
  4882.8    0.12       0  4928.4     0.1       0  4952.2    0.05       0
  4983.9     0.1       0  5458.6    0.12       0  6196.2    0.05       0
  6238.7    0.12       0
Bank Sta=4952.2,4983.9
Exp/Cntr=0.3,0.1

Type RM Length L Ch R = 1,33304,646,646,646
BEGIN DESCRIPTION:
IRISH CREEK 62.0
END DESCRIPTION:
XS GIS Cut Line= 3
      2543224.97     13591224.99      2541575.40     13590375.17
      2539498.22     13589976.54
#Sta/Elev= 30
  3139.7  217.16  3252.2  216.12  3286.6  208.45  3321.3  207.30  3347.4  207.28
  3364.0  210.38  3426.0  208.81  3530.9  206.65  3535.1  206.54  4112.0  195.46
  4324.9  194.46  4416.7  195.25  4652.9  189.50  4898.1  185.77  4973.3  185.49
  4976.6  181.63  4977.1  181.13  5008.9  181.63  5046.6  185.49  5451.9  186.38
  5586.3  186.61  5853.3  193.76  5952.9  196.34  6152.2  202.45  6251.8  205.28
  6533.3  213.81  6594.4  218.56  6869.3  229.97  7052.6  244.07  7110.4  244.97
#Mann=15,-1,0
  3139.7    0.05       0  3321.3   0.013       0  3426.0    0.12       0
  3530.9   0.013       0  3535.1    0.12       0  4324.9    0.05       0
  4652.9    0.12       0  4898.1     0.1       0  4976.6    0.05       0
  5008.9     0.1       0  5451.9    0.12       0  5853.3   0.013       0
  5952.9    0.04       0  6152.2    0.05       0  6251.8    0.04       0
Bank Sta=4976.6,5008.9
Exp/Cntr=0.3,0.1

Type RM Length L Ch R = 1,32658,759,759,759
BEGIN DESCRIPTION:
IRISH CREEK 61.0
END DESCRIPTION:
XS GIS Cut Line= 3
      2543489.44     13591003.97      2541674.86     13589759.94
      2539428.51     13589386.17
#Sta/Elev= 30
  2799.9  217.77  3004.8  211.33  3169.0  202.61  3531.3  198.53  3599.6  197.82
  3648.3  197.03  3765.3  194.47  3775.2  194.52  3999.3  189.71  4144.7  189.76
  4255.6  191.92  4427.3  188.53  4663.9  185.27  4831.3  183.77  4967.0  183.68
  4980.5  178.69  4981.1  178.19  5013.0  178.69  5020.1  182.74  5040.4  183.35
  5716.2  195.50  5838.5  197.82  5937.8  200.19  6136.3  205.22  6372.9  211.52
  6499.7  215.40  6828.5  226.05  7169.2  241.08  7219.9  247.93  7277.2  247.66
#Mann=20,-1,0
  2799.9    0.03       0  3004.8    0.05       0  3531.3   0.013       0
  3599.6    0.05       0  3648.3   0.013       0  3765.3    0.05       0
  3775.2    0.12       0  3999.3   0.013       0  4144.7    0.05       0
  4427.3    0.12       0  4663.9    0.12       0  4831.3     0.1       0
  4980.5    0.05       0  5013.0     0.1       0  5716.2    0.12       0
  5838.5   0.013       0  5937.8    0.12       0  6136.3    0.04       0
  6372.9    0.12       0  6499.7    0.04       0
Bank Sta=4980.5,5013
Exp/Cntr=0.3,0.1

Type RM Length L Ch R = 1,31899,800,800,800
BEGIN DESCRIPTION:
IRISH CREEK 60.0
END DESCRIPTION:
XS GIS Cut Line= 3
      2543621.35     13590802.54      2541945.38     13589155.16
      2539982.47     13588698.40
#Sta/Elev= 30
  2683.2  212.18  2785.7  210.26  3157.6  197.47  3163.5  197.33  3331.9  194.44
  3666.8  190.68  3909.3  187.74  4234.5  189.21  4594.9  183.70  4970.0  182.98
  4984.1  182.26  4996.2  177.88  4996.7  177.38  5028.7  177.88  5030.0  181.73
  5043.9  182.13  5105.5  180.91  5566.3  192.07  6419.2  215.88  6509.5  218.79
  6532.6  221.49  6555.2  219.39  6738.0  224.91  6840.7  238.96  6865.7  238.84
  6871.5  240.71  6902.3  238.90  6942.3  243.43  7004.9  249.99  7048.6  251.12
#Mann=12,-1,0
  2683.2    0.03       0  2785.7    0.12       0  3157.6    0.05       0
  3163.5    0.12       0  3331.9    0.05       0  3666.8    0.12       0
  4594.9     0.1       0  4996.2    0.05       0  5028.7     0.1       0
  5566.3    0.12       0  6555.2    0.03       0  6942.3   0.013       0
Bank Sta=4996.2,5028.7
Exp/Cntr=0.3,0.1