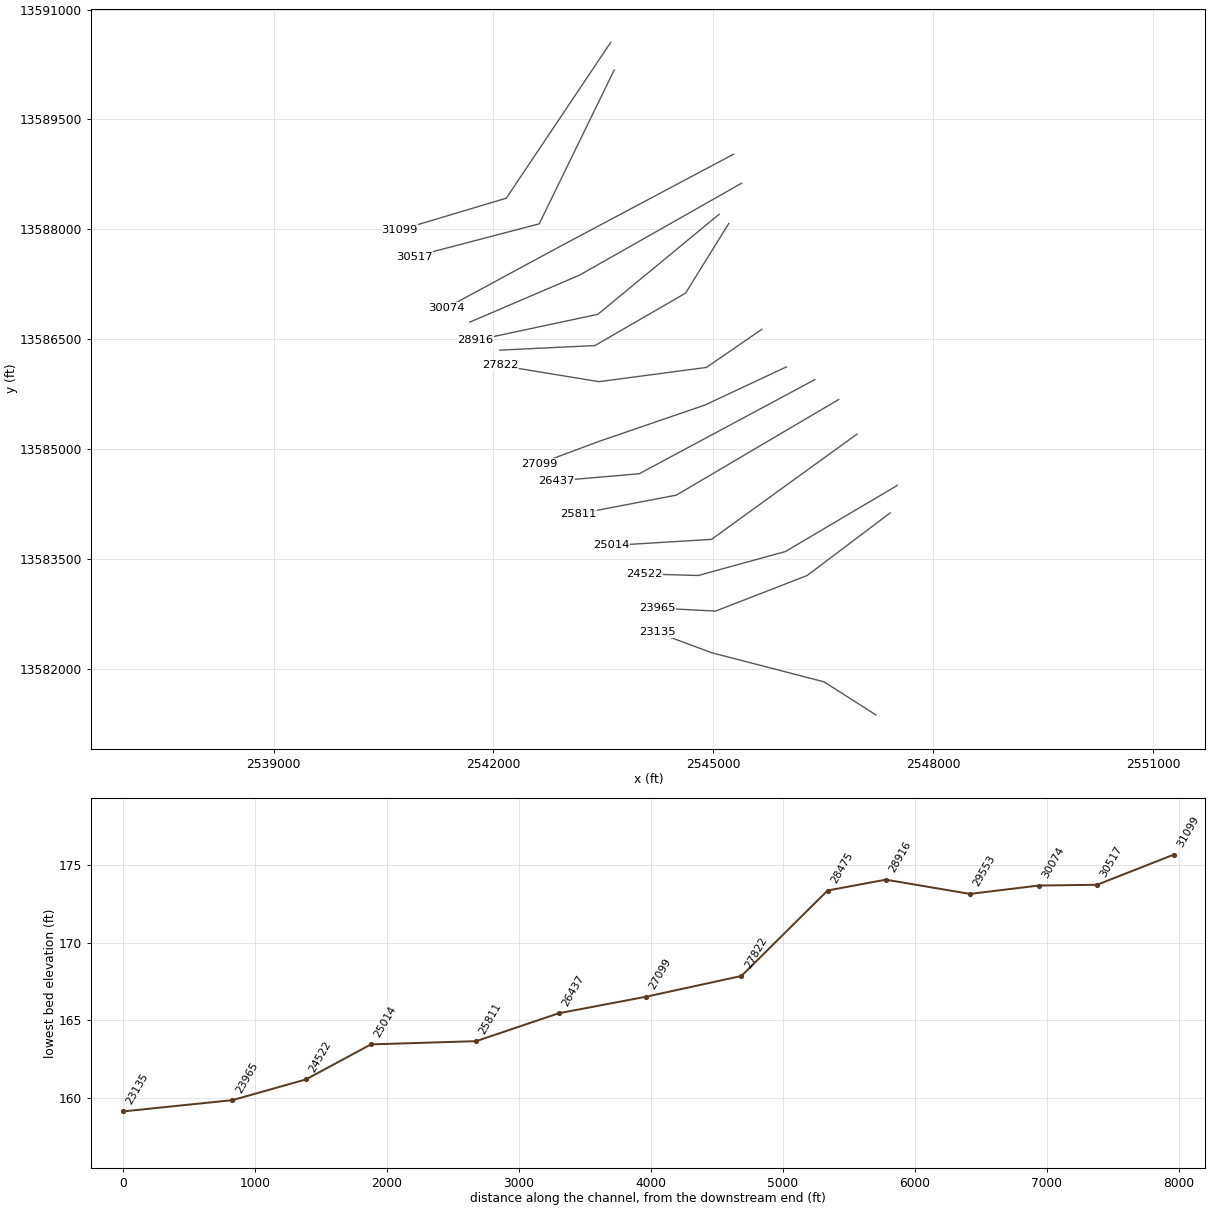
HEC-RAS study IRISH CREEK.prj: IRISH CREEK Base Level Engineering

--- IRISH CREEK.g01 (geometry) --- (continued)

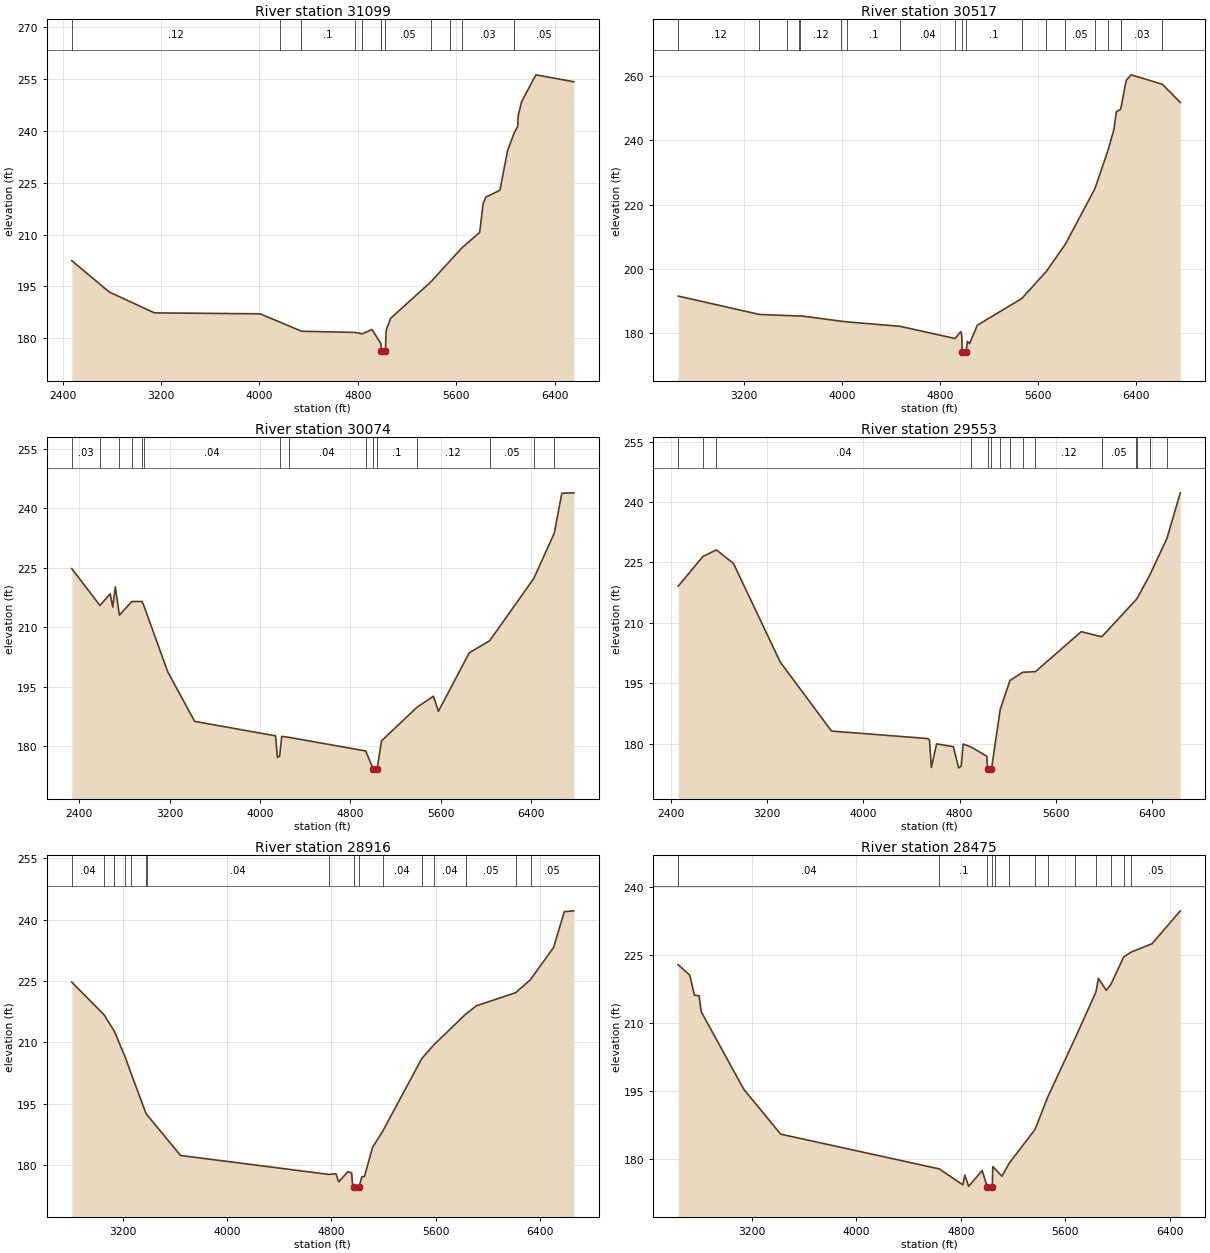
Type RM Length L Ch R = 1,31099,582,582,582
BEGIN DESCRIPTION:
IRISH CREEK 59.0
END DESCRIPTION:
XS GIS Cut Line= 3
      2543600.53     13590552.54      2542175.00     13588425.00
      2540719.29     13587990.28
#Sta/Elev= 30
  2474.7  202.44  2779.9  193.36  3146.1  187.34  4004.6  187.06  4166.7  184.67
  4341.6  182.02  4774.5  181.68  4835.8  181.27  4914.1  182.54  4987.7  178.37
  4990.8  176.19  4991.4  175.69  5023.5  176.19  5028.2  181.50  5032.7  182.69
  5067.0  185.80  5391.3  196.24  5547.0  202.32  5645.0  206.14  5789.7  210.62
  5817.6  218.93  5839.3  220.82  5954.1  222.81  6016.7  234.32  6069.3  239.32
  6098.3  241.25  6103.5  244.54  6131.4  248.53  6246.4  256.21  6554.9  254.20
#Mann=12,-1,0
  2474.7    0.12       0  4166.7    0.05       0  4341.6     0.1       0
  4774.5    0.04       0  4835.8     0.1       0  4987.7    0.05       0
  4990.8    0.05       0  5023.5    0.05       0  5391.3    0.12       0
  5547.0    0.05       0  5645.0    0.03       0  6069.3    0.05       0
Bank Sta=4990.8,5023.5
Exp/Cntr=0.3,0.1

Type RM Length L Ch R = 1,30517,443,443,443
BEGIN DESCRIPTION:
IRISH CREEK 58.0
END DESCRIPTION:
XS GIS Cut Line= 3
      2543649.16     13590177.57      2542625.00     13588075.00
      2540920.02     13587628.97
#Sta/Elev= 30
  2661.0  191.51  3324.3  185.79  3546.6  185.45  3646.4  185.32  3657.7  185.38
  3991.1  183.69  4041.9  183.46  4471.5  182.10  4922.3  178.29  4968.7  180.46
  4977.5  179.19  4980.5  174.24  4981.1  173.74  5013.4  174.24  5022.5  177.42
  5041.1  176.69  5103.4  182.41  5466.9  190.75  5668.8  199.25  5823.1  207.67
  6064.0  224.93  6173.4  237.13  6219.5  243.41  6239.7  248.95  6274.4  249.69
  6274.8  249.73  6320.5  258.76  6361.0  260.45  6615.9  257.49  6762.1  251.85
#Mann=19,-1,0
  2661.0    0.12       0  3324.3    0.05       0  3546.6    0.12       0
  3646.4    0.05       0  3657.7    0.12       0  3991.1    0.05       0
  4041.9     0.1       0  4471.5    0.04       0  4922.3     0.1       0
  4980.5    0.05       0  5013.4     0.1       0  5466.9    0.04       0
  5668.8    0.12       0  5823.1    0.05       0  6064.0    0.12       0
  6173.4    0.03       0  6274.4    0.05       0  6274.8    0.03       0
  6615.9    0.05       0
Bank Sta=4980.5,5013.4
Exp/Cntr=0.3,0.1

Type RM Length L Ch R = 1,30074,521,521,521
BEGIN DESCRIPTION:
IRISH CREEK 57.0
END DESCRIPTION:
XS GIS Cut Line= 3
      2545275.00     13589025.00      2542925.22     13587775.57
      2541358.71     13586928.23
#Sta/Elev= 30
  2334.1  224.81  2583.4  215.52  2673.9  218.44  2696.5  215.12  2719.2  220.21
  2755.6  213.08  2865.4  216.50  2956.7  216.52  2975.1  215.21  3183.5  198.75
  3421.4  186.25  4137.3  182.60  4153.6  177.13  4173.4  177.48  4191.5  182.46
  4253.3  182.23  4935.0  178.78  5001.9  174.19  5002.5  173.69  5034.9  174.19
  5075.5  181.35  5388.4  189.81  5534.1  192.60  5577.9  188.79  5850.9  203.56
  6032.2  206.63  6422.3  222.34  6603.2  233.77  6670.1  243.84  6776.4  243.95
#Mann=15,-1,0
  2334.1    0.03       0  2583.4    0.05       0  2755.6    0.03       0
  2865.4    0.05       0  2956.7    0.03       0  2975.1    0.04       0
  4173.4     0.1       0  4253.3    0.04       0  4935.0     0.1       0
  5001.9    0.05       0  5034.9     0.1       0  5388.4    0.12       0
  6032.2    0.05       0  6422.3    0.12       0  6603.2    0.05       0
Bank Sta=5001.9,5034.9
Exp/Cntr=0.3,0.1

Type RM Length L Ch R = 1,29553,637,637,637
BEGIN DESCRIPTION:
IRISH CREEK 56.0
END DESCRIPTION:
XS GIS Cut Line= 3
      2545385.28     13588628.97      2543175.00     13587375.00
      2541678.49     13586733.80
#Sta/Elev= 30
  2463.2  219.12  2669.0  226.51  2780.3  228.14  2922.4  224.73  3310.4  200.25
  3735.9  183.11  4533.5  181.25  4549.4  180.93  4565.2  174.06  4608.5  179.93
  4748.4  179.21  4791.7  173.93  4813.3  174.41  4829.2  179.89  4896.8  179.11
  5026.2  176.85  5031.4  173.65  5032.0  173.15  5064.4  173.65  5137.2  188.50
  5218.1  195.68  5323.8  197.71  5429.6  197.88  5809.6  207.80  5980.6  206.54
  6267.2  215.82  6275.5  216.17  6381.2  222.01  6520.5  230.92  6632.5  242.31
#Mann=15,-1,0
  2463.2    0.03       0  2669.0    0.05       0  2780.3    0.04       0
  4896.8     0.1       0  5031.4    0.05       0  5064.4     0.1       0
  5137.2    0.05       0  5218.1    0.12       0  5323.8    0.05       0
  5429.6    0.12       0  5980.6    0.05       0  6267.2    0.12       0
  6275.5    0.05       0  6381.2    0.12       0  6520.5    0.05       0
Bank Sta=5031.4,5064.4
Exp/Cntr=0.3,0.1

Type RM Length L Ch R = 1,28916,441,441,441
BEGIN DESCRIPTION:
IRISH CREEK 55.0
END DESCRIPTION:
XS GIS Cut Line= 3
      2545079.72     13588205.36      2543424.59     13586840.17
      2541753.31     13586483.13
#Sta/Elev= 30
  2806.5  224.74  3054.6  216.74  3133.2  212.72  3214.9  206.55  3257.8  202.74
  3375.2  192.69  3382.4  192.33  3641.8  182.31  4779.3  177.67  4834.8  177.82
  4856.1  175.84  4926.4  178.35  4954.8  178.04  4961.8  175.28  4973.0  174.57
  4974.0  174.07  5012.0  174.57  5033.4  177.10  5053.8  177.17  5115.2  184.27
  5192.5  188.17  5492.5  205.97  5584.1  209.32  5829.9  216.88  5914.0  218.96
  6215.0  222.16  6328.6  225.37  6505.9  233.25  6587.7  241.98  6661.0  242.19
#Mann=16,-1,0
  2806.5    0.04       0  3054.6   0.013       0  3133.2    0.04       0
  3214.9   0.013       0  3257.8    0.04       0  3375.2   0.013       0
  3382.4    0.04       0  4779.3     0.1       0  4973.0    0.05       0
  5012.0     0.1       0  5192.5    0.04       0  5492.5    0.05       0
  5584.1    0.04       0  5829.9    0.05       0  6215.0    0.12       0
  6328.6    0.05       0
Bank Sta=4973,5012
Exp/Cntr=0.3,0.1

Type RM Length L Ch R = 1,28475,653,653,653
BEGIN DESCRIPTION:
Mapping XS 771f490d
END DESCRIPTION:
XS GIS Cut Line= 4
      2545211.64     13588080.33      2544621.38     13587128.96
      2543385.27     13586413.69      2542088.32     13586351.27
#Sta/Elev= 30
  2635.8  222.91  2724.5  220.60  2759.8  216.19  2795.8  216.04  2811.2  212.58
  3137.2  195.44  3420.6  185.51  4635.9  177.83  4815.7  174.32  4831.5  176.48
  4860.4  173.98  4964.3  177.48  5002.6  173.87  5003.6  173.37  5041.7  173.87
  5045.2  178.33  5058.8  177.97  5115.7  176.22  5170.6  179.07  5368.9  186.54
  5467.2  193.74  5678.5  206.84  5835.6  216.88  5854.6  219.91  5914.7  217.26
  5949.3  218.53  6048.2  224.63  6105.7  225.70  6265.1  227.54  6482.0  234.81
#Mann=13,-1,0
  2635.8    0.04       0  4635.9     0.1       0  5002.6    0.05       0
  5041.7     0.1       0  5058.8    0.05       0  5170.6    0.12       0
  5368.9    0.05       0  5467.2    0.04       0  5678.5    0.12       0
  5835.6    0.04       0  5949.3    0.05       0  6048.2    0.04       0
  6105.7    0.05       0
Bank Sta=5002.6,5041.7
Exp/Cntr=0.3,0.1

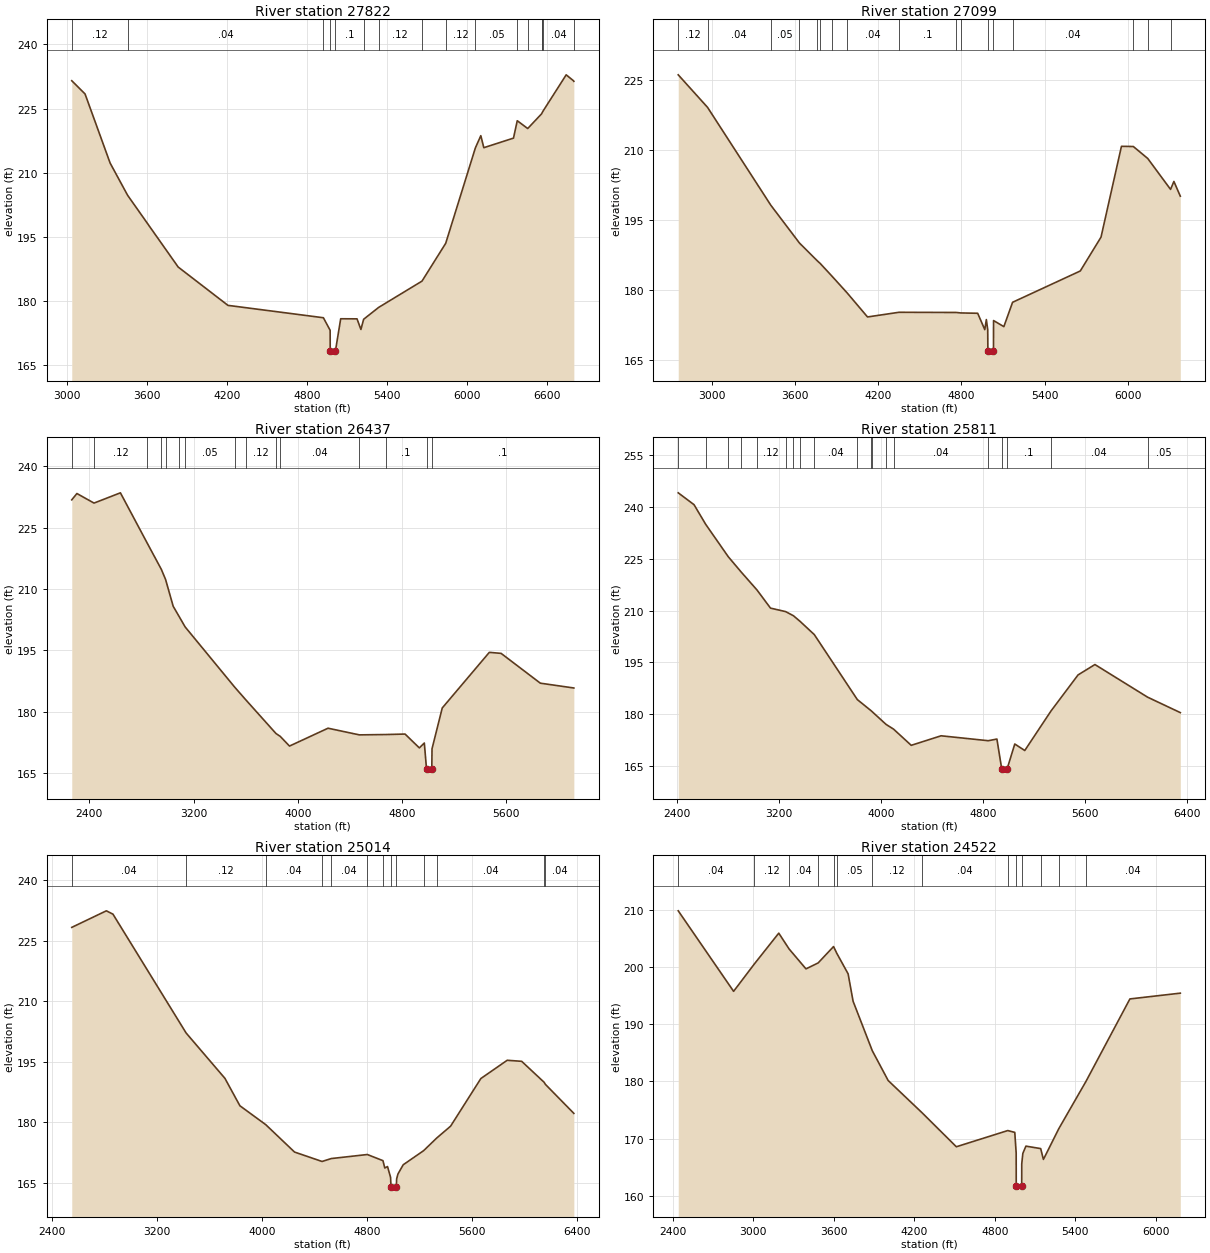
Type RM Length L Ch R = 1,27822,723,723,723
BEGIN DESCRIPTION:
Mapping XS a714eb42
END DESCRIPTION:
XS GIS Cut Line= 4
      2545663.03     13586635.90      2544906.10     13586115.07
      2543440.83     13585920.63      2542088.34     13586142.58
#Sta/Elev= 30
  3035.2  231.51  3134.9  228.42  3323.0  212.27  3454.5  204.73  3833.7  187.97
  4207.3  179.01  4923.4  176.12  4974.0  173.18  4974.5  168.35  4975.5  167.85
  5013.7  168.35  5053.2  175.88  5175.7  175.86  5204.9  173.38  5225.3  175.76
  5337.8  178.53  5663.3  184.68  5841.1  193.51  6063.9  215.82  6104.6  218.67
  6127.1  215.86  6349.8  218.10  6378.1  222.16  6456.6  220.34  6560.8  223.78
  6564.8  224.03  6572.8  224.47  6745.3  232.89  6800.8  231.48  6802.7  231.37
#Mann=16,-1,0
  3035.2    0.12       0  3454.5    0.04       0  4923.4     0.1       0
  4974.5    0.05       0  5013.7     0.1       0  5225.3    0.04       0
  5337.8    0.12       0  5663.3    0.04       0  5841.1    0.12       0
  6063.9    0.05       0  6378.1    0.04       0  6456.6    0.05       0
  6560.8    0.04       0  6564.8    0.05       0  6572.8    0.04       0
  6800.8    0.05       0
Bank Sta=4974.5,5013.7
Exp/Cntr=0.3,0.1

Type RM Length L Ch R = 1,27099,662,662,662
BEGIN DESCRIPTION:
Mapping XS 442ecbb2
END DESCRIPTION:
XS GIS Cut Line= 4
      2545996.42     13586122.04      2544885.27     13585601.19
      2543447.77     13585108.13      2542629.20     13584802.90
#Sta/Elev= 30
  2758.1  226.07  2969.7  219.10  3426.1  198.15  3632.1  190.08  3760.5  186.28
  3781.6  185.71  3867.7  182.95  3974.9  179.44  4123.0  174.25  4349.6  175.25
  4764.0  175.21  4795.5  175.11  4917.4  175.04  4968.7  171.54  4979.9  173.69
  4989.9  171.53  4991.0  167.01  4992.0  166.51  5031.3  167.01  5031.9  173.48
  5106.2  172.18  5169.1  177.39  5657.3  184.09  5806.8  191.33  5954.2  210.77
  6039.8  210.73  6143.7  208.17  6308.3  201.55  6332.4  203.25  6378.6  200.10
#Mann=17,-1,0
  2758.1    0.12       0  2969.7    0.04       0  3426.1    0.05       0
  3632.1    0.04       0  3760.5    0.05       0  3781.6    0.12       0
  3867.7    0.05       0  3974.9    0.04       0  4349.6     0.1       0
  4764.0    0.05       0  4795.5     0.1       0  4991.0    0.05       0
  5031.3     0.1       0  5169.1    0.04       0  6039.8   0.013       0
  6143.7    0.05       0  6308.3    0.12       0
Bank Sta=4991,5031.3
Exp/Cntr=0.3,0.1

Type RM Length L Ch R = 1,26437,626,626,626
BEGIN DESCRIPTION:
Mapping XS a8bcfe08
END DESCRIPTION:
XS GIS Cut Line= 3
      2546385.23     13585948.39      2543989.44     13584663.69
      2542858.71     13584566.57
#Sta/Elev= 30
  2265.7  231.81  2305.1  233.36  2436.5  231.02  2639.0  233.53  2843.2  221.32
  2953.1  214.81  2985.6  212.34  3044.2  205.77  3089.3  203.29  3135.6  200.73
  3517.1  185.95  3601.8  182.87  3832.8  174.65  3865.7  173.94  3936.8  171.57
  4232.5  175.94  4472.8  174.31  4674.4  174.39  4823.7  174.51  4933.4  171.12
  4971.5  172.32  4988.5  165.94  4989.5  165.44  5028.9  165.94  5030.6  170.90
  5109.1  180.89  5470.4  194.50  5560.8  194.25  5861.9  186.96  6119.1  185.78
#Mann=15,-1,0
  2265.7    0.05       0  2436.5    0.12       0  2843.2    0.05       0
  2953.1    0.12       0  2985.6    0.05       0  3089.3    0.04       0
  3135.6    0.05       0  3517.1    0.04       0  3601.8    0.12       0
  3832.8    0.05       0  3865.7    0.04       0  4472.8    0.05       0
  4674.4     0.1       0  4988.5    0.05       0  5028.9     0.1       0
Bank Sta=4988.5,5028.9
Exp/Cntr=0.3,0.1

Type RM Length L Ch R = 1,25811,797,797,797
BEGIN DESCRIPTION:
Mapping XS 1393609d
END DESCRIPTION:
XS GIS Cut Line= 3
      2546711.65     13585677.57      2544496.38     13584372.02
      2543158.01     13584115.44
#Sta/Elev= 30
  2410.2  243.98  2534.0  240.56  2625.4  234.89  2802.6  225.52  2905.5  221.03
  3027.2  215.94  3133.0  210.70  3251.8  209.69  3313.1  208.49  3364.1  206.90
  3476.5  203.05  3813.4  184.30  3924.4  180.99  3925.7  180.94  4038.1  177.15
  4097.9  175.75  4235.8  171.09  4470.0  173.84  4839.2  172.42  4907.2  172.90
  4945.6  164.14  4946.6  163.64  4986.0  164.14  5047.3  171.47  5125.5  169.59
  5330.6  180.98  5543.0  191.41  5675.3  194.41  6087.5  185.00  6344.3  180.53
#Mann=19,-1,0
  2410.2    0.04       0  2625.4    0.05       0  2802.6    0.04       0
  2905.5    0.05       0  3027.2    0.12       0  3251.8    0.05       0
  3313.1    0.12       0  3364.1    0.05       0  3476.5    0.04       0
  3813.4    0.05       0  3924.4    0.12       0  3925.7    0.05       0
  4038.1    0.12       0  4097.9    0.04       0  4839.2     0.1       0
  4945.6    0.05       0  4986.0     0.1       0  5330.6    0.04       0
  6087.5    0.05       0
Bank Sta=4945.6,4986
Exp/Cntr=0.3,0.1

Type RM Length L Ch R = 1,25014,492,492,492
BEGIN DESCRIPTION:
Mapping XS c5489038
END DESCRIPTION:
XS GIS Cut Line= 3
      2546961.68     13585205.37      2544975.55     13583767.85
      2543608.75     13583684.60
#Sta/Elev= 30
  2552.7  228.25  2815.8  232.35  2866.1  231.53  3422.7  202.11  3718.4  190.86
  3832.4  184.07  4029.2  179.39  4248.2  172.61  4457.4  170.28  4527.8  171.00
  4802.1  172.00  4921.1  170.48  4934.9  168.66  4955.8  169.02  4979.0  166.35
  4982.3  163.93  4983.3  163.43  5022.9  163.93  5025.1  165.95  5035.1  167.17
  5075.1  169.46  5230.7  172.96  5329.0  176.05  5435.8  179.02  5666.2  190.82
  5866.6  195.34  5976.8  195.08  6148.0  189.88  6156.6  189.40  6373.8  182.19
#Mann=13,-1,0
  2552.7    0.04       0  3422.7    0.12       0  4029.2    0.04       0
  4457.4    0.03       0  4527.8    0.04       0  4802.1    0.05       0
  4921.1     0.1       0  4982.3    0.05       0  5022.9     0.1       0
  5230.7    0.12       0  5329.0    0.04       0  6148.0    0.05       0
  6156.6    0.04       0
Bank Sta=4982.3,5022.9
Exp/Cntr=0.3,0.1

Type RM Length L Ch R = 1,24522,557,557,557
BEGIN DESCRIPTION:
Mapping XS 2f4c2f6e
END DESCRIPTION:
XS GIS Cut Line= 4
      2547510.31     13584503.99      2545982.49     13583601.19
      2544794.99     13583274.80      2544059.44     13583295.61
#Sta/Elev= 30
  2440.0  209.78  2852.7  195.72  3007.3  200.50  3189.3  205.88  3265.9  203.13
  3392.1  199.64  3482.9  200.68  3597.6  203.54  3621.8  202.36  3706.2  198.77
  3743.2  193.99  3886.4  185.34  4004.6  180.14  4256.4  174.53  4512.8  168.57
  4896.1  171.40  4948.3  171.08  4958.7  167.46  4959.2  161.67  4960.2  161.17
  4999.8  161.67  5000.2  165.57  5008.4  167.41  5031.3  168.68  5141.4  168.25
  5161.7  166.36  5276.4  171.73  5478.0  179.95  5806.3  194.39  6182.0  195.40
#Mann=14,-1,0
  2440.0    0.04       0  3007.3    0.12       0  3265.9    0.04       0
  3482.9    0.05       0  3597.6    0.04       0  3621.8    0.05       0
  3886.4    0.12       0  4256.4    0.04       0  4896.1     0.1       0
  4959.2    0.05       0  4999.8     0.1       0  5141.4    0.12       0
  5276.4    0.05       0  5478.0    0.04       0
Bank Sta=4959.2,4999.8
Exp/Cntr=0.3,0.1

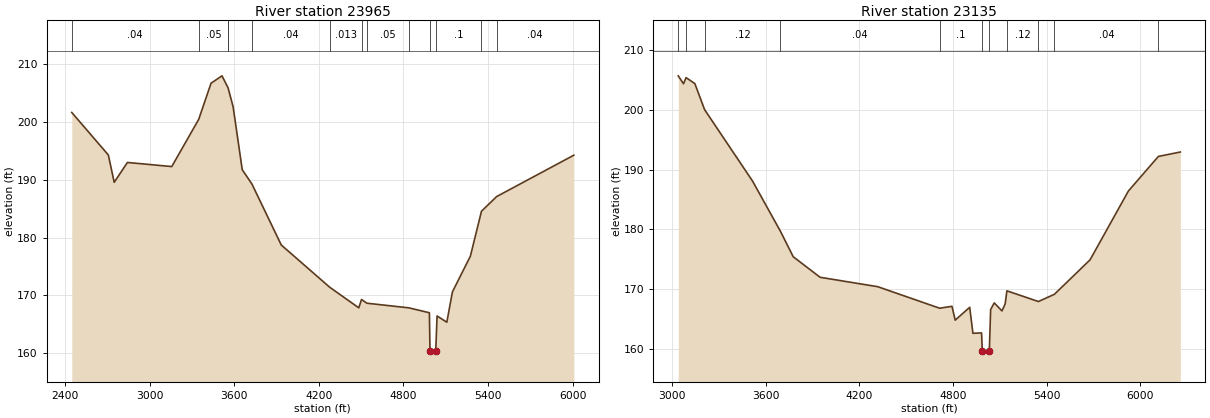
Type RM Length L Ch R = 1,23965,830,830,830
BEGIN DESCRIPTION:
Mapping XS 392a4305
END DESCRIPTION:
XS GIS Cut Line= 4
      2547413.08     13584128.99      2546281.10     13583274.80
      2545031.10     13582788.69      2544232.49     13582830.35
#Sta/Elev= 30
  2448.7  201.64  2707.9  194.29  2749.5  189.56  2843.2  192.99  3157.5  192.28
  3348.2  200.43  3436.0  206.70  3513.5  207.98  3555.9  205.94  3557.0  205.87
  3592.6  202.61  3657.1  191.74  3725.8  189.26  3933.8  178.71  4277.3  171.40
  4483.3  167.84  4502.7  169.29  4540.7  168.64  4837.3  167.84  4983.8  166.99
  4988.0  160.33  4989.0  159.83  5028.6  160.33  5038.2  166.43  5107.3  165.35
  5147.0  170.60  5274.2  176.77  5352.9  184.55  5460.5  187.09  6007.7  194.25
#Mann=13,-1,0
  2448.7    0.04       0  3348.2    0.05       0  3555.9    0.04       0
  3557.0    0.12       0  3725.8    0.04       0  4277.3   0.013       0
  4502.7     0.1       0  4540.7    0.05       0  4837.3     0.1       0
  4988.0    0.05       0  5028.6     0.1       0  5352.9    0.05       0
  5460.5    0.04       0
Bank Sta=4988,5028.6
Exp/Cntr=0.3,0.1

Type RM Length L Ch R = 1,23135,531,531,531
BEGIN DESCRIPTION:
Mapping XS 0dd666e6
END DESCRIPTION:
XS GIS Cut Line= 4
      2547218.59     13581372.03      2546510.27     13581823.41
      2544982.49     13582219.24      2544232.52     13582497.01
#Sta/Elev= 30
  3038.8  205.71  3072.5  204.38  3089.0  205.41  3145.3  204.41  3207.7  200.05
  3515.1  188.08  3693.2  179.71  3775.8  175.41  3948.1  171.97  4318.0  170.39
  4714.3  166.79  4793.2  167.11  4813.9  164.79  4906.9  166.94  4927.5  162.59
  4982.9  162.65  4987.7  159.60  4988.7  159.10  5032.6  159.60  5041.1  166.57
  5064.1  167.68  5113.5  166.34  5134.1  167.50  5145.3  169.70  5347.4  167.91
  5449.7  169.12  5678.2  174.89  5924.3  186.43  6116.2  192.21  6256.7  192.95
#Mann=11,-1,0
  3038.8    0.04       0  3089.0   0.013       0  3207.7    0.12       0
  3693.2    0.04       0  4714.3     0.1       0  4987.7    0.05       0
  5032.6     0.1       0  5145.3    0.12       0  5347.4    0.05       0
  5449.7    0.04       0  6116.2    0.05       0
Bank Sta=4987.7,5032.6
Exp/Cntr=0.3,0.1