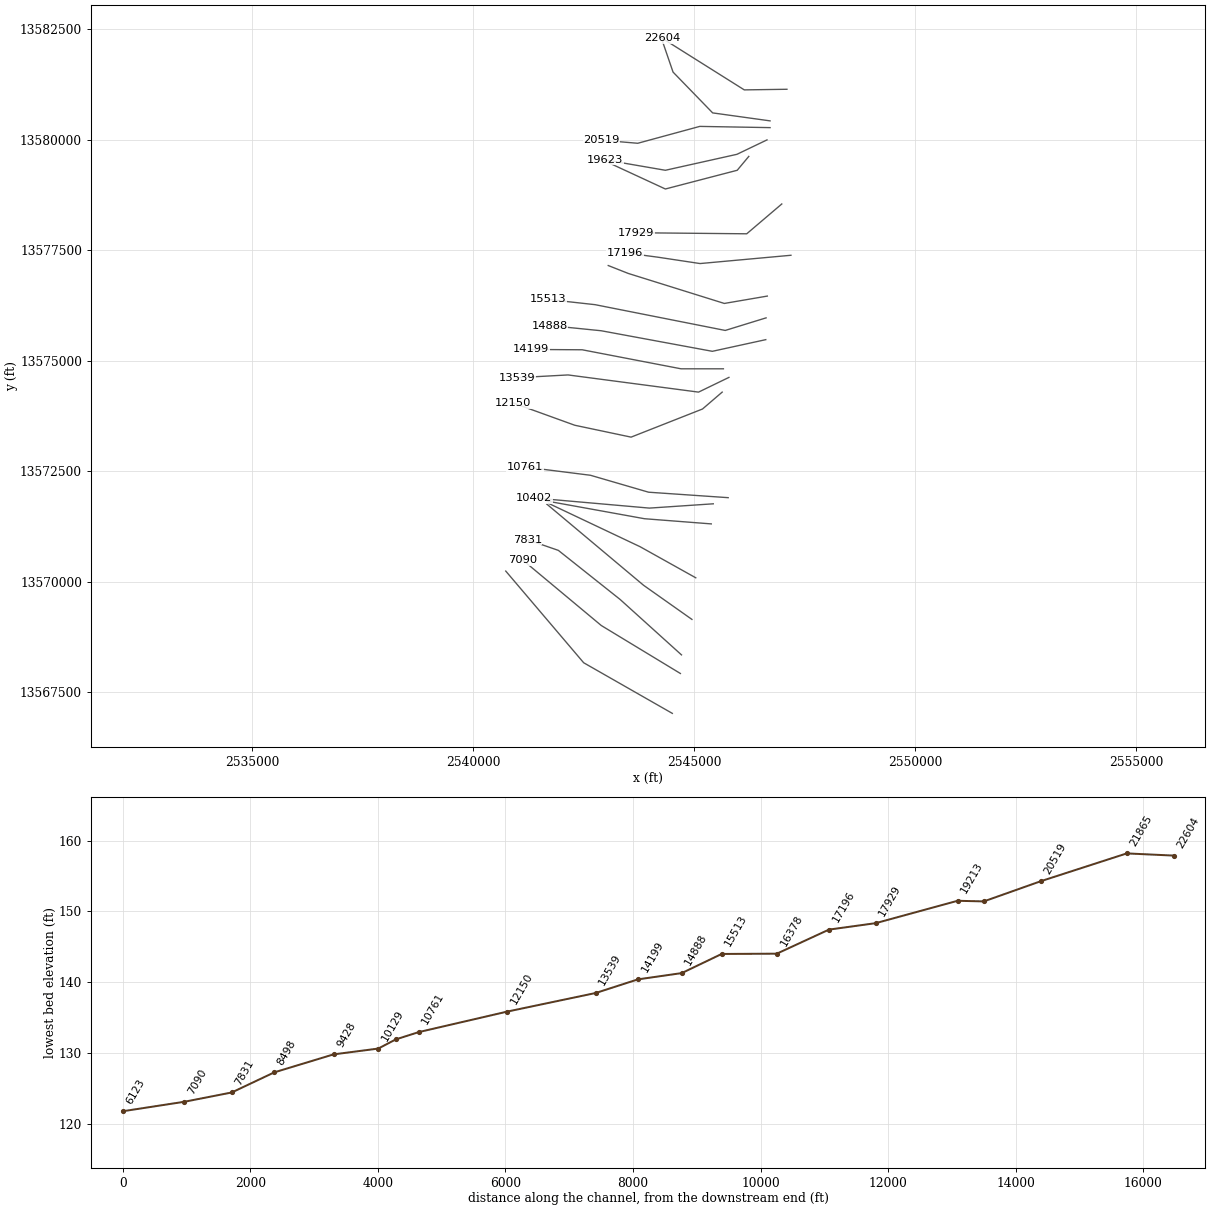
HEC-RAS study IRISH CREEK.prj: IRISH CREEK Base Level Engineering

--- IRISH CREEK.g01 (geometry) --- (continued)

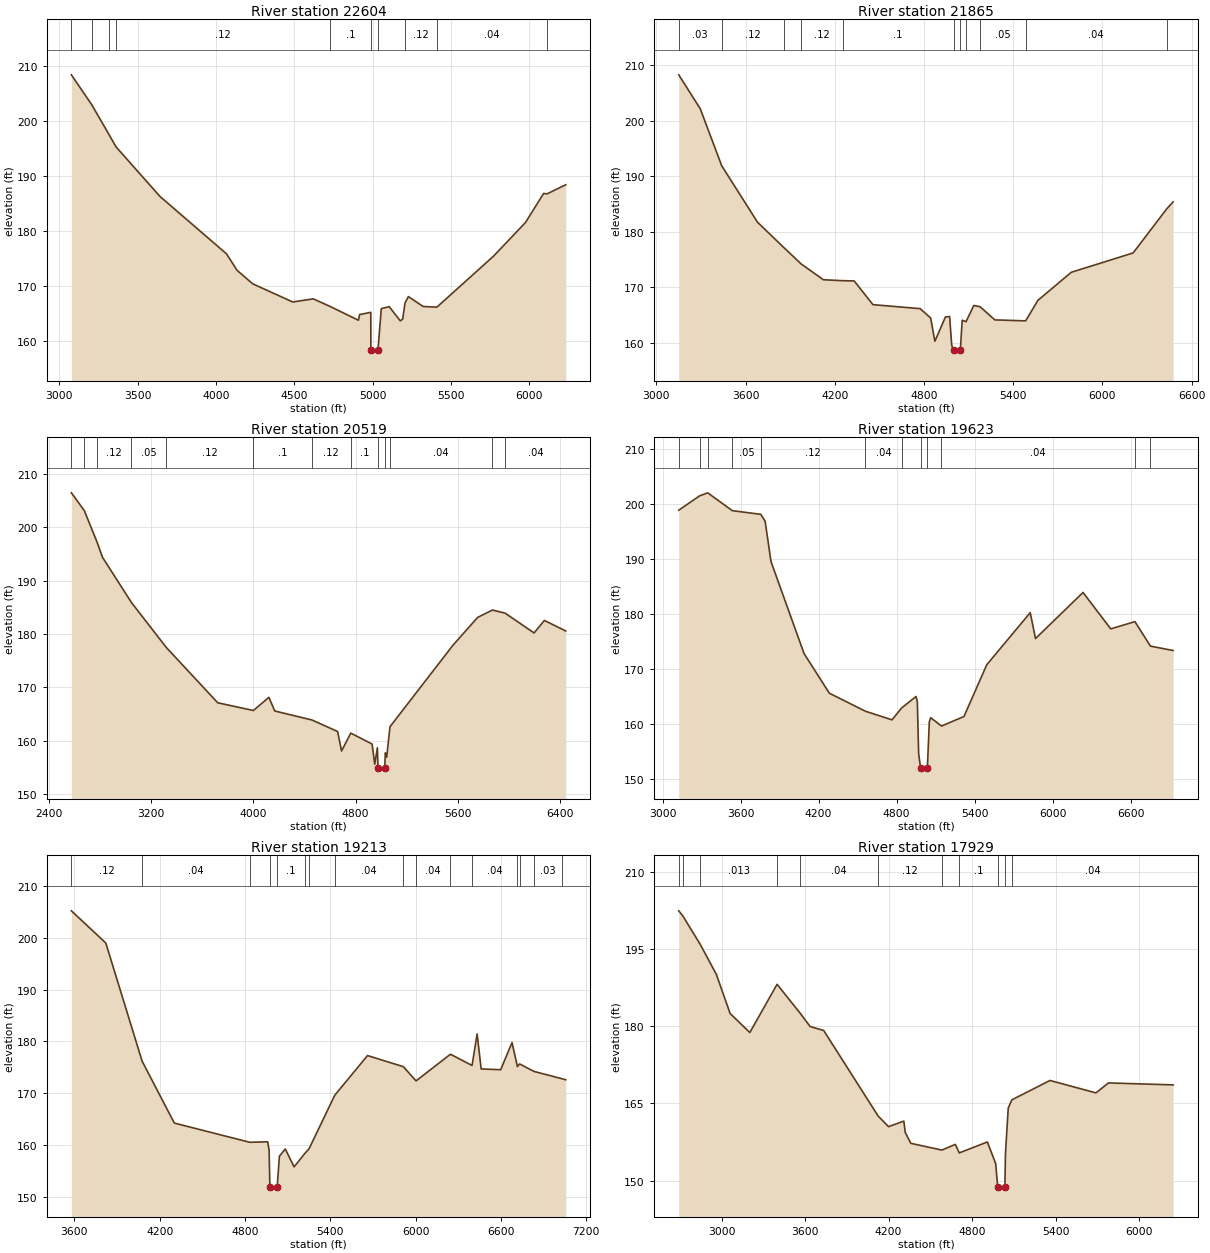
Type RM Length L Ch R = 1,22604,739,739,739
BEGIN DESCRIPTION:
Mapping XS a0ab2304
END DESCRIPTION:
XS GIS Cut Line= 3
      2547100.50     13581142.85      2546135.27     13581128.96
      2544281.10     13582295.63
#Sta/Elev= 30
  3076.4  208.48  3206.5  203.04  3314.0  197.75  3361.5  195.38  3642.0  186.36
  4067.0  175.92  4134.1  172.93  4234.2  170.47  4489.7  167.17  4620.4  167.74
  4728.8  166.35  4908.9  163.85  4916.3  164.88  4987.8  165.29  4988.4  158.37
  4989.4  157.87  5033.4  158.37  5054.9  165.96  5105.4  166.32  5176.3  163.73
  5191.5  164.07  5206.2  166.99  5228.0  168.15  5322.2  166.35  5409.5  166.23
  5772.0  175.52  5975.8  181.64  6091.2  186.91  6112.9  186.83  6232.4  188.49
#Mann=10,-1,0
  3076.4    0.04       0  3206.5    0.12       0  3314.0    0.05       0
  3361.5    0.12       0  4728.8     0.1       0  4988.4    0.05       0
  5033.4     0.1       0  5206.2    0.12       0  5409.5    0.04       0
  6112.9    0.05       0
Bank Sta=4988.4,5033.4
Exp/Cntr=0.3,0.1

Type RM Length L Ch R = 1,21865,1346,1346,1346
BEGIN DESCRIPTION:
Mapping XS d27cb72b
END DESCRIPTION:
XS GIS Cut Line= 4
      2546718.58     13580427.58      2545419.99     13580608.13
      2544524.16     13581531.74      2544288.04     13582219.25
#Sta/Elev= 30
  3150.6  208.24  3295.6  202.12  3439.6  191.88  3680.4  181.73  3855.4  177.22
  3974.1  174.22  4123.5  171.38  4253.9  171.21  4330.2  171.17  4456.6  166.90
  4774.2  166.18  4844.9  164.49  4873.2  160.31  4944.0  164.68  4972.3  164.77
  4986.4  159.59  4999.1  158.68  5000.1  158.18  5044.2  158.68  5056.9  164.11
  5082.6  163.83  5134.9  166.75  5177.2  166.53  5276.3  164.16  5483.5  163.98
  5566.2  167.68  5790.4  172.72  6206.5  176.20  6432.9  184.15  6475.3  185.39
#Mann=11,-1,0
  3150.6    0.03       0  3439.6    0.12       0  3855.4    0.05       0
  3974.1    0.12       0  4253.9     0.1       0  4999.1    0.05       0
  5044.2     0.1       0  5082.6    0.12       0  5177.2    0.05       0
  5483.5    0.04       0  6432.9    0.05       0
Bank Sta=4999.1,5044.2
Exp/Cntr=0.3,0.1

Type RM Length L Ch R = 1,20519,896,896,896
BEGIN DESCRIPTION:
Mapping XS 9b069bc9
END DESCRIPTION:
XS GIS Cut Line= 4
      2546718.63     13580274.80      2545128.33     13580302.57
      2543725.55     13579920.63      2542908.47     13579989.87
#Sta/Elev= 30
  2578.7  206.45  2679.8  203.12  2778.2  197.28  2822.4  194.34  3047.7  185.90
  3320.0  177.47  3722.5  167.08  4001.5  165.63  4122.6  168.10  4168.4  165.54
  4459.2  163.85  4659.8  161.69  4690.9  158.04  4762.7  161.39  4929.3  159.34
  4950.0  155.56  4970.7  158.64  4976.0  154.76  4977.0  154.26  5027.6  154.76
  5032.9  157.69  5043.3  156.87  5069.2  162.59  5561.5  177.87  5754.1  183.08
  5870.0  184.47  5969.0  183.89  6195.7  180.17  6276.0  182.52  6443.1  180.54
#Mann=13,-1,0
  2578.7    0.03       0  2679.8    0.05       0  2778.2    0.12       0
  3047.7    0.05       0  3320.0    0.12       0  4001.5     0.1       0
  4459.2    0.12       0  4762.7     0.1       0  4976.0    0.05       0
  5027.6     0.1       0  5069.2    0.04       0  5870.0   0.013       0
  5969.0    0.04       0
Bank Sta=4976,5027.6
Exp/Cntr=0.3,0.1

Type RM Length L Ch R = 1,19623,410,410,410
BEGIN DESCRIPTION:
Mapping XS 79ce74f1
END DESCRIPTION:
XS GIS Cut Line= 4
      2546649.14     13579997.01      2545968.60     13579670.63
      2544350.55     13579309.52      2542982.49     13579545.63
#Sta/Elev= 30
  3124.8  198.92  3284.4  201.53  3347.5  202.09  3536.7  198.84  3755.8  198.17
  3788.9  196.92  3834.2  189.56  4088.2  172.82  4282.8  165.59  4560.0  162.31
  4764.4  160.74  4838.3  162.90  4948.8  164.99  4959.1  164.08  4969.3  154.58
  4984.5  151.90  4985.5  151.40  5036.2  151.90  5051.3  160.35  5061.5  161.13
  5144.9  159.61  5317.7  161.35  5493.1  170.78  5827.2  180.27  5867.8  175.55
  6233.1  183.94  6446.2  177.31  6632.0  178.63  6751.6  174.17  6925.7  173.37
#Mann=12,-1,0
  3124.8    0.12       0  3284.4    0.05       0  3347.5    0.12       0
  3536.7    0.05       0  3755.8    0.12       0  4560.0    0.04       0
  4838.3     0.1       0  4984.5    0.05       0  5036.2     0.1       0
  5144.9    0.04       0  6632.0    0.03       0  6751.6    0.04       0
Bank Sta=4984.5,5036.2
Exp/Cntr=0.3,0.1

Type RM Length L Ch R = 1,19213,1284,1284,1284
BEGIN DESCRIPTION:
Mapping XS 00b7621e
END DESCRIPTION:
XS GIS Cut Line= 4
      2546237.18     13579623.37      2545975.55     13579309.52
      2544350.55     13578885.91      2543089.70     13579469.83
#Sta/Elev= 30
  3579.1  205.21  3821.2  199.00  4076.4  176.21  4303.2  164.24  4834.0  160.53
  4959.7  160.63  4970.0  159.01  4975.2  151.99  4976.2  151.49  5026.9  151.99
  5042.3  157.85  5083.7  159.24  5145.7  155.78  5220.5  158.35  5250.6  159.26
  5431.4  169.60  5662.1  177.27  5914.1  175.13  6003.6  172.38  6245.5  177.53
  6397.4  175.36  6433.1  181.44  6461.5  174.69  6598.8  174.54  6678.8  179.79
  6716.4  175.15  6732.3  175.65  6833.3  174.21  7027.1  172.82  7056.5  172.60
#Mann=16,-1,0
  3579.1    0.12       0  4076.4    0.04       0  4834.0     0.1       0
  4975.2    0.05       0  5026.9     0.1       0  5220.5    0.04       0
  5250.6    0.12       0  5431.4    0.04       0  5914.1    0.03       0
  6003.6    0.04       0  6245.5    0.03       0  6397.4    0.04       0
  6716.4    0.03       0  6732.3    0.04       0  6833.3    0.03       0
  7027.1    0.04       0
Bank Sta=4975.2,5026.9
Exp/Cntr=0.3,0.1

Type RM Length L Ch R = 1,17929,733,733,733
BEGIN DESCRIPTION:
Mapping XS 4c87ed2c
END DESCRIPTION:
XS GIS Cut Line= 3
      2546983.71     13578546.97      2546190.83     13577872.02
      2543680.70     13577895.67
#Sta/Elev= 30
  2692.5  202.50  2721.6  201.52  2847.8  195.93  2962.8  190.12  3061.6  182.52
  3203.2  178.81  3398.9  188.20  3566.0  182.53  3636.4  179.98  3733.8  179.21
  4125.1  162.55  4199.6  160.49  4309.6  161.57  4319.6  159.37  4359.6  157.25
  4582.6  155.93  4679.6  157.04  4707.9  155.38  4909.6  157.51  4969.6  153.28
  4983.7  148.83  4984.7  148.33  5035.5  148.83  5039.6  155.26  5059.6  164.10
  5085.2  165.70  5359.7  169.48  5689.7  167.06  5779.7  169.00  6244.0  168.62
#Mann=11,-1,0
  2692.5    0.05       0  2721.6    0.04       0  2847.8   0.013       0
  3398.9    0.05       0  3566.0    0.04       0  4125.1    0.12       0
  4582.6    0.04       0  4707.9     0.1       0  4983.7    0.05       0
  5035.5     0.1       0  5085.2    0.04       0
Bank Sta=4983.7,5035.5
Exp/Cntr=0.3,0.1

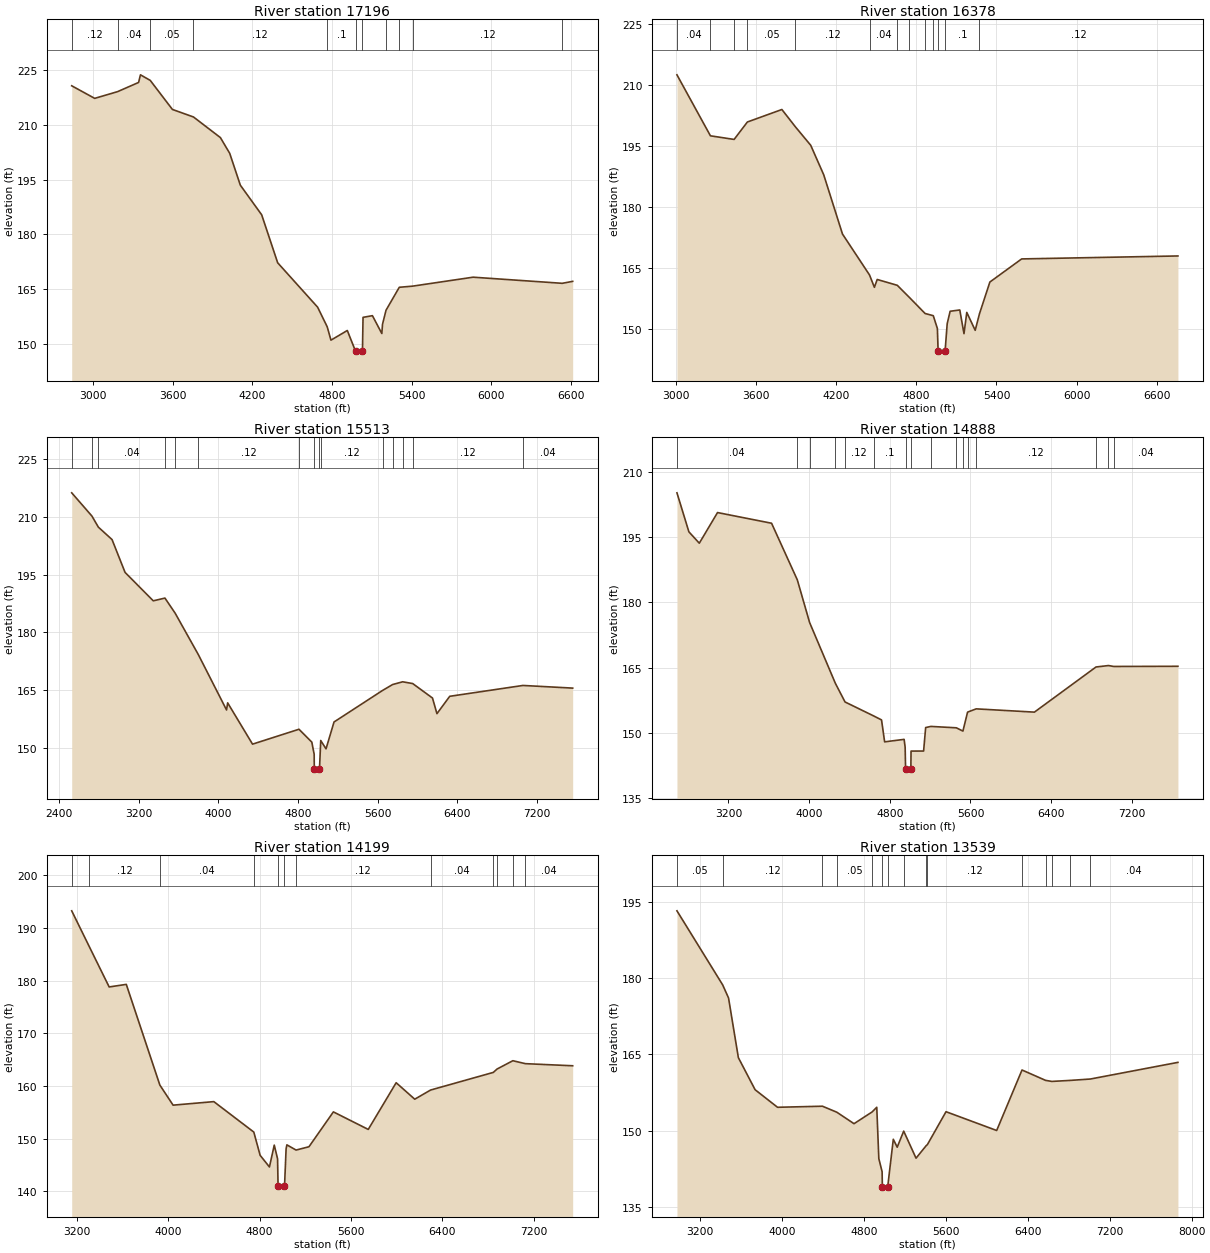
Type RM Length L Ch R = 1,17196,818,818,818
BEGIN DESCRIPTION:
Mapping XS a8bd1940
END DESCRIPTION:
XS GIS Cut Line= 4
      2547190.84     13577385.91      2545135.27     13577198.41
      2544190.18     13577341.06      2543440.85     13577441.30
#Sta/Elev= 30
  2837.5  220.79  3010.8  217.34  3183.7  219.19  3341.7  221.71  3355.5  223.80
  3429.2  222.28  3596.5  214.30  3755.3  212.23  3958.0  206.58  4028.3  202.26
  4108.5  193.51  4269.3  185.39  4389.8  172.22  4691.0  160.03  4763.2  154.65
  4791.4  150.98  4914.7  153.63  4977.1  147.92  4978.1  147.42  5028.9  147.92
  5033.3  157.24  5104.1  157.70  5174.9  152.80  5180.1  155.34  5206.6  159.20
  5306.5  165.49  5406.4  165.80  5862.6  168.26  6534.9  166.58  6613.4  167.12
#Mann=11,-1,0
  2837.5    0.12       0  3183.7    0.04       0  3429.2    0.05       0
  3755.3    0.12       0  4763.2     0.1       0  4977.1    0.05       0
  5028.9     0.1       0  5206.6    0.12       0  5306.5    0.05       0
  5406.4    0.12       0  6534.9    0.05       0
Bank Sta=4977.1,5028.9
Exp/Cntr=0.3,0.1

Type RM Length L Ch R = 1,16378,865,865,865
BEGIN DESCRIPTION:
Mapping XS 50fd8ac0
END DESCRIPTION:
XS GIS Cut Line= 4
      2546656.05     13576462.29      2545683.88     13576295.63
      2543510.88     13576974.82      2543058.66     13577153.33
#Sta/Elev= 30
  3008.9  212.56  3259.4  197.54  3436.6  196.65  3535.9  200.94  3794.1  204.02
  3895.1  199.76  4009.9  195.21  4107.3  187.94  4247.7  173.35  4450.0  163.27
  4486.5  160.23  4507.5  162.16  4657.9  160.72  4747.7  157.76  4865.9  153.78
  4927.2  153.24  4958.0  150.07  4963.3  144.52  4964.3  144.02  5015.6  144.52
  5031.3  151.26  5053.3  154.33  5125.6  154.65  5157.0  148.81  5177.9  154.05
  5240.9  149.64  5272.7  153.69  5350.8  161.53  5588.6  167.22  6758.1  167.95
#Mann=13,-1,0
  3008.9    0.04       0  3259.4    0.03       0  3436.6    0.12       0
  3535.9    0.05       0  3895.1    0.12       0  4450.0    0.04       0
  4657.9    0.05       0  4747.7    0.04       0  4865.9    0.12       0
  4927.2     0.1       0  4963.3    0.05       0  5015.6     0.1       0
  5272.7    0.12       0
Bank Sta=4963.3,5015.6
Exp/Cntr=0.3,0.1

Type RM Length L Ch R = 1,15513,625,625,625
BEGIN DESCRIPTION:
Mapping XS 59eccaf7
END DESCRIPTION:
XS GIS Cut Line= 4
      2546628.30     13575969.23      2545704.71     13575684.52
      2542760.27     13576267.85      2541698.85     13576385.79
#Sta/Elev= 30
  2524.6  216.29  2727.9  210.25  2792.7  207.37  2930.1  204.14  3060.8  195.62
  3344.3  188.23  3461.9  188.94  3564.0  185.04  3797.2  174.27  4081.1  159.87
  4092.3  161.72  4342.3  150.99  4809.3  154.86  4938.4  151.51  4962.0  148.35
  4963.2  144.48  4964.2  143.98  5015.5  144.48  5027.9  151.94  5081.1  149.77
  5161.7  156.75  5650.0  164.95  5750.8  166.48  5851.7  167.19  5952.5  166.73
  6151.5  162.97  6196.2  158.91  6324.8  163.42  7060.8  166.24  7560.7  165.55
#Mann=15,-1,0
  2524.6    0.04       0  2727.9    0.05       0  2792.7    0.04       0
  3461.9    0.05       0  3564.0    0.04       0  3797.2    0.12       0
  4809.3     0.1       0  4963.2    0.05       0  5015.5     0.1       0
  5027.9    0.12       0  5650.0    0.05       0  5750.8    0.12       0
  5851.7    0.05       0  5952.5    0.12       0  7060.8    0.04       0
Bank Sta=4963.2,5015.5
Exp/Cntr=0.3,0.1

Type RM Length L Ch R = 1,14888,689,689,689
BEGIN DESCRIPTION:
Mapping XS 99c58071
END DESCRIPTION:
XS GIS Cut Line= 4
      2546621.35     13575476.18      2545413.05     13575212.30
      2542899.16     13575677.57      2541732.48     13575795.63
#Sta/Elev= 30
  2690.3  205.15  2808.6  196.20  2911.8  193.59  3092.5  200.62  3628.2  198.17
  3883.3  185.18  4005.4  175.38  4260.2  161.45  4356.5  157.15  4639.2  153.96
  4718.3  153.03  4748.9  148.00  4942.1  148.57  4952.3  146.75  4956.6  141.78
  4957.6  141.28  5008.9  141.78  5010.8  145.88  5135.3  145.89  5155.6  151.28
  5207.4  151.54  5459.8  151.22  5525.0  150.47  5571.1  154.82  5656.8  155.57
  6233.7  154.82  6844.3  165.18  6968.0  165.51  7019.4  165.30  7656.3  165.34
#Mann=16,-1,0
  2690.3    0.04       0  3883.3    0.12       0  4005.4    0.03       0
  4260.2    0.05       0  4356.5    0.12       0  4639.2     0.1       0
  4956.6    0.05       0  5008.9     0.1       0  5207.4    0.12       0
  5459.8    0.05       0  5525.0    0.12       0  5571.1    0.05       0
  5656.8    0.12       0  6844.3    0.04       0  6968.0   0.013       0
  7019.4    0.04       0
Bank Sta=4956.6,5008.9
Exp/Cntr=0.3,0.1

Type RM Length L Ch R = 1,14199,660,660,660
BEGIN DESCRIPTION:
Mapping XS f8afbc8b
END DESCRIPTION:
XS GIS Cut Line= 4
      2545663.10     13574816.46      2544704.71     13574816.46
      2542468.60     13575247.02      2541315.79     13575253.96
#Sta/Elev= 30
  3154.8  193.25  3307.2  186.52  3482.9  178.79  3632.9  179.28  3926.8  160.16
  4042.9  156.34  4399.7  157.01  4749.8  151.23  4805.4  146.81  4886.9  144.60
  4929.0  148.75  4958.1  146.15  4962.5  140.89  4963.5  140.39  5014.9  140.89
  5019.2  141.01  5032.8  148.05  5039.6  148.80  5120.0  147.81  5233.1  148.44
  5447.0  155.06  5752.5  151.73  5996.9  160.60  6159.8  157.47  6298.4  159.21
  6848.0  162.56  6880.8  163.20  7019.2  164.78  7128.9  164.22  7543.2  163.82
#Mann=12,-1,0
  3154.8    0.05       0  3307.2    0.12       0  3926.8    0.04       0
  4749.8     0.1       0  4962.5    0.05       0  5014.9     0.1       0
  5120.0    0.12       0  6298.4    0.04       0  6848.0    0.05       0
  6880.8    0.04       0  7019.2   0.013       0  7128.9    0.04       0
Bank Sta=4962.5,5014.9
Exp/Cntr=0.3,0.1

Type RM Length L Ch R = 1,13539,1389,1389,1389
BEGIN DESCRIPTION:
Mapping XS fa6d1b6a
END DESCRIPTION:
XS GIS Cut Line= 4
      2545788.02     13574622.01      2545100.55     13574288.69
      2542149.16     13574677.57      2541003.28     13574615.07
#Sta/Elev= 30
  2977.7  193.25  3423.6  178.68  3481.1  176.09  3576.9  164.35  3740.2  158.04
  3959.1  154.58  4397.4  154.79  4537.6  153.61  4705.5  151.35  4881.9  153.66
  4927.4  154.58  4947.6  144.47  4979.7  141.88  4981.9  138.97  4982.9  138.47
  5034.4  138.97  5088.8  148.28  5126.9  146.72  5190.3  149.89  5310.7  144.56
  5409.4  147.02  5421.7  147.24  5603.2  153.71  6097.5  150.01  6344.8  161.92
  6574.4  159.88  6635.8  159.67  6814.6  159.87  7011.3  160.14  7866.2  163.42
#Mann=15,-1,0
  2977.7    0.05       0  3423.6    0.12       0  4397.4    0.04       0
  4537.6    0.05       0  4881.9    0.12       0  4981.9    0.05       0
  5034.4    0.12       0  5190.3     0.1       0  5409.4    0.05       0
  5421.7    0.12       0  6344.8    0.04       0  6574.4    0.05       0
  6635.8    0.04       0  6814.6    0.12       0  7011.3    0.04       0
Bank Sta=4981.9,5034.4
Exp/Cntr=0.3,0.1

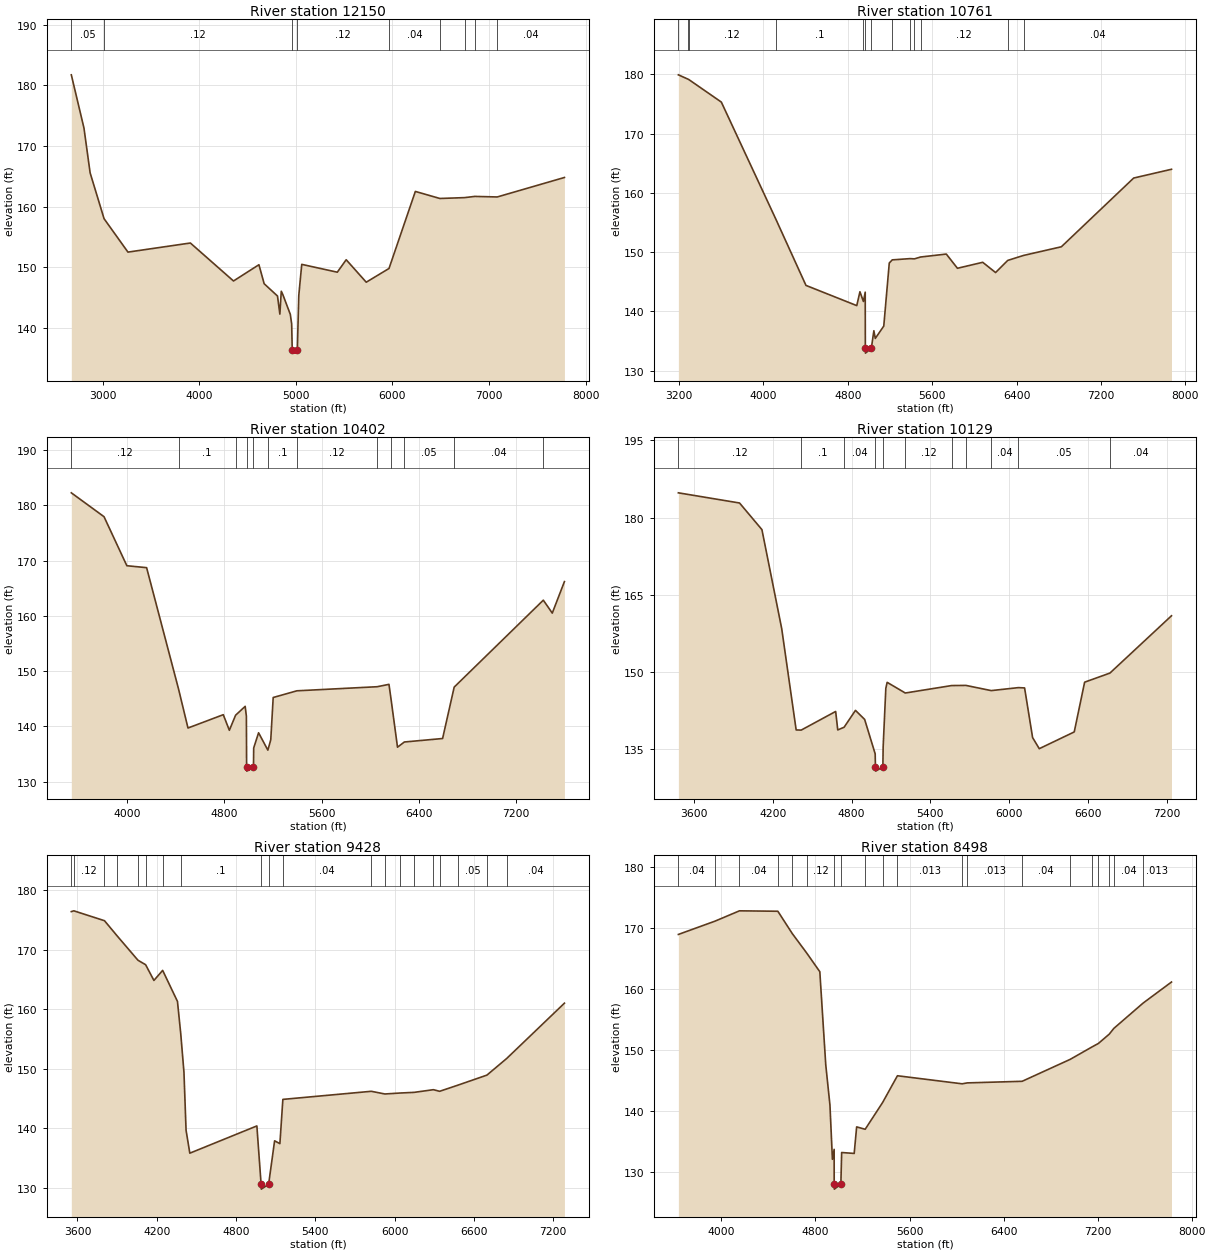
Type RM Length L Ch R = 1,12150,1389,1389,1389
BEGIN DESCRIPTION:
Mapping XS f5e353d7
END DESCRIPTION:
XS GIS Cut Line= 5
      2545635.29     13574288.70      2545190.83     13573906.74
      2543574.91     13573269.96      2542301.94     13573538.69
      2540912.10     13574041.73
#Sta/Elev= 30
  2677.1  181.71  2808.0  172.93  2871.6  165.56  3015.8  158.00  3263.1  152.49
  3908.9  153.99  4355.0  147.73  4618.2  150.41  4672.3  147.28  4810.4  145.25
  4834.8  142.27  4849.4  146.04  4864.5  145.53  4943.1  142.22  4956.9  140.64
  4962.8  136.34  4963.9  135.84  5015.5  136.34  5030.6  145.35  5061.2  150.47
  5429.2  149.18  5521.1  151.23  5728.5  147.53  5964.0  149.79  6236.6  162.49
  6490.4  161.33  6746.5  161.47  6851.0  161.67  7084.2  161.58  7779.1  164.79
#Mann=9,-1,0
  2677.1    0.05       0  3015.8    0.12       0  4962.8    0.05       0
  5015.5    0.12       0  5964.0    0.04       0  6490.4    0.05       0
  6746.5    0.04       0  6851.0    0.05       0  7084.2    0.04       0
Bank Sta=4962.8,5015.5
Exp/Cntr=0.3,0.1

Type RM Length L Ch R = 1,10761,359,359,359
BEGIN DESCRIPTION:
Mapping XS 1e4774f6
END DESCRIPTION:
XS GIS Cut Line= 4
      2545771.08     13571899.79      2543971.22     13572023.43
      2542656.10     13572406.74      2541170.02     13572594.24
#Sta/Elev= 30
  3195.9  179.91  3290.7  179.15  3295.7  179.10  3602.9  175.31  4118.6  155.58
  4404.8  144.37  4886.0  140.96  4916.0  143.30  4948.9  141.66  4966.1  143.23
  4967.3  133.74  4968.6  132.94  5023.9  133.74  5048.1  136.72  5061.5  135.42
  5141.9  137.51  5194.0  148.15  5222.5  148.68  5390.3  148.89  5432.4  148.85
  5490.1  149.16  5734.3  149.66  5839.8  147.26  6079.3  148.27  6201.0  146.54
  6316.5  148.59  6466.8  149.43  6824.5  150.89  7509.6  162.49  7867.7  163.97
#Mann=13,-1,0
  3195.9    0.12       0  3290.7    0.05       0  3295.7    0.12       0
  4118.6     0.1       0  4948.9    0.04       0  4967.3    0.04       0
  5023.9    0.04       0  5222.5     0.1       0  5390.3    0.12       0
  5432.4     0.1       0  5490.1    0.12       0  6316.5   0.013       0
  6466.8    0.04       0
Bank Sta=4967.3,5023.9
Exp/Cntr=0.3,0.1

Type RM Length L Ch R = 1,10402,273,273,273
BEGIN DESCRIPTION:
Mapping XS 86dc06e4
END DESCRIPTION:
XS GIS Cut Line= 3
      2545433.83     13571760.90      2543989.44     13571663.69
      2541385.26     13571892.85
#Sta/Elev= 30
  3538.3  182.26  3807.7  177.94  3995.8  169.07  4158.5  168.72  4421.4  146.78
  4499.3  139.71  4790.0  142.12  4840.1  139.30  4891.3  142.02  4970.4  143.63
  4980.4  141.83  4982.2  132.71  4983.5  131.91  5038.8  132.71  5040.6  136.09
  5080.8  138.85  5157.2  135.71  5181.2  137.58  5201.2  145.23  5396.3  146.44
  6057.7  147.18  6154.9  147.61  6174.1  144.59  6225.2  136.24  6281.6  137.18
  6596.6  137.81  6692.1  147.11  7426.3  162.84  7500.1  160.50  7600.2  166.20
#Mann=12,-1,0
  3538.3    0.12       0  4421.4     0.1       0  4891.3    0.04       0
  4982.2    0.04       0  5038.8    0.04       0  5157.2     0.1       0
  5396.3    0.12       0  6057.7    0.05       0  6174.1    0.04       0
  6281.6    0.05       0  6692.1    0.04       0  7426.3   0.013       0
Bank Sta=4982.2,5038.8
Exp/Cntr=0.3,0.1

Type RM Length L Ch R = 1,10129,701,701,701
BEGIN DESCRIPTION:
Mapping XS 43b9f549
END DESCRIPTION:
XS GIS Cut Line= 3
      2545389.41     13571306.04      2543879.02     13571423.22
      2541674.12     13571822.53
#Sta/Elev= 30
  3480.6  184.81  3946.4  182.83  4116.9  177.65  4267.4  158.40  4377.7  138.64
  4416.2  138.61  4678.6  142.24  4694.5  138.64  4743.0  139.17  4829.3  142.45
  4899.3  140.69  4979.5  133.99  4981.5  131.42  4982.8  130.62  5038.1  131.42
  5040.3  135.37  5060.6  146.74  5070.8  147.91  5208.8  145.83  5561.8  147.28
  5670.7  147.31  5863.2  146.30  6070.6  146.88  6117.5  146.82  6178.5  137.15
  6229.3  134.99  6495.6  138.25  6574.8  147.94  6767.4  149.71  7236.3  160.87
#Mann=11,-1,0
  3480.6    0.12       0  4416.2     0.1       0  4743.0    0.04       0
  4981.5    0.04       0  5038.1    0.04       0  5208.8    0.12       0
  5561.8    0.04       0  5670.7    0.12       0  5863.2    0.04       0
  6070.6    0.05       0  6767.4    0.04       0
Bank Sta=4981.5,5038.1
Exp/Cntr=0.3,0.1

Type RM Length L Ch R = 1,9428,930,930,930
BEGIN DESCRIPTION:
Mapping XS d08308ce
END DESCRIPTION:
XS GIS Cut Line= 3
      2545037.86     13570086.43      2543779.20     13570789.54
      2541709.94     13571769.94
#Sta/Elev= 30
  3553.4  176.44  3572.4  176.57  3804.4  174.91  3901.2  172.33  4057.6  168.27
  4115.8  167.51  4178.4  164.87  4244.6  166.56  4356.6  161.35  4381.6  155.89
  4405.7  149.46  4421.7  139.70  4450.1  135.84  4957.5  140.42  4989.6  130.60
  4990.9  129.80  5046.3  130.60  5091.7  137.92  5131.7  137.44  5154.2  144.88
  5823.4  146.24  5926.2  145.79  6040.7  145.95  6146.8  146.06  6293.3  146.51
  6340.6  146.24  6477.3  147.26  6698.3  148.96  6847.8  151.75  7284.9  161.05
#Mann=20,-1,0
  3553.4    0.04       0  3572.4    0.12       0  3804.4   0.013       0
  3901.2    0.04       0  4057.6   0.013       0  4115.8    0.05       0
  4244.6   0.013       0  4381.6     0.1       0  4989.6    0.05       0
  5046.3     0.1       0  5154.2    0.04       0  5823.4    0.05       0
  5926.2    0.04       0  6040.7    0.05       0  6146.8    0.04       0
  6293.3    0.05       0  6340.6    0.04       0  6477.3    0.05       0
  6698.3    0.12       0  6847.8    0.04       0
Bank Sta=4989.6,5046.3
Exp/Cntr=0.3,0.1

Type RM Length L Ch R = 1,8498,667,667,667
BEGIN DESCRIPTION:
Mapping XS 0b6a83c1
END DESCRIPTION:
XS GIS Cut Line= 3
      2544951.11     13569144.55      2543857.32     13569917.14
      2541669.88     13571753.04
#Sta/Elev= 30
  3633.5  169.00  3945.4  171.18  4153.1  172.87  4479.8  172.80  4602.6  169.14
  4725.4  165.95  4836.8  162.89  4887.3  147.63  4923.0  141.02  4943.9  132.15
  4958.7  133.78  4959.0  128.06  4960.3  127.26  5015.8  128.06  5022.5  133.26
  5129.2  133.11  5150.0  137.46  5222.7  137.07  5371.1  141.46  5497.0  145.84
  6047.8  144.52  6091.1  144.67  6557.8  144.93  6967.0  148.53  7151.1  150.55
  7206.4  151.13  7299.5  152.67  7337.9  153.60  7587.6  157.76  7828.4  161.20
#Mann=20,-1,0
  3633.5    0.04       0  3945.4    0.05       0  4153.1    0.04       0
  4479.8   0.013       0  4602.6   0.013       0  4725.4    0.12       0
  4959.0    0.03       0  5015.8    0.12       0  5222.7     0.1       0
  5371.1    0.12       0  5497.0   0.013       0  6047.8    0.04       0
  6091.1   0.013       0  6557.8    0.04       0  6967.0   0.013       0
  7151.1    0.12       0  7206.4   0.013       0  7299.5    0.12       0
  7337.9    0.04       0  7587.6   0.013       0
Bank Sta=4959,5015.8
Exp/Cntr=0.3,0.1

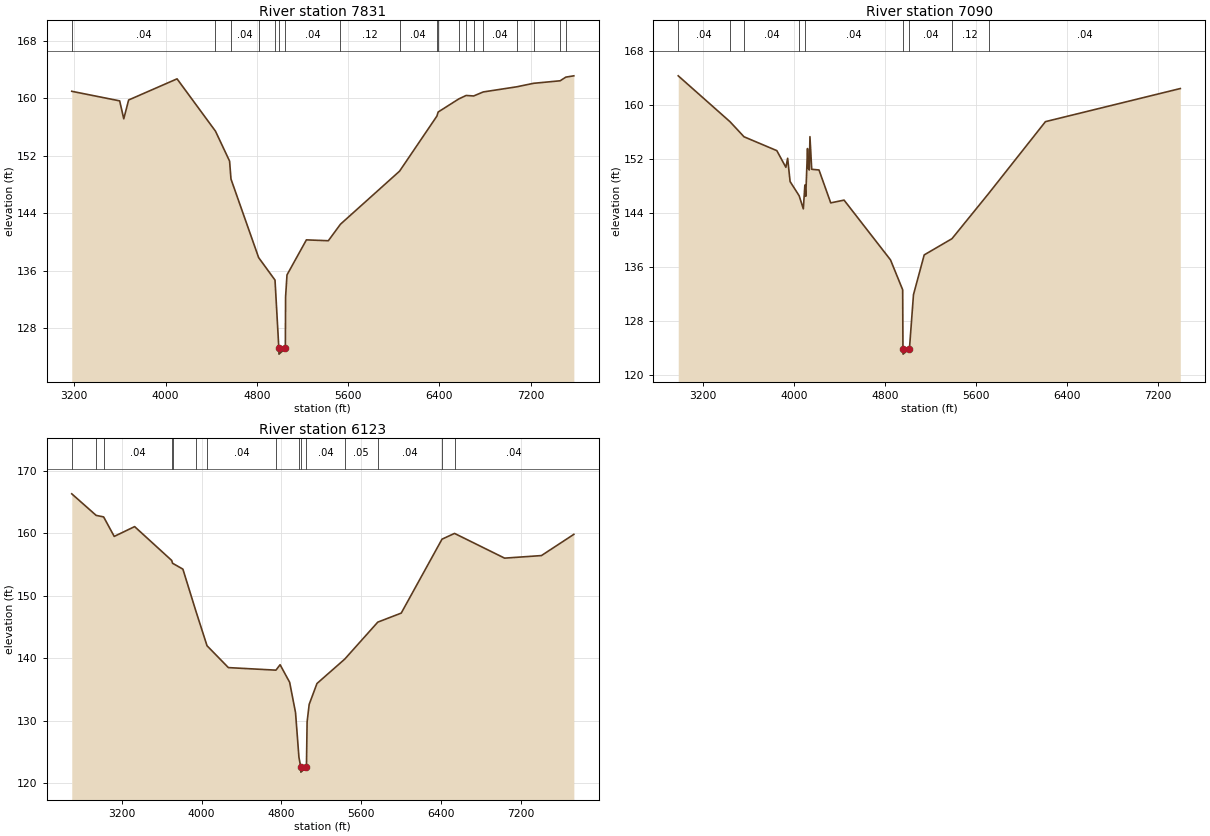
Type RM Length L Ch R = 1,7831,741,741,741
BEGIN DESCRIPTION:
Mapping XS 5c2ce228
END DESCRIPTION:
XS GIS Cut Line= 4
      2544714.94     13568341.64      2543327.11     13569595.98
      2541929.54     13570707.09      2541226.38     13570950.16
#Sta/Elev= 30
  3177.5  160.95  3597.3  159.62  3633.2  157.13  3675.8  159.74  4100.2  162.68
  4436.9  155.41  4560.5  151.25  4572.9  148.75  4815.1  137.84  4958.7  134.71
  4992.4  125.22  4993.7  124.42  5049.3  125.22  5051.4  132.38  5063.7  135.43
  5233.8  140.30  5426.0  140.18  5532.5  142.48  6050.3  149.85  6377.3  157.50
  6388.6  158.07  6569.3  159.89  6633.7  160.37  6699.3  160.30  6783.7  160.86
  7075.3  161.57  7224.8  162.06  7457.4  162.41  7507.6  162.92  7577.6  163.10
#Mann=19,-1,0
  3177.5    0.04       0  4436.9   0.013       0  4572.9    0.04       0
  4815.1    0.05       0  4958.7    0.04       0  4992.4    0.04       0
  5049.3    0.04       0  5532.5    0.12       0  6050.3    0.04       0
  6377.3    0.05       0  6388.6    0.04       0  6569.3    0.05       0
  6633.7    0.04       0  6699.3    0.05       0  6783.7    0.04       0
  7075.3   0.013       0  7224.8    0.04       0  7457.4    0.05       0
  7507.6    0.04       0
Bank Sta=4992.4,5049.3
Exp/Cntr=0.3,0.1

Type RM Length L Ch R = 1,7090,967,967,967
BEGIN DESCRIPTION:
Mapping XS c30223c2
END DESCRIPTION:
XS GIS Cut Line= 3
      2544689.93     13567920.65      2542901.76     13569005.70
      2541122.29     13570490.04
#Sta/Elev= 30
  2984.2  164.29  3438.9  157.50  3561.9  155.27  3850.0  153.22  3929.5  150.75
  3945.0  152.09  3966.4  148.65  4045.9  146.55  4082.7  144.61  4096.3  148.13
  4104.0  146.47  4119.5  153.53  4125.3  150.64  4135.0  150.36  4140.8  155.29
  4156.3  150.46  4220.3  150.36  4323.4  145.49  4440.4  145.90  4848.4  137.05
  4955.1  132.63  4957.5  123.91  4958.8  123.11  5014.6  123.91  5050.0  131.91
  5144.1  137.79  5388.0  140.19  5709.7  146.87  6208.8  157.51  7393.1  162.41
#Mann=9,-1,0
  2984.2    0.04       0  3438.9   0.013       0  3561.9    0.04       0
  4045.9    0.05       0  4096.3    0.04       0  4957.5    0.04       0
  5014.6    0.04       0  5388.0    0.12       0  5709.7    0.04       0
Bank Sta=4957.5,5014.6
Exp/Cntr=0.3,0.1

Type RM Length L Ch R = 1,6123,0,0,0
BEGIN DESCRIPTION:
Mapping XS e485ba1b
END DESCRIPTION:
XS GIS Cut Line= 3
      2544507.64     13567017.87      2542502.46     13568163.69
      2540740.29     13570238.35
#Sta/Elev= 30
  2698.4  166.34  2942.6  162.89  3017.8  162.64  3123.9  159.52  3328.3  161.09
  3700.0  155.67  3708.5  155.22  3812.1  154.28  3938.7  147.74  4053.9  142.01
  4267.8  138.51  4744.6  138.10  4786.1  138.97  4881.8  136.16  4940.8  131.31
  4974.8  124.18  4993.1  122.57  4994.4  121.77  5050.2  122.57  5056.8  129.81
  5077.6  132.62  5155.6  135.96  5434.0  139.87  5765.0  145.79  6000.2  147.24
  6408.8  159.08  6534.2  160.00  7036.0  156.04  7405.0  156.45  7729.9  159.85
#Mann=15,-1,0
  2698.4    0.04       0  2942.6   0.013       0  3017.8    0.04       0
  3700.0    0.05       0  3708.5    0.12       0  3938.7    0.05       0
  4053.9    0.04       0  4744.6    0.05       0  4974.8    0.04       0
  4993.1    0.04       0  5050.2    0.04       0  5434.0    0.05       0
  5765.0    0.04       0  6408.8   0.013       0  6534.2    0.04       0
Bank Sta=4993.1,5050.2
Exp/Cntr=0.3,0.1

Chan Stop Cuts=-1