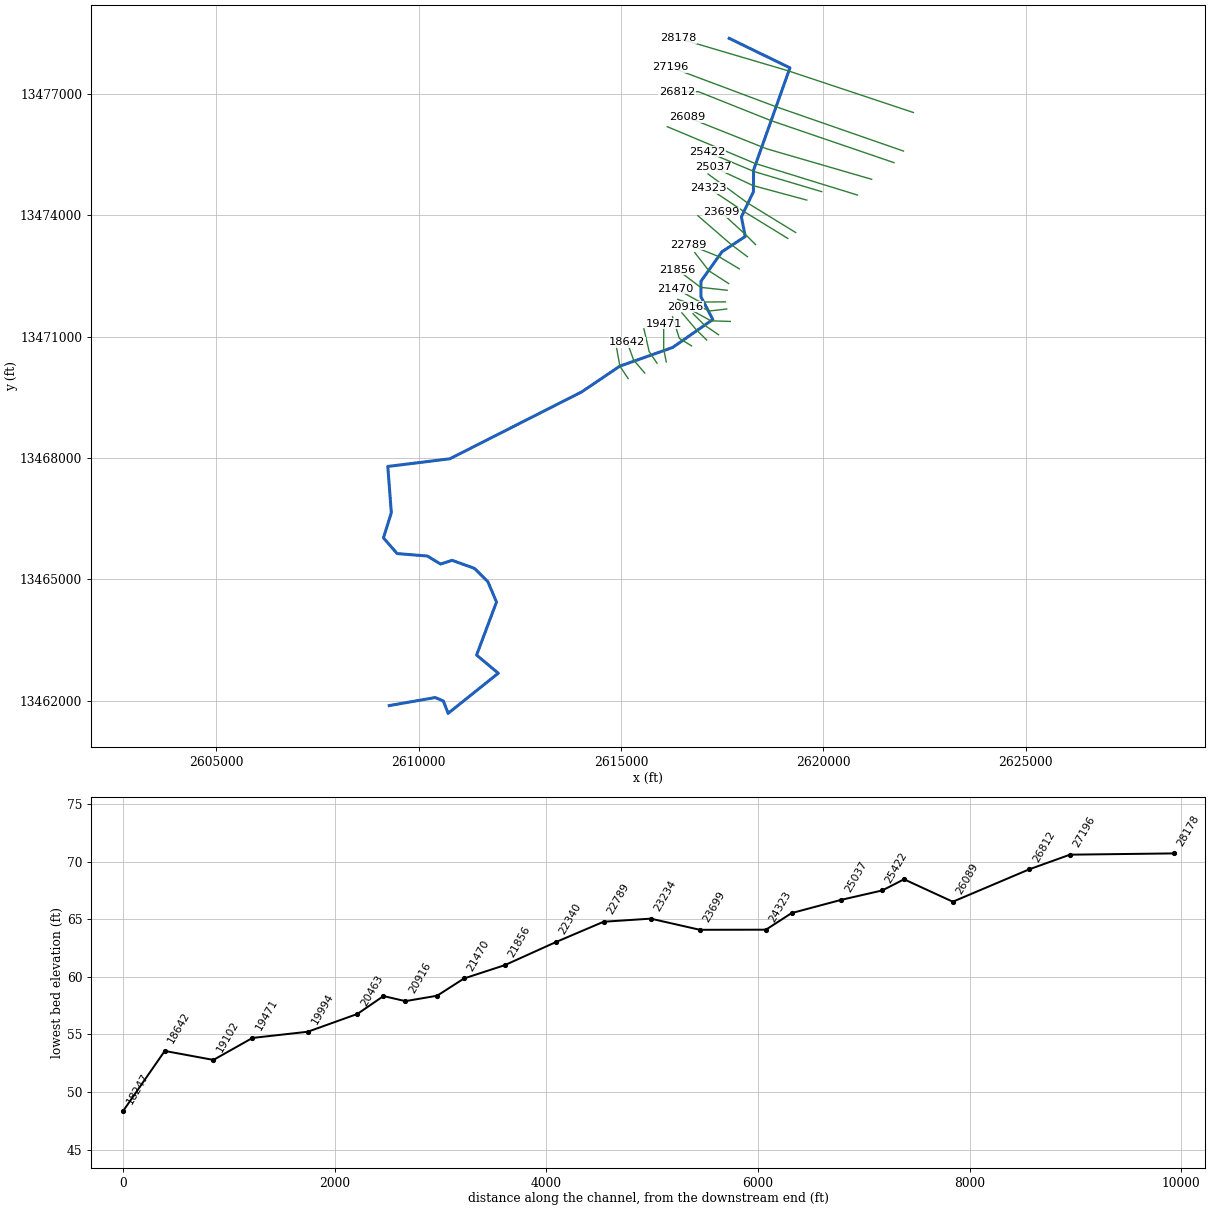
--- JIM BRANCH OUTFALL.prj (project) ---

Proj Title=JIM BRANCH OUTFALL Base Level Engineering
Current Plan=p01
Default Exp/Contr=0.3,0.1
English Units
Geom File=g01
Flow File=f01
Plan File=p01
Y Axis Title=Elevation
X Axis Title(PF)=Main Channel Distance
X Axis Title(XS)=Station
BEGIN DESCRIPTION:
JIM BRANCH OUTFALL
END DESCRIPTION:
DSS Export Rating Curves= 0
DSS Export Rating Curve Sorted= 0
DSS Export Volume Flow Curves= 0
DXF OffsetX= 0
DXF OffsetY= 0
DXF ScaleX= 1
DXF ScaleY= 10

--- JIM BRANCH OUTFALL.p01 (plan) ---

Plan Title=Multiple Run
Program Version=4.10
Short Identifier=Multiple
Geom File=g01
Flow File=f01
Subcritical Flow
K Sum by GR= 0
Std Step Tol= 0.01
Critical Tol= 0.01
Num of Std Step Trials= 20
Max Error Tol= 0.3
Flow Tol Ratio= 0.001
Split Flow NTrial= 30
Split Flow Tol= 0.02
Split Flow Ratio= 0.02
Log Output Level= 0
Friction Slope Method= 1
Unsteady Friction Slope Method= 2
Unsteady Bridges Friction Slope Method= 1
Parabolic Critical Depth
Global Vel Dist= 1 , 1 , 1
Global Log Level= 0
CheckData=True
Encroach Param=-1 ,0,0, 0
BEGIN DESCRIPTION:
Multiple Run
END DESCRIPTION:
Computation Interval=1HOUR
Output Interval=1HOUR
Run HTab= 0
Run UNet= 0
Run PostProcess= 0
Run WQNet= 0
UNET Theta= 1
UNET Theta Warmup= 1
UNET ZTol= 0.02
UNET ZSATol= 0.05
UNET MxIter= 20
UNET MaxInSteps= 0
UNET DtIC= 0
UNET DtMin= 0
UNET MaxCRTS= 20
UNET WFStab= 2
UNET SFStab= 1
UNET WFX= 1
UNET SFX= 1
UNET DSS MLevel= 4
UNET DZMax Abort= 100
UNET Convert EG Bridges= 0
UNET Use Existing IB Tables=-1
UNET Froude Reduction=False
UNET Froude Limit= 1
UNET Froude Power= 10
UNET Time Slicing=0,0, 5
UNET Junction Losses=0
Instantaneous Interval=1HOUR
Write IC File= 0
Write IC File at Sim End=0
Echo Input=False
Echo Parameters=False
Echo Output=False
Write Detailed= 0
WQ AD Non Conservative
WQ ULTIMATE=-1
WQ Max Comp Step=1HOUR
WQ Output Interval=15MIN
WQ Output Selected Increments= 0
WQ Output face flow=0
WQ Output face velocity=0
WQ Output face area=0
WQ Output face dispersion=0
WQ Output cell volume=0
WQ Output cell surface area=0
WQ Output cell continuity=0
WQ Output cumulative cell continuity=0
WQ Output face conc=0
WQ Output face dconc_dx=0
WQ Output face courant=0
WQ Output face peclet=0
WQ Output face adv mass=0
WQ Output face disp mass=0
WQ Output cell mass=0
WQ Output cell source sink temp=0
WQ Output cell source sink nsm=0
WQ Output MaxMinRange=-1
WQ Daily Max Min Mean=-1
WQ Daily Range=0
WQ Daily Time=0
WQ Create Restart=0
WQ Fixed Restart=0
WQ System Summary=0
WQ Use Fixed Temperature=0
Sorting and Armoring Iterations= 10
XS Update Threshold= 0.02
Hydraulics Update Threshold= 0.02
Energy Slope Method= 1
Volume Change Method= 0
XS Weighting Method= 0
Number of US Weighted Cross Sections= 1
Number of DS Weighted Cross Sections= 1
Upstream XS Weight=0.25
Main XS Weight=0.5
Downstream XS Weight=0.25
Number of DS XS's Weighted with US Boundary= 1
Upstream Boundary Weight= 1
Weight of XSs Associated with US Boundary= 0
Number of US XS's Weighted with DS Boundary= 1
Downstream Boundary Weight= 0.5
Weight of XSs Associated with DS Boundary= 0.5
Sediment Output Level= 4
Mass or Volume Output= 0
Output Increment Type= 1
Profile and TS Output Increment= 10
XS Output Flag= 0
XS Output Increment= 10
Disregard all LS=0
Disregard all Conn=0
Disregard all Breaches=0
Disregard all Pumps=0

--- JIM BRANCH OUTFALL.f01 (steady flow) ---

Flow Title=Multiple
Number of Profiles=7
Profile Names=10-year,25-year,50-year,1pct_min,100-year,1pct_plu,500-year
River Rch & RM= JIM BRANCH OUTFA,Reach-1,28178
     781    1211    1582     998    1991    3972    3115
River Rch & RM= JIM BRANCH OUTFA,Reach-1,26089
     967    1516    1997    1268    2530    5049    4019
River Rch & RM= JIM BRANCH OUTFA,Reach-1,23699
    1288    2059    2747    1767    3526    7035    5744
Boundary for River Rch & Prof#=JIM BRANCH OUTFA,Reach-1,1
Up Type=0
Dn Type=3
Dn Slope=0.005
Boundary for River Rch & Prof#=JIM BRANCH OUTFA,Reach-1,2
Up Type=0
Dn Type=3
Dn Slope=0.005
Boundary for River Rch & Prof#=JIM BRANCH OUTFA,Reach-1,3
Up Type=0
Dn Type=3
Dn Slope=0.005
Boundary for River Rch & Prof#=JIM BRANCH OUTFA,Reach-1,4
Up Type=0
Dn Type=3
Dn Slope=0.005
Boundary for River Rch & Prof#=JIM BRANCH OUTFA,Reach-1,5
Up Type=0
Dn Type=3
Dn Slope=0.005
Boundary for River Rch & Prof#=JIM BRANCH OUTFA,Reach-1,6
Up Type=0
Dn Type=3
Dn Slope=0.005
Boundary for River Rch & Prof#=JIM BRANCH OUTFA,Reach-1,7
Up Type=0
Dn Type=3
Dn Slope=0.005

--- JIM BRANCH OUTFALL.g01 (geometry) ---

Geom Title=Existing Conditions
Program Version=4.10

River Reach=JIM BRANCH OUTFA,Reach-1
Reach XY= 30
        2617675.       13478375.      2619175.36     13477645.21
      2618277.26     13475119.06      2618272.76     13474580.93
      2617975.51     13473959.79      2618071.56     13473476.25
      2617497.86     13473098.84      2616977.24     13472369.07
      2616977.24     13471980.93      2617269.92     13471422.69
       2616277.3     13470730.83      2614972.68     13470269.23
      2614027.29     13469630.85      2610773.45     13467978.75
      2609237.91      13467788.5      2609325.39     13466645.13
      2609130.83      13466022.7      2609468.24     13465634.12
      2610218.89      13465573.2      2610540.27     13465375.37
      2610828.32     13465466.96       2611377.3     13465269.17
      2611711.38     13464938.21      2611924.47     13464435.47
      2611432.29     13463124.91      2611968.02     13462675.21
      2610728.32     13461682.58       2610611.8     13461988.73
      2610409.78      13462074.5        2609275.       13461875.

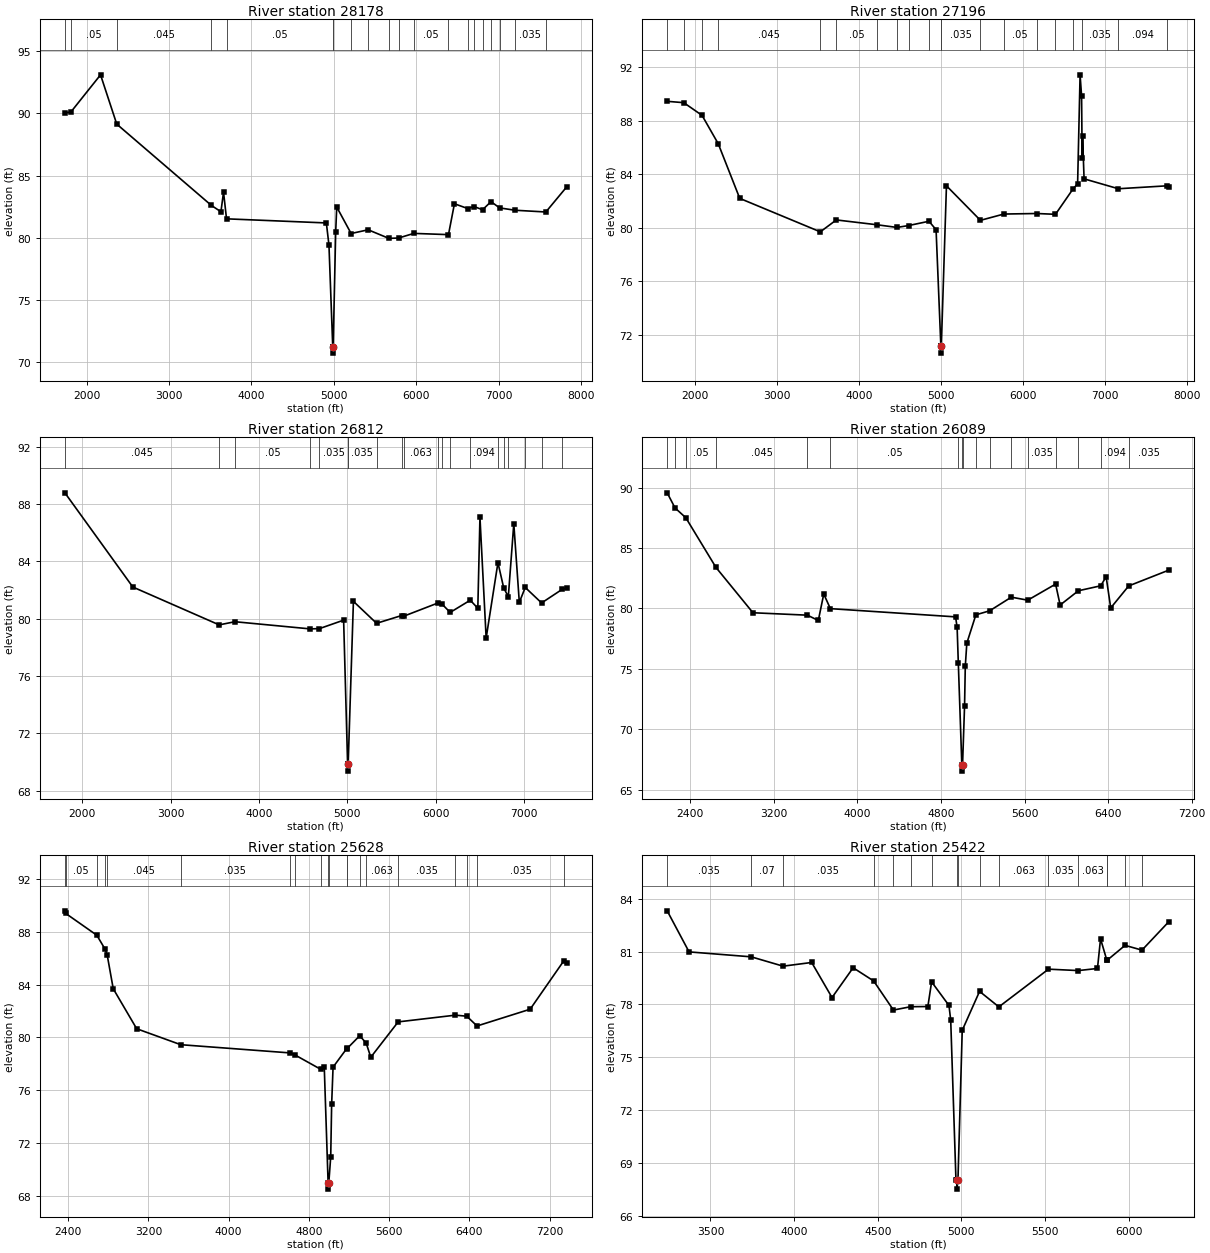
Type RM Length L Ch R = 1 ,28178   ,982,982,982
BEGIN DESCRIPTION:
Mapping XS 0d345d8f
END DESCRIPTION:
XS GIS Cut Line= 3
      2622225.62     13476540.69      2619131.87     13477571.94
      2616419.19     13478373.77
#Sta/Elev= 30
  1735.6   90.06  1806.9    90.1  2168.4    93.1  2365.2   89.14  3513.4   82.61
  3629.6    82.1  3661.2   83.67  3697.6   81.53  4909.1    81.2  4940.7   79.43
  4986.8   71.24  4987.2   70.74  4991.9   71.24  5022.3   80.45  5035.1   82.48
  5209.7   80.35  5416.6   80.65    5668   79.96  5787.2   79.99  5970.9   80.36
  6391.4   80.26  6463.7   82.74  6623.7   82.36  6701.4   82.52  6804.8   82.26
  6908.1   82.91  7011.4   82.41  7198.8   82.22  7573.3   82.08  7825.4   84.09
#Mann= 20 ,-1 , 0
  1735.6    .063       0  1806.9     .05       0  2365.2    .045       0
  3513.4    .035       0  3697.6     .05       0  4986.8    .035       0
  4991.9     .05       0  5209.7     .07       0  5416.6     .07       0
    5668     .05       0  5787.2    .035       0  5970.9     .05       0
  6391.4    .063       0  6623.7     .05       0  6701.4    .035       0
  6804.8    .035       0  6908.1     .05       0  7011.4    .035       0
  7198.8    .035       0  7573.3    .094       0
Bank Sta=4986.8,4991.9
XS Rating Curve= 0 ,0
Exp/Cntr=0.3,0.1

Type RM Length L Ch R = 1 ,27196   ,384,384,384
BEGIN DESCRIPTION:
Mapping XS 876fbfdd
END DESCRIPTION:
XS GIS Cut Line= 3
      2621980.85     13475587.56      2618824.58     13476686.52
      2616226.26     13477660.24
#Sta/Elev= 30
  1658.5   89.44  1860.8   89.34  2083.6   88.39  2281.1   86.27  2543.1   82.19
  3525.4   79.69  3720.3   80.58  4215.1   80.22  4460.3   80.02  4601.1   80.16
  4850.1   80.48  4936.6   79.85  4995.2   71.13  4995.6   70.63  5000.4   71.13
  5063.2   83.13  5477.4   80.55    5763   81.02  6162.5   81.06  6392.4      81
  6604.5   82.88  6662.1   83.28  6692.3   91.42  6710.6   89.83  6717.3   85.24
  6722.6   86.82  6740.9   83.65  7158.9   82.91  7756.2   83.13  7775.4   83.06
#Mann= 20 ,-1 , 0
  1658.5     .05       0  1860.8     .07       0  2083.6     .12       0
  2281.1    .045       0  3525.4    .035       0  3720.3     .05       0
  4215.1     .07       0  4460.3     .12       0  4601.1     .12       0
  4850.1    .035       0  4995.2    .035       0  5000.4    .035       0
  5477.4     .07       0    5763     .05       0  6162.5     .05       0
  6392.4    .094       0  6604.5    .063       0  6710.6    .035       0
  7158.9    .094       0  7756.2     .12       0
Bank Sta=4995.2,5000.4
XS Rating Curve= 0 ,0
Exp/Cntr=0.3,0.1

Type RM Length L Ch R = 1 ,26812   ,723,723,723
BEGIN DESCRIPTION:
Mapping XS d76cf93a
END DESCRIPTION:
XS GIS Cut Line= 4
      2621746.49     13475301.09       2618715.2     13476337.57
      2616913.12     13477056.32      2616381.84      13477045.9
#Sta/Elev= 30
  1804.8   88.77  2573.4    82.2    3550   79.56  3728.3   79.78  4579.6   79.28
  4684.5    79.3  4957.6   79.89  5002.7   69.86  5003.2   69.36  5009.1   69.86
  5068.4    81.2  5330.3   79.67  5612.5   80.21  5643.6   80.18  6021.7   81.08
  6073.7   80.99  6162.8   80.43  6389.9   81.28  6475.4   80.72  6499.6   87.06
  6569.7   78.64    6703    83.9  6768.6   82.13  6820.5   81.53  6882.4   86.62
  6944.8   81.13  7011.8   82.17  7196.7   81.09  7427.3   82.03  7479.9   82.15
#Mann= 20 ,-1 , 0
  1804.8    .045       0    3550    .035       0  3728.3     .05       0
  4579.6     .07       0  4684.5    .035       0  5002.7    .035       0
  5009.1    .035       0  5330.3    .063       0  5612.5    .035       0
  5643.6    .063       0  6021.7     .05       0  6073.7    .063       0
  6162.8     .05       0  6389.9    .094       0    6703    .063       0
  6768.6    .035       0  6820.5    .094       0  7011.8     .12       0
  7196.7    .094       0  7427.3    .035       0
Bank Sta=5002.7,5009.1
XS Rating Curve= 0 ,0
Exp/Cntr=0.3,0.1

Type RM Length L Ch R = 1 ,26089   ,461,461,461
BEGIN DESCRIPTION:
Mapping XS 0b83f1e0
END DESCRIPTION:
XS GIS Cut Line= 3
      2621194.36     13474889.65      2618595.41     13475644.86
      2616647.46     13476420.91
#Sta/Elev= 30
  2178.5   89.56  2253.6   88.31  2356.8    87.5  2645.4   83.39  2999.7   79.64
  3520.8   79.44  3625.3      79  3677.4   81.19  3740.7   79.98  4939.2    79.3
  4954.1   78.44  4965.6   75.47  4999.3   67.04  4999.8   66.54    5006   67.04
  5025.3   71.92  5032.3   75.21  5046.9   77.12  5133.6   79.47  5265.3    79.8
  5473.2   80.93  5630.2   80.68  5896.9   82.01  5940.3   80.28  6115.1   81.46
    6329   81.87  6380.6   82.62  6424.7   80.04  6596.9   81.86  6981.8   83.17
#Mann= 17 ,-1 , 0
  2178.5    .035       0  2253.6     .07       0  2356.8     .05       0
  2645.4    .045       0  3520.8    .035       0  3740.7     .05       0
  4965.6    .035       0  4999.3    .035       0    5006    .035       0
  5133.6     .07       0  5265.3     .05       0  5473.2    .063       0
  5630.2    .035       0  5896.9    .063       0  6115.1    .035       0
    6329    .094       0  6596.9    .035       0
Bank Sta=4999.3,5006
XS Rating Curve= 0 ,0
Exp/Cntr=0.3,0.1

Type RM Length L Ch R = 1 ,25628   ,206,206,206
BEGIN DESCRIPTION:
Mapping XS 71d9c604
END DESCRIPTION:
XS GIS Cut Line= 3
      2620845.38     13474499.03      2618313.55     13475281.75
      2616144.45     13476190.44
#Sta/Elev= 30
  2367.6   89.59  2374.7    89.4    2686   87.74  2769.2   86.67  2789.7   86.23
  2849.8   83.68  3083.4   80.65    3523   79.44  4608.3   78.82  4657.5   78.68
    4917   77.58  4953.3   77.75  4991.6   68.99  4992.1   68.49  4998.8   68.99
  5017.7   70.94  5026.9   74.91  5041.1   77.74  5176.7   79.14  5182.5   79.16
  5306.8   80.12  5371.2   79.56  5417.2   78.49    5690   81.17  6260.7   81.68
  6373.9    81.6  6476.3   80.86  7005.8   82.13  7343.1   85.82  7369.4   85.65
#Mann= 20 ,-1 , 0
  2367.6     .07       0  2374.7     .05       0    2686    .045       0
  2769.2     .05       0  2789.7    .045       0    3523    .035       0
  4608.3     .05       0  4657.5    .035       0    4917    .063       0
  4991.6    .035       0  4998.8    .063       0  5176.7     .07       0
  5182.5    .063       0  5306.8    .035       0  5371.2    .063       0
    5690    .035       0  6260.7    .063       0  6373.9    .094       0
  6476.3    .035       0  7343.1    .063       0
Bank Sta=4991.6,4998.8
XS Rating Curve= 0 ,0
Exp/Cntr=0.3,0.1

Type RM Length L Ch R = 1 ,25422   ,385,385,385
BEGIN DESCRIPTION:
Mapping XS 1e98a010
END DESCRIPTION:
XS GIS Cut Line= 3
      2619959.35     13474583.84      2618292.72     13475080.36
      2617129.81     13475566.35
#Sta/Elev= 30
  3241.3   83.31  3372.1   80.98  3743.7    80.7  3934.2   80.17  4105.1   80.38
  4226.7   78.39  4352.9   80.08  4475.7   79.33  4593.7   77.68  4697.1   77.87
  4799.6   77.88    4822   79.28  4925.8   77.94  4936.2   77.11  4967.5   68.06
  4972.3   68.02  4972.8   67.52  4979.5   68.02  5005.1   76.53  5108.7   78.74
    5224   77.86  5520.7      80  5699.3   79.92  5813.5   80.04  5831.9   81.72
  5869.4   80.51  5870.6    80.5  5978.4   81.35  6079.6   81.08  6240.7    82.7
#Mann= 17 ,-1 , 0
  3241.3    .035       0  3743.7     .07       0  3934.2    .035       0
  4475.7    .063       0  4593.7    .035       0  4697.1    .063       0
    4822     .07       0  4972.3    .035       0  4979.5     .07       0
  5108.7    .035       0    5224    .063       0  5520.7    .035       0
  5699.3    .063       0  5869.4    .035       0  5870.6    .063       0
  5978.4    .035       0  6079.6    .063       0
Bank Sta=4972.3,4979.5
XS Rating Curve= 0 ,0
Exp/Cntr=0.3,0.1

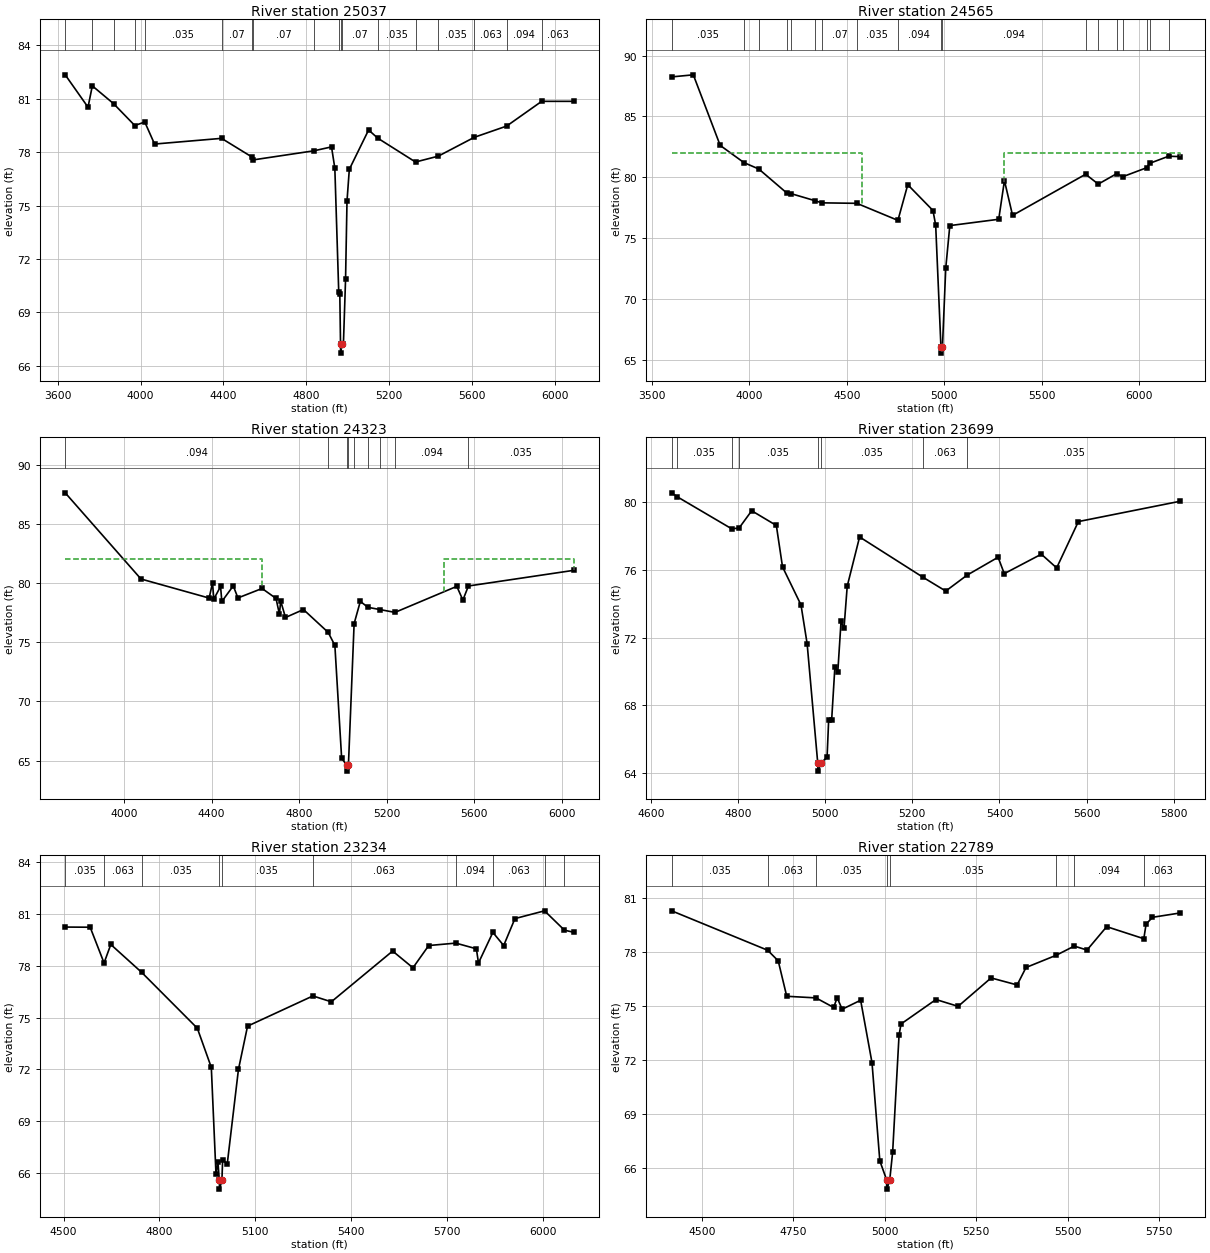
Type RM Length L Ch R = 1 ,25037   ,472,472,472
BEGIN DESCRIPTION:
Mapping XS e59be6c9
END DESCRIPTION:
XS GIS Cut Line= 3
       2619591.3     13474375.51      2618264.94     13474733.14
      2617287.36     13475190.73
#Sta/Elev= 30
  3636.6   82.35  3746.7   80.53  3767.4   81.73  3869.9   80.73  3972.5    79.5
  4020.5    79.7  4067.8   78.46  4391.1   78.78    4538   77.73  4544.2   77.57
  4836.7   78.08  4921.8    78.3  4937.8    77.1  4956.6   70.15  4961.8   70.02
  4965.2   67.21  4965.7   66.71  4972.4   67.21  4979.2   67.23  4989.5   70.85
  4996.5   75.26  5007.7   77.04  5100.7   79.25    5145   78.79  5327.1   77.45
    5437   77.78  5611.1   78.84  5766.9   79.47    5936   80.86  6089.7   80.86
#Mann= 18 ,-1 , 0
  3636.6     .07       0  3767.4     .05       0  3869.9    .035       0
  3972.5     .05       0  4020.5    .035       0  4391.1     .07       0
    4538    .035       0  4544.2     .07       0  4836.7    .094       0
  4956.6     .07       0  4965.2    .035       0  4972.4     .07       0
    5145    .035       0  5327.1    .063       0    5437    .035       0
  5611.1    .063       0  5766.9    .094       0    5936    .063       0
Bank Sta=4965.2,4972.4
XS Rating Curve= 0 ,0
Exp/Cntr=0.3,0.1

Type RM Length L Ch R = 1 ,24565   ,242,242,242
BEGIN DESCRIPTION:
Mapping XS 748c6f05
END DESCRIPTION:
XS GIS Cut Line= 3
      2619316.99     13473573.44      2618129.52     13474302.58
      2617151.25     13475020.68
#Sta/Elev= 30
  3601.3   88.25  3712.3   88.42  3850.1   82.62  3971.6   81.21  4048.1   80.68
  4190.8   78.72  4212.8   78.66  4335.7   78.08  4371.1    77.9  4551.1   77.86
  4761.6   76.46  4812.1   79.39  4941.4   77.27  4955.3   76.06  4982.3   66.05
  4982.8   65.55    4990   66.05  5006.9   72.53  5027.8   76.03  5278.6   76.55
  5307.9   79.73  5349.6   76.87  5724.3   80.25  5789.1   79.44  5884.9   80.31
  5913.5   80.04    6038   80.79  6053.2   81.15  6149.8   81.73  6208.3    81.7
#Mann= 18 ,-1 , 0
  3601.3    .035       0  3971.6    .063       0  4048.1    .035       0
  4190.8     .05       0  4212.8     .07       0  4335.7    .035       0
  4371.1     .07       0  4551.1    .035       0  4761.6    .094       0
  4982.3    .035       0    4990    .094       0  5724.3     .12       0
  5789.1    .094       0  5884.9     .12       0  5913.5    .094       0
    6038    .063       0  6053.2    .094       0  6149.8    .063       0
#XS Ineff= 2 , 0
       0  4577.6      82    5307       0      82
Permanent Ineff=
       F       F
Bank Sta=4982.3,4990
XS Rating Curve= 0 ,0
Exp/Cntr=0.3,0.1

Type RM Length L Ch R = 1 ,24323   ,624,624,624
BEGIN DESCRIPTION:
Mapping XS 1fea9760
END DESCRIPTION:
XS GIS Cut Line= 3
      2619122.58     13473427.58      2618035.77     13474094.25
      2617164.24     13474674.12
#Sta/Elev= 30
  3731.6   87.62  4077.7   80.34    4389   78.73  4404.5   80.02  4410.3   78.64
  4441.2   79.71    4447   78.44  4499.2   79.76  4520.5   78.74  4630.7   79.54
  4694.5    78.7    4710   77.37  4715.8   78.48  4737.7   77.09  4819.8   77.76
  4932.8   75.83  4963.3   74.73  4994.2   65.21  5017.3   64.61  5017.8   64.11
  5025.2   64.61  5051.2   76.57  5079.6   78.45    5114   77.95  5171.4   77.75
  5237.9   77.52  5520.2   79.72    5548   78.56  5573.3   79.75  6053.4   81.07
#Mann= 9 ,-1 , 0
  3731.6    .094       0  4932.8    .063       0  5017.3    .035       0
  5025.2    .063       0  5051.2    .035       0    5114    .063       0
  5171.4    .035       0  5237.9    .094       0  5573.3    .035       0
#XS Ineff= 2 , 0
       0  4630.7      82    5464       0      82
Permanent Ineff=
       F       F
Bank Sta=5017.3,5025.2
XS Rating Curve= 0 ,0
Exp/Cntr=0.3,0.1

Type RM Length L Ch R = 1 ,23699   ,465,465,465
BEGIN DESCRIPTION:
JIM BRANCH OUTFALL 29.0
END DESCRIPTION:
XS GIS Cut Line= 3
        2618325.       13473275.        2618075.       13473525.
      2617474.99     13474075.01
#Sta/Elev= 30
  4647.2   80.56  4659.1   80.34  4785.2   78.43  4802.1   78.48    4831    79.5
  4887.6   78.63  4901.8   76.18  4944.2   73.93  4958.3   71.64  4982.6    64.6
  4983.1    64.1  4990.7    64.6  5004.1   64.92  5007.8   67.14  5014.6   67.11
    5022   70.23  5028.8   69.99  5036.2   72.96    5043   72.55  5050.4   75.04
  5078.8   77.95  5224.8   75.56  5276.7   74.75  5325.6   75.69  5396.9   76.75
  5411.1   75.78  5496.2   76.93  5531.4   76.12  5581.3   78.86  5814.7   80.06
#Mann= 8 ,-1 , 0
  4647.2    .063       0  4659.1    .035       0  4785.2    .063       0
  4802.1    .035       0  4982.6    .035       0  4990.7    .035       0
  5224.8    .063       0  5325.6    .035       0
Bank Sta=4982.6,4990.7
XS Rating Curve= 0 ,0
Exp/Cntr=0.3,0.1

Type RM Length L Ch R = 1 ,23234   ,445,445,445
BEGIN DESCRIPTION:
JIM BRANCH OUTFALL 28.0
END DESCRIPTION:
XS GIS Cut Line= 3
        2618125.       13472975.        2617725.       13473275.
      2616900.02     13473988.93
#Sta/Elev= 30
  4505.2   80.25  4583.3   80.24  4626.8   78.17  4647.9   79.24  4744.8   77.62
  4918.7   74.39  4962.5   72.12  4977.1   65.95  4983.3   66.63  4987.6   65.57
  4988.1   65.07  4995.7   65.57  4997.9   66.76  5012.3   66.52  5047.4      72
  5075.9   74.51  5280.5   76.26  5338.1   75.92    5530   78.86  5593.6   77.89
    5643   79.18  5727.8   79.32  5792.1   78.99  5798.7   78.17  5843.7   79.94
  5877.6   79.18  5912.8   80.74  6005.4   81.19  6067.7   80.07  6096.2   79.95
#Mann= 10 ,-1 , 0
  4505.2    .035       0  4626.8    .063       0  4744.8    .035       0
  4987.6    .035       0  4995.7    .035       0  5280.5    .063       0
  5727.8    .094       0  5843.7    .063       0  6005.4    .094       0
  6067.7    .063       0
Bank Sta=4987.6,4995.7
XS Rating Curve= 0 ,0
Exp/Cntr=0.3,0.1

Type RM Length L Ch R = 1 ,22789   ,449,449,449
BEGIN DESCRIPTION:
JIM BRANCH OUTFALL 27.0
END DESCRIPTION:
XS GIS Cut Line= 3
      2617924.98     13472675.01        2617425.       13472975.
      2616675.04     13473274.98
#Sta/Elev= 30
  4416.9   80.27  4679.4   78.08  4708.4   77.49  4731.7   75.52  4811.7   75.43
    4860    74.9  4869.7   75.44  4883.4    74.8  4933.9    75.3    4965   71.83
  4986.4   66.37  5005.3    65.3  5005.8    64.8  5013.5    65.3  5021.5   66.86
    5039   73.36  5044.4   73.98    5140   75.34  5200.6   74.96  5290.8   76.54
  5362.1   76.15  5386.4   77.12    5469    77.8  5518.4   78.31  5553.3   78.09
  5607.1   79.39  5708.7   78.72  5714.9   79.53  5732.4   79.91  5807.7   80.15
#Mann= 8 ,-1 , 0
  4416.9    .035       0  4679.4    .063       0  4811.7    .035       0
  5005.3    .035       0  5013.5    .035       0    5469    .063       0
  5518.4    .094       0  5708.7    .063       0
Bank Sta=5005.3,5013.5
XS Rating Curve= 0 ,0
Exp/Cntr=0.3,0.1

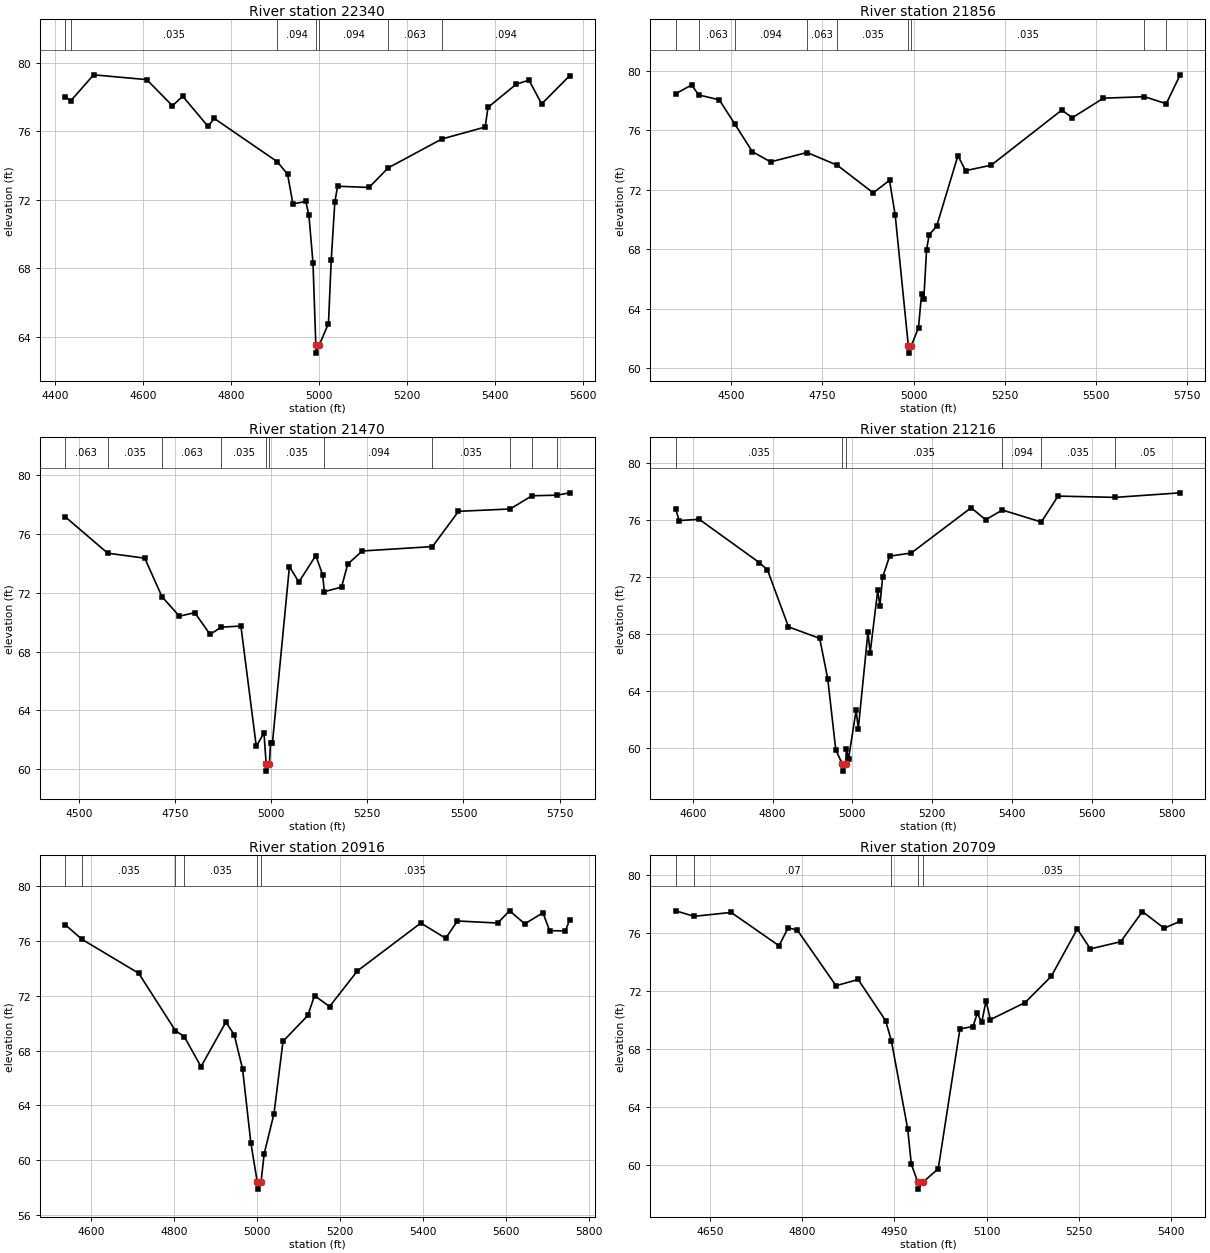
Type RM Length L Ch R = 1 ,22340   ,484,484,484
BEGIN DESCRIPTION:
JIM BRANCH OUTFALL 26.0
END DESCRIPTION:
XS GIS Cut Line= 3
      2617660.37      13472311.9        2617175.       13472625.
      2616824.99     13473075.01
#Sta/Elev= 30
  4422.4   78.02  4435.8   77.79  4487.5    79.3  4608.3   79.02  4666.8   77.49
  4690.1   78.05  4747.6   76.29    4762   76.75  4904.9   74.23  4928.6    73.5
  4940.9   71.76  4970.2    71.9  4977.2    71.1  4986.5   68.32  4992.9   63.54
  4993.4   63.04  5001.2   63.54  5021.7   64.77    5028   68.47  5036.2   71.87
  5042.5   72.79    5114   72.72  5157.3   73.86  5279.6   75.55  5378.2   76.25
  5384.6    77.4  5448.8   78.75  5477.8   78.99  5506.7    77.6  5570.1   79.24
#Mann= 7 ,-1 , 0
  4422.4    .063       0  4435.8    .035       0  4904.9    .094       0
  4992.9    .035       0  5001.2    .094       0  5157.3    .063       0
  5279.6    .094       0
Bank Sta=4992.9,5001.2
XS Rating Curve= 0 ,0
Exp/Cntr=0.3,0.1

Type RM Length L Ch R = 1 ,21856   ,386,386,386
BEGIN DESCRIPTION:
Mapping XS b7b4e17b
END DESCRIPTION:
XS GIS Cut Line= 3
      2617623.97     13472145.21      2616967.68     13472218.13
      2616389.75     13472655.49
#Sta/Elev= 30
    4347   78.46  4390.8   79.05    4410   78.38  4466.7   78.05  4509.2   76.43
  4557.3   74.57  4607.6   73.88  4707.6   74.51  4790.4   73.66  4889.3    71.8
  4934.1   72.64  4949.7    70.3  4985.7   61.53  4986.2   61.03  4994.1   61.53
  5013.7   62.75    5022      65  5028.3    64.7  5035.8   67.98  5042.8   68.97
  5063.6   69.57  5121.9    74.3  5142.7   73.29  5213.4   73.66  5406.9   77.36
    5436   76.85  5521.4   78.16    5634   78.26  5693.8   77.79  5732.1   79.73
#Mann= 9 ,-1 , 0
    4347    .035       0    4410    .063       0  4509.2    .094       0
  4707.6    .063       0  4790.4    .035       0  4985.7    .035       0
  4994.1    .035       0    5634    .063       0  5693.8    .035       0
Bank Sta=4985.7,4994.1
XS Rating Curve= 0 ,0
Exp/Cntr=0.3,0.1

Type RM Length L Ch R = 1 ,21470   ,254,254,254
BEGIN DESCRIPTION:
Mapping XS 9d4dcb91
END DESCRIPTION:
XS GIS Cut Line= 4
      2617582.25     13471858.76      2617045.81     13471853.55
      2616931.22     13471869.18      2616353.08     13472186.89
#Sta/Elev= 30
  4463.9    77.2  4574.9   74.71  4671.2   74.37    4716   71.75  4761.2   70.42
  4801.2   70.66  4841.2   69.18  4869.8   69.67  4921.2   69.75  4961.2   61.56
  4981.2   62.47  4986.9   60.37  4987.4   59.87  4995.4   60.37  4998.3   61.81
  5003.3   61.81  5047.4    73.8  5071.8   72.74    5116   74.55  5133.7   73.24
  5138.3   72.09  5182.9    72.4    5199   73.97  5236.9   74.86  5419.4   75.16
    5487   77.56  5621.4   77.72  5677.9   78.62  5743.4   78.66  5775.7   78.82
#Mann= 11 ,-1 , 0
  4463.9    .063       0  4574.9    .035       0    4716    .063       0
  4869.8    .035       0  4986.9    .035       0  4995.4    .035       0
  5138.3    .094       0  5419.4    .035       0  5621.4     .05       0
  5677.9    .035       0  5743.4     .05       0
Bank Sta=4986.9,4995.4
XS Rating Curve= 0 ,0
Exp/Cntr=0.3,0.1

Type RM Length L Ch R = 1 ,21216   ,300,300,300
BEGIN DESCRIPTION:
Mapping XS 2dc5e64f
END DESCRIPTION:
XS GIS Cut Line= 4
      2617613.51     13471681.67      2617202.06      13471634.8
      2617030.18     13471702.51      2616401.81     13471920.62
#Sta/Elev= 30
  4557.3   76.81  4565.9   75.98  4616.2   76.07  4767.2   73.02  4787.3   72.51
  4839.9   68.51  4918.1    67.7  4938.3   64.86  4958.4   59.86  4974.8   58.87
  4975.3   58.37  4983.3   58.87    4985   59.95  4990.4   59.25  5009.4   62.65
  5014.8   61.35  5039.1   68.15  5044.5   66.68  5063.5   71.07  5068.9   69.98
  5075.7   71.99  5093.3   73.48  5147.5    73.7  5297.5   76.88  5333.9   76.04
  5375.6   76.72  5473.4   75.88  5515.3    77.7  5658.6   77.61  5821.3   77.93
#Mann= 6 ,-1 , 0
  4557.3    .035       0  4974.8    .035       0  4983.3    .035       0
  5375.6    .094       0  5473.4    .035       0  5658.6     .05       0
Bank Sta=4974.8,4983.3
XS Rating Curve= 0 ,0
Exp/Cntr=0.3,0.1

Type RM Length L Ch R = 1 ,20916   ,207,207,207
BEGIN DESCRIPTION:
Mapping XS 65b46c44
END DESCRIPTION:
XS GIS Cut Line= 3
      2617702.09     13471374.38      2617222.89     13471390.01
      2616578.56     13471743.35
#Sta/Elev= 30
  4537.9   77.19  4578.8   76.11  4715.2   73.64  4803.5   69.46  4824.9   69.02
  4865.2   66.83  4925.2   70.08  4945.2   69.15  4965.2   66.67  4985.2   61.28
  5000.7    58.4  5001.2    57.9  5009.7    58.4  5017.2   60.47  5040.8   63.39
  5062.6   68.68  5122.3   70.56  5138.4   72.01  5174.6   71.21  5241.7   73.81
  5394.3    77.3  5454.1   76.19  5482.5   77.45  5579.2    77.3    5608   78.19
  5644.6   77.24  5688.2   78.05  5704.3   76.74  5742.2   76.73  5752.2    77.5
#Mann= 6 ,-1 , 0
  4537.9    .063       0  4578.8    .035       0  4803.5     .07       0
  4824.9    .035       0  5000.7    .035       0  5009.7    .035       0
Bank Sta=5000.7,5009.7
XS Rating Curve= 0 ,0
Exp/Cntr=0.3,0.1

Type RM Length L Ch R = 1 ,20709   ,246,246,246
BEGIN DESCRIPTION:
Mapping XS aa808d71
END DESCRIPTION:
XS GIS Cut Line= 3
       2617410.4     13471046.25      2617066.64     13471280.63
      2616780.16     13471567.11
#Sta/Elev= 30
    4594   77.55  4623.9   77.17  4684.3   77.44  4762.2   75.14  4777.1   76.38
    4792   76.22    4855   72.38    4891   72.81  4935.7   69.97  4945.2   68.56
  4971.6   62.51  4977.6   60.05    4988   58.84  4988.5   58.34    4997   58.84
  5021.4   59.75  5056.7    69.4  5077.9   69.56    5085   70.48  5092.1   69.85
  5099.2   71.34  5106.2   70.04  5162.8   71.22  5205.2   73.02  5247.7    76.3
  5268.9   74.92  5318.4   75.42  5353.7    77.5  5389.1   76.35  5415.2   76.83
#Mann= 5 ,-1 , 0
    4594    .035       0  4623.9     .07       0  4945.2    .035       0
    4988    .035       0    4997    .035       0
Bank Sta=4988,4997
XS Rating Curve= 0 ,0
Exp/Cntr=0.3,0.1

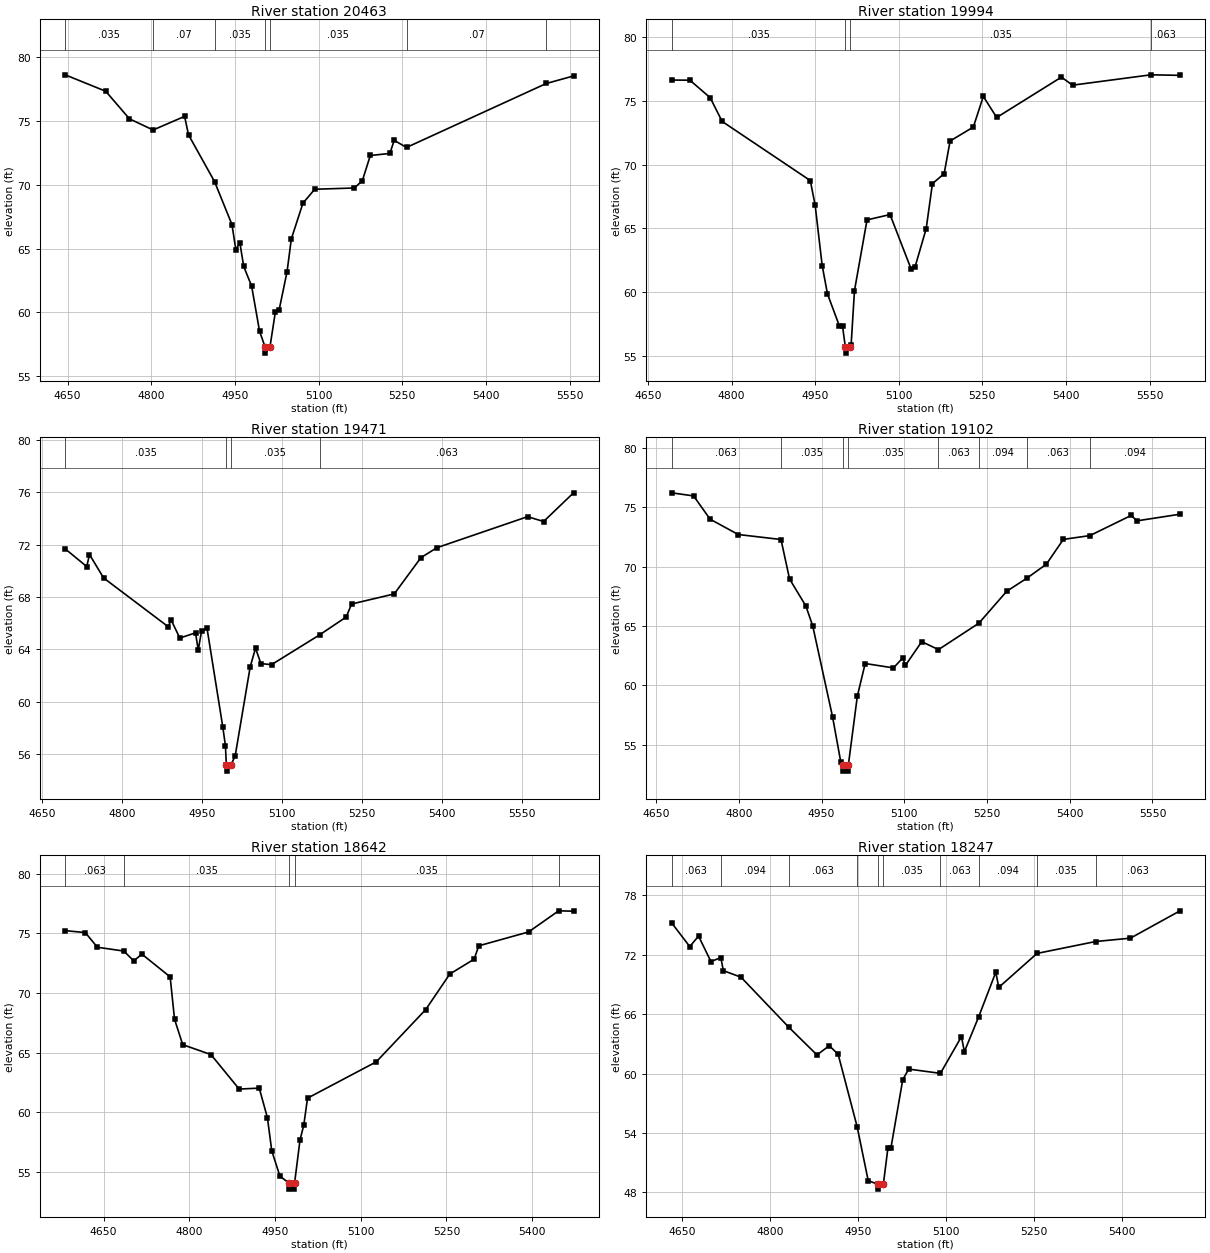
Type RM Length L Ch R = 1 ,20463   ,469,469,469
BEGIN DESCRIPTION:
Mapping XS 0315d3d1
END DESCRIPTION:
XS GIS Cut Line= 3
      2617118.75     13470916.02      2616868.72     13471160.84
      2616504.11     13471587.95
#Sta/Elev= 30
  4645.7   78.63  4718.4   77.34  4760.8   75.18  4803.3    74.3  4859.8   75.37
  4866.8   73.92  4913.5   70.25  4944.7   66.88  4951.7    64.9  4958.8   65.47
  4965.8   63.59    4980   62.05  4994.1   58.53  5003.9   57.29  5004.4   56.79
  5012.9   57.29  5022.6   60.04  5029.2   60.16  5043.5   63.18  5051.2   65.76
    5072   68.56  5093.1   69.65  5164.3   69.75  5178.5   70.32  5192.8    72.3
  5227.9   72.46  5235.6   73.49  5257.7   72.93  5508.3   77.95  5557.2   78.54
#Mann= 7 ,-1 , 0
  4645.7    .035       0  4803.3     .07       0  4913.5    .035       0
  5003.9    .035       0  5012.9    .035       0  5257.7     .07       0
  5508.3    .035       0
Bank Sta=5003.9,5012.9
XS Rating Curve= 0 ,0
Exp/Cntr=0.3,0.1

Type RM Length L Ch R = 1 ,19994   ,523,523,523
BEGIN DESCRIPTION:
Mapping XS 0922e2c5
END DESCRIPTION:
XS GIS Cut Line= 3
      2616743.74      13470770.2      2616441.64     13470957.72
      2616274.99     13471488.92
#Sta/Elev= 30
  4692.4   76.62  4725.1   76.61  4761.5   75.24    4783   73.38  4941.2   68.75
  4949.9   66.82  4962.5    62.1    4972   59.88  4993.2   57.39  4999.1   57.34
    5004   55.74  5004.5   55.24  5013.1   55.74  5014.5   55.91  5020.5   60.14
    5043   65.67  5084.3   66.09    5122   61.84    5129   61.96  5149.2   64.99
  5160.4   68.51  5181.4   69.29  5192.1   71.85  5233.8   72.94  5251.7   75.34
  5275.7   73.69  5391.9   76.85  5411.9   76.22  5552.4   77.03  5604.7   76.99
#Mann= 4 ,-1 , 0
  4692.4    .035       0    5004    .035       0  5013.1    .035       0
  5552.4    .063       0
Bank Sta=5004,5013.1
XS Rating Curve= 0 ,0
Exp/Cntr=0.3,0.1

Type RM Length L Ch R = 1 ,19471   ,369,369,369
BEGIN DESCRIPTION:
Mapping XS 5ee823c5
END DESCRIPTION:
XS GIS Cut Line= 3
      2616118.72      13470374.4      2616056.22     13470686.88
      2616056.22     13471321.11
#Sta/Elev= 30
  4693.5   71.67  4733.9   70.32    4739   71.24  4765.5   69.45  4886.8   65.72
  4891.9   66.26  4908.3   64.86  4937.8   65.26  4942.9   63.94  4949.1    65.4
  4959.3   65.62  4988.8    58.1  4993.9   56.62  4995.5    55.2    4996    54.7
  5004.6    55.2  5012.2   55.88  5040.3   62.67  5050.3   64.09  5060.3   62.91
  5080.3   62.83  5170.2    65.1  5220.3   66.47  5230.3   67.46  5310.3   68.23
  5360.3      71  5390.3   71.76  5560.3   74.13  5590.3   73.76  5646.4   75.95
#Mann= 4 ,-1 , 0
  4693.5    .035       0  4995.5    .035       0  5004.6    .035       0
  5170.2    .063       0
Bank Sta=4995.5,5004.6
XS Rating Curve= 0 ,0
Exp/Cntr=0.3,0.1

Type RM Length L Ch R = 1 ,19102   ,460,460,460
BEGIN DESCRIPTION:
Mapping XS 12ebd027
END DESCRIPTION:
XS GIS Cut Line= 3
      2615889.56     13470343.13      2615696.85     13470629.59
      2615566.87     13471191.09
#Sta/Elev= 30
  4678.3   76.22    4718   75.96    4748      74    4799   72.71  4876.5   72.29
    4892   68.97  4921.6   66.69    4934   65.02    4970   57.36    4985   53.53
  4989.2   53.29  4989.7   52.79  4998.1   52.79  4998.6   53.29  5014.9    59.1
  5029.1   61.85  5080.4   61.48    5097   62.31  5102.2    61.7  5131.7   63.69
    5162   63.02  5235.4   65.25  5285.7   67.93  5322.2   69.03  5357.6   70.21
  5388.4    72.3  5436.6   72.62  5511.5   74.32  5521.8   73.86  5599.9   74.42
#Mann= 8 ,-1 , 0
  4678.3    .063       0  4876.5    .035       0  4989.2    .035       0
  4998.6    .035       0    5162    .063       0  5235.4    .094       0
  5322.2    .063       0  5436.6    .094       0
Bank Sta=4989.2,4998.6
XS Rating Curve= 0 ,0
Exp/Cntr=0.3,0.1

Type RM Length L Ch R = 1 ,18642   ,395,395,395
BEGIN DESCRIPTION:
Mapping XS a5cdacf2
END DESCRIPTION:
XS GIS Cut Line= 3
      2615587.49     13470098.33      2615311.43     13470421.26
      2615155.18     13470858.75
#Sta/Elev= 30
  4582.9   75.22    4618   75.06  4639.2   73.83  4685.5   73.51  4702.8   72.69
  4717.1   73.25  4766.5   71.35  4774.2    67.8  4788.5   65.67  4837.9   64.84
  4887.3   61.95  4922.4   62.03  4936.7   59.55  4944.3   56.78  4958.6   54.65
  4974.8   54.07  4975.3   53.57  4983.7   53.57  4984.2   54.07  4993.7   57.68
  5000.3   58.93  5006.9   61.19  5127.1   64.23  5213.5    68.6  5255.9   71.59
  5298.4   72.83  5306.5   73.95  5393.6   75.11  5446.3   76.88  5472.3   76.85
#Mann= 5 ,-1 , 0
  4582.9    .063       0  4685.5    .035       0  4974.8    .035       0
  4984.2    .035       0  5446.3    .063       0
Bank Sta=4974.8,4984.2
XS Rating Curve= 0 ,0
Exp/Cntr=0.3,0.1

Type RM Length L Ch R = 1 ,18247   ,433,433,433
BEGIN DESCRIPTION:
Mapping XS a7bf2adc
END DESCRIPTION:
XS GIS Cut Line= 3
      2615176.03     13469962.89      2614972.89     13470270.22
      2614884.35     13470759.78
#Sta/Elev= 30
  4632.4   75.21  4663.2   72.82  4678.2   73.88  4699.3    71.3  4716.1   71.71
  4720.4   70.39  4750.5   69.73  4832.2   64.66  4879.9   61.88  4900.9   62.81
    4916   61.94  4948.3   54.64  4967.2   49.18  4983.5   48.83    4984   48.33
    4993   48.83  5000.7   52.46  5005.8   52.46    5026   59.37  5036.1   60.45
  5090.2   60.02    5126   63.72    5131   62.21  5155.1   65.69  5184.5   70.23
  5189.6    68.7  5254.8   72.13  5354.5   73.33  5413.8   73.67  5498.3   76.43
#Mann= 10 ,-1 , 0
  4632.4    .063       0  4716.1    .094       0  4832.2    .063       0
  4948.3    .035       0  4983.5    .035       0    4993    .035       0
  5090.2    .063       0  5155.1    .094       0  5254.8    .035       0
  5354.5    .063       0
Bank Sta=4983.5,4993
XS Rating Curve= 0 ,0
Exp/Cntr=0.3,0.1