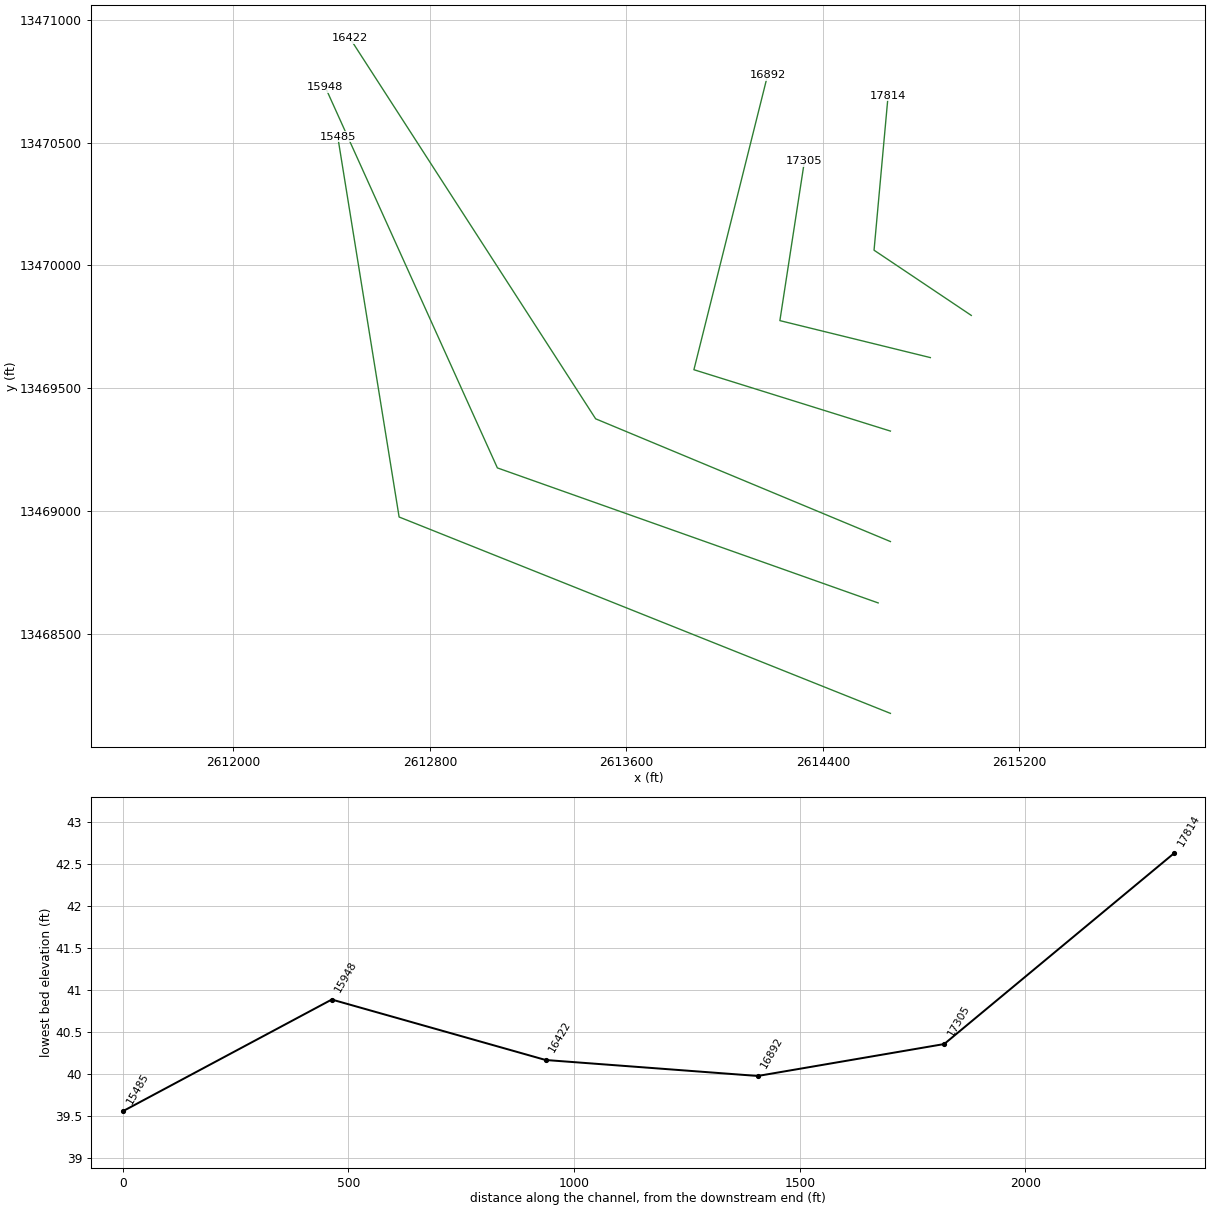
HEC-RAS study JIM BRANCH OUTFALL.prj: JIM BRANCH OUTFALL Base Level Engineering

--- JIM BRANCH OUTFALL.g01 (geometry) --- (continued)

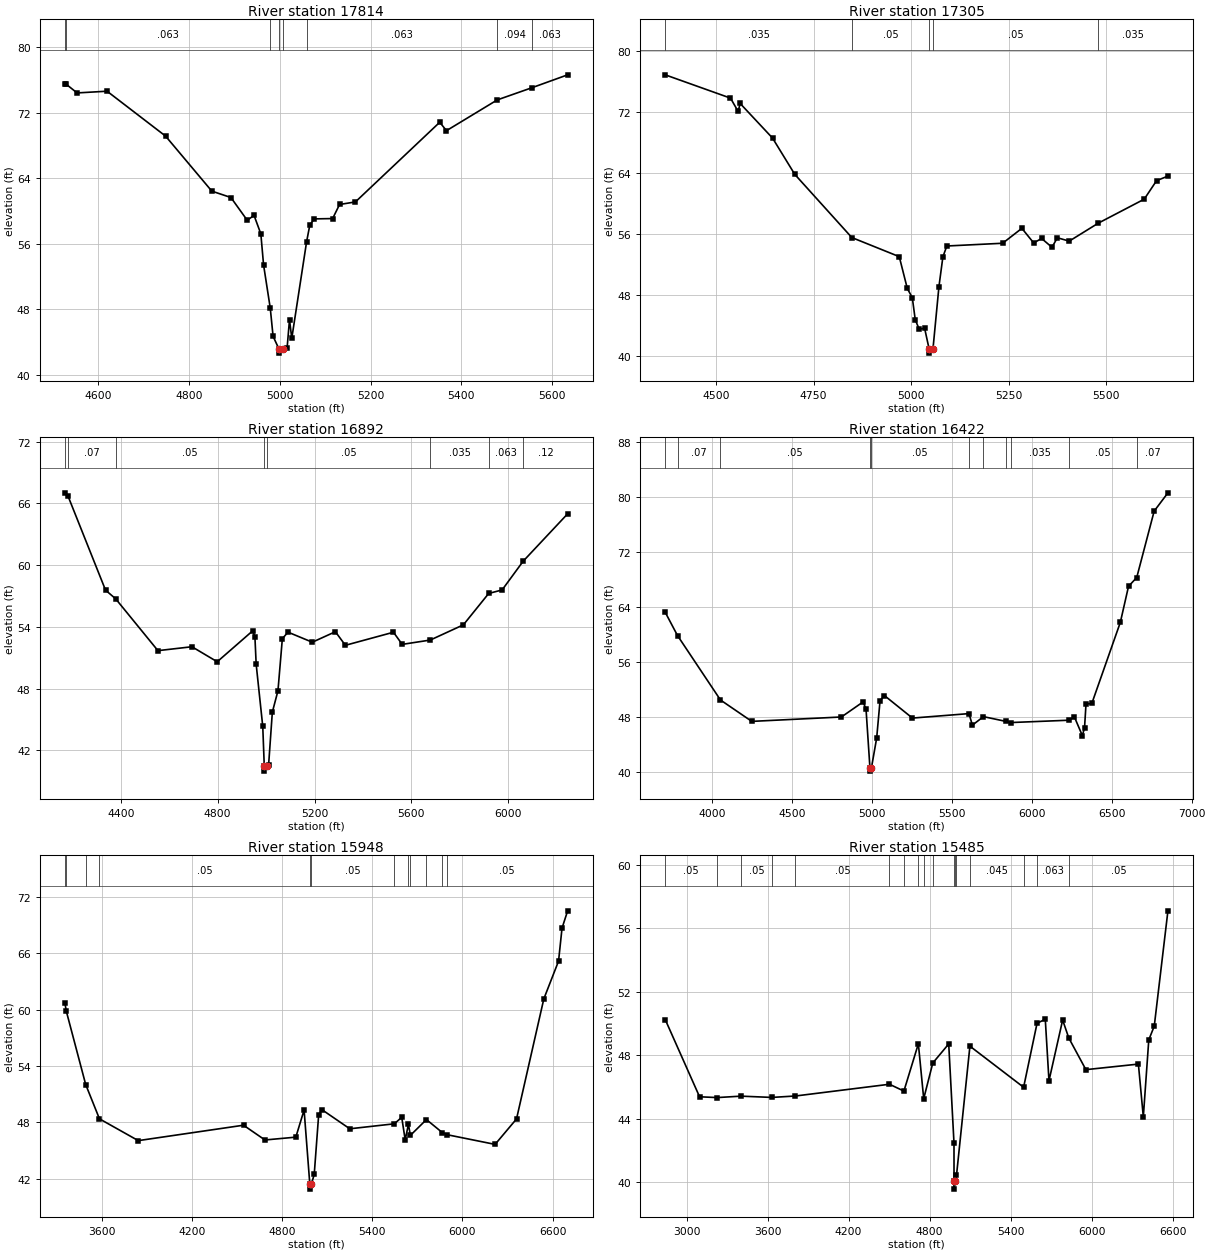
Type RM Length L Ch R = 1 ,17814   ,509,509,509
BEGIN DESCRIPTION:
Mapping XS f1342197
END DESCRIPTION:
XS GIS Cut Line= 3
      2615004.14     13469796.26      2614608.31     13470061.88
      2614665.51     13470691.09
#Sta/Elev= 30
  4526.1    75.5    4528    75.5    4553    74.4    4619   74.61    4748   69.13
    4850   62.41  4892.1   61.63  4928.1   58.85  4943.1   59.45  4958.1   57.19
  4964.1   53.41  4978.9   48.11  4985.1   44.68  4998.1   43.13  4998.6   42.63
  5007.6   43.13    5016   43.25  5021.3   46.71  5026.3   44.43    5059   56.23
  5066.2    58.3  5076.2   59.02  5116.4   59.06  5131.7   60.78  5166.6   61.09
  5352.6   70.82  5367.4   69.79  5479.5   73.55  5556.1   75.04  5634.6   76.61
#Mann= 8 ,-1 , 0
  4526.1    .094       0    4528    .063       0  4978.9    .035       0
  4998.1    .035       0  5007.6    .035       0    5059    .063       0
  5479.5    .094       0  5556.1    .063       0
Bank Sta=4998.1,5007.6
XS Rating Curve= 0 ,0
Exp/Cntr=0.3,0.1

Type RM Length L Ch R = 1 ,17305   ,413,413,413
BEGIN DESCRIPTION:
JIM BRANCH OUTFALL 15.0
END DESCRIPTION:
XS GIS Cut Line= 3
      2614837.44     13469624.39        2614225.       13469775.
      2614324.99     13470424.96
#Sta/Elev= 30
  4369.8   76.91  4537.1   73.85  4556.7    72.1  4561.8   73.15  4644.9    68.6
  4701.8   63.84    4848   55.54  4969.6   53.03  4990.2   48.85    5003   47.65
  5010.6   44.73  5020.7   43.51  5034.6   43.62  5046.3   40.86  5046.8   40.36
  5055.9   40.86  5071.3   49.11  5081.4      53  5091.5   54.43  5234.5   54.79
  5283.8   56.75  5314.1   54.83  5334.4   55.42  5360.9   54.26  5374.8   55.51
  5405.2   55.07    5480   57.44  5597.4   60.58    5629   63.01  5658.1   63.61
#Mann= 5 ,-1 , 0
  4369.8    .035       0    4848     .05       0  5046.3    .035       0
  5055.9     .05       0    5480    .035       0
Bank Sta=5046.3,5055.9
XS Rating Curve= 0 ,0
Exp/Cntr=0.3,0.1

Type RM Length L Ch R = 1 ,16892   ,470,470,470
BEGIN DESCRIPTION:
JIM BRANCH OUTFALL 14.0
END DESCRIPTION:
XS GIS Cut Line= 3
      2614674.96     13469325.01        2613875.       13469575.
      2614174.99     13470774.96
#Sta/Elev= 30
  4169.8   67.03  4182.1   66.74  4337.4   57.57  4379.2   56.73  4553.7   51.69
  4694.1   52.07  4798.4   50.61    4945   53.62    4954   53.03  4959.2   50.36
  4986.4   44.32  4992.6   40.48  4993.1   39.98  5002.2   40.48  5010.5   40.57
  5025.9   45.71  5049.1   47.79  5067.2   52.85  5090.4   53.49  5190.9   52.51
  5286.2   53.53  5327.4   52.21  5525.9   53.48  5561.9    52.3  5677.8   52.72
  5814.5    54.2    5919   57.25  5974.3   57.59  6061.1   60.38  6244.8   64.99
#Mann= 8 ,-1 , 0
  4169.8    .035       0  4182.1     .07       0  4379.2     .05       0
  4992.6    .035       0  5002.2     .05       0  5677.8    .035       0
    5919    .063       0  6061.1     .12       0
Bank Sta=4992.6,5002.2
XS Rating Curve= 0 ,0
Exp/Cntr=0.3,0.1

Type RM Length L Ch R = 1 ,16422   ,474,474,474
BEGIN DESCRIPTION:
JIM BRANCH OUTFALL 13.0
END DESCRIPTION:
XS GIS Cut Line= 3
      2614674.96     13468875.02        2613475.       13469375.
      2612475.02     13470924.97
#Sta/Elev= 30
    3707   63.26    3784   59.87  4052.6   50.51  4248.6    47.4  4809.2   48.04
  4944.7   50.23  4963.1   49.19  4987.5   40.67    4988   40.17  4997.1   40.67
  5029.7   44.98  5050.8   50.41  5078.4   51.15  5253.4   47.88  5607.2   48.53
  5628.3   46.85  5697.6   48.09  5837.8    47.4  5867.8   47.23  6233.1   47.57
  6266.5   48.05    6316   45.34  6329.8   46.43  6339.1   49.93  6375.4      50
    6554   61.81    6605   67.03  6656.4   68.31  6765.4   77.96  6851.5   80.62
#Mann= 11 ,-1 , 0
    3707     .05       0    3784     .07       0  4052.6     .05       0
  4987.5    .035       0  4997.1     .05       0  5607.2    .035       0
  5697.6     .05       0  5837.8     .12       0  5867.8    .035       0
  6233.1     .05       0  6656.4     .07       0
Bank Sta=4987.5,4997.1
XS Rating Curve= 0 ,0
Exp/Cntr=0.3,0.1

Type RM Length L Ch R = 1 ,15948   ,463,463,463
BEGIN DESCRIPTION:
JIM BRANCH OUTFALL 12.0
END DESCRIPTION:
XS GIS Cut Line= 3
      2614624.99       13468625.        2613075.       13469175.
      2612375.01     13470724.98
#Sta/Elev= 30
  3355.3   60.71  3363.7   59.87  3493.5   52.02    3585   48.37  3843.4   46.05
  4543.7   47.69  4686.5   46.12  4891.9   46.42  4946.9   49.31  4985.1   41.39
  4985.6   40.89  4994.7   41.39  5014.3   42.45  5043.9    48.8    5066   49.34
    5251   47.31  5547.3   47.84  5596.6   48.53  5619.7   46.13  5641.1   47.78
  5654.2   46.61  5761.1   48.29  5867.9   46.89  5895.5   46.69  6217.9   45.65
  6360.6   48.36  6542.2   61.13  6640.2   65.15  6663.3   68.65  6700.7    70.5
#Mann= 12 ,-1 , 0
  3355.3     .07       0  3363.7     .05       0  3493.5     .07       0
    3585     .05       0  4985.1    .035       0  4994.7     .05       0
  5547.3    .035       0  5641.1    .063       0  5654.2     .12       0
  5761.1     .05       0  5867.9     .12       0  5895.5     .05       0
Bank Sta=4985.1,4994.7
XS Rating Curve= 0 ,0
Exp/Cntr=0.3,0.1

Type RM Length L Ch R = 1 ,15485   ,0,0,0
BEGIN DESCRIPTION:
JIM BRANCH OUTFALL 11.0
END DESCRIPTION:
XS GIS Cut Line= 3
        2614675.       13468175.        2612675.       13468975.
        2612425.       13470525.
#Sta/Elev= 30
  2841.6   50.25  3096.1   45.38  3226.3   45.33  3402.6   45.42  3631.8   45.34
  3806.7   45.43  4502.8   46.17  4609.8   45.74  4716.9   48.72  4756.5   45.26
  4823.9   47.51  4941.8   48.71  4980.9   42.46  4981.1   40.06  4981.6   39.56
  4991.3   40.06  4999.4   40.42  5098.8   48.57  5496.6   45.98  5596.1   50.01
  5657.1   50.27  5684.5   46.39  5785.8   50.22  5831.1   49.09  5957.9   47.09
  6346.9   47.44  6383.4   44.11  6423.9   48.97  6464.4   49.83  6565.7    57.1
#Mann= 17 ,-1 , 0
  2841.6     .05       0  3226.3    .035       0  3402.6     .05       0
  3631.8    .035       0  3806.7     .05       0  4502.8    .035       0
  4609.8     .05       0  4716.9    .045       0  4756.5     .05       0
  4823.9    .045       0  4981.1    .035       0  4991.3    .045       0
  4999.4    .035       0  5098.8    .045       0  5496.6     .05       0
  5596.1    .063       0  5831.1     .05       0
Bank Sta=4981.1,4991.3
XS Rating Curve= 0 ,0
Exp/Cntr=0.3,0.1

Chan Stop Cuts=-1
Use User Specified Reach Order=0
Composite Channel Slope=5