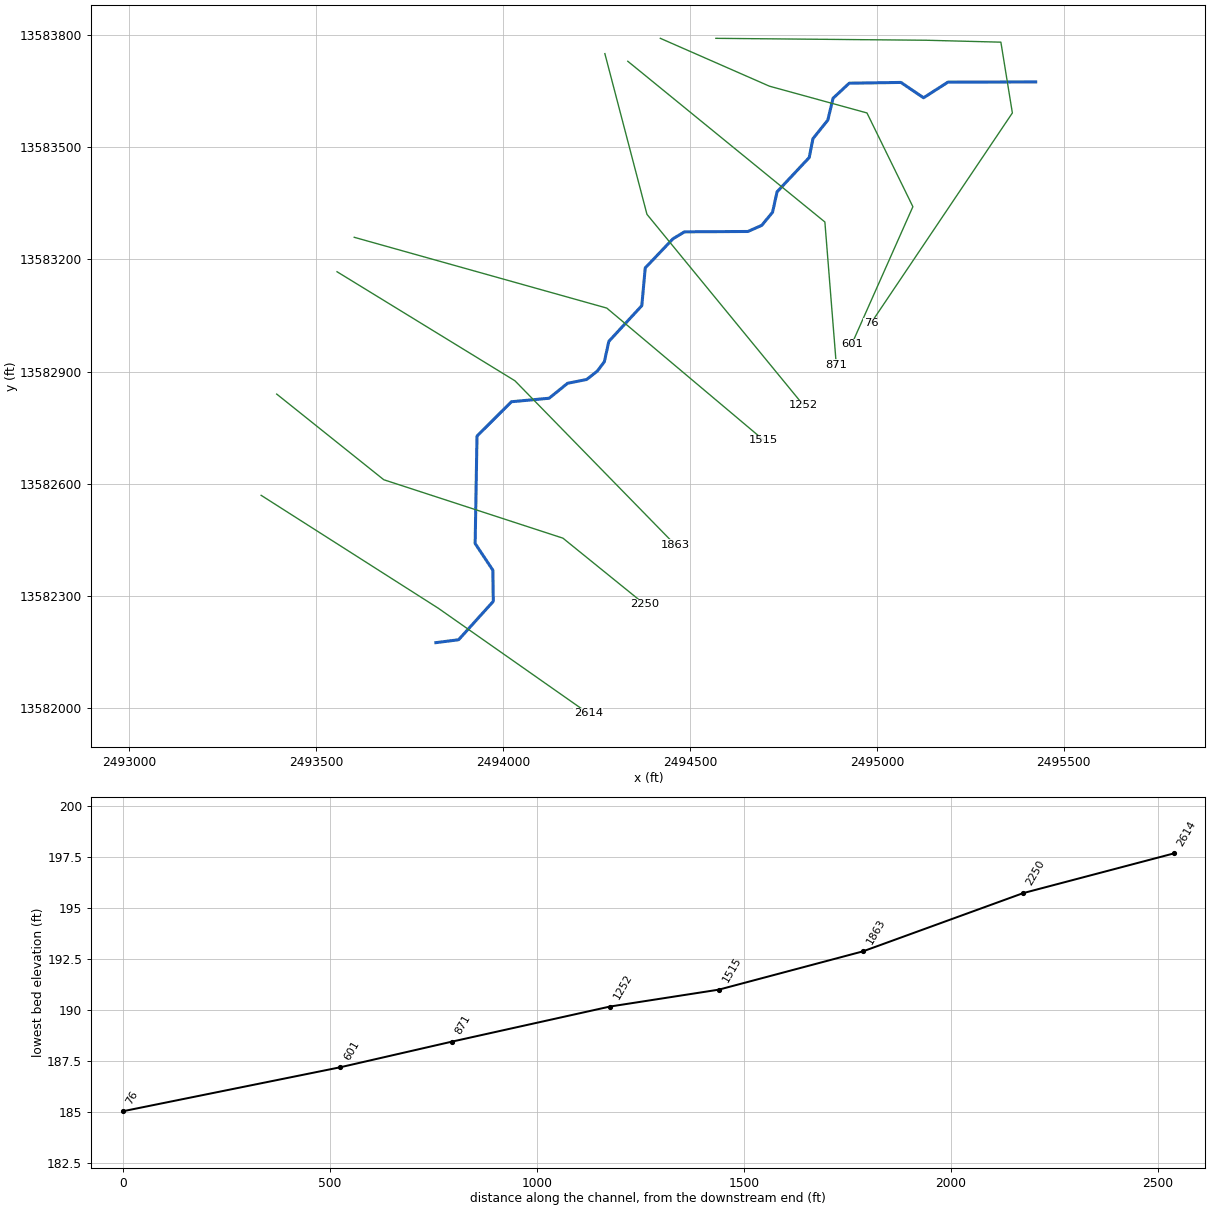
--- LG Stream002.prj (project) ---

Proj Title=LG Stream002 Base Level Engineering
Current Plan=p01
Default Exp/Contr=0.3,0.1
English Units
Geom File=g01
Flow File=f01
Plan File=p01
Y Axis Title=Elevation
X Axis Title(PF)=Main Channel Distance
X Axis Title(XS)=Station
BEGIN DESCRIPTION:
LG Stream002
END DESCRIPTION:
DSS Export Rating Curves= 0
DSS Export Rating Curve Sorted= 0
DSS Export Volume Flow Curves= 0
DXF OffsetX= 0
DXF OffsetY= 0
DXF ScaleX= 1
DXF ScaleY= 10

--- LG Stream002.p01 (plan) ---

Plan Title=Multiple Run
Short Identifier=Multiple
Geom File=g01
Flow File=f01
Subcritical Flow
K Sum by GR= 0
Std Step Tol= 0.01
Critical Tol= 0.01
Num of Std Step Trials= 20
Max Error Tol= 0.3
Flow Tol Ratio= 0.001
Split Flow NTrial= 30
Split Flow Tol= 0.02
Split Flow Ratio= 0.02
Log Output Level= 0
Friction Slope Method= 1
Unsteady Friction Slope Method= 2
Unsteady Bridges Friction Slope Method= 1
Parabolic Critical Depth
Global Vel Dist=  1 , 1 , 1
Global Log Level= 0
CheckData=True
Encroach Param= -1, 0, 0, 0
BEGIN DESCRIPTION:
Multiple Run
END DESCRIPTION:

--- LG Stream002.f01 (steady flow) ---

Flow Title=Multiple
Number of Profiles=7
Profile Names=10-year,25-year,50-year,1pct_min,100-year,1pct_plu,500-year
River Rch & RM= LG Stream002,Reach-1,2614
     774    1268    1721    1132    2258    4505    3850
Boundary for River Rch & Prof#=LG Stream002,Reach-1,1
Up Type=0
Dn Type=3
Dn Slope=0.005
Boundary for River Rch & Prof#=LG Stream002,Reach-1,2
Up Type=0
Dn Type=3
Dn Slope=0.005
Boundary for River Rch & Prof#=LG Stream002,Reach-1,3
Up Type=0
Dn Type=3
Dn Slope=0.005
Boundary for River Rch & Prof#=LG Stream002,Reach-1,4
Up Type=0
Dn Type=3
Dn Slope=0.005
Boundary for River Rch & Prof#=LG Stream002,Reach-1,5
Up Type=0
Dn Type=3
Dn Slope=0.005
Boundary for River Rch & Prof#=LG Stream002,Reach-1,6
Up Type=0
Dn Type=3
Dn Slope=0.005
Boundary for River Rch & Prof#=LG Stream002,Reach-1,7
Up Type=0
Dn Type=3
Dn Slope=0.005

--- LG Stream002.g01 (geometry) ---

Geom Title=Existing Conditions

River Reach=LG Stream002,Reach-1
Reach XY= 30
      2493820.56     13582175.00      2493881.25     13582182.74
      2493974.07     13582285.47      2493972.84     13582369.02
      2493925.52     13582440.22      2493930.45     13582727.47
      2494022.56     13582819.48      2494123.42     13582828.83
      2494172.85     13582868.85      2494223.58     13582878.86
      2494252.14     13582901.16      2494271.11     13582926.43
      2494283.19     13582981.02      2494371.37     13583076.50
      2494380.52     13583177.44      2494454.79     13583255.41
      2494485.43     13583273.95      2494655.12     13583274.92
      2494692.14     13583291.27      2494721.13     13583326.40
      2494733.19     13583381.02      2494819.15     13583472.71
      2494829.19     13583523.27      2494868.89     13583572.84
      2494883.00     13583631.39      2494926.25     13583671.56
      2495064.56     13583673.63      2495125.00     13583632.56
      2495190.16     13583674.34      2495425.00     13583675.00

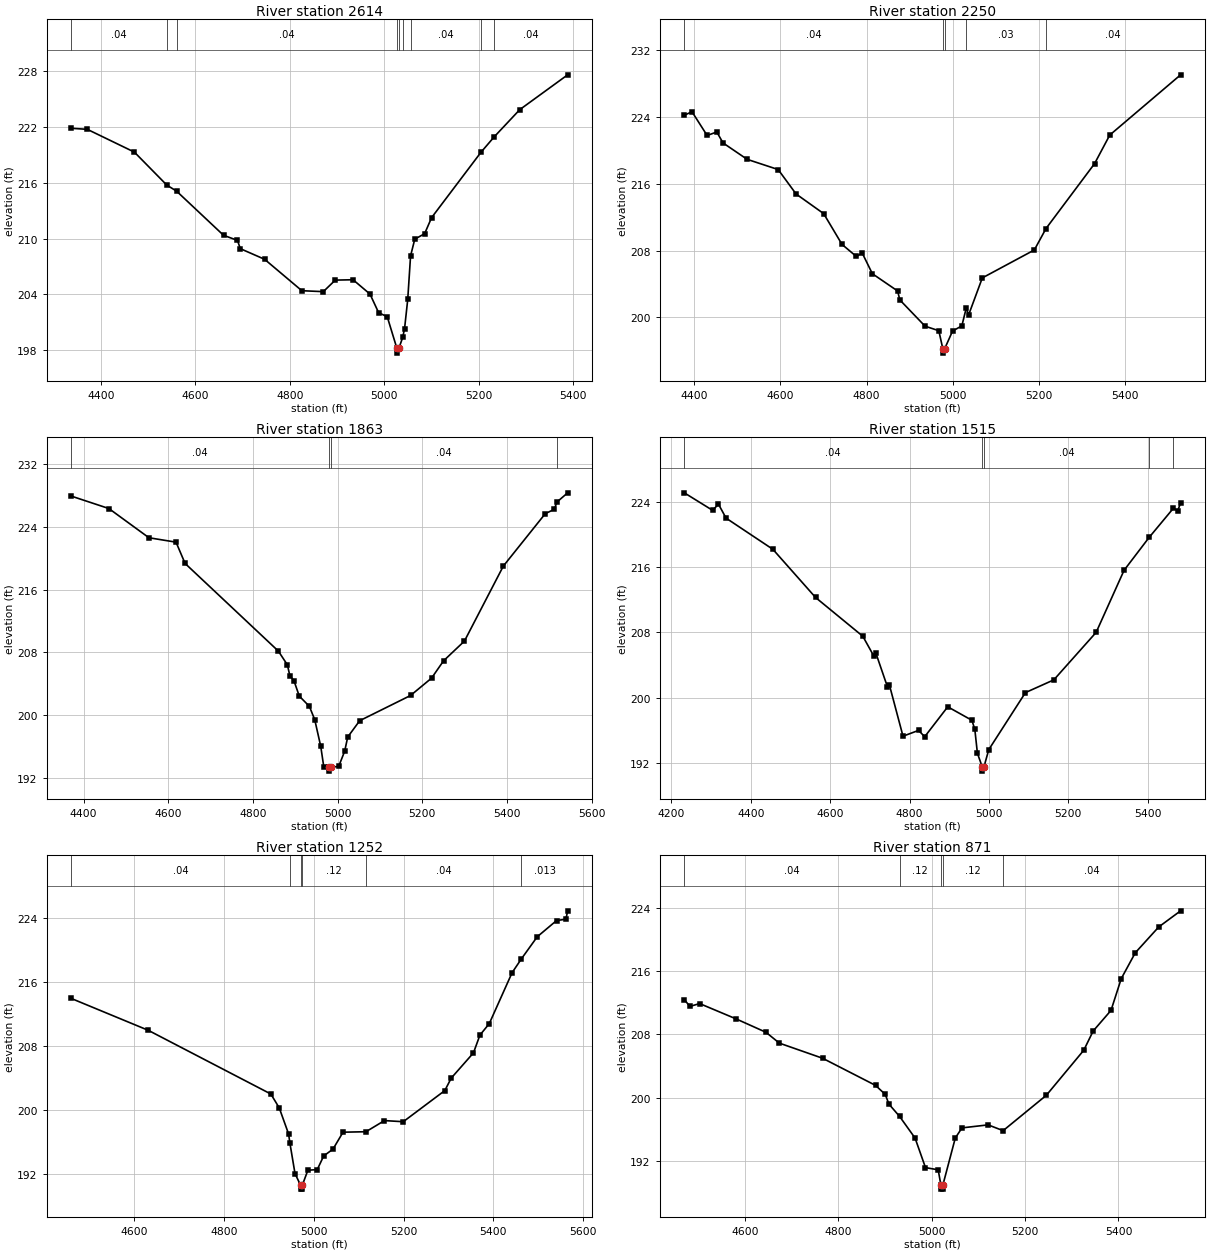
Type RM Length L Ch R = 1,2614,364,364,364
BEGIN DESCRIPTION:
LGII4486
END DESCRIPTION:
XS GIS Cut Line= 3
      2493353.04     13582569.10      2493826.97     13582267.04
      2494227.98     13581985.81
#Sta/Elev= 30
  4337.0  221.86  4370.8  221.75  4470.6  219.30  4539.4  215.75  4559.9  215.11
  4659.5  210.36  4689.0  209.81  4695.1  208.92  4746.5  207.78  4825.5  204.40
  4871.0  204.30  4896.3  205.54  4934.0  205.58  4969.9  204.04  4988.2  202.04
  5006.5  201.60  5027.0  198.19  5027.3  197.69  5031.0  198.19  5039.3  199.39
  5043.2  200.33  5049.9  203.46  5055.9  208.14  5064.8  209.94  5085.7  210.53
  5100.5  212.26  5205.2  219.29  5233.1  220.94  5287.4  223.87  5388.8  227.61
#Mann=9,-1,0
  4337.0    0.04       0  4539.4    0.12       0  4559.9    0.04       0
  5027.0    0.04       0  5031.0    0.04       0  5039.3    0.12       0
  5055.9    0.04       0  5205.2    0.12       0  5233.1    0.04       0
Bank Sta=5027,5031
Exp/Cntr=0.3,0.1

Type RM Length L Ch R = 1,2250,387,387,387
BEGIN DESCRIPTION:
LGII4485
END DESCRIPTION:
XS GIS Cut Line= 4
      2493394.65     13582839.98      2493681.13     13582610.79
      2494160.30     13582454.54      2494379.04     13582277.47
#Sta/Elev= 30
  4376.7  224.17  4394.5  224.59  4429.7  221.75  4452.1  222.17  4466.6  220.86
  4522.6  218.90  4594.6  217.68  4636.2  214.76  4700.3  212.41  4742.9  208.73
  4776.2  207.29  4789.7  207.71  4813.3  205.23  4871.9  203.17  4877.1  202.10
  4935.7  198.96  4967.6  198.42  4977.0  196.24  4977.3  195.74  4981.0  196.24
  4999.5  198.38  5021.1  199.00  5031.4  201.15  5036.7  200.29  5068.6  204.73
  5189.4  208.07  5216.5  210.63  5329.3  218.39  5364.5  221.80  5529.0  229.00
#Mann=5,-1,0
  4376.7    0.04       0  4977.0    0.04       0  4981.0    0.04       0
  5031.4    0.03       0  5216.5    0.04       0
Bank Sta=4977,4981
Exp/Cntr=0.3,0.1

Type RM Length L Ch R = 1,1863,348,348,348
BEGIN DESCRIPTION:
LGII4484
END DESCRIPTION:
XS GIS Cut Line= 3
      2493556.03     13583167.23      2494032.00     13582875.51
      2494460.92     13582436.38
#Sta/Elev= 30
  4371.1  227.89  4459.7  226.31  4554.4  222.59  4618.3  222.03  4639.7  219.32
  4860.0  208.16  4881.3  206.41  4887.2  205.01  4896.7  204.41  4909.4  202.43
  4933.2  201.13  4945.9  199.43  4960.1  196.03  4967.2  193.45  4979.4  193.38
  4979.6  192.88  4983.4  193.38  5002.5  193.48  5016.6  195.42  5023.8  197.22
  5052.1  199.30  5172.2  202.51  5221.8  204.72  5250.1  206.92  5299.5  209.44
  5391.4  218.99  5490.4  225.66  5511.7  226.21  5517.8  227.13  5543.2  228.31
#Mann=4,-1,0
  4371.1    0.04       0  4979.4    0.04       0  4983.4    0.04       0
  5517.8   0.013       0
Bank Sta=4979.4,4983.4
Exp/Cntr=0.3,0.1

Type RM Length L Ch R = 1,1515,263,263,263
BEGIN DESCRIPTION:
LGII4483
END DESCRIPTION:
XS GIS Cut Line= 3
      2493602.10     13583259.34      2494277.65     13583069.99
      2494697.27     13582716.89
#Sta/Elev= 30
  4232.8  225.09  4303.9  222.95  4318.9  223.69  4338.0  221.99  4455.9  218.17
  4563.4  212.27  4682.4  207.52  4710.2  205.09  4715.4  205.44  4744.3  201.34
  4749.5  201.53  4783.6  195.28  4822.9  195.99  4838.2  195.21  4896.3  198.88
  4957.1  197.23  4964.5  196.12  4971.0  193.19  4983.3  191.50  4983.5  191.00
  4987.4  191.50  4999.6  193.63  5092.0  200.62  5163.5  202.18  5270.1  208.00
  5340.4  215.60  5403.4  219.62  5464.8  223.21  5475.6  222.90  5482.8  223.86
#Mann=5,-1,0
  4232.8    0.04       0  4983.3    0.04       0  4987.4    0.04       0
  5403.4   0.013       0  5464.8    0.05       0
Bank Sta=4983.3,4987.4
Exp/Cntr=0.3,0.1

Type RM Length L Ch R = 1,1252,381,381,381
BEGIN DESCRIPTION:
LGII4482
END DESCRIPTION:
XS GIS Cut Line= 3
      2494272.53     13583750.64      2494385.12     13583320.76
      2494804.38     13582809.46
#Sta/Elev= 30
  4459.8  213.98  4631.0  210.01  4904.2  202.05  4922.9  200.32  4943.7  197.07
  4946.5  195.98  4958.0  192.12  4970.3  190.67  4970.6  190.17  4974.2  190.17
  4974.4  190.67  4986.7  192.53  5007.6  192.61  5021.9  194.31  5042.7  195.17
  5065.0  197.28  5116.1  197.34  5157.3  198.73  5199.2  198.59  5291.8  202.48
  5306.1  204.04  5355.6  207.19  5370.0  209.41  5390.8  210.84  5441.7  217.21
  5462.6  218.95  5497.7  221.69  5540.8  223.72  5561.6  223.88  5565.4  224.93
#Mann=6,-1,0
  4459.8    0.04       0  4946.5    0.12       0  4970.3    0.05       0
  4974.4    0.12       0  5116.1    0.04       0  5462.6   0.013       0
Bank Sta=4970.3,4974.4
Exp/Cntr=0.3,0.1

Type RM Length L Ch R = 1,871,270,270,270
BEGIN DESCRIPTION:
LGII4481
END DESCRIPTION:
XS GIS Cut Line= 3
      2494333.92     13583730.20      2494861.07     13583300.28
      2494891.63     13582918.24
#Sta/Elev= 30
  4469.7  212.40  4481.7  211.54  4502.5  211.90  4580.8  209.96  4644.7  208.27
  4673.4  206.90  4766.0  204.99  4879.5  201.56  4900.3  200.42  4908.2  199.19
  4931.0  197.64  4964.2  194.90  4986.5  191.17  5013.7  190.89  5019.6  188.95
  5019.9  188.45  5023.5  188.45  5023.7  188.95  5050.4  194.91  5064.7  196.19
  5120.7  196.57  5152.9  195.84  5245.5  200.31  5325.8  206.01  5345.8  208.43
  5384.1  211.04  5406.0  215.05  5436.1  218.32  5486.3  221.58  5533.2  223.62
#Mann=5,-1,0
  4469.7    0.04       0  4931.0    0.12       0  5019.6    0.05       0
  5023.7    0.12       0  5152.9    0.04       0
Bank Sta=5019.6,5023.7
Exp/Cntr=0.3,0.1

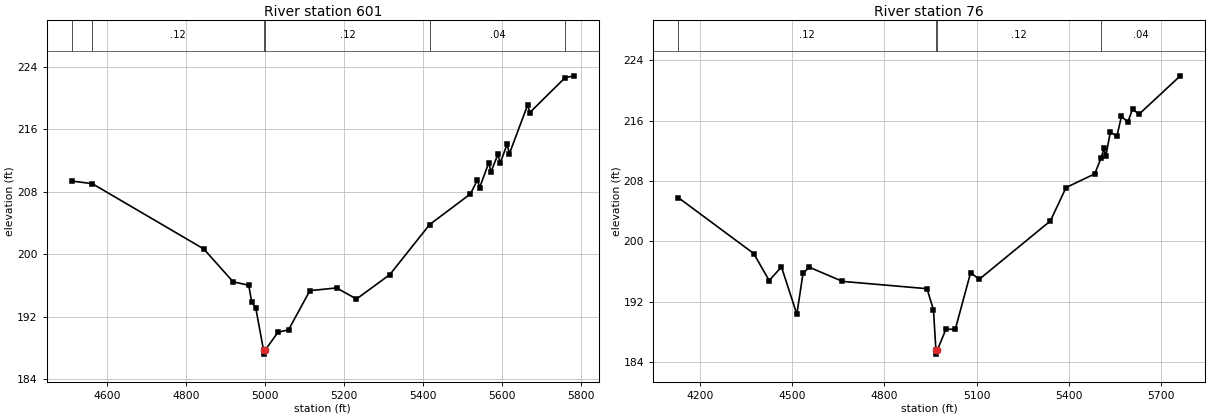
Type RM Length L Ch R = 1,601,525,525,525
BEGIN DESCRIPTION:
LGII4480
END DESCRIPTION:
XS GIS Cut Line= 5
      2494420.97     13583791.58      2494712.66     13583663.64
      2494973.66     13583592.00      2495096.49     13583341.23
      2494932.73     13582972.78
#Sta/Elev= 30
  4510.8  209.36  4562.6  209.03  4845.2  200.66  4919.3  196.46  4958.9  196.01
  4966.5  193.91  4976.9  193.08  4996.5  187.69  4996.7  187.19  5000.6  187.69
  5032.9  189.99  5059.9  190.31  5113.8  195.32  5181.4  195.67  5231.9  194.25
  5316.4  197.38  5417.2  203.79  5520.5  207.71  5538.3  209.51  5543.8  208.52
  5567.0  211.70  5572.5  210.53  5590.3  212.81  5595.8  211.65  5613.6  214.10
  5619.0  212.85  5665.5  219.11  5671.0  218.14  5760.0  222.59  5782.4  222.84
#Mann=6,-1,0
  4510.8    0.04       0  4562.6    0.12       0  4996.5    0.05       0
  5000.6    0.12       0  5417.2    0.04       0  5760.0   0.013       0
Bank Sta=4996.5,5000.6
Exp/Cntr=0.3,0.1

Type RM Length L Ch R = 1,76,0,0,0
BEGIN DESCRIPTION:
LGII4479
END DESCRIPTION:
XS GIS Cut Line= 6
      2494569.41     13583791.59      2495106.77     13583786.70
      2495132.31     13583786.47      2495331.90     13583781.35
      2495362.61     13583592.00      2494984.23     13583029.54
#Sta/Elev= 30
  4129.7  205.80  4375.3  198.37  4425.3  194.79  4465.3  196.60  4515.3  190.32
  4535.3  195.73  4555.3  196.57  4663.7  194.68  4938.5  193.71  4959.5  190.89
  4967.5  185.53  4967.8  185.03  4971.7  185.53  5000.0  188.34  5030.4  188.32
  5080.1  195.81  5108.7  194.97  5339.6  202.70  5390.6  207.13  5483.6  208.94
  5505.0  211.09  5513.6  212.31  5519.6  211.26  5534.6  214.51  5555.6  213.91
  5570.6  216.56  5591.6  215.82  5606.6  217.55  5627.6  216.85  5762.0  221.95
#Mann=4,-1,0
  4129.7    0.12       0  4967.5    0.05       0  4971.7    0.12       0
  5505.0    0.04       0
Bank Sta=4967.5,4971.7
Exp/Cntr=0.3,0.1

Chan Stop Cuts=-1