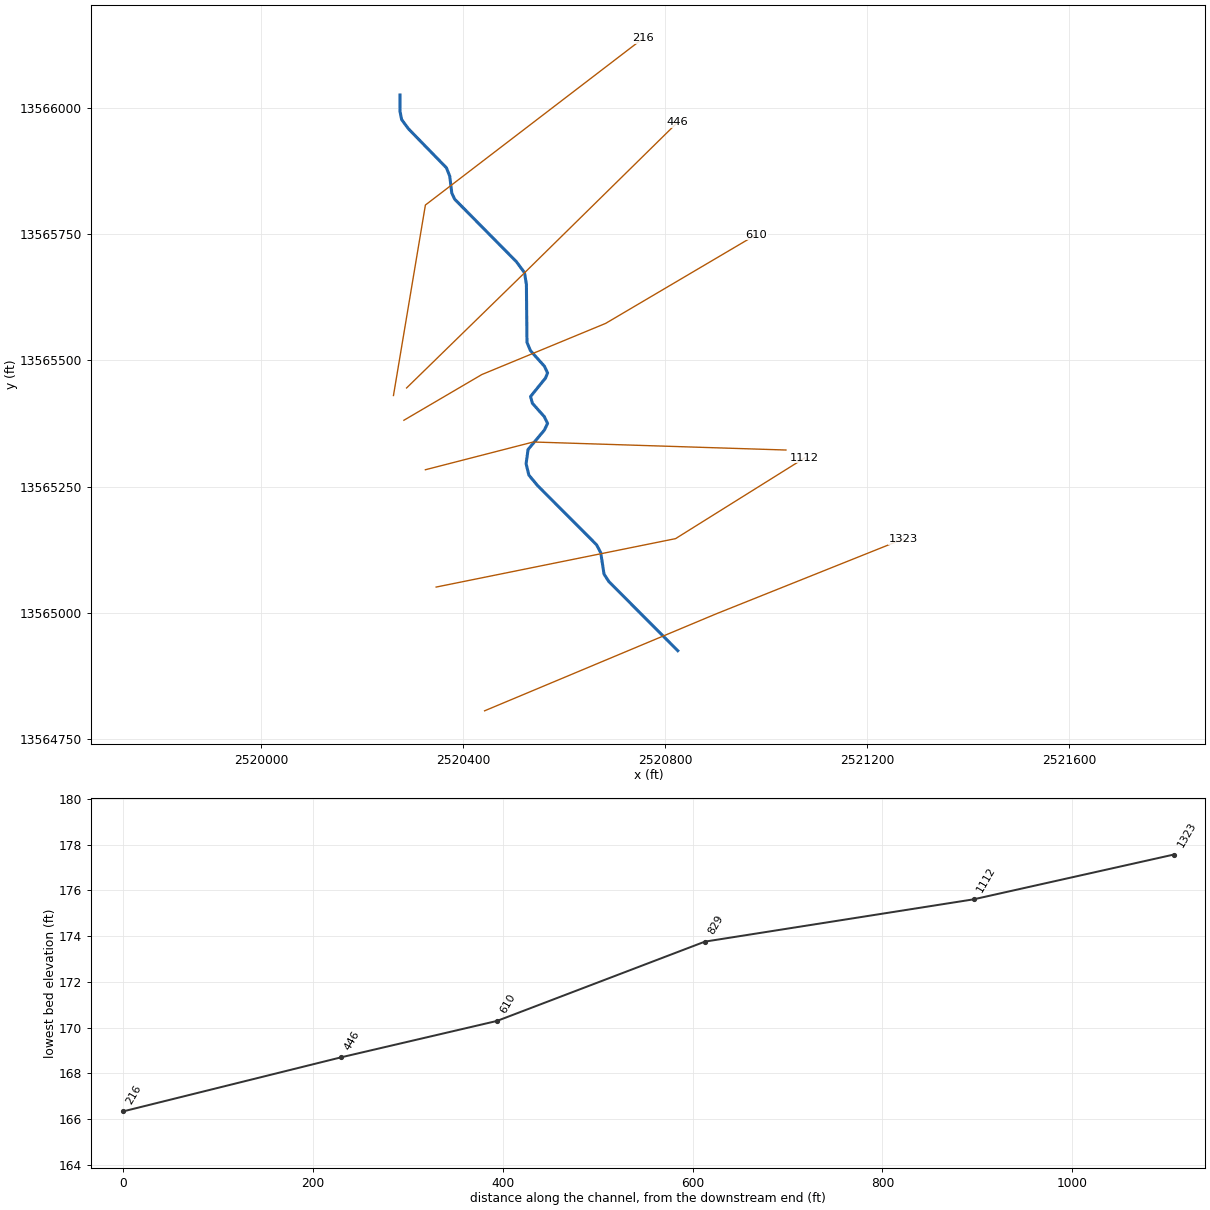
--- LG Stream010.prj (project) ---

Proj Title=LG Stream010 Base Level Engineering
Current Plan=p01
Default Exp/Contr=0.3,0.1
English Units
Geom File=g01
Flow File=f01
Plan File=p01
Y Axis Title=Elevation
X Axis Title(PF)=Main Channel Distance
X Axis Title(XS)=Station
BEGIN DESCRIPTION:
LG Stream010
END DESCRIPTION:
DSS Export Rating Curves= 0
DSS Export Rating Curve Sorted= 0
DSS Export Volume Flow Curves= 0
DXF OffsetX= 0
DXF OffsetY= 0
DXF ScaleX= 1
DXF ScaleY= 10

--- LG Stream010.p01 (plan) ---

Plan Title=Multiple Run
Short Identifier=Multiple
Geom File=g01
Flow File=f01
Subcritical Flow
K Sum by GR= 0
Std Step Tol= 0.01
Critical Tol= 0.01
Num of Std Step Trials= 20
Max Error Tol= 0.3
Flow Tol Ratio= 0.001
Split Flow NTrial= 30
Split Flow Tol= 0.02
Split Flow Ratio= 0.02
Log Output Level= 0
Friction Slope Method= 1
Unsteady Friction Slope Method= 2
Unsteady Bridges Friction Slope Method= 1
Parabolic Critical Depth
Global Vel Dist=  1 , 1 , 1
Global Log Level= 0
CheckData=True
Encroach Param= -1, 0, 0, 0
BEGIN DESCRIPTION:
Multiple Run
END DESCRIPTION:

--- LG Stream010.f01 (steady flow) ---

Flow Title=Multiple
Number of Profiles=7
Profile Names=10-year,25-year,50-year,1pct_min,100-year,1pct_plu,500-year
River Rch & RM= LG Stream010,Reach-1,1323
     529     850    1139     742    1480    2952    2468
Boundary for River Rch & Prof#=LG Stream010,Reach-1,1
Up Type=0
Dn Type=3
Dn Slope=0.005
Boundary for River Rch & Prof#=LG Stream010,Reach-1,2
Up Type=0
Dn Type=3
Dn Slope=0.005
Boundary for River Rch & Prof#=LG Stream010,Reach-1,3
Up Type=0
Dn Type=3
Dn Slope=0.005
Boundary for River Rch & Prof#=LG Stream010,Reach-1,4
Up Type=0
Dn Type=3
Dn Slope=0.005
Boundary for River Rch & Prof#=LG Stream010,Reach-1,5
Up Type=0
Dn Type=3
Dn Slope=0.005
Boundary for River Rch & Prof#=LG Stream010,Reach-1,6
Up Type=0
Dn Type=3
Dn Slope=0.005
Boundary for River Rch & Prof#=LG Stream010,Reach-1,7
Up Type=0
Dn Type=3
Dn Slope=0.005

--- LG Stream010.g01 (geometry) ---

Geom Title=Existing Conditions

River Reach=LG Stream010,Reach-1
Reach XY= 30
      2520825.00     13564925.00      2520688.63     13565061.79
      2520678.97     13565076.65      2520672.47     13565118.95
      2520664.22     13565134.68      2520547.72     13565251.54
      2520530.11     13565272.71      2520524.67     13565295.16
      2520528.56     13565323.35      2520560.86     13565361.81
      2520567.19     13565375.09      2520560.67     13565388.38
      2520536.97     13565415.01      2520533.55     13565428.33
      2520563.19     13565464.94      2520567.22     13565474.90
      2520560.94     13565488.16      2520533.44     13565518.81
      2520526.39     13565535.44      2520525.27     13565650.11
      2520521.46     13565673.53      2520505.39     13565695.16
      2520383.16     13565818.95      2520377.53     13565831.05
      2520373.45     13565864.36      2520366.84     13565881.05
      2520291.62     13565958.31      2520278.29     13565976.36
      2520274.93     13565993.12      2520275.00     13566025.00

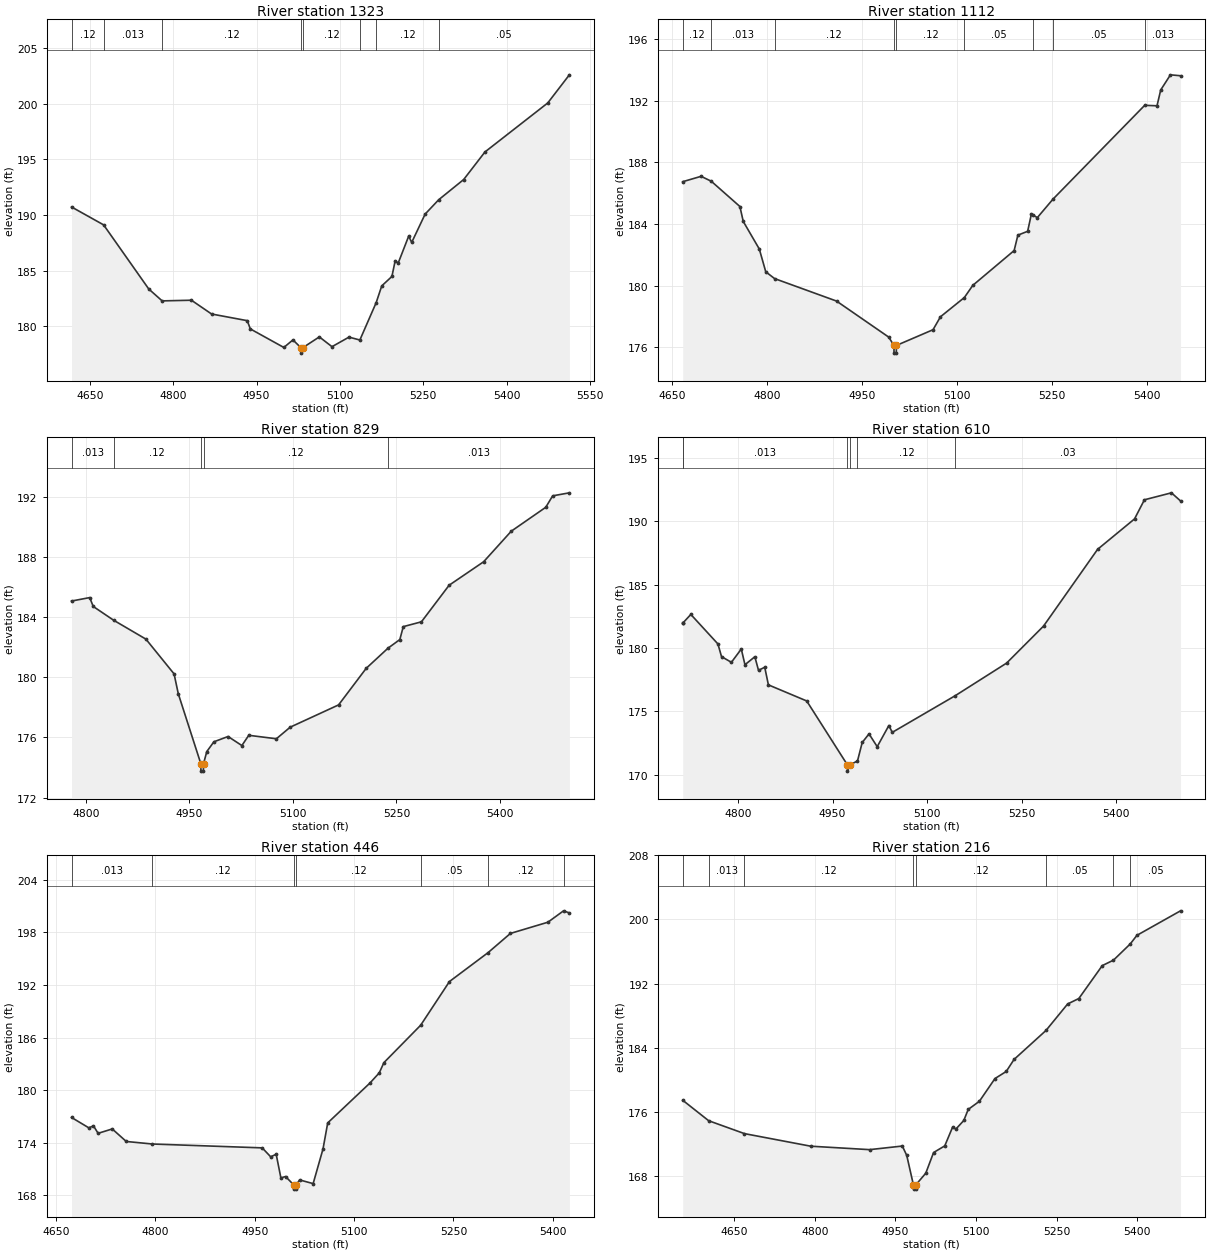
Type RM Length L Ch R = 1,1323,211,211,211
BEGIN DESCRIPTION:
LGII4501
END DESCRIPTION:
XS GIS Cut Line= 3
      2520442.48     13564806.04      2520900.47     13564997.76
      2521271.68     13565146.24
#Sta/Elev= 30
  4616.8  190.72  4674.5  189.11  4755.8  183.34  4779.9  182.27  4832.6  182.33
  4868.9  181.09  4933.2  180.49  4938.6  179.75  4999.0  178.08  5015.4  178.76
  5029.5  178.07  5029.7  177.57  5033.5  178.07  5062.9  179.03  5085.7  178.15
  5116.3  179.01  5135.9  178.75  5165.3  182.12  5175.3  183.62  5193.6  184.47
  5199.5  185.89  5204.9  185.67  5223.8  188.10  5229.2  187.53  5253.4  190.08
  5277.8  191.37  5322.8  193.19  5361.1  195.67  5474.2  200.08  5513.1  202.61
#Mann=8,-1,0
  4616.8    0.12       0  4674.5   0.013       0  4779.9    0.12       0
  5029.5    0.05       0  5033.5    0.12       0  5135.9    0.05       0
  5165.3    0.12       0  5277.8    0.05       0
Bank Sta=5029.5,5033.5
Exp/Cntr=0.3,0.1

Type RM Length L Ch R = 1,1112,283,283,283
BEGIN DESCRIPTION:
LGII4500
END DESCRIPTION:
XS GIS Cut Line= 3
      2520346.59     13565051.02      2520820.58     13565146.88
      2521076.26     13565306.69
#Sta/Elev= 30
  4667.1  186.74  4696.1  187.09  4712.2  186.77  4757.3  185.13  4762.6  184.16
  4787.9  182.37  4798.1  180.89  4812.0  180.45  4909.7  178.99  4992.0  176.65
  5000.2  176.11  5000.4  175.61  5003.9  175.61  5004.2  176.11  5061.9  177.13
  5073.6  177.97  5111.3  179.22  5124.6  180.01  5189.8  182.27  5195.7  183.27
  5211.1  183.52  5217.0  184.64  5219.7  184.57  5226.4  184.41  5251.1  185.61
  5395.7  191.70  5415.1  191.67  5421.0  192.70  5436.3  193.68  5452.2  193.62
#Mann=9,-1,0
  4667.1    0.12       0  4712.2   0.013       0  4812.0    0.12       0
  5000.2    0.05       0  5004.2    0.12       0  5111.3    0.05       0
  5219.7    0.12       0  5251.1    0.05       0  5395.7   0.013       0
Bank Sta=5000.2,5004.2
Exp/Cntr=0.3,0.1

Type RM Length L Ch R = 1,829,219,219,219
BEGIN DESCRIPTION:
LGII4499
END DESCRIPTION:
XS GIS Cut Line= 3
      2520325.25     13565283.27      2520538.90     13565338.21
      2521039.15     13565322.32
#Sta/Elev= 30
  4779.4  185.06  4805.7  185.29  4810.8  184.70  4840.2  183.79  4887.1  182.53
  4927.9  180.22  4934.0  178.90  4966.6  174.26  4966.8  173.76  4970.3  173.76
  4970.6  174.26  4975.3  175.06  4985.6  175.71  5006.1  176.06  5026.1  175.46
  5036.1  176.14  5076.1  175.91  5096.1  176.68  5166.2  178.16  5206.2  180.59
  5237.8  181.93  5254.9  182.50  5259.9  183.36  5286.2  183.68  5326.3  186.11
  5376.3  187.67  5416.3  189.70  5466.3  191.29  5476.3  192.05  5500.5  192.25
#Mann=5,-1,0
  4779.4   0.013       0  4840.2    0.12       0  4966.6    0.05       0
  4970.6    0.12       0  5237.8   0.013       0
Bank Sta=4966.6,4970.6
Exp/Cntr=0.3,0.1

Type RM Length L Ch R = 1,610,164,164,164
BEGIN DESCRIPTION:
LGII4498
END DESCRIPTION:
XS GIS Cut Line= 4
      2520282.69     13565381.24      2520437.11     13565471.77
      2520682.10     13565572.96      2520980.22     13565748.64
#Sta/Elev= 30
  4712.1  182.01  4712.9  182.01  4725.0  182.66  4768.0  180.33  4773.7  179.33
  4789.4  178.88  4805.1  179.93  4810.9  178.69  4826.6  179.32  4832.4  178.25
  4842.3  178.49  4848.1  177.10  4908.9  175.83  4973.4  170.79  4973.6  170.29
  4977.4  170.79  4989.5  171.09  4997.0  172.55  5007.8  173.23  5020.8  172.22
  5039.3  173.89  5044.7  173.35  5144.8  176.25  5226.2  178.82  5284.8  181.74
  5370.6  187.80  5429.2  190.20  5444.9  191.71  5487.8  192.26  5502.2  191.62
#Mann=6,-1,0
  4712.1    0.12       0  4712.9   0.013       0  4973.4    0.05       0
  4977.4   0.013       0  4989.5    0.12       0  5144.8    0.03       0
Bank Sta=4973.4,4977.4
Exp/Cntr=0.3,0.1

Type RM Length L Ch R = 1,446,230,230,230
BEGIN DESCRIPTION:
LGII4497
END DESCRIPTION:
XS GIS Cut Line= 3
      2520288.01     13565445.16      2520506.35     13565658.18
      2520824.69     13565971.21
#Sta/Elev= 30
  4673.6  176.88  4699.6  175.70  4706.7  175.92  4713.7  175.07  4735.0  175.57
  4756.2  174.14  4795.7  173.85  4961.4  173.41  4974.2  172.39  4982.5  172.68
  4989.6  169.98  4996.6  170.14  5008.8  169.20  5009.0  168.70  5012.5  168.70
  5012.8  169.20  5017.9  169.75  5038.3  169.33  5053.2  173.29  5060.3  176.26
  5123.9  180.80  5138.1  181.97  5145.1  183.14  5200.6  187.41  5244.1  192.40
  5302.4  195.70  5336.1  197.89  5392.7  199.17  5416.3  200.47  5425.1  200.23
#Mann=7,-1,0
  4673.6   0.013       0  4795.7    0.12       0  5008.8    0.05       0
  5012.8    0.12       0  5200.6    0.05       0  5302.4    0.12       0
  5416.3    0.03       0
Bank Sta=5008.8,5012.8
Exp/Cntr=0.3,0.1

Type RM Length L Ch R = 1,216,0,0,0
BEGIN DESCRIPTION:
LGII4496
END DESCRIPTION:
XS GIS Cut Line= 3
      2520262.03     13565430.19      2520325.27     13565807.30
      2520756.71     13566137.54
#Sta/Elev= 30
  4554.5  177.43  4602.8  174.87  4669.4  173.26  4792.6  171.69  4902.0  171.26
  4962.9  171.71  4971.1  170.54  4983.6  166.83  4983.9  166.33  4987.4  166.33
  4987.6  166.83  5006.5  168.32  5021.0  170.90  5041.8  171.73  5056.3  174.06
  5062.6  173.84  5077.2  174.90  5085.4  176.28  5106.2  177.30  5135.2  180.14
  5156.1  181.02  5170.6  182.52  5230.0  186.14  5270.3  189.45  5291.1  190.13
  5334.7  194.24  5355.5  194.92  5386.8  196.95  5399.1  198.02  5480.2  201.08
#Mann=8,-1,0
  4554.5    0.12       0  4602.8   0.013       0  4669.4    0.12       0
  4983.6    0.05       0  4987.6    0.12       0  5230.0    0.05       0
  5355.5    0.12       0  5386.8    0.05       0
Bank Sta=4983.6,4987.6
Exp/Cntr=0.3,0.1

Chan Stop Cuts=-1