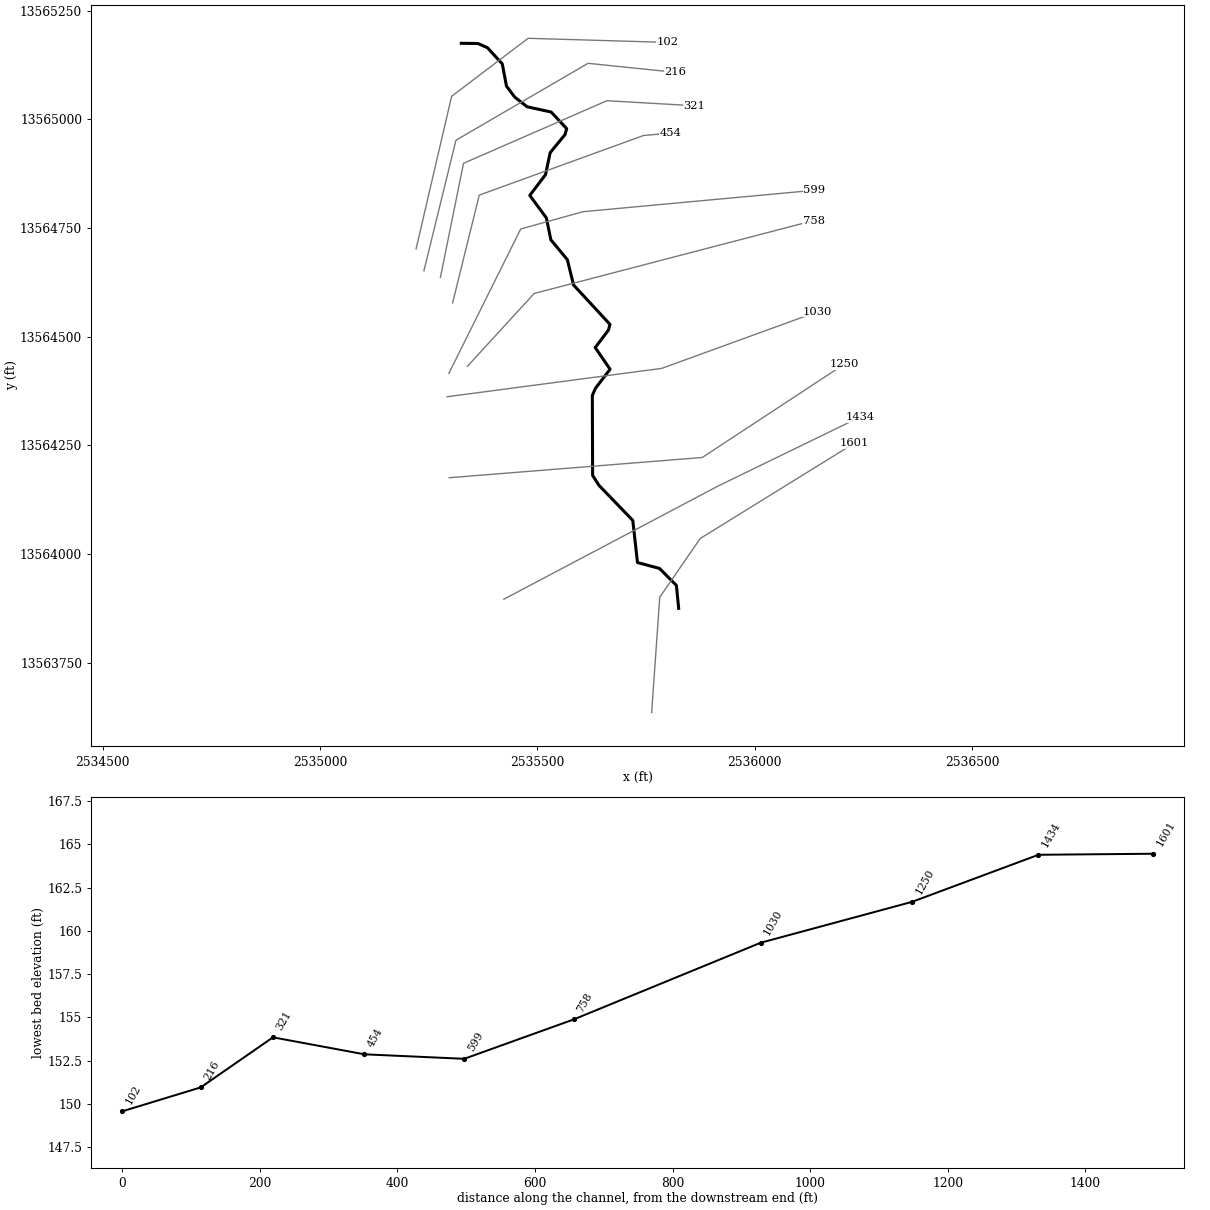
--- LG Stream019.prj (project) ---

Proj Title=LG Stream019 Base Level Engineering
Current Plan=p01
Default Exp/Contr=0.3,0.1
English Units
Geom File=g01
Flow File=f01
Plan File=p01
Y Axis Title=Elevation
X Axis Title(PF)=Main Channel Distance
X Axis Title(XS)=Station
BEGIN DESCRIPTION:
LG Stream019
END DESCRIPTION:
DSS Export Rating Curves= 0
DSS Export Rating Curve Sorted= 0
DSS Export Volume Flow Curves= 0
DXF OffsetX= 0
DXF OffsetY= 0
DXF ScaleX= 1
DXF ScaleY= 10

--- LG Stream019.p01 (plan) ---

Plan Title=Multiple Run
Short Identifier=Multiple
Geom File=g01
Flow File=f01
Subcritical Flow
K Sum by GR= 0
Std Step Tol= 0.01
Critical Tol= 0.01
Num of Std Step Trials= 20
Max Error Tol= 0.3
Flow Tol Ratio= 0.001
Split Flow NTrial= 30
Split Flow Tol= 0.02
Split Flow Ratio= 0.02
Log Output Level= 0
Friction Slope Method= 1
Unsteady Friction Slope Method= 2
Unsteady Bridges Friction Slope Method= 1
Parabolic Critical Depth
Global Vel Dist=  1 , 1 , 1
Global Log Level= 0
CheckData=True
Encroach Param= -1, 0, 0, 0
BEGIN DESCRIPTION:
Multiple Run
END DESCRIPTION:

--- LG Stream019.f01 (steady flow) ---

Flow Title=Multiple
Number of Profiles=7
Profile Names=10-year,25-year,50-year,1pct_min,100-year,1pct_plu,500-year
River Rch & RM= LG Stream019,Reach-1,1601
     219     327     416     258     515    1027     777
Boundary for River Rch & Prof#=LG Stream019,Reach-1,1
Up Type=0
Dn Type=3
Dn Slope=0.005
Boundary for River Rch & Prof#=LG Stream019,Reach-1,2
Up Type=0
Dn Type=3
Dn Slope=0.005
Boundary for River Rch & Prof#=LG Stream019,Reach-1,3
Up Type=0
Dn Type=3
Dn Slope=0.005
Boundary for River Rch & Prof#=LG Stream019,Reach-1,4
Up Type=0
Dn Type=3
Dn Slope=0.005
Boundary for River Rch & Prof#=LG Stream019,Reach-1,5
Up Type=0
Dn Type=3
Dn Slope=0.005
Boundary for River Rch & Prof#=LG Stream019,Reach-1,6
Up Type=0
Dn Type=3
Dn Slope=0.005
Boundary for River Rch & Prof#=LG Stream019,Reach-1,7
Up Type=0
Dn Type=3
Dn Slope=0.005

--- LG Stream019.g01 (geometry) ---

Geom Title=Existing Conditions

River Reach=LG Stream019,Reach-1
Reach XY= 30
      2535825.00     13563875.00      2535819.79     13563927.86
      2535780.92     13563966.86      2535730.25     13563980.45
      2535719.44     13564077.36      2535641.46     13564158.25
      2535627.06     13564180.86      2535626.37     13564364.57
      2535633.44     13564381.19      2535667.22     13564425.10
      2535633.04     13564475.00      2535663.33     13564515.00
      2535667.00     13564528.33      2535583.18     13564618.94
      2535568.90     13564677.19      2535531.05     13564722.81
      2535520.57     13564773.36      2535482.50     13564825.00
      2535518.64     13564872.72      2535529.41     13564923.36
      2535563.78     13564965.26      2535567.33     13564978.66
      2535531.67     13565016.84      2535476.50     13565028.89
      2535447.87     13565051.16      2535428.87     13565076.44
      2535419.28     13565127.48      2535385.25     13565164.67
      2535363.38     13565174.50      2535325.00     13565175.00

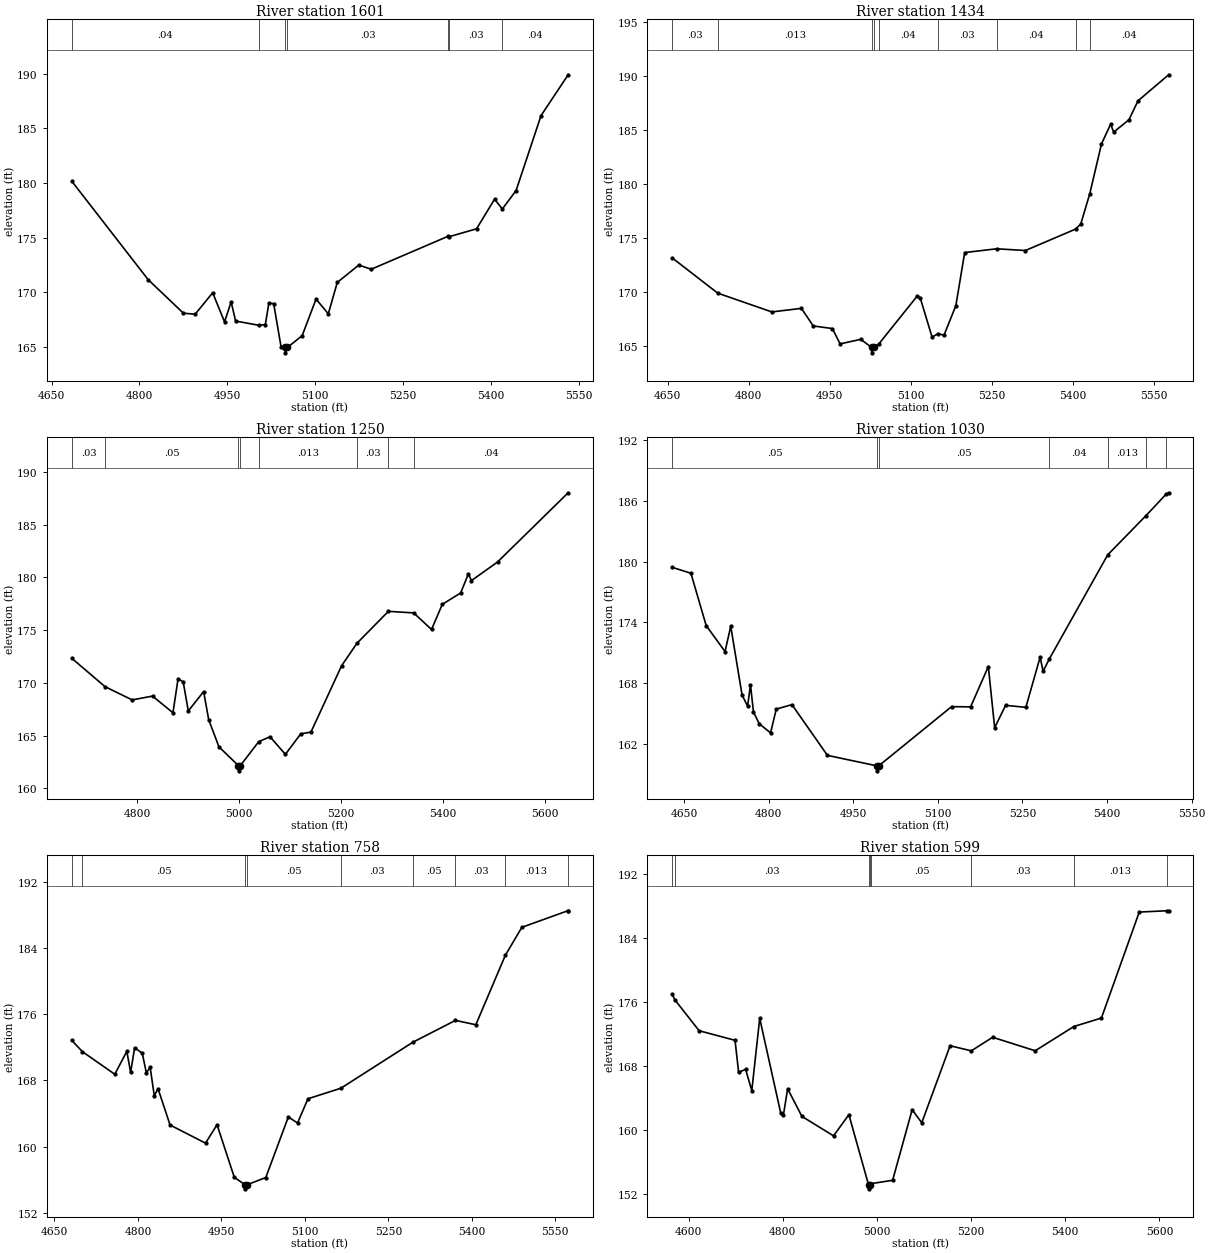
Type RM Length L Ch R = 1,1601,167,167,167
BEGIN DESCRIPTION:
LGII4520
END DESCRIPTION:
XS GIS Cut Line= 4
      2535762.84     13563635.15      2535781.48     13563900.68
      2535874.65     13564035.78      2536228.72     13564254.74
#Sta/Elev= 30
  4684.6  180.15  4814.8  171.15  4874.9  168.08  4895.0  167.98  4924.9  169.95
  4945.1  167.28  4956.4  169.11  4964.0  167.36  5003.7  166.97  5014.7  167.04
  5020.7  168.99  5028.9  168.95  5041.7  164.95  5048.5  164.95  5048.8  164.45
  5052.5  164.95  5077.5  166.02  5101.2  169.37  5122.1  168.02  5137.4  170.89
  5174.1  172.48  5195.4  172.10  5325.7  175.10  5328.6  175.08  5375.0  175.80
  5405.7  178.51  5418.9  177.61  5442.4  179.30  5484.9  186.15  5531.2  189.89
#Mann=7,-1,0
  4684.6    0.04       0  5003.7    0.03       0  5048.5    0.04       0
  5052.5    0.03       0  5325.7    0.05       0  5328.6    0.03       0
  5418.9    0.04       0
Bank Sta=5048.5,5052.5
Exp/Cntr=0.3,0.1

Type RM Length L Ch R = 1,1434,184,184,184
BEGIN DESCRIPTION:
LGII4519
END DESCRIPTION:
XS GIS Cut Line= 3
      2535422.79     13563896.04      2535916.58     13564156.91
      2536241.33     13564314.65
#Sta/Elev= 30
  4658.5  173.18  4742.7  169.92  4842.9  168.18  4897.7  168.51  4919.7  166.88
  4955.1  166.64  4969.4  165.22  5007.7  165.64  5027.7  164.89  5028.0  164.39
  5031.7  164.89  5040.9  165.20  5112.1  169.64  5117.8  169.48  5139.8  165.84
  5150.5  166.17  5161.8  166.02  5183.8  168.76  5200.2  173.68  5259.4  174.03
  5312.7  173.87  5405.9  175.86  5415.3  176.34  5431.9  179.13  5453.6  183.75
  5470.6  185.58  5476.1  184.84  5504.3  185.97  5521.3  187.74  5578.0  190.15
#Mann=9,-1,0
  4658.5    0.03       0  4742.7   0.013       0  5027.7    0.03       0
  5031.7   0.013       0  5040.9    0.04       0  5150.5    0.03       0
  5259.4    0.04       0  5405.9    0.03       0  5431.9    0.04       0
Bank Sta=5027.7,5031.7
Exp/Cntr=0.3,0.1

Type RM Length L Ch R = 1,1250,220,220,220
BEGIN DESCRIPTION:
LGII4518
END DESCRIPTION:
XS GIS Cut Line= 3
      2535297.01     13564175.55      2535879.31     13564222.13
      2536205.44     13564436.44
#Sta/Elev= 30
  4671.3  172.33  4736.7  169.64  4789.7  168.39  4829.8  168.75  4869.9  167.17
  4879.9  170.39  4890.0  170.10  4900.0  167.34  4930.1  169.18  4940.1  166.51
  4960.2  163.94  4998.3  162.17  4998.6  161.67  5002.3  162.17  5038.2  164.43
  5060.5  164.90  5090.6  163.23  5120.7  165.17  5140.8  165.34  5201.0  171.63
  5231.2  173.76  5292.8  176.78  5342.5  176.63  5377.5  175.06  5398.6  177.44
  5434.7  178.52  5449.8  180.33  5455.8  179.69  5507.0  181.45  5645.7  188.01
#Mann=8,-1,0
  4671.3    0.03       0  4736.7    0.05       0  4998.3    0.05       0
  5002.3    0.05       0  5038.2   0.013       0  5231.2    0.03       0
  5292.8   0.013       0  5342.5    0.04       0
Bank Sta=4998.3,5002.3
Exp/Cntr=0.3,0.1

Type RM Length L Ch R = 1,1030,272,272,272
BEGIN DESCRIPTION:
LGII4517
END DESCRIPTION:
XS GIS Cut Line= 3
      2535292.33     13564361.89      2535786.14     13564427.11
      2536144.86     13564557.55
#Sta/Elev= 30
  4629.4  179.44  4662.4  178.86  4689.5  173.68  4722.9  171.11  4733.0  173.61
  4753.1  166.81  4762.9  165.71  4768.0  167.82  4773.3  165.13  4783.4  163.98
  4803.6  163.06  4813.7  165.42  4841.5  165.86  4904.4  160.84  4991.5  159.81
  4991.8  159.31  4995.5  159.81  5124.4  165.66  5158.2  165.64  5189.6  169.63
  5200.8  163.58  5220.2  165.79  5256.1  165.59  5281.4  170.56  5286.7  169.16
  5297.7  170.38  5401.2  180.68  5469.1  184.56  5504.8  186.69  5509.2  186.82
#Mann=7,-1,0
  4629.4    0.05       0  4991.5    0.05       0  4995.5    0.05       0
  5297.7    0.04       0  5401.2   0.013       0  5469.1    0.12       0
  5504.8   0.013       0
Bank Sta=4991.5,4995.5
Exp/Cntr=0.3,0.1

Type RM Length L Ch R = 1,758,159,159,159
BEGIN DESCRIPTION:
LGII4516
END DESCRIPTION:
XS GIS Cut Line= 3
      2535338.91     13564431.77      2535492.64     13564599.48
      2536135.51     13564767.18
#Sta/Elev= 30
  4681.2  172.84  4700.2  171.48  4758.5  168.74  4780.1  171.52  4786.9  168.96
  4794.1  171.95  4807.8  171.29  4815.2  168.91  4822.0  169.58  4829.4  166.15
  4836.2  166.99  4857.8  162.60  4921.5  160.41  4942.2  162.64  4973.2  156.27
  4992.5  155.38  4992.8  154.88  4996.5  155.38  5029.8  156.25  5070.3  163.58
  5086.8  162.84  5105.6  165.78  5164.7  167.05  5293.9  172.61  5370.6  175.26
  5407.2  174.73  5460.2  183.13  5489.9  186.52  5572.4  188.52  5573.1  188.52
#Mann=9,-1,0
  4681.2    0.03       0  4700.2    0.05       0  4992.5    0.05       0
  4996.5    0.05       0  5164.7    0.03       0  5293.9    0.05       0
  5370.6    0.03       0  5460.2   0.013       0  5572.4    0.12       0
Bank Sta=4992.5,4996.5
Exp/Cntr=0.3,0.1

Type RM Length L Ch R = 1,599,145,145,145
BEGIN DESCRIPTION:
Mapping XS dfe7c963
END DESCRIPTION:
XS GIS Cut Line= 4
      2535296.31     13564415.62      2535461.61     13564747.80
      2535604.67     13564787.54      2536137.18     13564836.82
#Sta/Elev= 30
  4565.2  177.01  4570.3  176.32  4622.2  172.42  4698.5  171.22  4706.1  167.21
  4720.9  167.58  4734.1  164.92  4750.9  173.97  4795.7  162.06  4801.3  161.87
  4810.2  165.15  4840.5  161.69  4907.7  159.25  4940.3  161.90  4982.1  153.11
  4982.4  152.61  4986.1  153.11  4988.3  153.27  5033.2  153.68  5074.7  162.52
  5095.1  160.89  5155.3  170.54  5200.3  169.90  5245.7  171.60  5336.1  169.91
  5418.2  172.95  5476.7  174.01  5557.1  187.29  5615.2  187.45  5619.5  187.44
#Mann=8,-1,0
  4565.2    0.05       0  4570.3    0.03       0  4982.1    0.05       0
  4986.1    0.03       0  4988.3    0.05       0  5200.3    0.03       0
  5418.2   0.013       0  5615.2    0.12       0
Bank Sta=4982.1,4986.1
Exp/Cntr=0.3,0.1

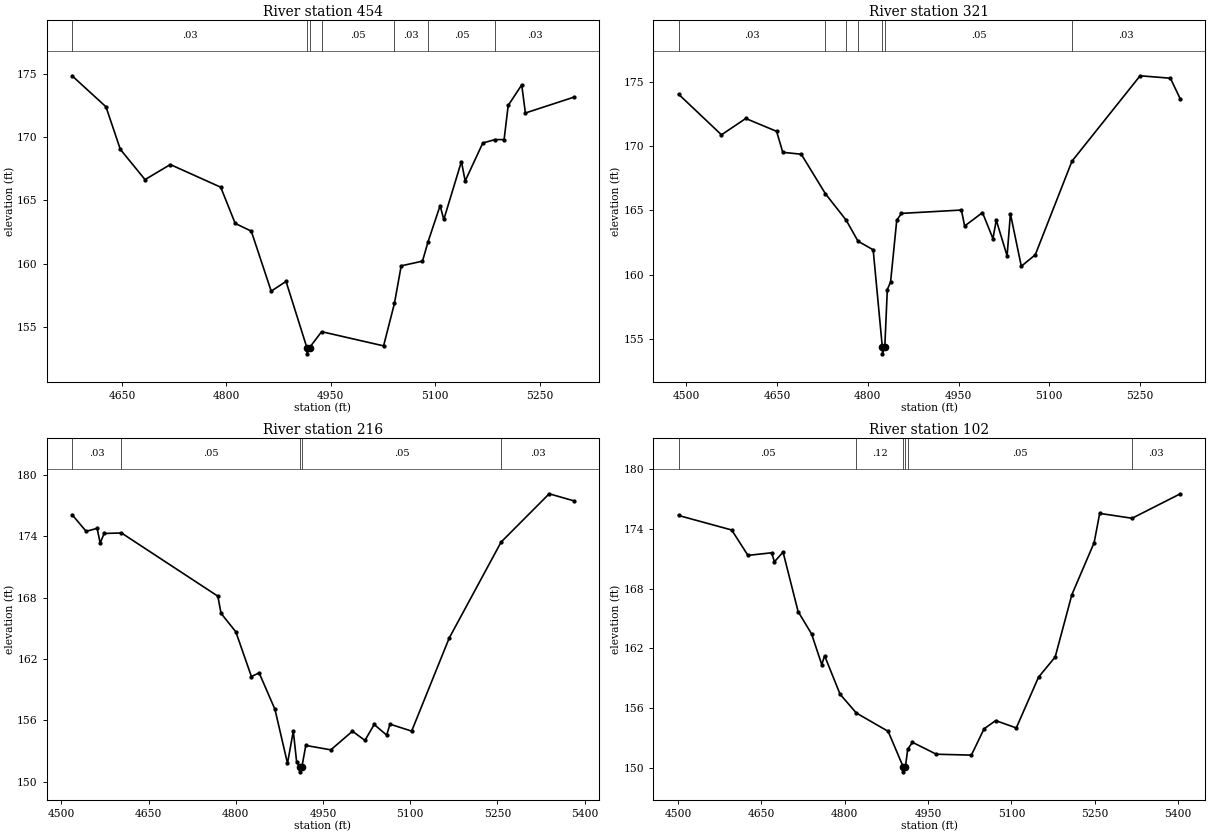
Type RM Length L Ch R = 1,454,133,133,133
BEGIN DESCRIPTION:
LGII4515
END DESCRIPTION:
XS GIS Cut Line= 4
      2535304.98     13564577.73      2535366.24     13564825.69
      2535744.21     13564962.85      2535807.15     13564968.51
#Sta/Elev= 30
  4578.4  174.83  4627.1  172.38  4647.7  169.02  4683.2  166.63  4719.5  167.82
  4791.9  166.03  4812.7  163.17  4835.8  162.56  4864.4  157.82  4885.7  158.59
  4915.6  153.37  4915.9  152.87  4919.6  153.37  4936.8  154.62  5025.8  153.50
  5041.4  156.85  5051.1  159.82  5081.7  160.19  5089.8  161.74  5107.0  164.57
  5112.3  163.48  5137.6  168.06  5143.0  166.52  5168.3  169.52  5185.9  169.79
  5198.9  169.79  5204.8  172.49  5224.2  174.11  5229.5  171.89  5299.1  173.14
#Mann=7,-1,0
  4578.4    0.03       0  4915.6    0.05       0  4919.6    0.03       0
  4936.8    0.05       0  5041.4    0.03       0  5089.8    0.05       0
  5185.9    0.03       0
Bank Sta=4915.6,4919.6
Exp/Cntr=0.3,0.1

Type RM Length L Ch R = 1,321,105,105,105
BEGIN DESCRIPTION:
LGII4514a
END DESCRIPTION:
XS GIS Cut Line= 4
      2535276.80     13564636.02      2535330.04     13564898.86
      2535659.94     13565042.88      2535861.36     13565031.32
#Sta/Elev= 30
  4486.9  174.04  4557.9  170.88  4598.1  172.15  4649.1  171.15  4659.3  169.52
  4689.9  169.37  4729.8  166.30  4764.2  164.24  4783.7  162.61  4808.8  161.94
  4824.0  154.35  4824.2  153.85  4828.0  154.35  4832.2  158.85  4837.6  159.44
  4847.8  164.24  4855.6  164.77  4954.7  165.03  4960.1  163.79  4989.6  164.83
  5006.9  162.81  5012.4  164.24  5030.3  161.47  5035.8  164.74  5053.8  160.66
  5076.9  161.55  5137.6  168.83  5250.3  175.47  5300.4  175.28  5316.8  173.66
#Mann=7,-1,0
  4486.9    0.03       0  4729.8    0.05       0  4764.2    0.03       0
  4783.7    0.05       0  4824.0    0.05       0  4828.0    0.05       0
  5137.6    0.03       0
Bank Sta=4824,4828
Exp/Cntr=0.3,0.1

Type RM Length L Ch R = 1,216,114,114,114
BEGIN DESCRIPTION:
Mapping XS 05456971
END DESCRIPTION:
XS GIS Cut Line= 4
      2535238.90     13564651.49      2535312.67     13564952.03
      2535616.49     13565128.90      2535817.22     13565108.28
#Sta/Elev= 30
  4518.5  176.10  4542.7  174.47  4561.6  174.76  4566.8  173.32  4573.6  174.26
  4603.4  174.31  4769.2  168.13  4774.6  166.46  4800.1  164.64  4826.9  160.27
  4840.1  160.64  4867.4  157.06  4888.9  151.79  4898.9  154.94  4904.6  151.94
  4909.7  151.46  4909.9  150.96  4913.7  151.46  4920.4  153.54  4963.4  153.11
  5000.6  154.93  5022.1  154.03  5037.9  155.59  5059.4  154.55  5065.2  155.62
  5102.4  154.94  5166.9  164.03  5256.2  173.42  5338.9  178.14  5381.3  177.45
#Mann=5,-1,0
  4518.5    0.03       0  4603.4    0.05       0  4909.7    0.05       0
  4913.7    0.05       0  5256.2    0.03       0
Bank Sta=4909.7,4913.7
Exp/Cntr=0.3,0.1

Type RM Length L Ch R = 1,102,0,0,0
BEGIN DESCRIPTION:
LGII4514
END DESCRIPTION:
XS GIS Cut Line= 4
      2535220.89     13564701.83      2535302.66     13565052.99
      2535478.67     13565186.47      2535800.07     13565176.98
#Sta/Elev= 30
  4500.9  175.34  4596.6  173.88  4625.8  171.33  4668.3  171.59  4673.5  170.69
  4689.0  171.66  4716.1  165.68  4740.3  163.44  4758.6  160.36  4763.8  161.24
  4791.6  157.38  4820.9  155.49  4878.1  153.65  4905.2  150.08  4905.5  149.58
  4909.2  150.08  4913.3  151.84  4921.8  152.55  4964.8  151.35  5027.9  151.26
  5050.7  153.90  5071.6  154.73  5108.7  153.99  5148.7  159.09  5178.7  161.12
  5208.7  167.38  5248.8  172.61  5258.8  175.55  5317.1  175.06  5403.9  177.52
#Mann=6,-1,0
  4500.9    0.05       0  4820.9    0.12       0  4905.2    0.05       0
  4909.2    0.12       0  4913.3    0.05       0  5317.1    0.03       0
Bank Sta=4905.2,4909.2
Exp/Cntr=0.3,0.1

Chan Stop Cuts=-1