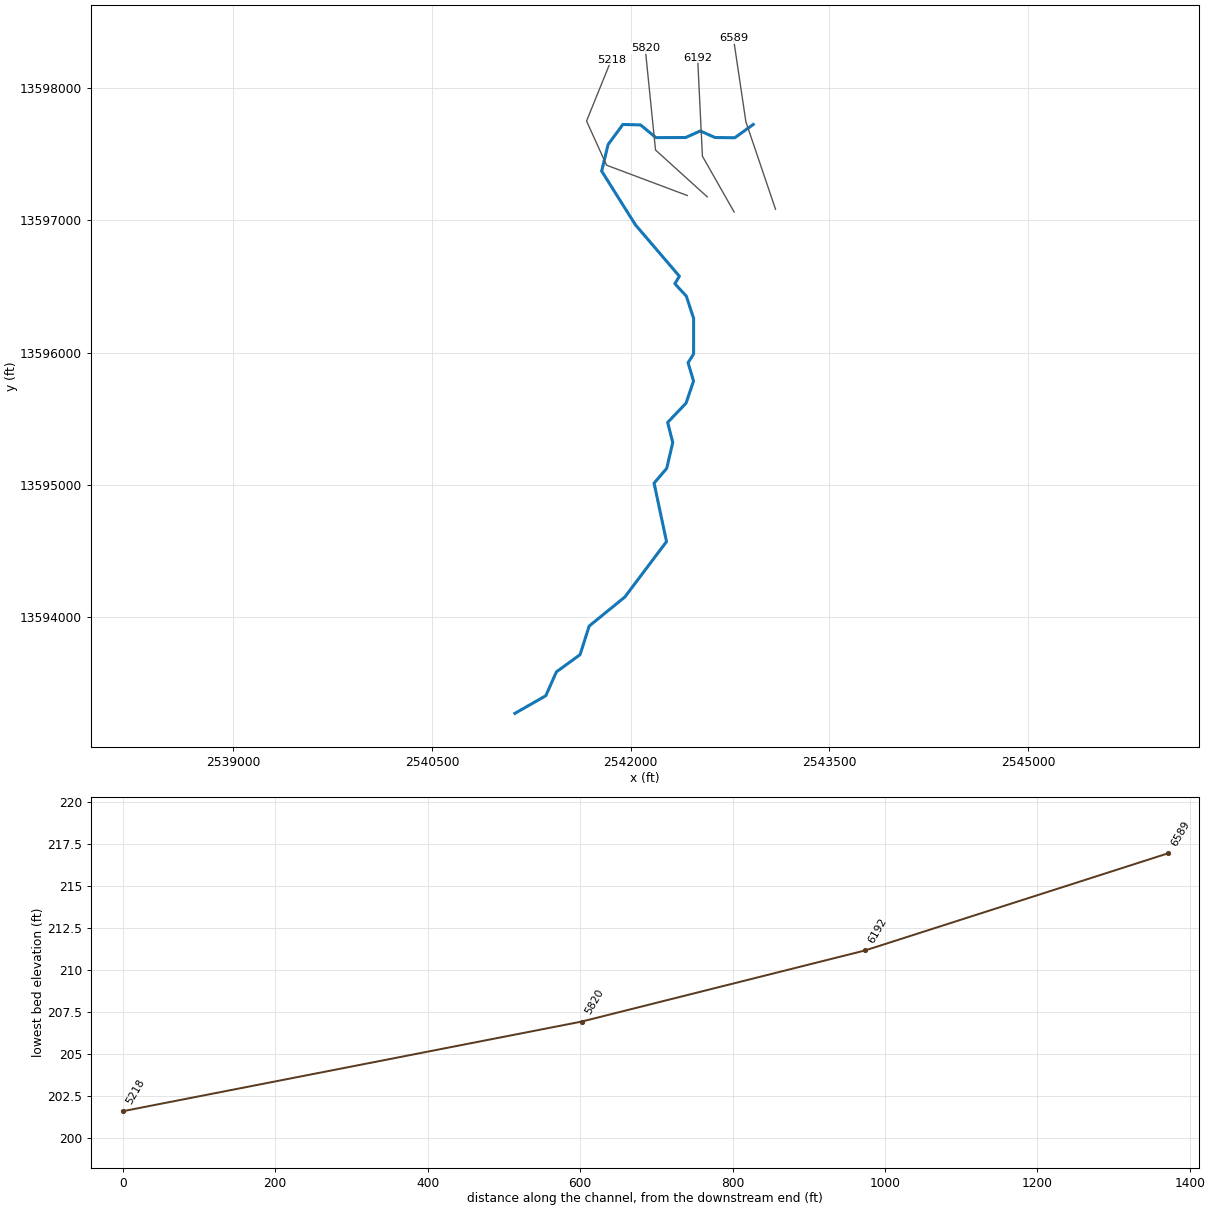
--- LG Stream043.prj (project) ---

Proj Title=LG Stream043 Base Level Engineering
Current Plan=p01
Default Exp/Contr=0.3,0.1
English Units
Geom File=g01
Flow File=f01
Plan File=p01
Y Axis Title=Elevation
X Axis Title(PF)=Main Channel Distance
X Axis Title(XS)=Station
BEGIN DESCRIPTION:
LG Stream043
END DESCRIPTION:
DSS Export Rating Curves= 0
DSS Export Rating Curve Sorted= 0
DSS Export Volume Flow Curves= 0
DXF OffsetX= 0
DXF OffsetY= 0
DXF ScaleX= 1
DXF ScaleY= 10

--- LG Stream043.p01 (plan) ---

Plan Title=Multiple Run
Short Identifier=Multiple
Geom File=g01
Flow File=f01
Subcritical Flow
K Sum by GR= 0
Std Step Tol= 0.01
Critical Tol= 0.01
Num of Std Step Trials= 20
Max Error Tol= 0.3
Flow Tol Ratio= 0.001
Split Flow NTrial= 30
Split Flow Tol= 0.02
Split Flow Ratio= 0.02
Log Output Level= 0
Friction Slope Method= 1
Unsteady Friction Slope Method= 2
Unsteady Bridges Friction Slope Method= 1
Parabolic Critical Depth
Global Vel Dist=  1 , 1 , 1
Global Log Level= 0
CheckData=True
Encroach Param= -1, 0, 0, 0
BEGIN DESCRIPTION:
Multiple Run
END DESCRIPTION:

--- LG Stream043.f01 (steady flow) ---

Flow Title=Multiple
Number of Profiles=7
Profile Names=10-year,25-year,50-year,1pct_min,100-year,1pct_plu,500-year
River Rch & RM= LG Stream043,Reach-1,6589
     408     636     835     533    1063    2121    1702
Boundary for River Rch & Prof#=LG Stream043,Reach-1,1
Up Type=0
Dn Type=3
Dn Slope=0.005
Boundary for River Rch & Prof#=LG Stream043,Reach-1,2
Up Type=0
Dn Type=3
Dn Slope=0.005
Boundary for River Rch & Prof#=LG Stream043,Reach-1,3
Up Type=0
Dn Type=3
Dn Slope=0.005
Boundary for River Rch & Prof#=LG Stream043,Reach-1,4
Up Type=0
Dn Type=3
Dn Slope=0.005
Boundary for River Rch & Prof#=LG Stream043,Reach-1,5
Up Type=0
Dn Type=3
Dn Slope=0.005
Boundary for River Rch & Prof#=LG Stream043,Reach-1,6
Up Type=0
Dn Type=3
Dn Slope=0.005
Boundary for River Rch & Prof#=LG Stream043,Reach-1,7
Up Type=0
Dn Type=3
Dn Slope=0.005

--- LG Stream043.g01 (geometry) ---

Geom Title=Existing Conditions

River Reach=LG Stream043,Reach-1
Reach XY= 30
      2542925.00     13597725.00      2542785.20     13597624.50
      2542635.50     13597626.22      2542525.00     13597675.82
      2542414.50     13597626.22      2542190.16     13597625.39
      2542073.53     13597721.46      2541940.04     13597724.69
      2541828.82     13597573.42      2541780.10     13597372.71
      2542035.78     13596965.32      2542366.98     13596578.33
      2542333.02     13596521.67      2542419.45     13596427.43
      2542474.48     13596259.78      2542474.34     13595990.16
      2542432.56     13595925.00      2542473.89     13595785.55
      2542417.14     13595618.83      2542278.46     13595473.50
      2542316.92     13595321.70      2542271.44     13595126.47
      2542175.94     13595014.52      2542269.91     13594572.70
      2541955.37     13594154.53      2541685.76     13593934.68
      2541617.15     13593718.81      2541438.47     13593588.57
      2541358.37     13593408.29      2541125.00     13593275.00

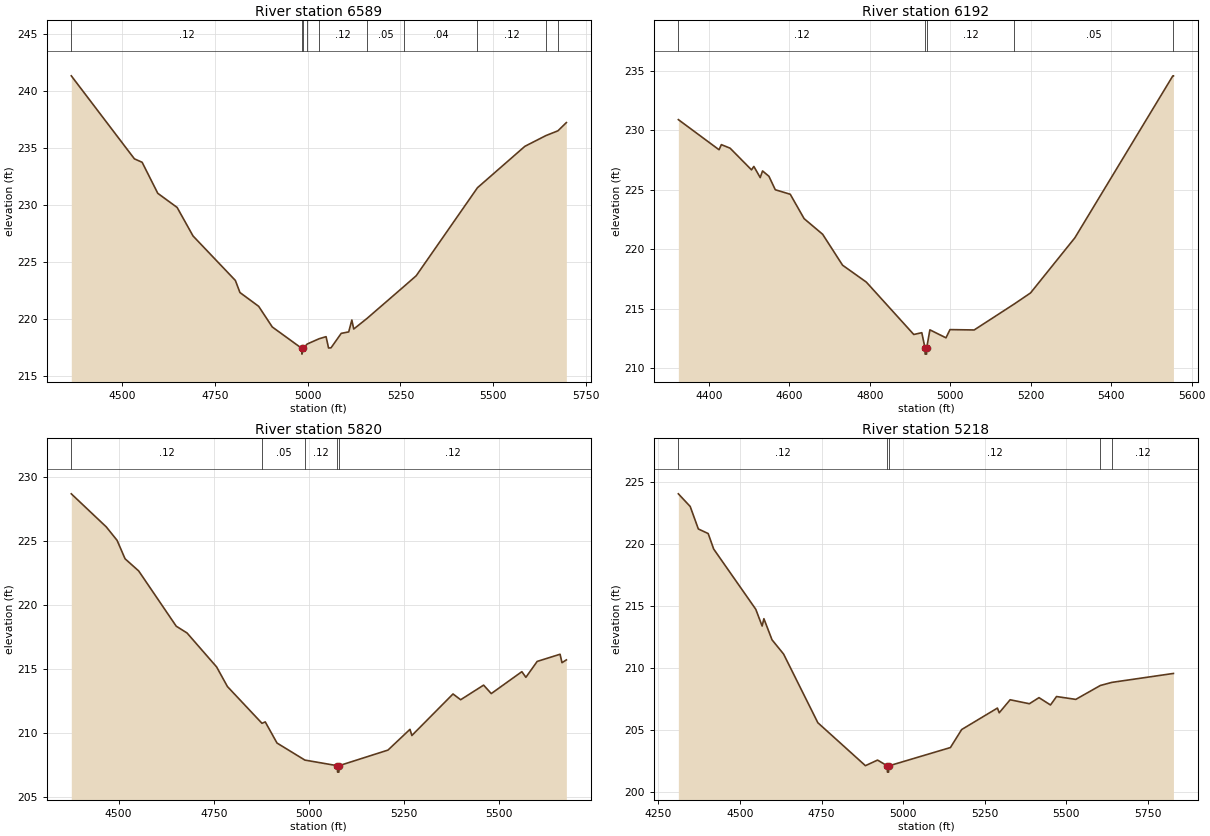
Type RM Length L Ch R = 1,6589,397,397,397
BEGIN DESCRIPTION:
LGII4130
END DESCRIPTION:
XS GIS Cut Line= 3
      2543093.05     13597083.99      2542869.10     13597745.41
      2542775.34     13598375.67
#Sta/Elev= 30
  4362.1  241.36  4532.4  234.08  4553.2  233.78  4595.4  231.06  4647.6  229.82
  4690.5  227.32  4804.7  223.42  4817.1  222.36  4867.6  221.15  4904.3  219.34
  4984.1  217.46  4984.3  216.96  4988.1  217.46  4998.1  217.84  5030.7  218.31
  5049.4  218.49  5056.1  217.50  5062.7  217.51  5090.3  218.78  5110.5  218.91
  5118.9  219.95  5124.0  219.16  5160.2  220.10  5259.4  222.89  5292.5  223.83
  5457.8  231.55  5585.7  235.18  5642.4  236.12  5674.9  236.54  5697.6  237.26
#Mann=10,-1,0
  4362.1    0.12       0  4984.1    0.05       0  4988.1    0.12       0
  4998.1    0.05       0  5030.7    0.12       0  5160.2    0.05       0
  5259.4    0.04       0  5457.8    0.12       0  5642.4    0.05       0
  5674.9    0.12       0
Bank Sta=4984.1,4988.1
Exp/Cntr=0.3,0.1

Type RM Length L Ch R = 1,6192,372,372,372
BEGIN DESCRIPTION:
LGII4129
END DESCRIPTION:
XS GIS Cut Line= 3
      2542780.57     13597063.10      2542540.97     13597485.00
      2542504.51     13598229.83
#Sta/Elev= 30
  4323.8  230.88  4425.0  228.35  4430.7  228.78  4452.5  228.48  4505.7  226.66
  4511.5  226.95  4527.3  226.01  4533.1  226.57  4549.0  226.12  4564.8  224.99
  4602.0  224.61  4636.5  222.56  4682.5  221.25  4732.1  218.65  4791.2  217.23
  4909.1  212.83  4929.1  212.98  4937.1  211.68  4937.4  211.18  4940.9  211.18
  4941.1  211.68  4949.2  213.22  4989.2  212.55  4999.2  213.24  5059.3  213.21
  5159.3  215.40  5199.4  216.32  5309.6  220.95  5553.3  234.56  5554.7  234.56
#Mann=5,-1,0
  4323.8    0.12       0  4937.1    0.05       0  4941.1    0.12       0
  5159.3    0.05       0  5553.3    0.12       0
Bank Sta=4937.1,4941.1
Exp/Cntr=0.3,0.1

Type RM Length L Ch R = 1,5820,602,602,602
BEGIN DESCRIPTION:
LGII4128
END DESCRIPTION:
XS GIS Cut Line= 3
      2542577.46     13597177.68      2542186.81     13597531.87
      2542108.82     13598301.31
#Sta/Elev= 30
  4375.7  228.66  4467.6  226.08  4496.0  225.03  4517.0  223.59  4552.8  222.64
  4651.4  218.33  4679.8  217.80  4757.5  215.15  4785.9  213.62  4876.7  210.75
  4885.3  210.86  4916.2  209.21  4989.4  207.88  5075.0  207.44  5075.3  206.94
  5078.8  206.94  5079.0  207.44  5207.7  208.66  5265.5  210.28  5270.5  209.80
  5378.6  213.04  5398.7  212.59  5459.0  213.73  5479.1  213.07  5559.5  214.78
  5570.1  214.34  5599.7  215.58  5659.9  216.14  5664.9  215.48  5676.4  215.70
#Mann=5,-1,0
  4375.7    0.12       0  4876.7    0.05       0  4989.4    0.12       0
  5075.0    0.05       0  5079.0    0.12       0
Bank Sta=5075,5079
Exp/Cntr=0.3,0.1

Type RM Length L Ch R = 1,5218,0,0,0
BEGIN DESCRIPTION:
LGII4127
END DESCRIPTION:
XS GIS Cut Line= 4
      2542426.35     13597188.14      2541817.02     13597417.29
      2541665.97     13597750.62      2541853.48     13598214.18
#Sta/Elev= 30
  4311.3  224.02  4347.6  223.00  4372.5  221.19  4402.7  220.82  4419.6  219.57
  4548.5  214.72  4568.0  213.37  4573.4  213.96  4598.3  212.26  4633.8  211.11
  4738.7  205.58  4884.5  202.12  4921.7  202.57  4951.8  202.10  4952.0  201.60
  4955.5  201.60  4955.8  202.10  5144.9  203.58  5179.4  205.03  5289.0  206.76
  5294.5  206.38  5327.9  207.43  5386.9  207.11  5416.4  207.60  5451.6  207.01
  5470.1  207.69  5529.1  207.46  5604.4  208.58  5639.6  208.83  5828.3  209.55
#Mann=5,-1,0
  4311.3    0.12       0  4951.8    0.05       0  4955.8    0.12       0
  5604.4    0.05       0  5639.6    0.12       0
Bank Sta=4951.8,4955.8
Exp/Cntr=0.3,0.1

Chan Stop Cuts=-1