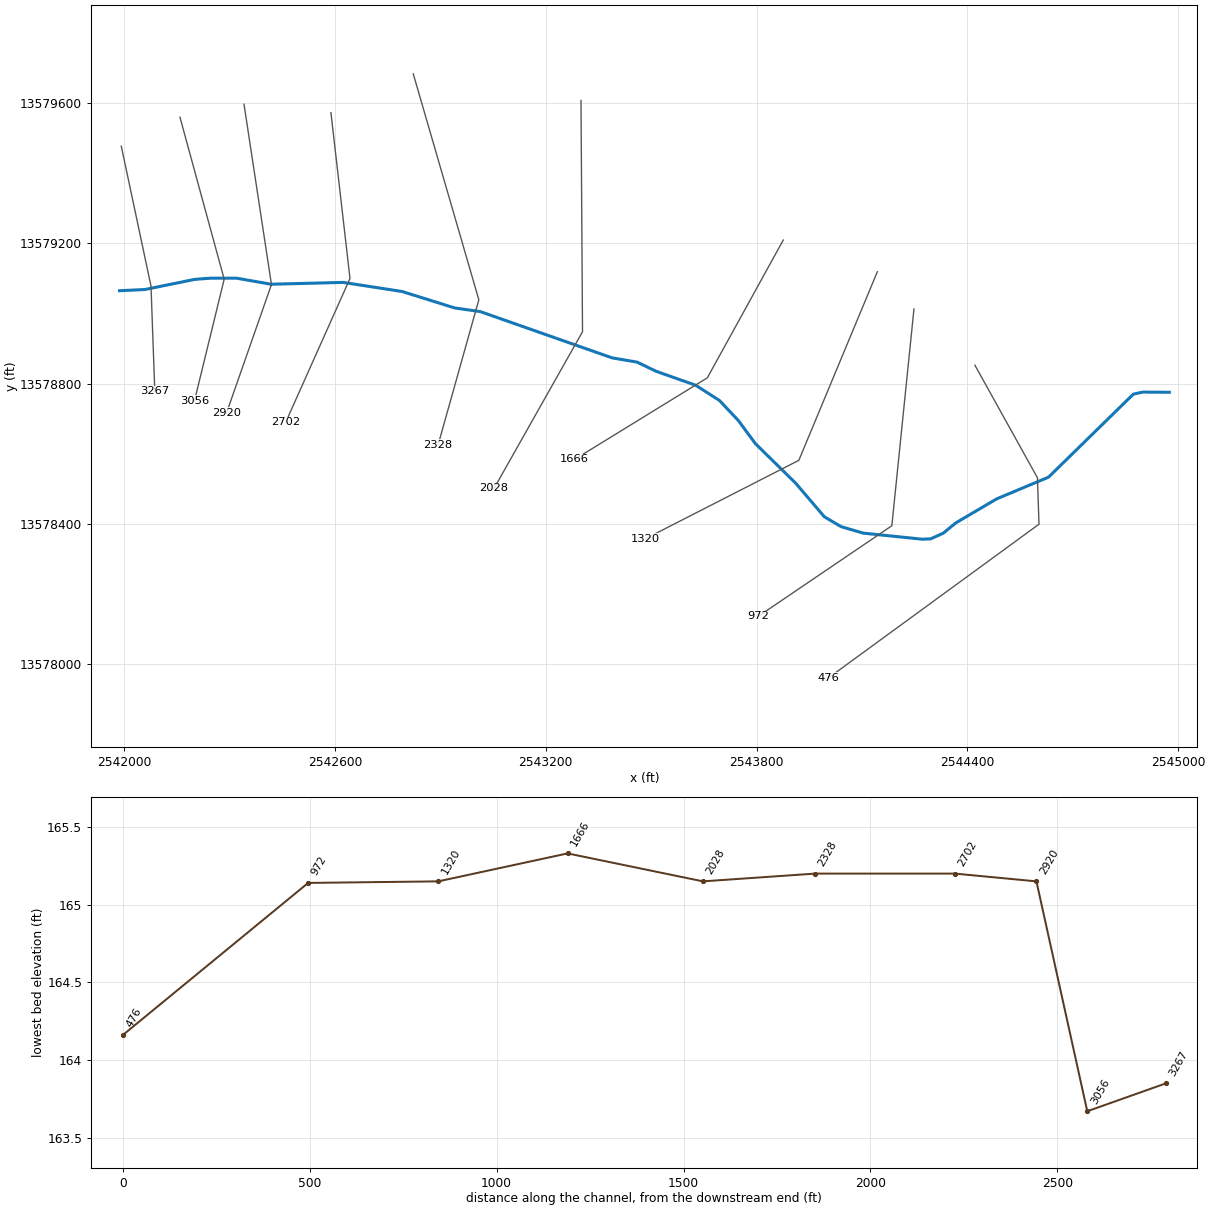
--- LG Stream067.prj (project) ---

Proj Title=LG Stream067 Base Level Engineering
Current Plan=p01
Default Exp/Contr=0.3,0.1
English Units
Geom File=g01
Flow File=f01
Plan File=p01
Y Axis Title=Elevation
X Axis Title(PF)=Main Channel Distance
X Axis Title(XS)=Station
BEGIN DESCRIPTION:
LG Stream067
END DESCRIPTION:
DSS Export Rating Curves= 0
DSS Export Rating Curve Sorted= 0
DSS Export Volume Flow Curves= 0
DXF OffsetX= 0
DXF OffsetY= 0
DXF ScaleX= 1
DXF ScaleY= 10

--- LG Stream067.p01 (plan) ---

Plan Title=Multiple Run
Short Identifier=Multiple
Geom File=g01
Flow File=f01
Subcritical Flow
K Sum by GR= 0
Std Step Tol= 0.01
Critical Tol= 0.01
Num of Std Step Trials= 20
Max Error Tol= 0.3
Flow Tol Ratio= 0.001
Split Flow NTrial= 30
Split Flow Tol= 0.02
Split Flow Ratio= 0.02
Log Output Level= 0
Friction Slope Method= 1
Unsteady Friction Slope Method= 2
Unsteady Bridges Friction Slope Method= 1
Parabolic Critical Depth
Global Vel Dist=  1 , 1 , 1
Global Log Level= 0
CheckData=True
Encroach Param= -1, 0, 0, 0
BEGIN DESCRIPTION:
Multiple Run
END DESCRIPTION:

--- LG Stream067.f01 (steady flow) ---

Flow Title=Multiple
Number of Profiles=7
Profile Names=10-year,25-year,50-year,1pct_min,100-year,1pct_plu,500-year
River Rch & RM= LG Stream067,Reach-1,3267
     125     176     217     130     260     518     366
Boundary for River Rch & Prof#=LG Stream067,Reach-1,1
Up Type=0
Dn Type=3
Dn Slope=0.005
Boundary for River Rch & Prof#=LG Stream067,Reach-1,2
Up Type=0
Dn Type=3
Dn Slope=0.005
Boundary for River Rch & Prof#=LG Stream067,Reach-1,3
Up Type=0
Dn Type=3
Dn Slope=0.005
Boundary for River Rch & Prof#=LG Stream067,Reach-1,4
Up Type=0
Dn Type=3
Dn Slope=0.005
Boundary for River Rch & Prof#=LG Stream067,Reach-1,5
Up Type=0
Dn Type=3
Dn Slope=0.005
Boundary for River Rch & Prof#=LG Stream067,Reach-1,6
Up Type=0
Dn Type=3
Dn Slope=0.005
Boundary for River Rch & Prof#=LG Stream067,Reach-1,7
Up Type=0
Dn Type=3
Dn Slope=0.005

--- LG Stream067.g01 (geometry) ---

Geom Title=Existing Conditions

River Reach=LG Stream067,Reach-1
Reach XY= 30
      2541986.78     13579064.82      2542058.39     13579068.22
      2542201.27     13579097.23      2542246.41     13579100.70
      2542319.32     13579100.70      2542418.28     13579083.34
      2542623.14     13579088.55      2542791.54     13579062.51
      2542940.85     13579015.63      2543013.77     13579005.22
      2543388.77     13578873.27      2543459.95     13578861.12
      2543513.77     13578835.08      2543626.61     13578795.15
      2543694.32     13578751.75      2543748.14     13578694.45
      2543796.75     13578628.48      2543911.34     13578515.63
      2543993.02     13578419.76      2544040.76     13578391.55
      2544103.70     13578373.10      2544271.88     13578355.74
      2544295.75     13578356.82      2544331.56     13578373.10
      2544367.37     13578402.40      2544483.47     13578470.76
      2544631.17     13578532.86      2544872.50     13578769.65
      2544899.75     13578775.59      2544975.00     13578775.00

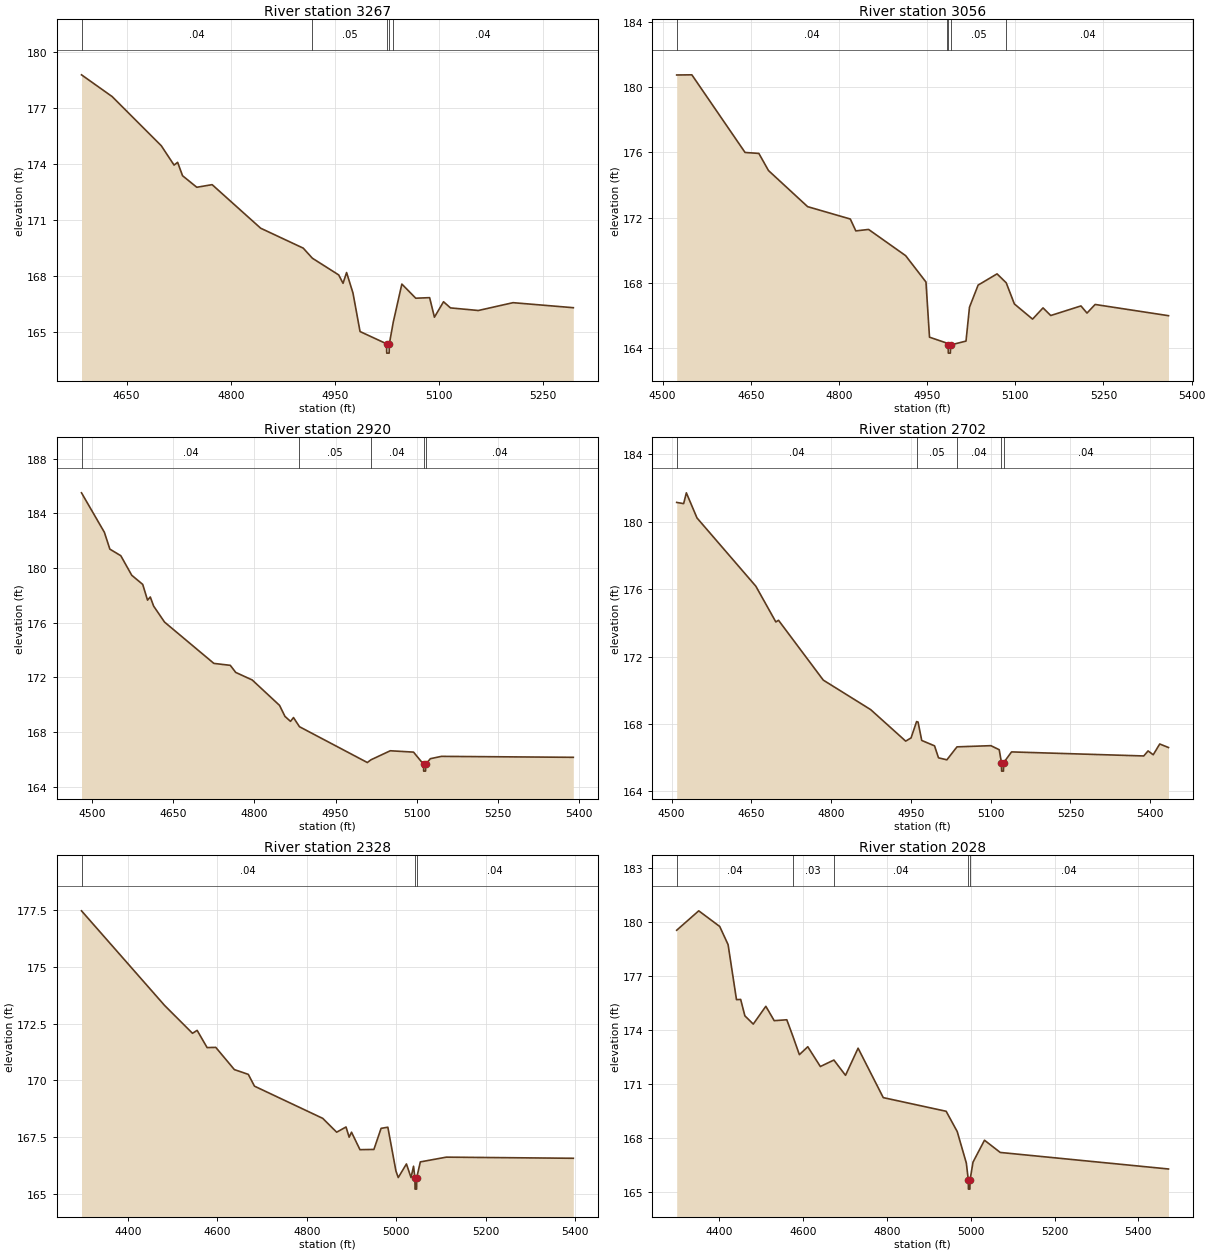
Type RM Length L Ch R = 1,3267,211,211,211
BEGIN DESCRIPTION:
Mapping XS 5e7c6347
END DESCRIPTION:
XS GIS Cut Line= 3
      2541991.71     13579477.39      2542076.34     13579078.11
      2542087.13     13578778.25
#Sta/Elev= 30
  4585.1  178.80  4629.3  177.63  4700.0  174.99  4718.4  173.95  4723.5  174.10
  4730.6  173.38  4751.1  172.76  4773.2  172.90  4843.1  170.56  4904.4  169.49
  4917.5  168.95  4955.5  168.05  4961.7  167.60  4966.8  168.18  4976.0  167.08
  4986.2  165.01  5024.4  164.35  5024.6  163.85  5028.1  163.85  5028.4  164.35
  5034.0  165.51  5046.4  167.56  5066.4  166.80  5086.4  166.83  5093.3  165.78
  5106.4  166.61  5116.4  166.28  5156.5  166.14  5206.5  166.56  5293.3  166.29
#Mann=5,-1,0
  4585.1    0.04       0  4917.5    0.05       0  5024.4    0.05       0
  5028.4    0.05       0  5034.0    0.04       0
Bank Sta=5024.4,5028.4
Exp/Cntr=0.3,0.1

Type RM Length L Ch R = 1,3056,136,136,136
BEGIN DESCRIPTION:
Mapping XS bc89473d
END DESCRIPTION:
XS GIS Cut Line= 3
      2542158.80     13579559.89      2542284.67     13579097.64
      2542200.03     13578750.38
#Sta/Elev= 30
  4524.1  180.76  4549.9  180.77  4640.4  176.00  4663.9  175.94  4680.2  174.89
  4746.8  172.67  4819.4  171.91  4828.8  171.18  4850.5  171.27  4913.5  169.66
  4948.1  168.04  4954.1  164.65  4984.1  164.28  4985.9  164.17  4986.1  163.67
  4989.6  163.67  4989.9  164.17  5016.2  164.41  5022.1  166.49  5036.8  167.85
  5069.0  168.54  5084.6  167.99  5098.5  166.69  5129.4  165.76  5147.2  166.45
  5160.3  165.98  5211.7  166.57  5222.0  166.13  5235.8  166.66  5360.6  165.97
#Mann=5,-1,0
  4524.1    0.04       0  4984.1    0.05       0  4985.9    0.05       0
  4989.9    0.05       0  5084.6    0.04       0
Bank Sta=4985.9,4989.9
Exp/Cntr=0.3,0.1

Type RM Length L Ch R = 1,2920,218,218,218
BEGIN DESCRIPTION:
Mapping XS 2515cc43
END DESCRIPTION:
XS GIS Cut Line= 3
      2542341.09     13579596.78      2542419.22     13579082.45
      2542291.18     13578715.69
#Sta/Elev= 30
  4480.7  185.51  4523.0  182.62  4533.1  181.39  4553.3  180.91  4573.5  179.48
  4593.8  178.81  4602.7  177.66  4607.8  177.89  4614.0  177.22  4634.2  176.05
  4725.3  173.03  4755.6  172.89  4765.7  172.37  4796.1  171.82  4846.6  169.96
  4856.7  169.15  4866.9  168.79  4872.4  169.07  4883.4  168.40  5008.8  165.78
  5015.6  165.98  5051.2  166.64  5094.2  166.54  5112.7  165.65  5112.9  165.15
  5116.4  165.15  5116.7  165.65  5125.3  166.06  5145.7  166.23  5389.4  166.16
#Mann=5,-1,0
  4480.7    0.04       0  4883.4    0.05       0  5015.6    0.04       0
  5112.7    0.05       0  5116.7    0.04       0
Bank Sta=5112.7,5116.7
Exp/Cntr=0.3,0.1

Type RM Length L Ch R = 1,2702,374,374,374
BEGIN DESCRIPTION:
Mapping XS d2c66ee3
END DESCRIPTION:
XS GIS Cut Line= 3
      2542588.49     13579572.93      2542642.74     13579099.81
      2542459.99     13578689.93
#Sta/Elev= 30
  4509.5  181.14  4522.6  181.07  4527.7  181.71  4547.7  180.22  4658.4  176.17
  4696.0  174.05  4701.0  174.15  4785.2  170.60  4874.3  168.85  4940.2  166.98
  4950.3  167.17  4960.7  168.14  4963.5  168.11  4970.4  167.02  4994.5  166.70
  5001.9  165.99  5017.7  165.87  5036.7  166.64  5100.5  166.71  5116.1  166.47
  5120.4  165.70  5120.6  165.20  5124.1  165.20  5124.4  165.70  5139.3  166.34
  5388.0  166.10  5396.1  166.40  5405.8  166.17  5418.0  166.81  5434.5  166.60
#Mann=5,-1,0
  4509.5    0.04       0  4960.7    0.05       0  5036.7    0.04       0
  5120.4    0.05       0  5124.4    0.04       0
Bank Sta=5120.4,5124.4
Exp/Cntr=0.3,0.1

Type RM Length L Ch R = 1,2328,300,300,300
BEGIN DESCRIPTION:
Mapping XS c17b3709
END DESCRIPTION:
XS GIS Cut Line= 3
      2542822.86     13579683.60      2543009.50     13579039.05
      2542893.69     13578625.28
#Sta/Elev= 30
  4295.8  177.47  4481.7  173.30  4544.2  172.07  4554.6  172.20  4576.9  171.44
  4596.3  171.45  4637.9  170.47  4669.1  170.26  4682.9  169.74  4835.7  168.32
  4866.9  167.71  4887.8  167.94  4894.8  167.49  4900.1  167.71  4919.0  166.94
  4950.2  166.95  4966.3  167.88  4981.4  167.93  4999.5  166.00  5004.7  165.71
  5023.0  166.31  5033.3  165.71  5038.9  166.21  5042.0  165.70  5042.3  165.20
  5045.8  165.20  5046.0  165.70  5054.1  166.40  5112.3  166.61  5396.5  166.56
#Mann=3,-1,0
  4295.8    0.04       0  5042.0    0.04       0  5046.0    0.04       0
Bank Sta=5042,5046
Exp/Cntr=0.3,0.1

Type RM Length L Ch R = 1,2028,362,362,362
BEGIN DESCRIPTION:
Mapping XS 7e67d449
END DESCRIPTION:
XS GIS Cut Line= 3
      2543300.30     13579607.63      2543304.64     13578947.90
      2543052.90     13578500.85
#Sta/Elev= 30
  4299.0  179.55  4351.6  180.63  4401.6  179.76  4421.6  178.75  4441.6  175.69
  4451.6  175.70  4461.6  174.79  4481.6  174.33  4511.6  175.32  4531.6  174.52
  4561.6  174.57  4575.4  173.70  4591.6  172.63  4611.6  173.07  4641.6  171.97
  4673.9  172.33  4701.6  171.48  4731.6  172.99  4791.6  170.24  4941.6  169.48
  4968.0  168.35  4989.7  166.60  4994.5  165.65  4994.7  165.15  4998.2  165.15
  4998.5  165.65  5005.6  166.65  5033.0  167.87  5070.6  167.19  5471.8  166.27
#Mann=5,-1,0
  4299.0    0.04       0  4575.4    0.03       0  4673.9    0.04       0
  4994.5    0.04       0  4998.5    0.04       0
Bank Sta=4994.5,4998.5
Exp/Cntr=0.3,0.1

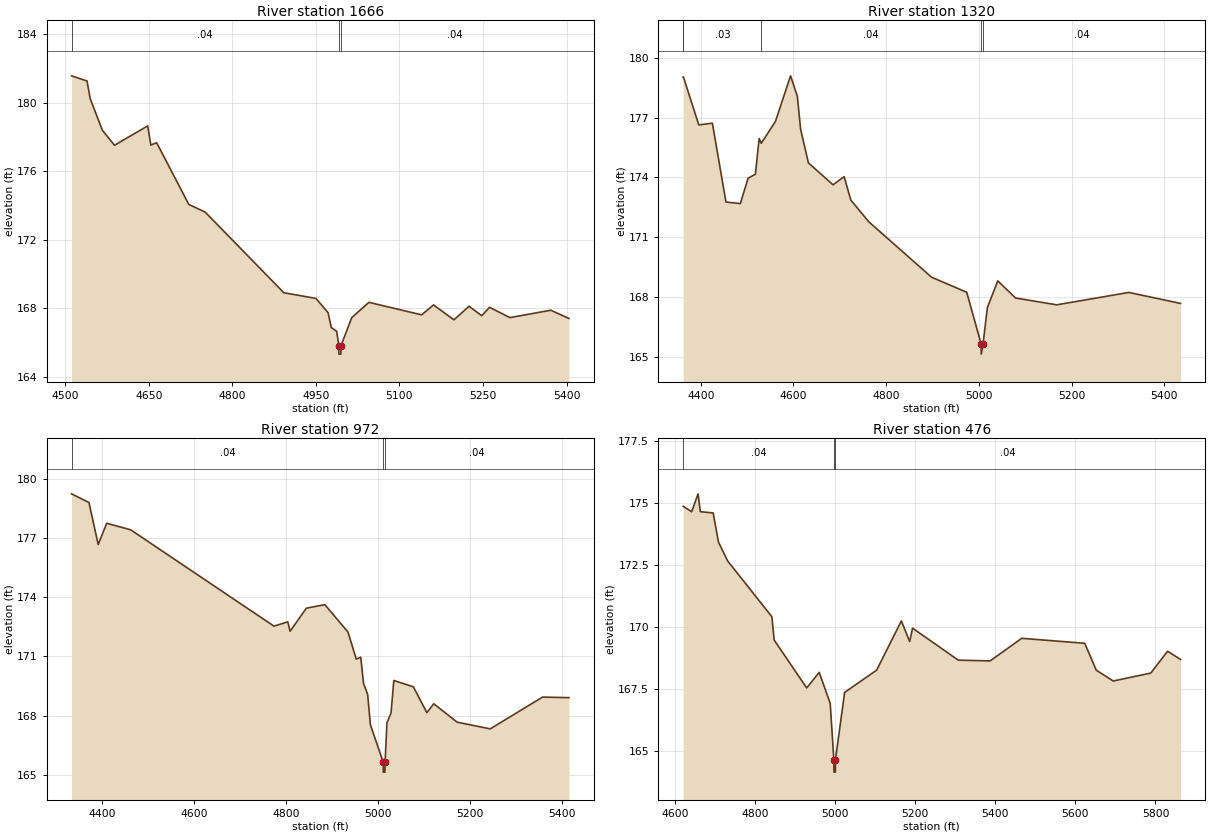
Type RM Length L Ch R = 1,1666,346,346,346
BEGIN DESCRIPTION:
Mapping XS 2c3b54c9
END DESCRIPTION:
XS GIS Cut Line= 3
      2543876.05     13579209.47      2543659.89     13578816.22
      2543281.75     13578583.22
#Sta/Elev= 30
  4511.5  181.56  4539.3  181.26  4545.0  180.23  4566.8  178.39  4588.6  177.51
  4648.2  178.64  4653.9  177.52  4664.3  177.66  4722.0  174.06  4751.5  173.61
  4892.6  168.91  4950.2  168.58  4972.0  167.75  4977.8  166.88  4987.4  166.66
  4991.3  165.83  4991.5  165.33  4995.0  165.33  4995.3  165.83  5014.5  167.46
  5045.3  168.35  5140.0  167.62  5161.3  168.20  5197.9  167.33  5225.1  168.12
  5247.9  167.57  5261.8  168.06  5298.5  167.46  5371.8  167.89  5404.4  167.41
#Mann=3,-1,0
  4511.5    0.04       0  4991.3    0.04       0  4995.3    0.04       0
Bank Sta=4991.3,4995.3
Exp/Cntr=0.3,0.1

Type RM Length L Ch R = 1,1320,348,348,348
BEGIN DESCRIPTION:
Mapping XS e13ff37f
END DESCRIPTION:
XS GIS Cut Line= 3
      2544143.89     13579119.01      2543920.38     13578580.83
      2543484.16     13578357.30
#Sta/Elev= 30
  4362.1  179.03  4362.8  179.03  4395.9  176.63  4425.2  176.72  4454.5  172.77
  4485.5  172.69  4502.2  173.96  4518.0  174.16  4526.1  175.95  4530.6  175.71
  4561.3  176.81  4593.8  179.09  4608.5  178.06  4615.5  176.42  4632.3  174.73
  4685.5  173.63  4709.4  174.04  4723.8  172.87  4762.5  171.78  4898.1  169.00
  4973.8  168.25  5005.0  165.65  5005.2  165.15  5009.0  165.65  5018.3  167.48
  5040.8  168.82  5079.2  167.96  5168.0  167.62  5323.4  168.24  5435.0  167.69
#Mann=5,-1,0
  4362.1    0.04       0  4362.8    0.03       0  4530.6    0.04       0
  5005.0    0.04       0  5009.0    0.04       0
Bank Sta=5005,5009
Exp/Cntr=0.3,0.1

Type RM Length L Ch R = 1,972,496,496,496
BEGIN DESCRIPTION:
Mapping XS 8a7791d0
END DESCRIPTION:
XS GIS Cut Line= 3
      2544248.07     13579012.70      2544185.13     13578394.20
      2543805.32     13578135.92
#Sta/Elev= 30
  4333.7  179.23  4371.6  178.79  4391.7  176.66  4410.1  177.74  4462.1  177.41
  4773.7  172.53  4803.7  172.75  4808.7  172.27  4844.0  173.44  4884.2  173.62
  4934.5  172.23  4952.5  170.86  4962.2  170.96  4968.3  169.63  4977.2  169.08
  4983.2  167.54  5011.1  165.64  5011.3  165.14  5014.8  165.14  5015.1  165.64
  5019.1  167.63  5028.0  168.13  5034.1  169.78  5076.5  169.46  5105.9  168.15
  5120.9  168.60  5171.7  167.67  5243.6  167.33  5357.4  168.94  5414.7  168.91
#Mann=3,-1,0
  4333.7    0.04       0  5011.1    0.04       0  5015.1    0.04       0
Bank Sta=5011.1,5015.1
Exp/Cntr=0.3,0.1

Type RM Length L Ch R = 1,476,0,0,0
BEGIN DESCRIPTION:
Mapping XS b8a324d5
END DESCRIPTION:
XS GIS Cut Line= 4
      2544421.66     13578852.13      2544599.63     13578530.92
      2544603.97     13578398.54      2544005.02     13577960.18
#Sta/Elev= 30
  4620.7  174.87  4642.0  174.65  4658.0  175.37  4663.7  174.65  4695.8  174.60
  4708.9  173.43  4731.7  172.67  4842.3  170.42  4848.0  169.48  4929.3  167.55
  4960.4  168.18  4987.9  166.93  4997.0  164.66  4997.3  164.16  5000.8  164.16
  5001.0  164.66  5023.9  167.37  5103.9  168.27  5165.6  170.25  5186.4  169.42
  5193.5  169.96  5307.7  168.67  5387.2  168.64  5466.1  169.55  5623.4  169.35
  5652.0  168.27  5694.5  167.83  5788.3  168.15  5830.3  169.03  5862.6  168.70
#Mann=3,-1,0
  4620.7    0.04       0  4997.0    0.04       0  5001.0    0.04       0
Bank Sta=4997,5001
Exp/Cntr=0.3,0.1

Chan Stop Cuts=-1