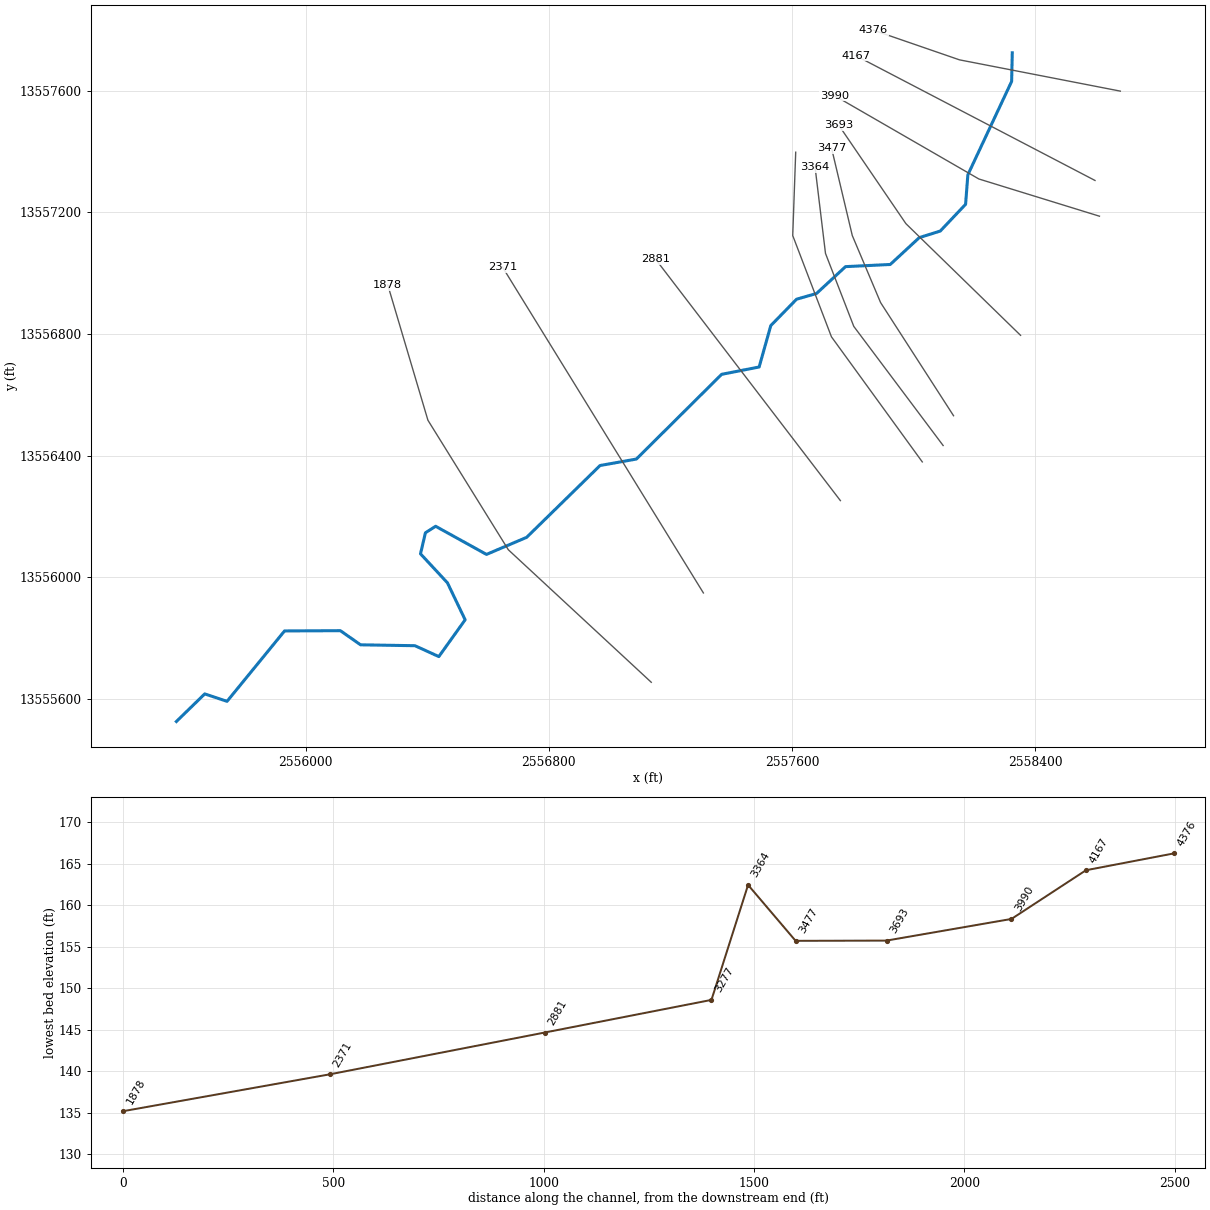
--- LG Stream082.prj (project) ---

Proj Title=LG Stream082 Base Level Engineering
Current Plan=p01
Default Exp/Contr=0.3,0.1
English Units
Geom File=g01
Flow File=f01
Plan File=p01
Y Axis Title=Elevation
X Axis Title(PF)=Main Channel Distance
X Axis Title(XS)=Station
BEGIN DESCRIPTION:
LG Stream082
END DESCRIPTION:
DSS Export Rating Curves= 0
DSS Export Rating Curve Sorted= 0
DSS Export Volume Flow Curves= 0
DXF OffsetX= 0
DXF OffsetY= 0
DXF ScaleX= 1
DXF ScaleY= 10

--- LG Stream082.p01 (plan) ---

Plan Title=Multiple Run
Short Identifier=Multiple
Geom File=g01
Flow File=f01
Subcritical Flow
K Sum by GR= 0
Std Step Tol= 0.01
Critical Tol= 0.01
Num of Std Step Trials= 20
Max Error Tol= 0.3
Flow Tol Ratio= 0.001
Split Flow NTrial= 30
Split Flow Tol= 0.02
Split Flow Ratio= 0.02
Log Output Level= 0
Friction Slope Method= 1
Unsteady Friction Slope Method= 2
Unsteady Bridges Friction Slope Method= 1
Parabolic Critical Depth
Global Vel Dist=  1 , 1 , 1
Global Log Level= 0
CheckData=True
Encroach Param= -1, 0, 0, 0
BEGIN DESCRIPTION:
Multiple Run
END DESCRIPTION:

--- LG Stream082.f01 (steady flow) ---

Flow Title=Multiple
Number of Profiles=7
Profile Names=10-year,25-year,50-year,1pct_min,100-year,1pct_plu,500-year
River Rch & RM= LG Stream082,Reach-1,4376
     537     858    1147     745    1486    2965    2465
Boundary for River Rch & Prof#=LG Stream082,Reach-1,1
Up Type=0
Dn Type=3
Dn Slope=0.005
Boundary for River Rch & Prof#=LG Stream082,Reach-1,2
Up Type=0
Dn Type=3
Dn Slope=0.005
Boundary for River Rch & Prof#=LG Stream082,Reach-1,3
Up Type=0
Dn Type=3
Dn Slope=0.005
Boundary for River Rch & Prof#=LG Stream082,Reach-1,4
Up Type=0
Dn Type=3
Dn Slope=0.005
Boundary for River Rch & Prof#=LG Stream082,Reach-1,5
Up Type=0
Dn Type=3
Dn Slope=0.005
Boundary for River Rch & Prof#=LG Stream082,Reach-1,6
Up Type=0
Dn Type=3
Dn Slope=0.005
Boundary for River Rch & Prof#=LG Stream082,Reach-1,7
Up Type=0
Dn Type=3
Dn Slope=0.005

--- LG Stream082.g01 (geometry) ---

Geom Title=Existing Conditions

River Reach=LG Stream082,Reach-1
Reach XY= 30
      2558325.00     13557725.00      2558322.90     13557630.87
      2558178.83     13557323.41      2558171.39     13557226.48
      2558088.24     13557138.62      2558018.96     13557116.82
      2557923.53     13557028.55      2557776.47     13557021.45
      2557681.04     13556933.18      2557615.30     13556914.23
      2557530.52     13556827.44      2557492.21     13556691.27
      2557368.83     13556667.14      2557088.30     13556388.40
      2556968.83     13556367.14      2556727.30     13556130.83
      2556595.18     13556074.70      2556428.00     13556167.24
      2556394.40     13556146.03      2556378.11     13556076.71
      2556466.84     13555981.05      2556524.99     13555859.58
      2556438.42     13555738.52      2556359.84     13555774.34
      2556180.94     13555777.26      2556114.49     13555823.78
      2555930.84     13555822.95      2555741.70     13555591.38
      2555668.33     13555615.83      2555575.00     13555525.00

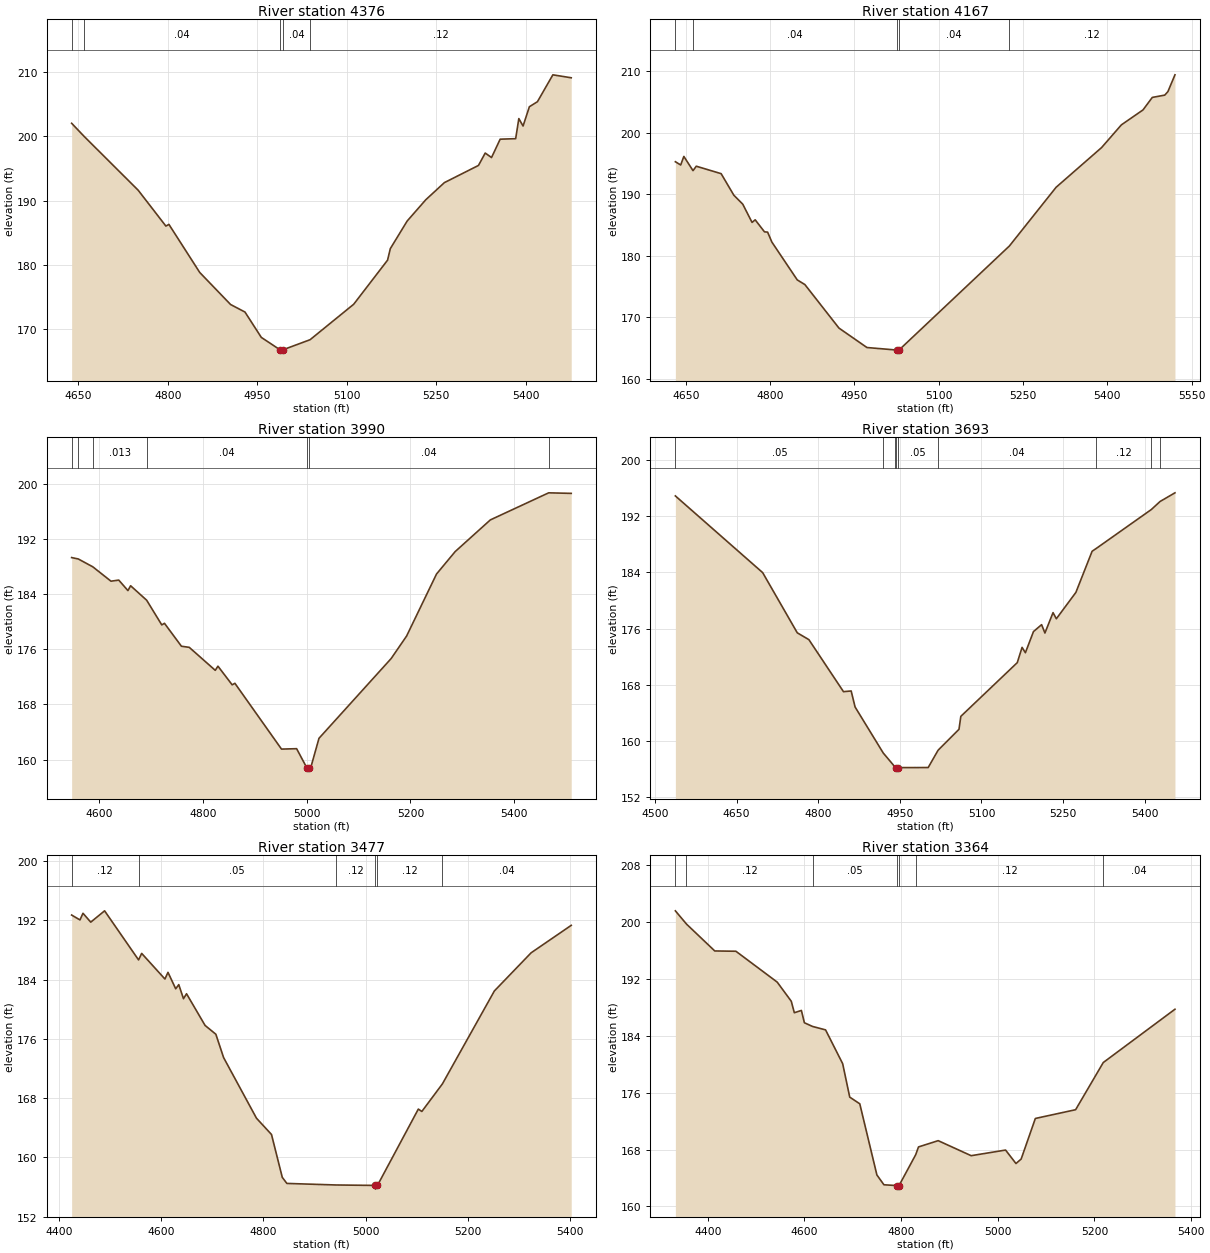
Type RM Length L Ch R = 1,4376,209,209,209
BEGIN DESCRIPTION:
LGII3526
END DESCRIPTION:
XS GIS Cut Line= 3
      2558680.46     13557598.89      2558151.40     13557701.76
      2557868.61     13557799.27
#Sta/Elev= 30
  4638.6  202.06  4659.6  200.01  4750.2  191.63  4796.7  186.04  4801.8  186.30
  4853.5  178.81  4905.2  173.82  4929.4  172.64  4956.8  168.69  4988.5  166.74
  4988.8  166.24  4992.5  166.74  5038.6  168.33  5111.8  173.86  5168.6  180.73
  5173.2  182.52  5201.5  186.83  5232.7  190.14  5263.9  192.81  5321.1  195.49
  5332.4  197.42  5343.0  196.72  5357.5  199.58  5383.5  199.66  5388.8  202.79
  5395.9  201.63  5406.5  204.64  5420.0  205.42  5445.9  209.61  5476.7  209.15
#Mann=5,-1,0
  4638.6    0.12       0  4659.6    0.04       0  4988.5    0.04       0
  4992.5    0.04       0  5038.6    0.12       0
Bank Sta=4988.5,4992.5
Exp/Cntr=0.3,0.1

Type RM Length L Ch R = 1,4167,177,177,177
BEGIN DESCRIPTION:
LGII3525
END DESCRIPTION:
XS GIS Cut Line= 2
      2558597.19     13557304.96      2557809.28     13557716.04
#Sta/Elev= 30
  4631.6  195.31  4641.1  194.78  4646.7  196.17  4663.0  193.86  4668.8  194.58
  4713.0  193.37  4735.6  189.87  4751.5  188.41  4768.0  185.45  4773.6  185.87
  4790.1  183.92  4795.7  183.87  4803.3  182.25  4848.4  176.11  4862.0  175.35
  4922.6  168.28  4972.4  165.12  5025.4  164.71  5025.7  164.21  5029.2  164.21
  5029.4  164.71  5225.8  181.62  5308.9  191.16  5389.8  197.61  5425.0  201.30
  5463.5  203.73  5480.0  205.76  5502.1  206.13  5507.7  206.69  5520.3  209.43
#Mann=5,-1,0
  4631.6   0.013       0  4663.0    0.04       0  5025.4    0.04       0
  5029.4    0.04       0  5225.8    0.12       0
Bank Sta=5025.4,5029.4
Exp/Cntr=0.3,0.1

Type RM Length L Ch R = 1,3990,297,297,297
BEGIN DESCRIPTION:
LGII3524
END DESCRIPTION:
XS GIS Cut Line= 3
      2558611.85     13557187.39      2558215.08     13557309.85
      2557739.92     13557584.17
#Sta/Elev= 30
  4546.4  189.27  4559.2  189.07  4587.3  187.93  4622.3  185.85  4637.3  186.01
  4655.0  184.49  4660.2  185.19  4691.2  183.09  4720.3  179.52  4725.5  179.75
  4758.2  176.43  4773.3  176.27  4823.5  172.94  4828.7  173.54  4856.1  170.84
  4861.4  171.06  4951.3  161.53  4980.5  161.59  5000.0  158.84  5000.3  158.34
  5004.0  158.84  5007.9  158.89  5023.6  163.09  5162.9  174.65  5192.7  177.91
  5250.4  186.89  5286.4  190.14  5354.3  194.73  5466.8  198.65  5510.3  198.57
#Mann=7,-1,0
  4546.4    0.05       0  4559.2    0.04       0  4587.3   0.013       0
  4691.2    0.04       0  5000.0    0.04       0  5004.0    0.04       0
  5466.8    0.12       0
Bank Sta=5000,5004
Exp/Cntr=0.3,0.1

Type RM Length L Ch R = 1,3693,216,216,216
BEGIN DESCRIPTION:
LGII3523
END DESCRIPTION:
XS GIS Cut Line= 3
      2558352.26     13556795.45      2557975.04     13557162.88
      2557754.60     13557486.19
#Sta/Elev= 30
  4537.6  194.87  4698.0  183.96  4761.6  175.40  4782.9  174.43  4846.5  167.03
  4860.6  167.13  4867.8  164.85  4919.6  158.30  4941.9  156.25  4943.5  156.23
  4943.8  155.73  4947.5  156.23  5002.1  156.24  5020.3  158.70  5058.7  161.68
  5062.1  163.52  5165.8  171.16  5174.6  173.33  5180.7  172.57  5195.6  175.58
  5210.5  176.56  5216.6  175.37  5231.5  178.27  5237.6  177.40  5273.5  181.15
  5303.3  187.00  5311.1  187.41  5412.2  192.94  5428.2  194.08  5455.5  195.31
#Mann=9,-1,0
  4537.6    0.05       0  4919.6    0.04       0  4941.9    0.05       0
  4943.5    0.05       0  4947.5    0.05       0  5020.3    0.04       0
  5311.1    0.12       0  5412.2    0.04       0  5428.2    0.12       0
Bank Sta=4943.5,4947.5
Exp/Cntr=0.3,0.1

Type RM Length L Ch R = 1,3477,113,113,113
BEGIN DESCRIPTION:
LGII3521
END DESCRIPTION:
XS GIS Cut Line= 4
      2558131.79     13556530.94      2557891.76     13556903.24
      2557798.68     13557123.69      2557730.42     13557411.33
#Sta/Elev= 30
  4424.7  192.72  4441.0  192.06  4446.9  192.96  4462.1  191.76  4489.2  193.29
  4555.7  186.66  4561.8  187.54  4607.3  184.08  4613.3  184.98  4628.4  182.76
  4634.4  183.32  4643.6  181.42  4649.6  182.09  4685.9  177.81  4707.0  176.62
  4722.2  173.46  4786.5  165.28  4815.9  163.08  4837.0  157.29  4846.0  156.47
  4942.1  156.26  5019.3  156.20  5019.5  155.70  5023.3  156.20  5103.3  166.51
  5110.2  166.19  5150.4  169.91  5252.2  182.47  5324.1  187.62  5402.6  191.33
#Mann=6,-1,0
  4424.7    0.12       0  4555.7    0.05       0  4942.1    0.12       0
  5019.3    0.05       0  5023.3    0.12       0  5150.4    0.04       0
Bank Sta=5019.3,5023.3
Exp/Cntr=0.3,0.1

Type RM Length L Ch R = 1,3364,87,87,87
BEGIN DESCRIPTION:
LGII3520
END DESCRIPTION:
XS GIS Cut Line= 4
      2558097.51     13556432.95      2557803.58     13556824.86
      2557710.50     13557064.90      2557676.21     13557348.99
#Sta/Elev= 30
  4333.0  201.55  4356.0  199.69  4414.5  195.91  4458.2  195.87  4543.7  191.53
  4572.8  188.84  4579.1  187.23  4593.7  187.55  4599.9  185.82  4616.8  185.30
  4643.7  184.82  4679.1  180.07  4693.7  175.37  4714.5  174.43  4749.9  164.43
  4764.5  163.05  4791.7  162.94  4791.9  162.44  4795.7  162.94  4830.2  167.28
  4836.0  168.37  4876.7  169.25  4944.9  167.14  5016.1  167.93  5037.6  166.04
  5048.3  166.66  5077.7  172.37  5161.0  173.60  5218.2  180.23  5366.5  187.72
#Mann=7,-1,0
  4333.0    0.05       0  4356.0    0.12       0  4616.8    0.05       0
  4791.7    0.05       0  4795.7    0.05       0  4830.2    0.12       0
  5218.2    0.04       0
Bank Sta=4791.7,4795.7
Exp/Cntr=0.3,0.1

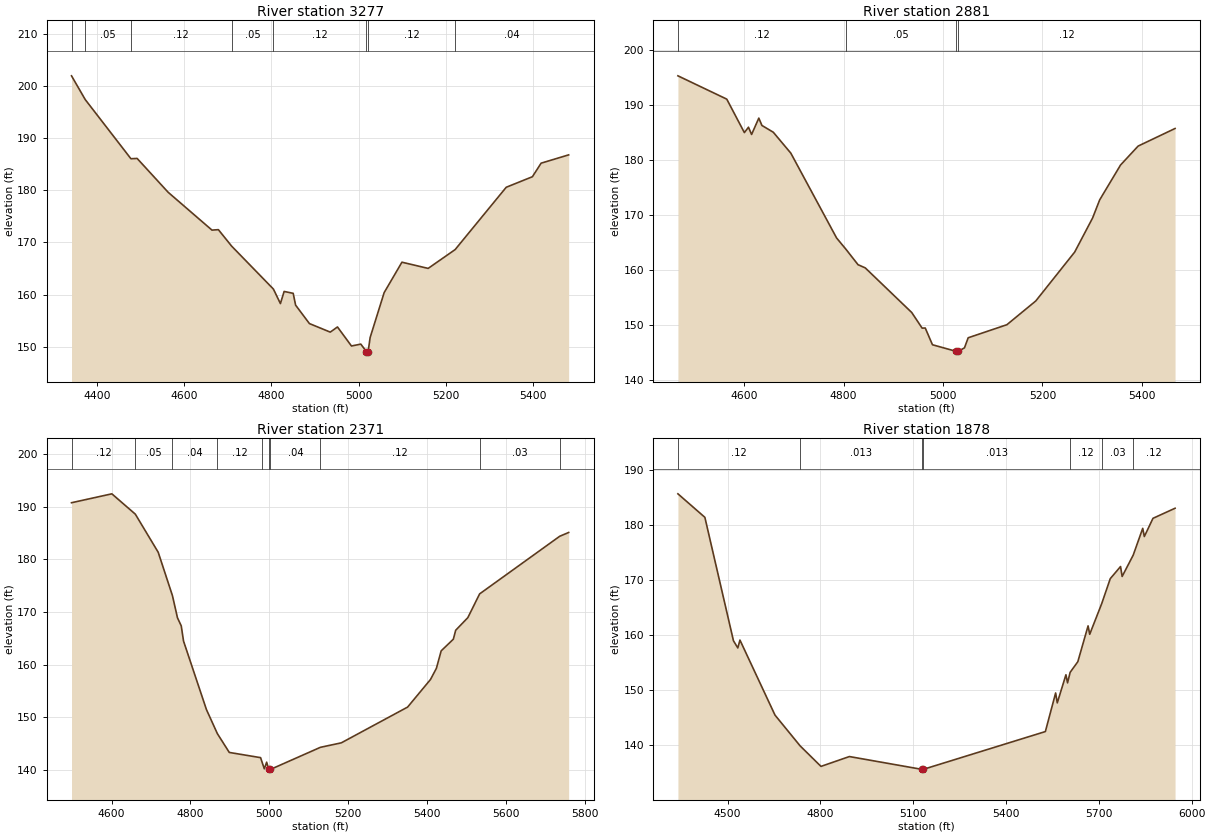
Type RM Length L Ch R = 1,3277,396,396,396
BEGIN DESCRIPTION:
LGII3522
END DESCRIPTION:
XS GIS Cut Line= 4
      2558028.91     13556379.07      2557730.09     13556790.56
      2557602.72     13557123.69      2557612.52     13557398.02
#Sta/Elev= 30
  4341.6  201.95  4373.1  197.39  4477.8  186.05  4492.0  186.11  4563.1  179.62
  4663.6  172.36  4678.3  172.45  4708.7  169.29  4804.5  161.05  4820.5  158.27
  4829.0  160.60  4849.8  160.24  4855.3  157.98  4887.0  154.44  4934.8  152.80
  4951.3  153.79  4983.4  150.14  5004.8  150.50  5017.6  149.08  5017.9  148.58
  5021.6  149.08  5026.2  151.76  5058.3  160.37  5099.1  166.21  5159.2  165.02
  5221.1  168.63  5338.2  180.58  5398.2  182.60  5418.2  185.20  5481.3  186.79
#Mann=8,-1,0
  4341.6    0.12       0  4373.1    0.05       0  4477.8    0.12       0
  4708.7    0.05       0  4804.5    0.12       0  5017.6    0.05       0
  5021.6    0.12       0  5221.1    0.04       0
Bank Sta=5017.6,5021.6
Exp/Cntr=0.3,0.1

Type RM Length L Ch R = 1,2881,510,510,510
BEGIN DESCRIPTION:
LGII3519
END DESCRIPTION:
XS GIS Cut Line= 2
      2557759.49     13556251.68      2557152.04     13557045.28
#Sta/Elev= 30
  4467.1  195.38  4565.3  191.13  4600.7  185.03  4608.9  186.01  4615.2  184.69
  4629.7  187.67  4636.0  186.33  4658.8  185.10  4694.1  181.28  4786.1  165.82
  4805.1  163.74  4829.2  160.95  4843.7  160.37  4937.2  152.23  4958.0  149.39
  4964.3  149.41  4978.8  146.36  5026.7  145.15  5026.9  144.65  5030.7  145.15
  5043.2  145.80  5050.6  147.63  5128.4  150.01  5186.5  154.34  5264.7  163.25
  5300.7  169.46  5315.0  172.77  5356.9  179.12  5392.2  182.57  5466.5  185.78
#Mann=4,-1,0
  4467.1    0.12       0  4805.1    0.05       0  5026.7    0.05       0
  5030.7    0.12       0
Bank Sta=5026.7,5030.7
Exp/Cntr=0.3,0.1

Type RM Length L Ch R = 1,2371,493,493,493
BEGIN DESCRIPTION:
LGII3518
END DESCRIPTION:
XS GIS Cut Line= 2
      2557308.78     13555947.96      2556647.70     13557020.37
#Sta/Elev= 30
  4498.5  190.77  4600.7  192.46  4660.2  188.60  4718.2  181.36  4754.3  173.12
  4767.0  168.92  4776.6  167.38  4782.4  164.49  4840.4  151.50  4868.1  146.93
  4898.3  143.36  4977.6  142.37  4981.9  141.41  4987.1  140.25  4993.0  141.51
  4998.2  140.12  4998.4  139.62  5002.2  140.12  5129.2  144.33  5182.2  145.18
  5350.2  151.97  5408.2  157.21  5423.1  159.32  5435.3  162.65  5466.1  164.86
  5472.0  166.55  5502.8  168.95  5532.7  173.46  5735.6  184.40  5758.3  185.12
#Mann=10,-1,0
  4498.5    0.12       0  4660.2    0.05       0  4754.3    0.04       0
  4868.1    0.12       0  4981.9    0.04       0  4998.2    0.04       0
  5002.2    0.04       0  5129.2    0.12       0  5532.7    0.03       0
  5735.6    0.12       0
Bank Sta=4998.2,5002.2
Exp/Cntr=0.3,0.1

Type RM Length L Ch R = 1,1878,0,0,0
BEGIN DESCRIPTION:
LGII3517
END DESCRIPTION:
XS GIS Cut Line= 4
      2557137.32     13555654.02      2556667.03     13556090.02
      2556402.49     13556516.22      2556270.51     13556961.02
#Sta/Elev= 30
  4339.5  185.72  4426.6  181.45  4519.0  159.03  4533.1  157.72  4540.0  159.15
  4653.3  145.52  4734.5  139.93  4801.9  136.20  4893.7  137.99  5128.3  135.66
  5128.6  135.16  5132.3  135.66  5527.2  142.53  5560.4  149.54  5565.7  147.74
  5593.7  152.85  5598.9  151.38  5607.3  153.29  5632.1  155.22  5665.3  161.73
  5670.5  160.20  5709.2  165.75  5737.0  170.31  5770.2  172.51  5775.4  170.71
  5811.2  174.59  5841.9  179.45  5847.1  177.96  5875.1  181.27  5946.4  183.10
#Mann=7,-1,0
  4339.5    0.12       0  4734.5   0.013       0  5128.3    0.03       0
  5132.3   0.013       0  5607.3    0.12       0  5709.2    0.03       0
  5811.2    0.12       0
Bank Sta=5128.3,5132.3
Exp/Cntr=0.3,0.1

Chan Stop Cuts=-1