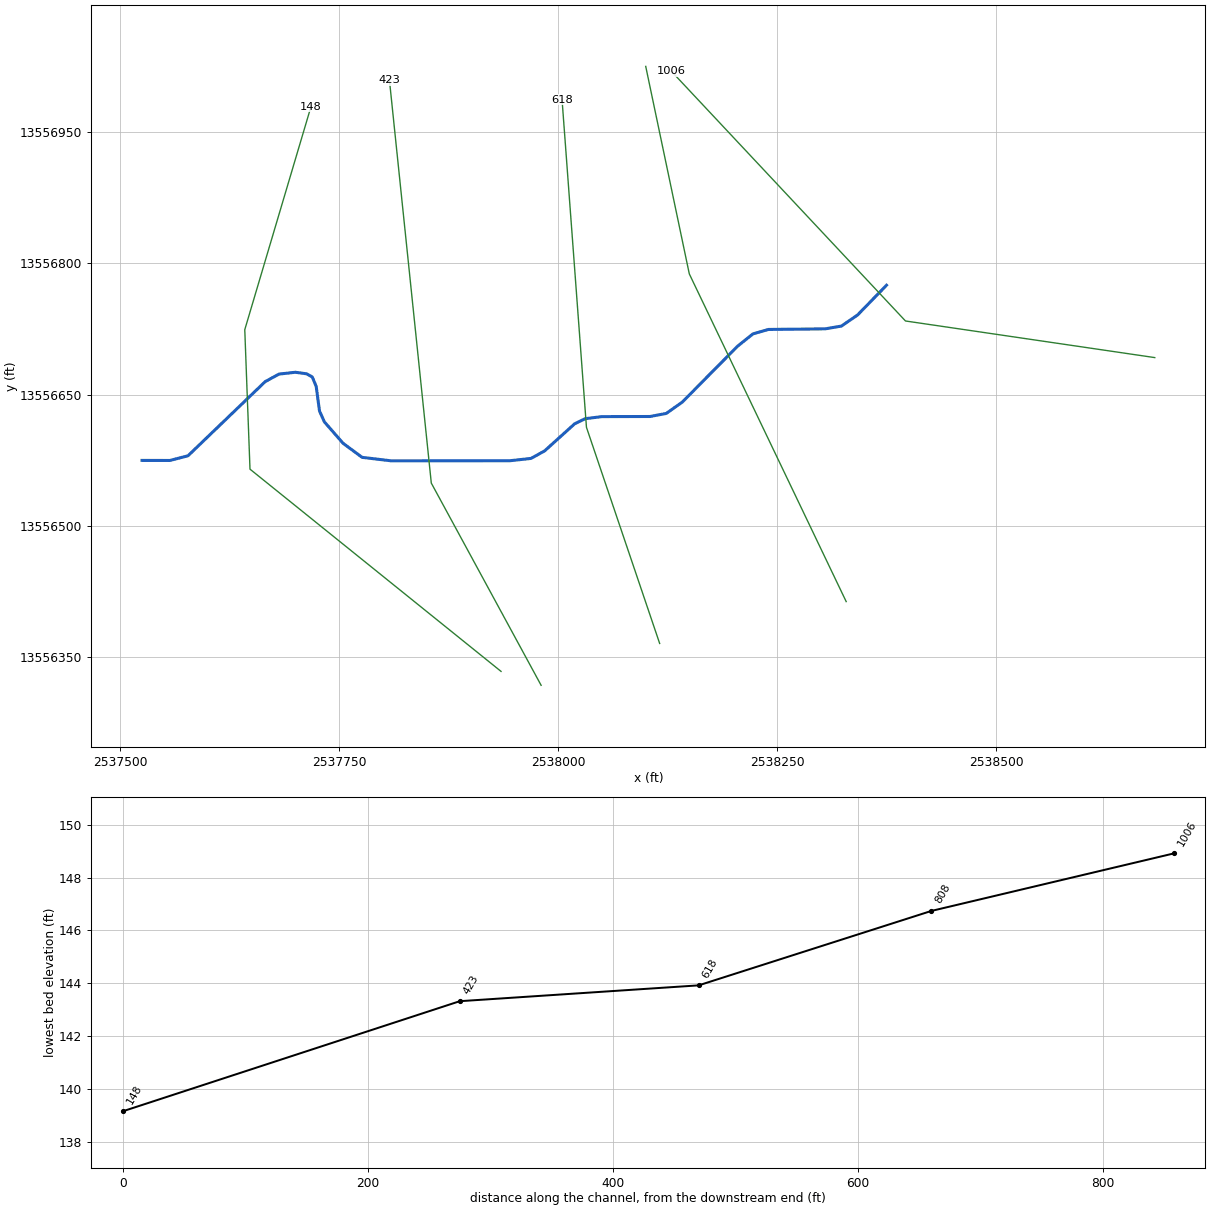
--- LG Stream088.prj (project) ---

Proj Title=LG Stream088 Base Level Engineering
Current Plan=p01
Default Exp/Contr=0.3,0.1
English Units
Geom File=g01
Flow File=f01
Plan File=p01
Y Axis Title=Elevation
X Axis Title(PF)=Main Channel Distance
X Axis Title(XS)=Station
BEGIN DESCRIPTION:
LG Stream088
END DESCRIPTION:
DSS Export Rating Curves= 0
DSS Export Rating Curve Sorted= 0
DSS Export Volume Flow Curves= 0
DXF OffsetX= 0
DXF OffsetY= 0
DXF ScaleX= 1
DXF ScaleY= 10

--- LG Stream088.p01 (plan) ---

Plan Title=Multiple Run
Short Identifier=Multiple
Geom File=g01
Flow File=f01
Subcritical Flow
K Sum by GR= 0
Std Step Tol= 0.01
Critical Tol= 0.01
Num of Std Step Trials= 20
Max Error Tol= 0.3
Flow Tol Ratio= 0.001
Split Flow NTrial= 30
Split Flow Tol= 0.02
Split Flow Ratio= 0.02
Log Output Level= 0
Friction Slope Method= 1
Unsteady Friction Slope Method= 2
Unsteady Bridges Friction Slope Method= 1
Parabolic Critical Depth
Global Vel Dist=  1 , 1 , 1
Global Log Level= 0
CheckData=True
Encroach Param= -1, 0, 0, 0
BEGIN DESCRIPTION:
Multiple Run
END DESCRIPTION:

--- LG Stream088.f01 (steady flow) ---

Flow Title=Multiple
Number of Profiles=7
Profile Names=10-year,25-year,50-year,1pct_min,100-year,1pct_plu,500-year
River Rch & RM= LG Stream088,Reach-1,1006
     404     629     825     526    1049    2093    1675
Boundary for River Rch & Prof#=LG Stream088,Reach-1,1
Up Type=0
Dn Type=3
Dn Slope=0.005
Boundary for River Rch & Prof#=LG Stream088,Reach-1,2
Up Type=0
Dn Type=3
Dn Slope=0.005
Boundary for River Rch & Prof#=LG Stream088,Reach-1,3
Up Type=0
Dn Type=3
Dn Slope=0.005
Boundary for River Rch & Prof#=LG Stream088,Reach-1,4
Up Type=0
Dn Type=3
Dn Slope=0.005
Boundary for River Rch & Prof#=LG Stream088,Reach-1,5
Up Type=0
Dn Type=3
Dn Slope=0.005
Boundary for River Rch & Prof#=LG Stream088,Reach-1,6
Up Type=0
Dn Type=3
Dn Slope=0.005
Boundary for River Rch & Prof#=LG Stream088,Reach-1,7
Up Type=0
Dn Type=3
Dn Slope=0.005

--- LG Stream088.g01 (geometry) ---

Geom Title=Existing Conditions

River Reach=LG Stream088,Reach-1
Reach XY= 30
      2538375.00     13556775.00      2538342.05     13556741.13
      2538323.59     13556728.39      2538304.92     13556725.19
      2538240.20     13556724.52      2538222.57     13556719.48
      2538204.86     13556705.33      2538141.74     13556641.49
      2538123.50     13556628.62      2538104.95     13556625.13
      2538050.00     13556624.99      2538030.98     13556622.64
      2538018.97     13556616.81      2537984.65     13556585.85
      2537969.06     13556577.26      2537945.15     13556574.64
      2537809.74     13556574.49      2537776.26     13556578.48
      2537754.49     13556594.56      2537733.15     13556619.02
      2537727.61     13556631.42      2537723.82     13556659.49
      2537719.37     13556670.23      2537712.96     13556673.86
      2537700.08     13556675.62      2537681.43     13556673.58
      2537665.59     13556664.94      2537577.51     13556580.33
      2537556.88     13556574.93      2537525.00     13556575.00

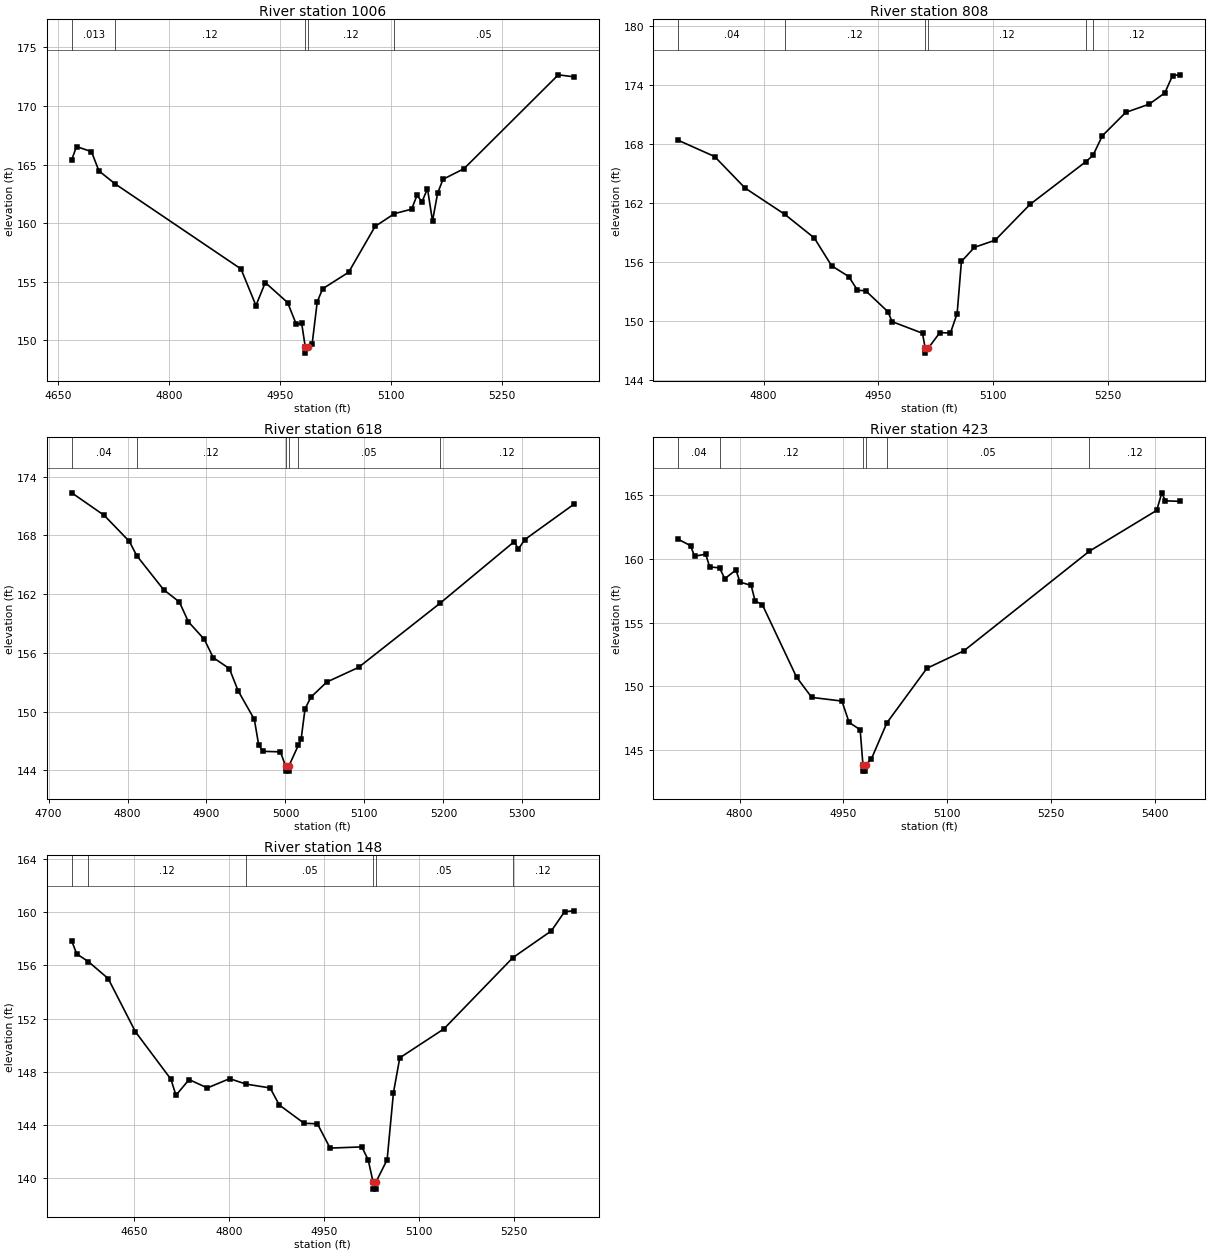
Type RM Length L Ch R = 1,1006,198,198,198
BEGIN DESCRIPTION:
LGII3516
END DESCRIPTION:
XS GIS Cut Line= 3
      2538681.30     13556692.39      2538396.66     13556734.19
      2538129.37     13557019.31
#Sta/Elev= 30
  4668.4  165.43  4674.8  166.54  4695.0  166.11  4705.1  164.46  4727.4  163.34
  4897.1  156.10  4917.3  152.98  4929.9  154.94  4960.1  153.23  4971.8  151.38
  4979.1  151.46  4984.0  149.42  4984.2  148.92  4988.0  149.42  4993.3  149.73
  5000.1  153.29  5007.4  154.41  5042.6  155.82  5078.3  159.73  5104.5  160.82
  5127.6  161.20  5134.9  162.37  5141.8  161.84  5149.1  162.95  5155.9  160.19
  5162.8  162.56  5170.1  163.75  5198.4  164.65  5325.9  172.66  5346.9  172.49
#Mann=5,-1,0
  4668.4   0.013       0  4727.4    0.12       0  4984.0    0.05       0
  4988.0    0.12       0  5104.5    0.05       0
Bank Sta=4984,4988
Exp/Cntr=0.3,0.1

Type RM Length L Ch R = 1,808,190,190,190
BEGIN DESCRIPTION:
LGII3515
END DESCRIPTION:
XS GIS Cut Line= 3
      2538328.97     13556413.77      2538149.84     13556787.94
      2538100.08     13557024.84
#Sta/Elev= 30
  4688.3  168.36  4735.9  166.71  4775.7  163.51  4827.7  160.84  4866.3  158.44
  4889.0  155.61  4911.4  154.52  4922.8  153.13  4933.6  153.07  4962.6  150.95
  4968.1  149.94  5007.9  148.76  5011.4  147.24  5011.7  146.74  5015.4  147.24
  5030.6  148.83  5044.4  148.78  5053.2  150.76  5058.8  156.05  5075.9  157.49
  5102.9  158.21  5148.6  161.85  5221.3  166.17  5230.9  166.82  5243.2  168.82
  5273.8  171.19  5304.5  172.03  5324.9  173.17  5335.1  174.94  5345.2  175.01
#Mann=6,-1,0
  4688.3    0.04       0  4827.7    0.12       0  5011.4    0.05       0
  5015.4    0.12       0  5221.3    0.05       0  5230.9    0.12       0
Bank Sta=5011.4,5015.4
Exp/Cntr=0.3,0.1

Type RM Length L Ch R = 1,618,195,195,195
BEGIN DESCRIPTION:
LGII3514
END DESCRIPTION:
XS GIS Cut Line= 3
      2538115.99     13556365.99      2538032.41     13556612.77
      2538004.54     13556986.99
#Sta/Elev= 30
  4729.4  172.34  4770.6  170.03  4802.3  167.38  4811.7  165.92  4845.7  162.45
  4865.6  161.20  4877.1  159.17  4897.3  157.37  4908.5  155.51  4929.0  154.39
  4940.0  152.13  4960.6  149.20  4966.1  146.59  4971.4  145.94  4993.6  145.89
  5000.2  144.42  5000.5  143.92  5004.0  143.92  5004.2  144.42  5016.2  146.54
  5019.8  147.15  5024.8  150.29  5032.3  151.48  5052.4  153.02  5092.5  154.51
  5195.4  161.04  5289.8  167.36  5294.9  166.58  5303.0  167.56  5365.2  171.17
#Mann=6,-1,0
  4729.4    0.04       0  4811.7    0.12       0  5000.2    0.05       0
  5004.2    0.12       0  5016.2    0.05       0  5195.4    0.12       0
Bank Sta=5000.2,5004.2
Exp/Cntr=0.3,0.1

Type RM Length L Ch R = 1,423,275,275,275
BEGIN DESCRIPTION:
LGII3513
END DESCRIPTION:
XS GIS Cut Line= 3
      2537980.63     13556318.23      2537855.26     13556549.08
      2537807.48     13557008.90
#Sta/Elev= 30
  4711.5  161.56  4729.3  161.05  4735.0  160.23  4751.2  160.38  4756.9  159.38
  4771.1  159.31  4778.7  158.46  4794.9  159.14  4800.6  158.19  4816.8  157.93
  4822.5  156.70  4832.9  156.42  4882.3  150.72  4904.2  149.12  4947.9  148.83
  4958.2  147.15  4974.2  146.58  4978.2  143.82  4978.4  143.32  4981.9  143.32
  4982.2  143.82  4990.2  144.25  5012.8  147.12  5070.6  151.41  5123.9  152.78
  5305.2  160.62  5402.4  163.83  5409.8  165.21  5414.8  164.58  5436.5  164.54
#Mann=6,-1,0
  4711.5    0.04       0  4771.1    0.12       0  4978.2    0.05       0
  4982.2    0.12       0  5012.8    0.05       0  5305.2    0.12       0
Bank Sta=4978.2,4982.2
Exp/Cntr=0.3,0.1

Type RM Length L Ch R = 1,148,0,0,0
BEGIN DESCRIPTION:
LGII3512
END DESCRIPTION:
XS GIS Cut Line= 4
      2537934.90     13556334.09      2537648.25     13556565.00
      2537642.28     13556724.24      2537717.91     13556979.00
#Sta/Elev= 30
  4551.0  157.83  4558.9  156.86  4577.1  156.29  4608.5  155.01  4651.6  151.00
  4707.6  147.43  4715.6  146.22  4736.4  147.40  4765.2  146.77  4800.4  147.47
  4826.3  147.06  4864.4  146.77  4878.8  145.49  4918.0  144.11  4939.1  144.07
  4959.1  142.24  5009.2  142.33  5019.2  141.37  5027.2  139.65  5027.4  139.15
  5030.9  139.15  5031.2  139.65  5049.2  141.36  5059.2  146.41  5069.2  149.04
  5138.7  151.21  5247.8  156.58  5308.7  158.60  5329.6  160.05  5344.2  160.11
#Mann=6,-1,0
  4551.0    0.04       0  4577.1    0.12       0  4826.3    0.05       0
  5027.2    0.05       0  5031.2    0.05       0  5247.8    0.12       0
Bank Sta=5027.2,5031.2
Exp/Cntr=0.3,0.1

Chan Stop Cuts=-1