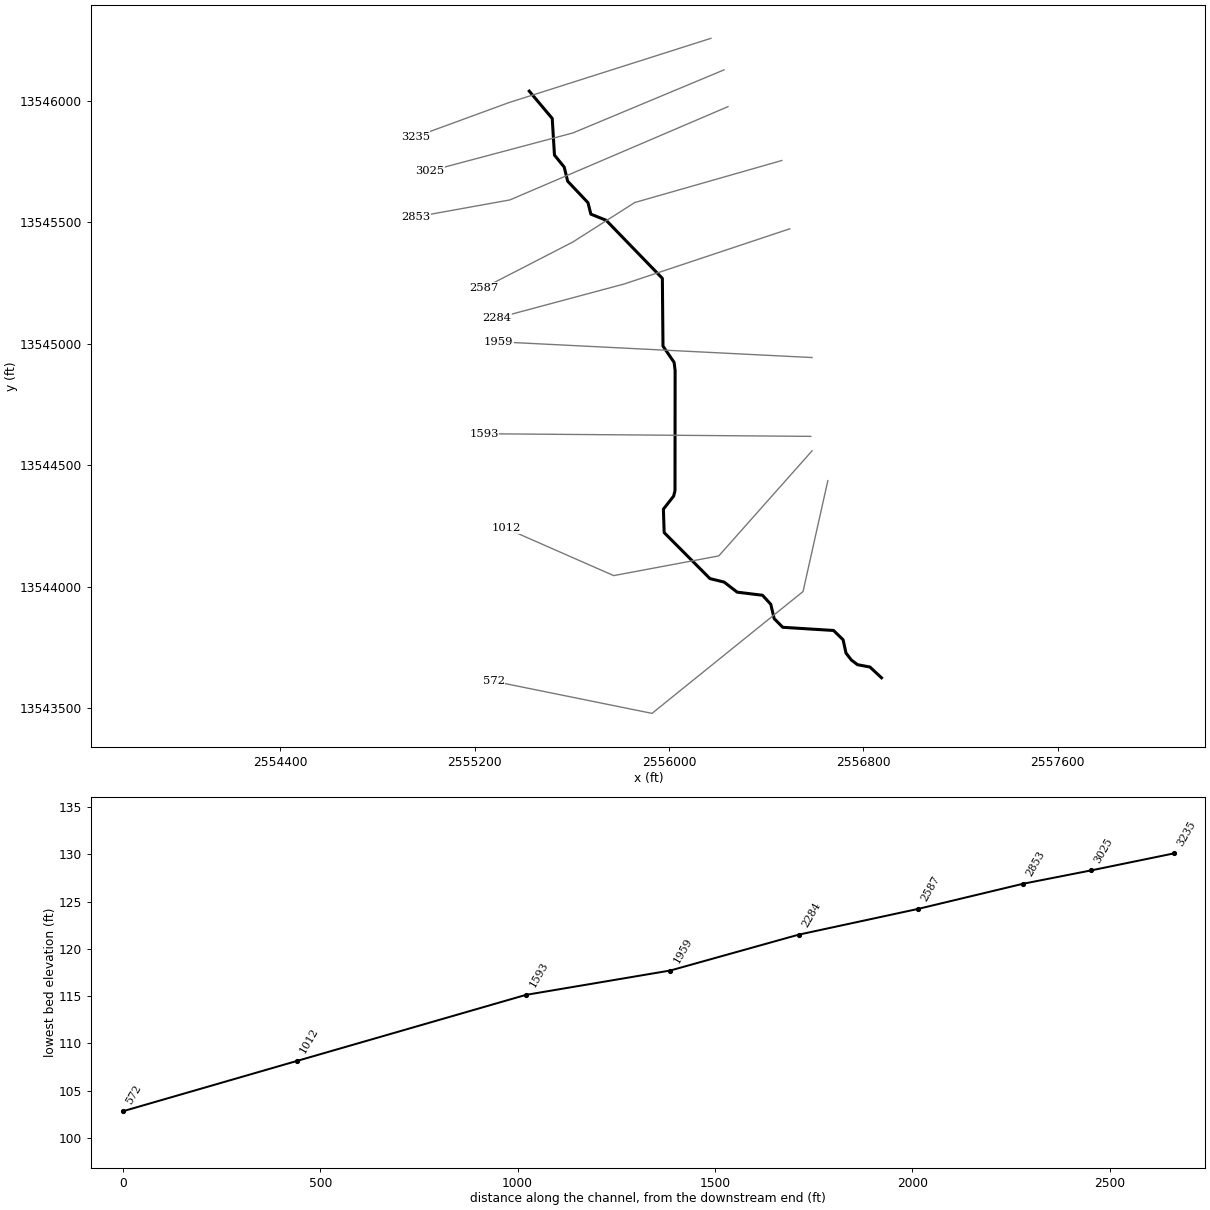
--- LG Stream117.prj (project) ---

Proj Title=LG Stream117 Base Level Engineering
Current Plan=p01
Default Exp/Contr=0.3,0.1
English Units
Geom File=g01
Flow File=f01
Plan File=p01
Y Axis Title=Elevation
X Axis Title(PF)=Main Channel Distance
X Axis Title(XS)=Station
BEGIN DESCRIPTION:
LG Stream117
END DESCRIPTION:
DSS Export Rating Curves= 0
DSS Export Rating Curve Sorted= 0
DSS Export Volume Flow Curves= 0
DXF OffsetX= 0
DXF OffsetY= 0
DXF ScaleX= 1
DXF ScaleY= 10

--- LG Stream117.p01 (plan) ---

Plan Title=Multiple Run
Short Identifier=Multiple
Geom File=g01
Flow File=f01
Subcritical Flow
K Sum by GR= 0
Std Step Tol= 0.01
Critical Tol= 0.01
Num of Std Step Trials= 20
Max Error Tol= 0.3
Flow Tol Ratio= 0.001
Split Flow NTrial= 30
Split Flow Tol= 0.02
Split Flow Ratio= 0.02
Log Output Level= 0
Friction Slope Method= 1
Unsteady Friction Slope Method= 2
Unsteady Bridges Friction Slope Method= 1
Parabolic Critical Depth
Global Vel Dist=  1 , 1 , 1
Global Log Level= 0
CheckData=True
Encroach Param= -1, 0, 0, 0
BEGIN DESCRIPTION:
Multiple Run
END DESCRIPTION:

--- LG Stream117.f01 (steady flow) ---

Flow Title=Multiple
Number of Profiles=7
Profile Names=10-year,25-year,50-year,1pct_min,100-year,1pct_plu,500-year
River Rch & RM= LG Stream117,Reach-1,3235
     693    1107    1476     953    1902    3794    3118
Boundary for River Rch & Prof#=LG Stream117,Reach-1,1
Up Type=0
Dn Type=3
Dn Slope=0.005
Boundary for River Rch & Prof#=LG Stream117,Reach-1,2
Up Type=0
Dn Type=3
Dn Slope=0.005
Boundary for River Rch & Prof#=LG Stream117,Reach-1,3
Up Type=0
Dn Type=3
Dn Slope=0.005
Boundary for River Rch & Prof#=LG Stream117,Reach-1,4
Up Type=0
Dn Type=3
Dn Slope=0.005
Boundary for River Rch & Prof#=LG Stream117,Reach-1,5
Up Type=0
Dn Type=3
Dn Slope=0.005
Boundary for River Rch & Prof#=LG Stream117,Reach-1,6
Up Type=0
Dn Type=3
Dn Slope=0.005
Boundary for River Rch & Prof#=LG Stream117,Reach-1,7
Up Type=0
Dn Type=3
Dn Slope=0.005

--- LG Stream117.g01 (geometry) ---

Geom Title=Existing Conditions

River Reach=LG Stream117,Reach-1
Reach XY= 30
      2555425.00     13546039.82      2555519.57     13545927.47
      2555528.76     13545776.56      2555568.86     13545727.17
      2555583.16     13545668.95      2555666.70     13545580.74
      2555678.55     13545533.50      2555741.48     13545508.27
      2555972.94     13545269.15      2555975.52     13544990.22
      2556021.22     13544923.43      2556025.43     13544890.18
      2556024.93     13544395.03      2556019.25     13544372.66
      2555977.16     13544319.02      2555980.40     13544222.57
      2556168.94     13544033.14      2556227.17     13544018.86
      2556280.97     13543977.34      2556385.10     13543964.61
      2556419.25     13543927.55      2556433.03     13543868.64
      2556468.53     13543832.70      2556677.70     13543819.64
      2556716.97     13543781.36      2556728.90     13543726.46
      2556751.14     13543697.84      2556776.35     13543678.71
      2556827.32     13543669.28      2556875.00     13543625.00

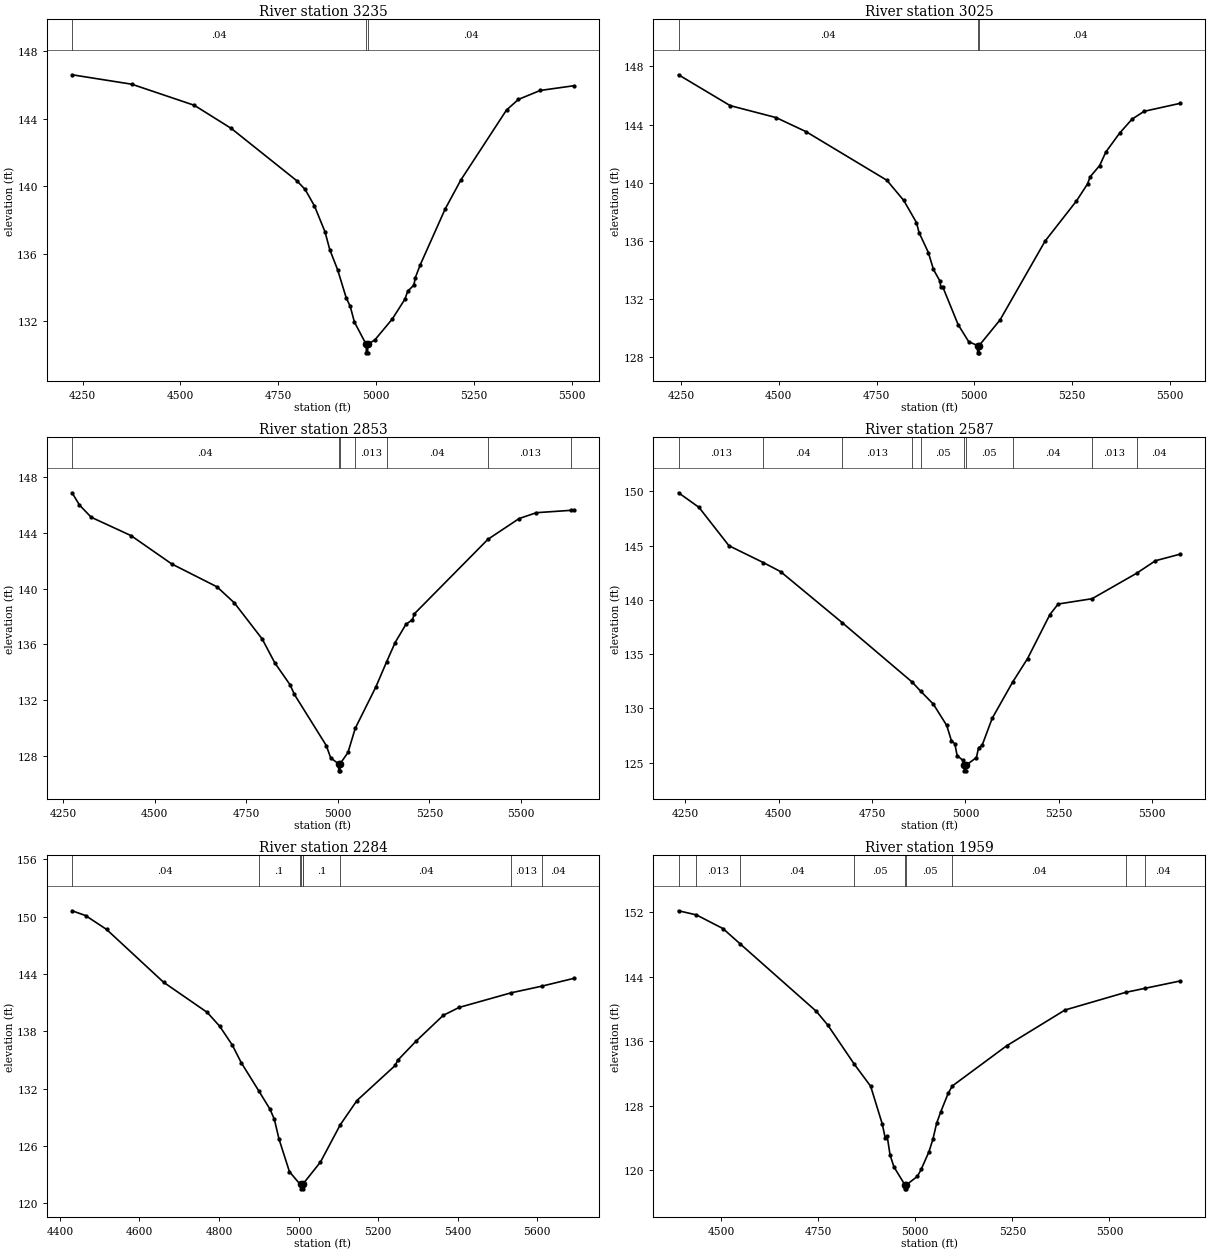
Type RM Length L Ch R = 1,3235,210,210,210
BEGIN DESCRIPTION:
LGII3029
END DESCRIPTION:
XS GIS Cut Line= 3
      2556172.76     13546257.21      2555340.02     13545992.25
      2554956.03     13545851.63
#Sta/Elev= 30
  4223.0  146.60  4375.8  146.04  4535.5  144.79  4629.9  143.42  4797.8  140.31
  4818.8  139.80  4842.7  138.82  4869.7  137.28  4881.8  136.23  4902.0  135.03
  4923.7  133.38  4934.2  132.86  4944.7  131.94  4974.9  130.61  4975.2  130.11
  4978.7  130.11  4978.9  130.61  4997.2  130.88  5041.4  132.11  5073.6  133.28
  5081.2  133.77  5096.9  134.13  5100.2  134.55  5112.9  135.32  5176.8  138.64
  5216.9  140.36  5333.6  144.51  5364.1  145.14  5419.8  145.67  5505.8  145.95
#Mann=3,-1,0
  4223.0    0.04       0  4974.9    0.04       0  4978.9    0.04       0
Bank Sta=4974.9,4978.9
Exp/Cntr=0.3,0.1

Type RM Length L Ch R = 1,3025,172,172,172
BEGIN DESCRIPTION:
LGII3028
END DESCRIPTION:
XS GIS Cut Line= 3
      2556226.87     13546127.44      2555604.99     13545867.87
      2555015.57     13545711.05
#Sta/Elev= 30
  4243.3  147.42  4375.4  145.30  4492.7  144.48  4569.6  143.51  4776.3  140.17
  4819.6  138.78  4852.1  137.26  4858.6  136.58  4882.5  135.20  4895.5  134.04
  4911.7  133.26  4914.5  132.81  4919.8  132.81  4958.6  130.25  4985.6  129.08
  5008.3  128.81  5008.5  128.31  5012.0  128.31  5012.3  128.81  5065.8  130.57
  5181.1  135.99  5261.4  138.75  5289.7  139.92  5296.4  140.41  5320.7  141.18
  5336.5  142.11  5371.5  143.40  5403.5  144.37  5434.6  144.91  5527.1  145.46
#Mann=3,-1,0
  4243.3    0.04       0  5008.3    0.04       0  5012.3    0.04       0
Bank Sta=5008.3,5012.3
Exp/Cntr=0.3,0.1

Type RM Length L Ch R = 1,2853,266,266,266
BEGIN DESCRIPTION:
LGII3027
END DESCRIPTION:
XS GIS Cut Line= 3
      2556243.11     13545976.03      2555345.42     13545592.08
      2554958.04     13545522.14
#Sta/Elev= 30
  4274.2  146.88  4294.4  146.00  4326.5  145.12  4435.3  143.80  4546.7  141.76
  4670.1  140.12  4717.2  138.97  4793.4  136.37  4827.9  134.65  4869.7  133.07
  4881.2  132.39  4968.2  128.72  4980.3  127.83  5001.9  127.40  5002.2  126.90
  5005.7  126.90  5005.9  127.40  5027.5  128.22  5047.4  129.96  5103.7  132.93
  5132.9  134.73  5156.3  136.12  5185.8  137.43  5203.5  137.76  5209.0  138.19
  5409.7  143.54  5494.9  145.03  5542.1  145.45  5637.0  145.62  5644.2  145.63
#Mann=7,-1,0
  4274.2    0.04       0  5001.9    0.04       0  5005.9    0.04       0
  5047.4   0.013       0  5132.9    0.04       0  5409.7   0.013       0
  5637.0    0.04       0
Bank Sta=5001.9,5005.9
Exp/Cntr=0.3,0.1

Type RM Length L Ch R = 1,2587,303,303,303
BEGIN DESCRIPTION:
LGII3026
END DESCRIPTION:
XS GIS Cut Line= 4
      2556464.81     13545754.32      2555859.15     13545581.27
      2555604.99     13545419.04      2555238.86     13545230.59
#Sta/Elev= 30
  4232.1  149.86  4286.7  148.52  4367.1  144.98  4459.0  143.43  4505.1  142.60
  4670.0  137.90  4856.8  132.44  4880.8  131.56  4914.3  130.38  4950.0  128.42
  4962.5  127.02  4971.8  126.73  4977.8  125.65  4993.0  125.21  4996.9  124.74
  4997.2  124.24  5000.7  124.24  5000.9  124.74  5029.4  125.46  5035.3  126.37
  5044.6  126.58  5071.7  129.08  5126.5  132.42  5166.3  134.58  5226.2  138.64
  5248.3  139.61  5339.1  140.10  5458.1  142.44  5508.8  143.60  5575.3  144.21
#Mann=10,-1,0
  4232.1   0.013       0  4459.0    0.04       0  4670.0   0.013       0
  4856.8     0.1       0  4880.8    0.05       0  4996.9    0.05       0
  5000.9    0.05       0  5126.5    0.04       0  5339.1   0.013       0
  5458.1    0.04       0
Bank Sta=4996.9,5000.9
Exp/Cntr=0.3,0.1

Type RM Length L Ch R = 1,2284,325,325,325
BEGIN DESCRIPTION:
LGII3025
END DESCRIPTION:
XS GIS Cut Line= 3
      2556497.27     13545473.12      2555815.89     13545246.00
      2555291.34     13545105.40
#Sta/Elev= 30
  4430.8  150.60  4464.8  150.10  4517.5  148.65  4660.9  143.12  4770.5  139.97
  4802.1  138.51  4833.7  136.54  4855.9  134.72  4899.8  131.78  4928.6  129.82
  4939.2  128.79  4950.8  126.74  4977.2  123.30  5002.5  122.06  5006.8  122.01
  5007.0  121.51  5010.5  121.51  5010.8  122.01  5012.1  122.06  5055.1  124.31
  5105.2  128.23  5146.9  130.75  5243.1  134.42  5248.9  134.94  5294.9  136.94
  5363.8  139.66  5403.8  140.49  5534.6  142.02  5611.3  142.71  5692.1  143.53
#Mann=9,-1,0
  4430.8    0.04       0  4899.8     0.1       0  5002.5    0.05       0
  5006.8    0.05       0  5010.8    0.05       0  5012.1     0.1       0
  5105.2    0.04       0  5534.6   0.013       0  5611.3    0.04       0
Bank Sta=5006.8,5010.8
Exp/Cntr=0.3,0.1

Type RM Length L Ch R = 1,1959,366,366,366
BEGIN DESCRIPTION:
LGII3024
END DESCRIPTION:
XS GIS Cut Line= 2
      2556589.13     13544943.17      2555298.36     13545007.98
#Sta/Elev= 30
  4390.3  152.16  4436.3  151.65  4504.6  149.96  4548.8  148.07  4744.9  139.72
  4774.9  137.99  4843.1  133.15  4885.1  130.43  4915.1  125.74  4922.7  124.01
  4927.7  124.24  4935.1  121.91  4945.1  120.44  4973.2  118.22  4973.4  117.72
  4976.9  117.72  4977.2  118.22  5005.2  119.25  5015.2  120.12  5035.2  122.31
  5045.3  123.84  5055.3  125.88  5065.3  127.21  5085.3  129.61  5095.7  130.47
  5235.5  135.44  5385.7  139.87  5541.5  142.05  5591.0  142.55  5682.7  143.47
#Mann=9,-1,0
  4390.3    0.04       0  4436.3   0.013       0  4548.8    0.04       0
  4843.1    0.05       0  4973.2    0.05       0  4977.2    0.05       0
  5095.7    0.04       0  5541.5   0.013       0  5591.0    0.04       0
Bank Sta=4973.2,4977.2
Exp/Cntr=0.3,0.1

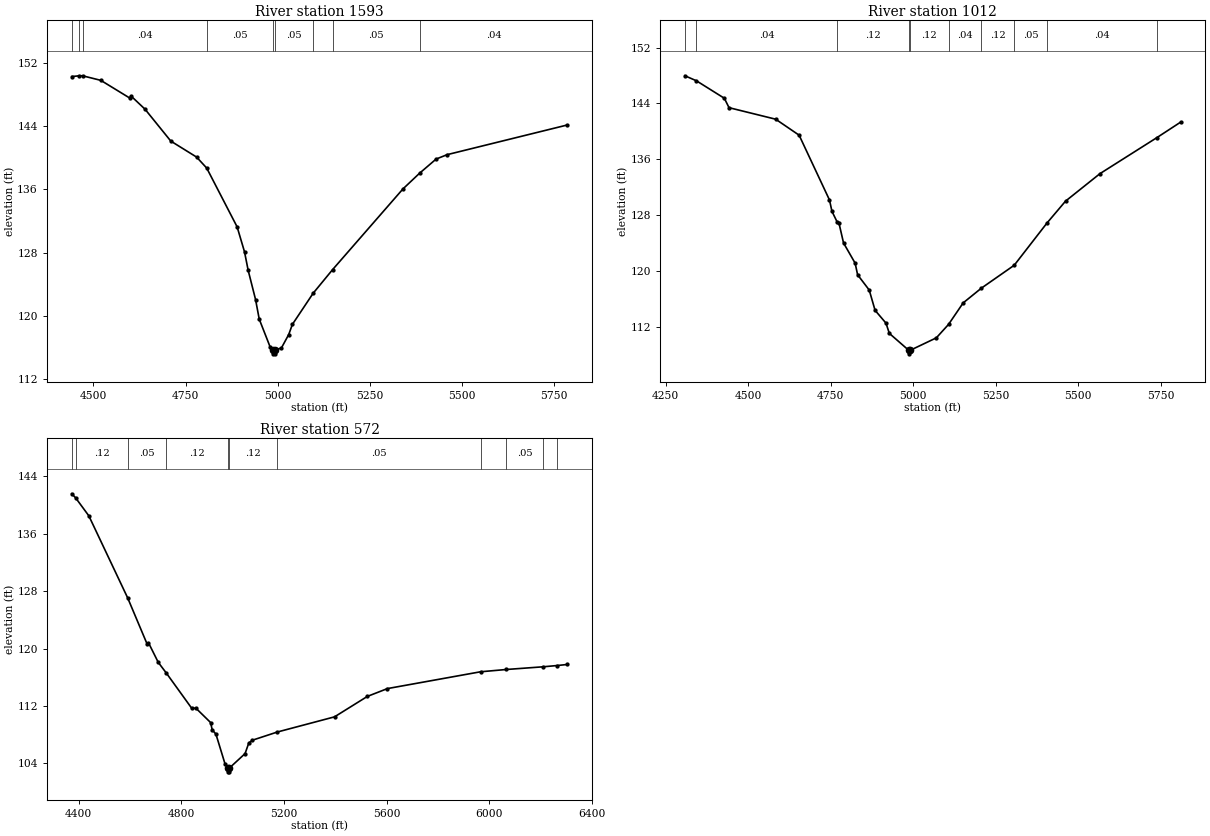
Type RM Length L Ch R = 1,1593,581,581,581
BEGIN DESCRIPTION:
LGII3023
END DESCRIPTION:
XS GIS Cut Line= 2
      2556583.79     13544618.72      2555238.63     13544629.52
#Sta/Elev= 30
  4441.2  150.33  4461.9  150.43  4470.5  150.43  4520.0  149.85  4598.0  147.62
  4603.0  147.82  4640.0  146.19  4710.0  142.14  4780.0  140.11  4807.4  138.72
  4890.0  131.25  4910.0  128.09  4920.0  125.73  4940.0  122.03  4950.0  119.54
  4980.0  115.96  4988.0  115.64  4988.3  115.14  4991.8  115.14  4992.0  115.64
  5010.0  115.87  5030.0  117.59  5040.0  118.88  5096.3  122.83  5149.1  125.83
  5340.0  136.07  5385.3  138.07  5430.0  139.86  5460.0  140.42  5786.4  144.19
#Mann=9,-1,0
  4441.2    0.04       0  4461.9    0.05       0  4470.5    0.04       0
  4807.4    0.05       0  4988.0    0.05       0  4992.0    0.05       0
  5096.3    0.04       0  5149.1    0.05       0  5385.3    0.04       0
Bank Sta=4988,4992
Exp/Cntr=0.3,0.1

Type RM Length L Ch R = 1,1012,440,440,440
BEGIN DESCRIPTION:
LGII3022
END DESCRIPTION:
XS GIS Cut Line= 4
      2556589.20     13544559.26      2556205.23     13544126.62
      2555772.63     13544045.51      2555329.82     13544239.91
#Sta/Elev= 30
  4308.5  147.97  4343.3  147.25  4427.8  144.75  4442.1  143.40  4583.4  141.75
  4654.5  139.46  4746.5  130.18  4754.0  128.55  4769.5  127.05  4774.9  126.94
  4789.1  124.02  4824.2  121.13  4831.8  119.46  4866.9  117.28  4884.7  114.37
  4917.7  112.54  4927.9  111.07  4986.9  108.64  4987.2  108.14  4990.9  108.64
  5070.3  110.43  5107.4  112.36  5151.7  115.44  5206.9  117.55  5306.4  120.83
  5405.7  126.88  5461.8  130.01  5566.2  133.95  5738.7  139.11  5810.7  141.33
#Mann=10,-1,0
  4308.5    0.05       0  4343.3    0.04       0  4769.5    0.12       0
  4986.9    0.05       0  4990.9    0.12       0  5107.4    0.04       0
  5206.9    0.12       0  5306.4    0.05       0  5405.7    0.04       0
  5738.7    0.05       0
Bank Sta=4986.9,4990.9
Exp/Cntr=0.3,0.1

Type RM Length L Ch R = 1,572,0,0,0
BEGIN DESCRIPTION:
LGII3022a
END DESCRIPTION:
XS GIS Cut Line= 4
      2556654.16     13544436.49      2556552.05     13543979.98
      2555930.31     13543478.38      2555278.51     13543610.55
#Sta/Elev= 30
  4372.6  141.57  4387.5  141.01  4439.1  138.50  4590.8  127.04  4666.4  120.62
  4671.5  120.82  4709.7  118.08  4741.2  116.59  4840.4  111.67  4856.1  111.71
  4913.6  109.70  4920.0  108.68  4934.4  108.09  4969.6  103.97  4982.0  103.33
  4982.3  102.83  4985.8  102.83  4986.0  103.33  5048.0  105.37  5062.4  106.84
  5076.8  107.24  5173.9  108.38  5396.6  110.49  5524.6  113.34  5602.9  114.43
  5965.6  116.77  6066.5  117.09  6207.9  117.46  6264.1  117.64  6304.3  117.79
#Mann=11,-1,0
  4372.6    0.05       0  4387.5    0.12       0  4590.8    0.05       0
  4741.2    0.12       0  4982.0    0.05       0  4986.0    0.12       0
  5173.9    0.05       0  5965.6    0.12       0  6066.5    0.05       0
  6207.9    0.12       0  6264.1    0.05       0
Bank Sta=4982,4986
Exp/Cntr=0.3,0.1

Chan Stop Cuts=-1