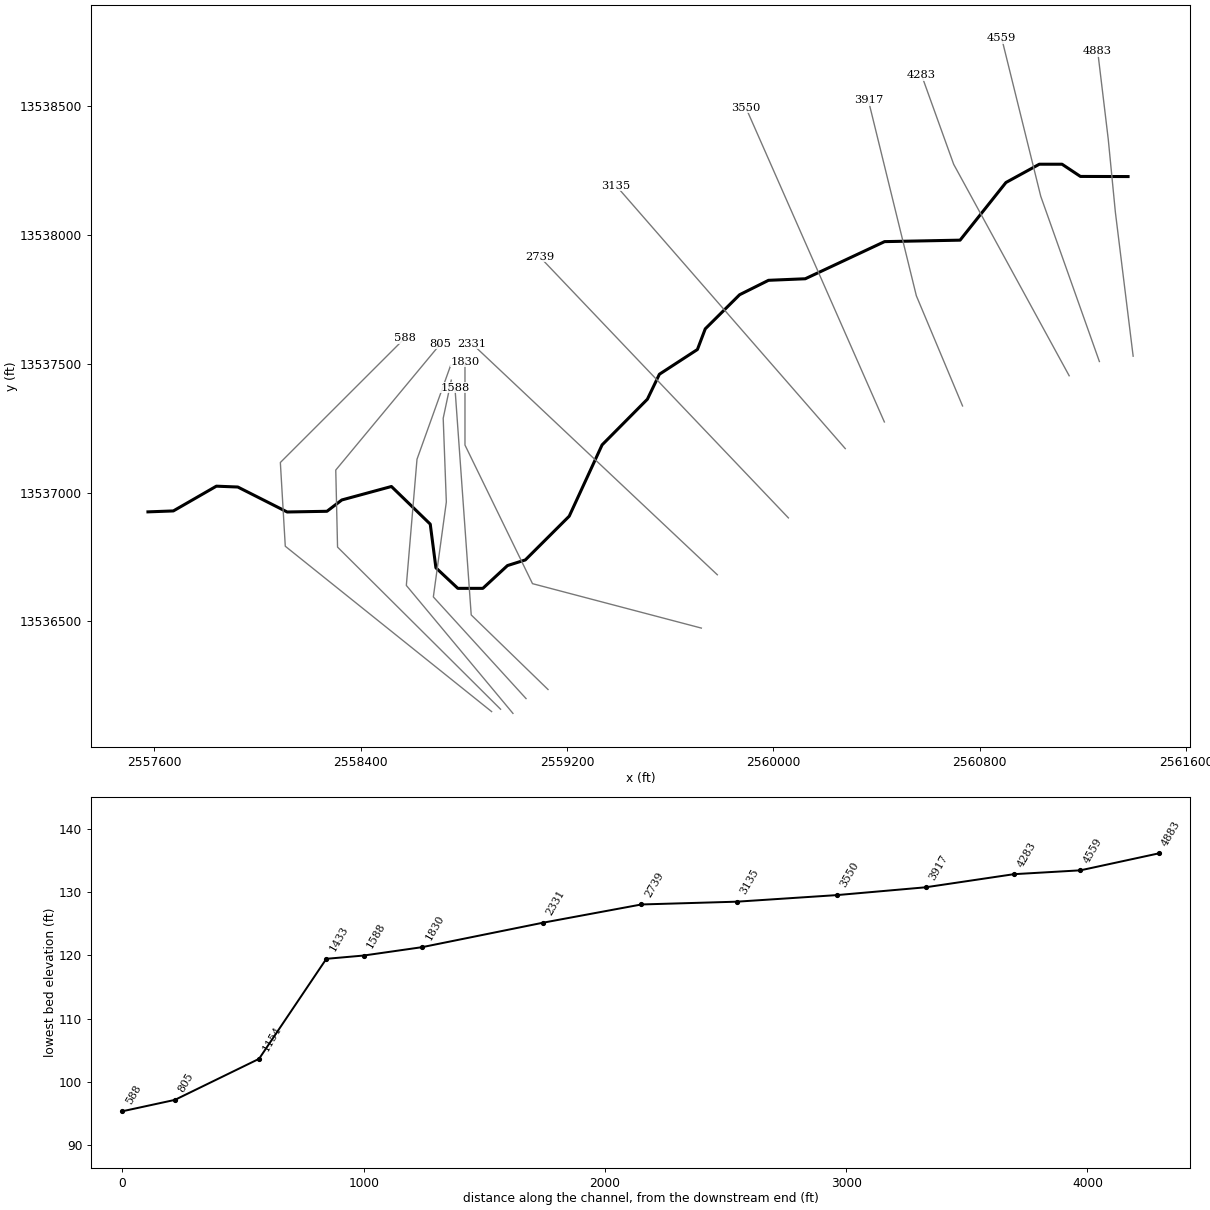
--- LG Stream119.prj (project) ---

Proj Title=LG Stream119 Base Level Engineering
Current Plan=p01
Default Exp/Contr=0.3,0.1
English Units
Geom File=g01
Flow File=f01
Plan File=p01
Y Axis Title=Elevation
X Axis Title(PF)=Main Channel Distance
X Axis Title(XS)=Station
BEGIN DESCRIPTION:
LG Stream119
END DESCRIPTION:
DSS Export Rating Curves= 0
DSS Export Rating Curve Sorted= 0
DSS Export Volume Flow Curves= 0
DXF OffsetX= 0
DXF OffsetY= 0
DXF ScaleX= 1
DXF ScaleY= 10

--- LG Stream119.p01 (plan) ---

Plan Title=Multiple Run
Short Identifier=Multiple
Geom File=g01
Flow File=f01
Subcritical Flow
K Sum by GR= 0
Std Step Tol= 0.01
Critical Tol= 0.01
Num of Std Step Trials= 20
Max Error Tol= 0.3
Flow Tol Ratio= 0.001
Split Flow NTrial= 30
Split Flow Tol= 0.02
Split Flow Ratio= 0.02
Log Output Level= 0
Friction Slope Method= 1
Unsteady Friction Slope Method= 2
Unsteady Bridges Friction Slope Method= 1
Parabolic Critical Depth
Global Vel Dist=  1 , 1 , 1
Global Log Level= 0
CheckData=True
Encroach Param= -1, 0, 0, 0
BEGIN DESCRIPTION:
Multiple Run
END DESCRIPTION:

--- LG Stream119.f01 (steady flow) ---

Flow Title=Multiple
Number of Profiles=7
Profile Names=10-year,25-year,50-year,1pct_min,100-year,1pct_plu,500-year
River Rch & RM= LG Stream119,Reach-1,4883
     824    1331    1790    1166    2327    4642    3881
Boundary for River Rch & Prof#=LG Stream119,Reach-1,1
Up Type=0
Dn Type=3
Dn Slope=0.005
Boundary for River Rch & Prof#=LG Stream119,Reach-1,2
Up Type=0
Dn Type=3
Dn Slope=0.005
Boundary for River Rch & Prof#=LG Stream119,Reach-1,3
Up Type=0
Dn Type=3
Dn Slope=0.005
Boundary for River Rch & Prof#=LG Stream119,Reach-1,4
Up Type=0
Dn Type=3
Dn Slope=0.005
Boundary for River Rch & Prof#=LG Stream119,Reach-1,5
Up Type=0
Dn Type=3
Dn Slope=0.005
Boundary for River Rch & Prof#=LG Stream119,Reach-1,6
Up Type=0
Dn Type=3
Dn Slope=0.005
Boundary for River Rch & Prof#=LG Stream119,Reach-1,7
Up Type=0
Dn Type=3
Dn Slope=0.005

--- LG Stream119.g01 (geometry) ---

Geom Title=Existing Conditions

River Reach=LG Stream119,Reach-1
Reach XY= 30
      2561375.00     13538225.00      2561190.21     13538225.51
      2561119.02     13538272.83      2561030.97     13538272.86
      2560901.53     13538201.99      2560723.75     13537978.45
      2560430.94     13537972.74      2560123.44     13537828.76
      2559980.93     13537822.75      2559868.94     13537766.86
      2559735.79     13537634.66      2559705.37     13537554.53
      2559557.92     13537458.58      2559511.37     13537361.79
      2559335.76     13537184.68      2559208.36     13536908.32
      2559038.21     13536738.63      2558968.96     13536716.82
      2558873.50     13536628.47      2558776.48     13536628.45
      2558691.42     13536708.20      2558669.53     13536877.45
      2558518.97     13537023.38      2558326.60     13536971.14
      2558269.06     13536927.26      2558114.81     13536924.54
      2557923.42     13537021.33      2557840.27     13537024.63
      2557673.50     13536928.63      2557575.00     13536925.00

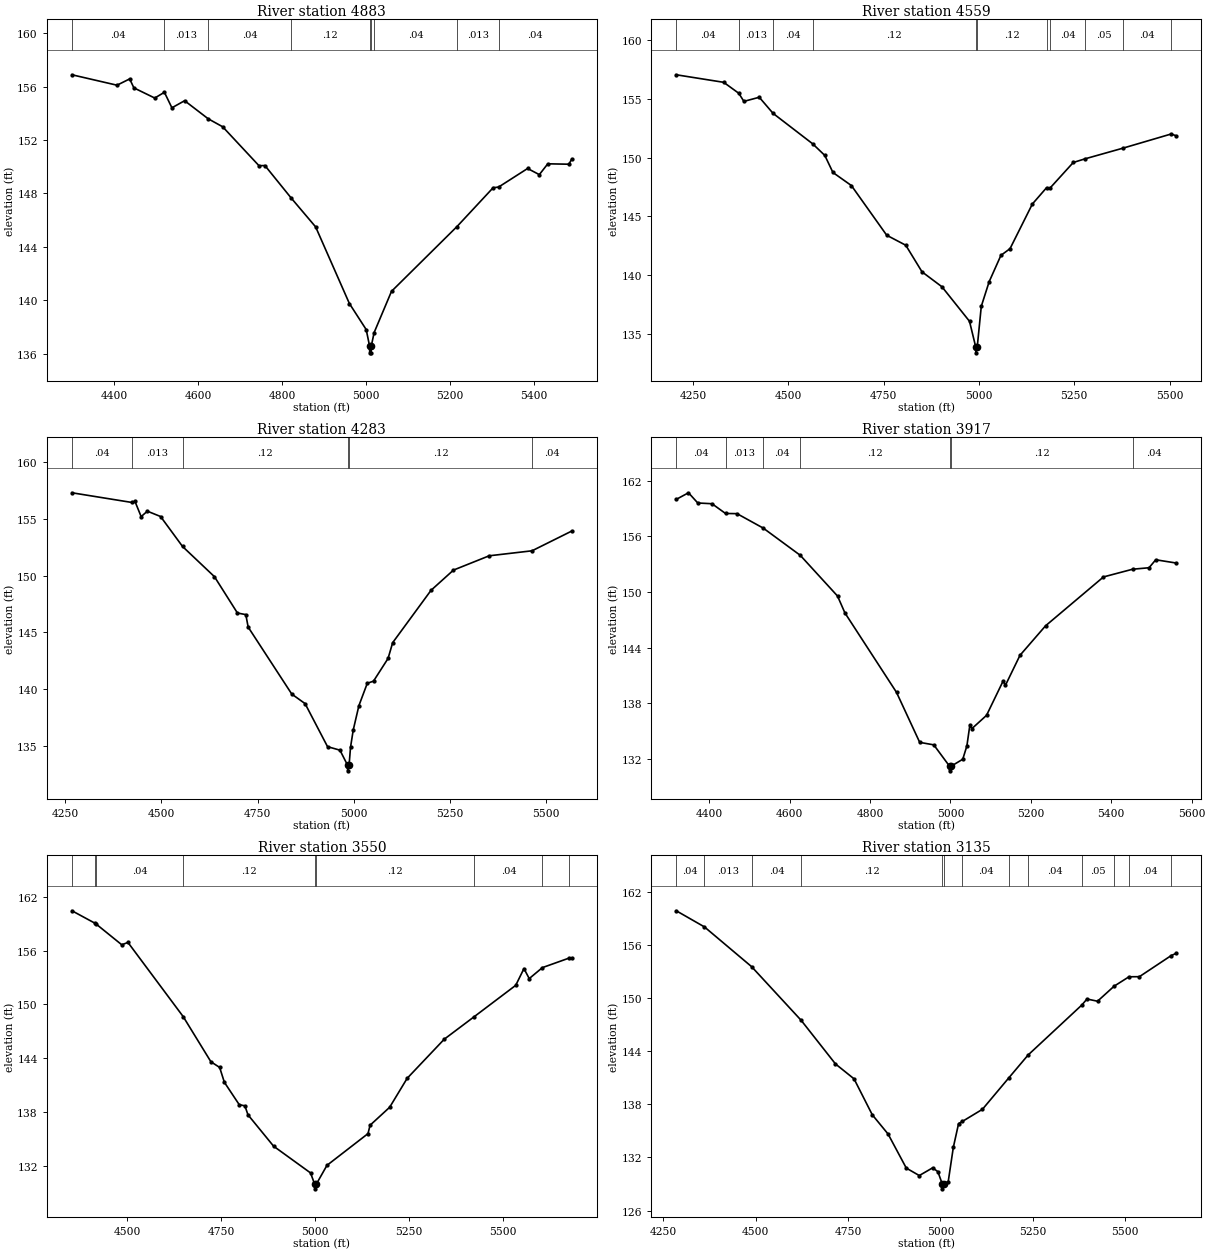
Type RM Length L Ch R = 1,4883,324,324,324
BEGIN DESCRIPTION:
LGII2946
END DESCRIPTION:
XS GIS Cut Line= 4
      2561394.72     13537528.55      2561325.82     13538086.62
      2561298.26     13538369.10      2561257.13     13538711.81
#Sta/Elev= 30
  4298.7  156.88  4406.0  156.10  4436.2  156.57  4446.3  155.90  4496.0  155.14
  4519.0  155.57  4536.9  154.41  4567.2  154.94  4623.3  153.59  4657.9  152.99
  4744.4  150.08  4758.6  150.09  4821.2  147.66  4879.5  145.50  4959.9  139.77
  5000.0  137.82  5008.1  136.58  5008.3  136.08  5011.8  136.08  5012.1  136.58
  5018.8  137.59  5060.3  140.68  5216.5  145.53  5302.5  148.43  5315.5  148.48
  5384.7  149.87  5412.6  149.41  5432.8  150.22  5483.1  150.19  5490.0  150.58
#Mann=9,-1,0
  4298.7    0.04       0  4519.0   0.013       0  4623.3    0.04       0
  4821.2    0.12       0  5008.1    0.05       0  5012.1    0.12       0
  5018.8    0.04       0  5216.5   0.013       0  5315.5    0.04       0
Bank Sta=5008.1,5012.1
Exp/Cntr=0.3,0.1

Type RM Length L Ch R = 1,4559,276,276,276
BEGIN DESCRIPTION:
LGII2945
END DESCRIPTION:
XS GIS Cut Line= 3
      2561263.81     13537507.89      2561036.45     13538148.63
      2560885.10     13538760.92
#Sta/Elev= 30
  4206.5  157.03  4330.8  156.39  4370.4  155.46  4383.8  154.77  4424.1  155.12
  4460.4  153.75  4564.0  151.17  4596.0  150.18  4617.3  148.73  4665.7  147.62
  4758.3  143.40  4808.3  142.55  4850.9  140.29  4903.2  139.02  4975.4  136.09
  4991.7  133.91  4992.0  133.41  4995.7  133.91  5006.3  137.36  5026.9  139.45
  5057.8  141.69  5081.7  142.26  5140.2  146.05  5177.5  147.44  5186.1  147.39
  5247.5  149.58  5278.3  149.89  5379.2  150.81  5504.2  152.00  5517.1  151.85
#Mann=11,-1,0
  4206.5    0.04       0  4370.4   0.013       0  4460.4    0.04       0
  4564.0    0.12       0  4991.7    0.05       0  4995.7    0.12       0
  5177.5   0.013       0  5186.1    0.04       0  5278.3    0.05       0
  5379.2    0.04       0  5504.2    0.05       0
Bank Sta=4991.7,4995.7
Exp/Cntr=0.3,0.1

Type RM Length L Ch R = 1,4283,366,366,366
BEGIN DESCRIPTION:
LGII2944
END DESCRIPTION:
XS GIS Cut Line= 3
      2561146.69     13537452.74      2560698.85     13538272.65
      2560574.82     13538617.16
#Sta/Elev= 30
  4267.3  157.29  4422.7  156.44  4431.2  156.53  4447.3  155.19  4463.4  155.67
  4497.8  155.20  4555.0  152.56  4638.0  149.90  4697.8  146.70  4719.6  146.56
  4725.7  145.46  4839.2  139.56  4873.8  138.72  4932.2  134.93  4964.5  134.62
  4984.3  133.30  4984.5  132.80  4988.3  133.30  4992.0  134.87  4999.1  136.40
  5013.8  138.54  5035.6  140.51  5051.8  140.70  5089.7  142.70  5101.7  144.09
  5201.5  148.70  5259.8  150.48  5352.8  151.74  5464.3  152.18  5567.7  153.92
#Mann=6,-1,0
  4267.3    0.04       0  4422.7   0.013       0  4555.0    0.12       0
  4984.3    0.05       0  4988.3    0.12       0  5464.3    0.04       0
Bank Sta=4984.3,4988.3
Exp/Cntr=0.3,0.1

Type RM Length L Ch R = 1,3917,367,367,367
BEGIN DESCRIPTION:
LGII2943
END DESCRIPTION:
XS GIS Cut Line= 3
      2560733.28     13537335.67      2560554.16     13537762.80
      2560368.22     13538520.35
#Sta/Elev= 30
  4318.1  159.99  4348.5  160.70  4371.6  159.60  4406.9  159.52  4440.6  158.47
  4469.2  158.45  4534.5  156.89  4626.5  153.96  4719.2  149.57  4737.6  147.75
  4865.9  139.19  4923.6  133.80  4958.6  133.53  4997.8  131.23  4998.0  130.73
  5001.8  131.23  5030.7  131.98  5041.0  133.43  5048.3  135.65  5053.4  135.28
  5089.8  136.71  5131.4  140.44  5136.6  139.93  5173.0  143.18  5236.6  146.36
  5380.7  151.63  5453.1  152.46  5494.0  152.62  5510.7  153.48  5561.3  153.13
#Mann=7,-1,0
  4318.1    0.04       0  4440.6   0.013       0  4534.5    0.04       0
  4626.5    0.12       0  4997.8    0.05       0  5001.8    0.12       0
  5453.1    0.04       0
Bank Sta=4997.8,5001.8
Exp/Cntr=0.3,0.1

Type RM Length L Ch R = 1,3550,415,415,415
BEGIN DESCRIPTION:
LGII2942
END DESCRIPTION:
XS GIS Cut Line= 2
      2560430.15     13537273.62      2559893.42     13538491.60
#Sta/Elev= 30
  4352.2  160.42  4413.3  159.04  4415.2  158.99  4484.8  156.64  4501.3  156.90
  4648.4  148.65  4722.2  143.63  4745.5  143.00  4758.0  141.35  4797.6  138.86
  4812.7  138.73  4820.9  137.73  4889.2  134.24  4987.5  131.27  4998.6  130.00
  4998.9  129.50  5002.6  130.00  5031.2  132.11  5140.5  135.64  5146.0  136.57
  5198.2  138.57  5244.8  141.79  5343.6  146.14  5423.9  148.66  5533.9  152.13
  5555.8  153.99  5569.9  152.88  5604.9  154.10  5675.4  155.15  5683.2  155.18
#Mann=9,-1,0
  4352.2    0.04       0  4413.3   0.013       0  4415.2    0.04       0
  4648.4    0.12       0  4998.6    0.05       0  5002.6    0.12       0
  5423.9    0.04       0  5604.9   0.013       0  5675.4    0.04       0
Bank Sta=4998.6,5002.6
Exp/Cntr=0.3,0.1

Type RM Length L Ch R = 1,3135,396,396,396
BEGIN DESCRIPTION:
LGII2941
END DESCRIPTION:
XS GIS Cut Line= 2
      2560278.58     13537170.28      2559389.90     13538189.85
#Sta/Elev= 30
  4285.2  159.85  4361.4  158.03  4489.1  153.54  4623.2  147.48  4716.0  142.56
  4766.2  140.88  4815.6  136.82  4858.3  134.65  4907.7  130.80  4942.8  129.96
  4978.9  130.83  4993.1  130.40  5005.4  128.96  5005.6  128.46  5009.4  128.96
  5021.1  129.27  5034.9  133.14  5049.1  135.82  5059.4  136.07  5113.7  137.44
  5184.7  140.97  5237.3  143.57  5382.6  149.21  5396.6  149.89  5425.1  149.64
  5470.1  151.34  5510.3  152.40  5538.4  152.41  5624.7  154.80  5637.7  155.04
#Mann=13,-1,0
  4285.2    0.04       0  4361.4   0.013       0  4489.1    0.04       0
  4623.2    0.12       0  5005.4    0.05       0  5009.4    0.12       0
  5059.4    0.04       0  5184.7    0.12       0  5237.3    0.04       0
  5382.6    0.05       0  5470.1   0.013       0  5510.3    0.04       0
  5624.7    0.05       0
Bank Sta=5005.4,5009.4
Exp/Cntr=0.3,0.1

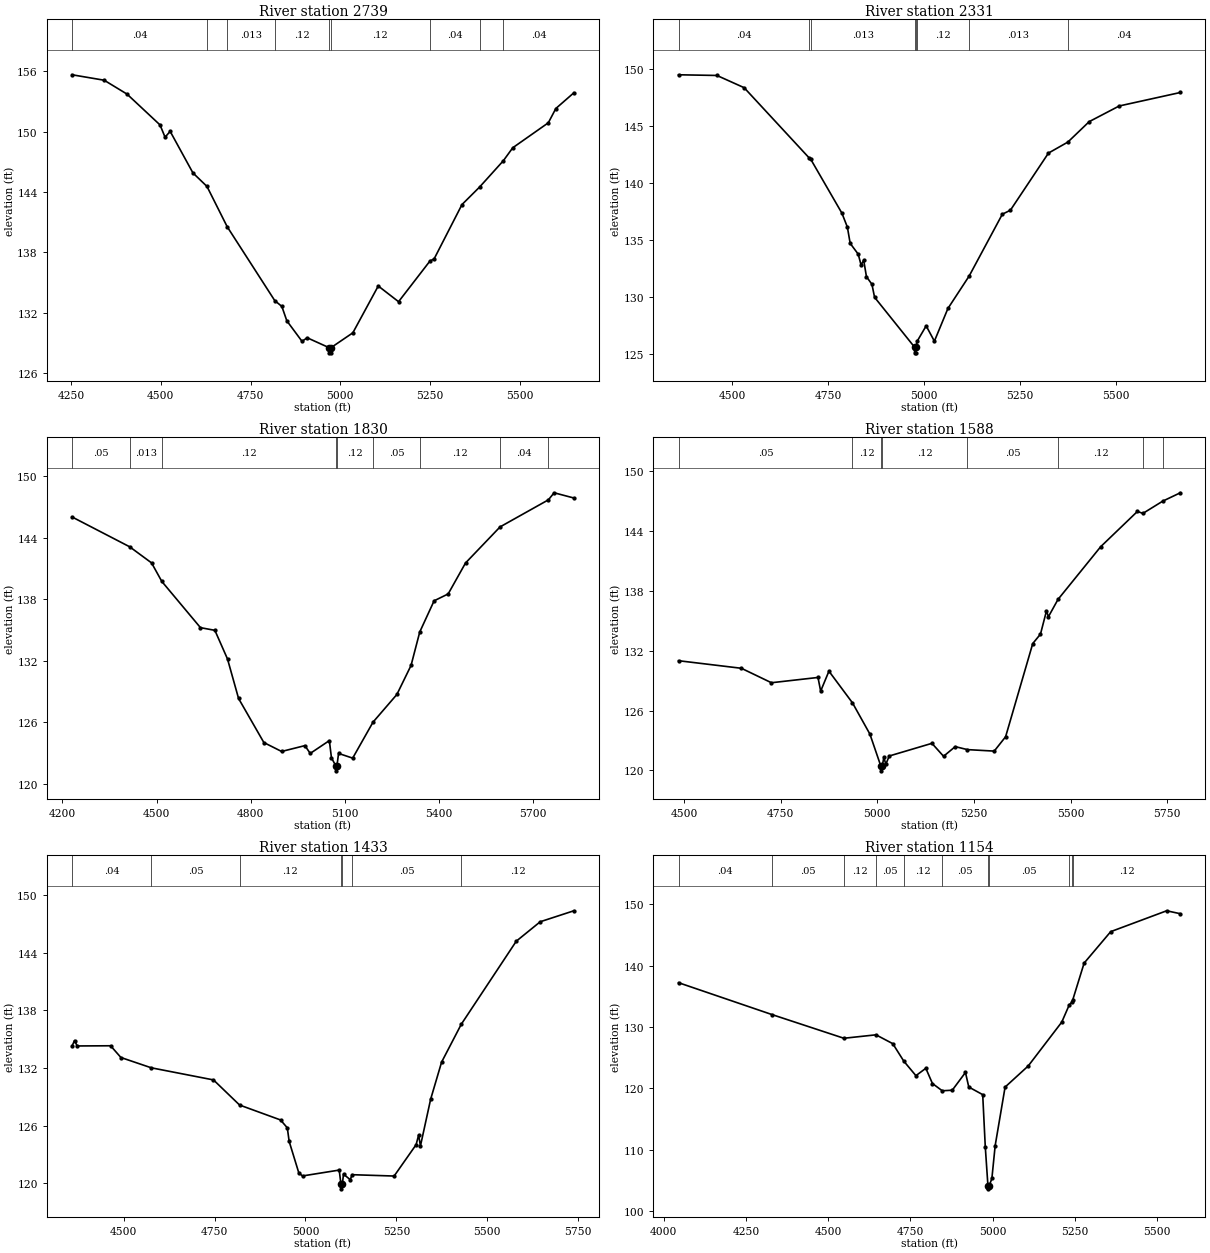
Type RM Length L Ch R = 1,2739,408,408,408
BEGIN DESCRIPTION:
LGII2940
END DESCRIPTION:
XS GIS Cut Line= 2
      2560058.10     13536901.59      2559093.54     13537914.37
#Sta/Elev= 30
  4252.6  155.64  4342.0  155.10  4405.8  153.72  4497.7  150.66  4511.8  149.44
  4526.0  150.02  4589.5  145.89  4628.6  144.55  4684.9  140.55  4817.5  133.21
  4837.3  132.63  4851.2  131.20  4893.6  129.16  4907.8  129.52  4969.7  128.52
  4969.9  128.02  4973.4  128.02  4973.7  128.52  5035.2  130.01  5106.0  134.66
  5162.6  133.10  5250.1  137.14  5261.7  137.35  5339.4  142.75  5388.5  144.49
  5454.6  147.10  5480.9  148.39  5580.0  150.87  5601.0  152.29  5651.2  153.85
#Mann=9,-1,0
  4252.6    0.04       0  4628.6    0.12       0  4684.9   0.013       0
  4817.5    0.12       0  4969.7    0.05       0  4973.7    0.12       0
  5250.1    0.04       0  5388.5   0.013       0  5454.6    0.04       0
Bank Sta=4969.7,4973.7
Exp/Cntr=0.3,0.1

Type RM Length L Ch R = 1,2331,501,501,501
BEGIN DESCRIPTION:
LGII2939
END DESCRIPTION:
XS GIS Cut Line= 2
      2559782.50     13536681.12      2558831.73     13537576.77
#Sta/Elev= 30
  4360.4  149.47  4460.4  149.41  4531.2  148.34  4700.3  142.20  4704.5  142.08
  4785.7  137.36  4799.9  136.14  4807.2  134.72  4828.2  133.77  4835.5  132.83
  4842.4  133.24  4849.6  131.80  4863.8  131.14  4870.7  130.00  4974.7  125.64
  4974.9  125.14  4978.4  125.14  4978.7  125.64  4982.0  126.18  5005.0  127.50
  5026.4  126.16  5061.6  129.02  5116.9  131.86  5203.3  137.27  5224.3  137.62
  5323.4  142.62  5373.8  143.58  5429.4  145.37  5507.5  146.74  5666.6  147.92
#Mann=8,-1,0
  4360.4    0.04       0  4700.3    0.12       0  4704.5   0.013       0
  4974.7    0.05       0  4978.7   0.013       0  4982.0    0.12       0
  5116.9   0.013       0  5373.8    0.04       0
Bank Sta=4974.7,4978.7
Exp/Cntr=0.3,0.1

Type RM Length L Ch R = 1,1830,242,242,242
BEGIN DESCRIPTION:
LGII2938
END DESCRIPTION:
XS GIS Cut Line= 4
      2559720.54     13536474.41      2559065.97     13536646.66
      2558804.16     13537184.06      2558804.16     13537507.93
#Sta/Elev= 30
  4230.5  146.05  4414.0  143.14  4483.7  141.57  4516.4  139.76  4639.5  135.25
  4685.4  134.99  4725.7  132.19  4760.9  128.34  4841.5  124.04  4898.0  123.17
  4972.2  123.74  4989.2  122.98  5050.1  124.23  5056.8  122.55  5070.4  121.78
  5070.6  121.28  5074.4  121.78  5079.4  122.98  5124.4  122.52  5189.2  126.03
  5265.2  128.73  5310.3  131.56  5338.1  134.83  5383.8  137.87  5428.6  138.54
  5483.9  141.56  5593.9  145.08  5747.8  147.72  5766.1  148.41  5829.0  147.90
#Mann=9,-1,0
  4230.5    0.05       0  4414.0   0.013       0  4516.4    0.12       0
  5070.4    0.05       0  5074.4    0.12       0  5189.2    0.05       0
  5338.1    0.12       0  5593.9    0.04       0  5747.8    0.12       0
Bank Sta=5070.4,5074.4
Exp/Cntr=0.3,0.1

Type RM Length L Ch R = 1,1588,155,155,155
BEGIN DESCRIPTION:
Mapping XS b63d5190
END DESCRIPTION:
XS GIS Cut Line= 3
      2559126.11     13536236.31      2558828.34     13536525.40
      2558765.31     13537405.63
#Sta/Elev= 30
  4486.0  131.01  4648.5  130.25  4726.2  128.80  4846.6  129.33  4853.5  127.96
  4874.9  129.96  4935.8  126.78  4980.8  123.65  5008.9  120.46  5009.1  119.96
  5012.9  120.46  5016.9  121.32  5021.9  120.62  5030.9  121.45  5141.2  122.72
  5171.3  121.42  5201.4  122.39  5232.9  122.09  5302.3  121.94  5331.7  123.38
  5401.9  132.73  5421.9  133.68  5437.4  136.01  5442.4  135.42  5467.2  137.16
  5577.6  142.45  5672.6  145.99  5686.7  145.79  5738.0  147.02  5783.5  147.86
#Mann=8,-1,0
  4486.0    0.05       0  4935.8    0.12       0  5008.9    0.05       0
  5012.9    0.12       0  5232.9    0.05       0  5467.2    0.12       0
  5686.7    0.04       0  5738.0    0.12       0
Bank Sta=5008.9,5012.9
Exp/Cntr=0.3,0.1

Type RM Length L Ch R = 1,1433,279,279,279
BEGIN DESCRIPTION:
Mapping XS e5d797bb
END DESCRIPTION:
XS GIS Cut Line= 5
      2559040.93     13536201.11      2558681.54     13536595.22
      2558731.89     13536963.27      2558719.73     13537287.92
      2558750.99     13537435.52
#Sta/Elev= 30
  4357.8  134.29  4364.5  134.85  4371.9  134.29  4463.8  134.31  4492.2  133.09
  4575.7  132.02  4746.9  130.76  4818.7  128.15  4931.3  126.60  4950.0  125.78
  4955.1  124.37  4981.8  121.08  4991.9  120.78  5092.8  121.39  5097.5  119.94
  5097.8  119.44  5101.5  119.94  5104.6  120.97  5123.1  120.39  5128.4  120.91
  5243.9  120.77  5304.4  124.03  5311.3  125.03  5316.3  123.90  5344.4  128.76
  5374.5  132.61  5428.7  136.55  5580.0  145.18  5645.9  147.20  5738.4  148.34
#Mann=7,-1,0
  4357.8    0.04       0  4575.7    0.05       0  4818.7    0.12       0
  5097.5    0.05       0  5101.5    0.12       0  5128.4    0.05       0
  5428.7    0.12       0
Bank Sta=5097.5,5101.5
Exp/Cntr=0.3,0.1

Type RM Length L Ch R = 1,1154,349,349,349
BEGIN DESCRIPTION:
LGII2937
END DESCRIPTION:
XS GIS Cut Line= 4
      2558990.16     13536143.74      2558576.80     13536639.77
      2558618.14     13537128.95      2558749.04     13537494.09
#Sta/Elev= 30
  4045.6  137.22  4329.4  132.03  4548.0  128.17  4645.5  128.73  4696.5  127.29
  4730.0  124.44  4766.8  122.08  4796.9  123.28  4817.0  120.80  4846.8  119.62
  4877.2  119.71  4917.3  122.60  4927.4  120.23  4969.7  118.99  4977.5  110.52
  4985.6  104.15  4985.8  103.65  4989.6  104.15  4997.6  105.35  5007.6  110.70
  5037.7  120.22  5108.0  123.66  5209.9  130.80  5232.7  133.61  5240.4  134.02
  5243.1  134.39  5277.8  140.41  5358.6  145.53  5528.6  148.93  5570.1  148.45
#Mann=11,-1,0
  4045.6    0.04       0  4329.4    0.05       0  4548.0    0.12       0
  4645.5    0.05       0  4730.0    0.12       0  4846.8    0.05       0
  4985.6    0.05       0  4989.6    0.05       0  5232.7    0.12       0
  5240.4    0.05       0  5243.1    0.12       0
Bank Sta=4985.6,4989.6
Exp/Cntr=0.3,0.1

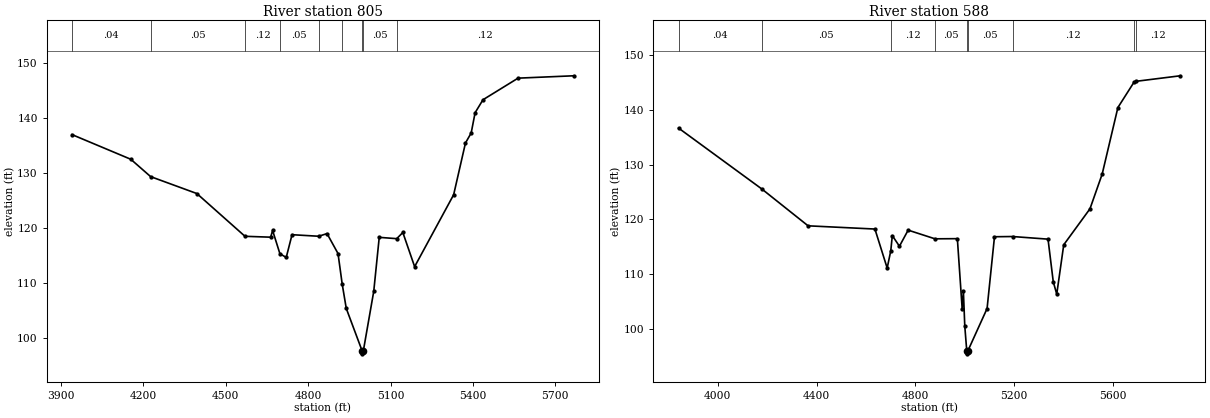
Type RM Length L Ch R = 1,805,217,217,217
BEGIN DESCRIPTION:
Mapping XS 6de2f446
END DESCRIPTION:
XS GIS Cut Line= 4
      2558942.09     13536159.92      2558310.12     13536788.42
      2558303.17     13537087.04      2558709.44     13537576.64
#Sta/Elev= 30
  3941.1  136.95  4154.8  132.48  4227.0  129.33  4395.2  126.26  4570.4  118.50
  4663.9  118.34  4670.9  119.56  4697.5  115.34  4720.5  114.66  4741.6  118.79
  4838.6  118.51  4869.0  118.99  4909.0  115.37  4924.3  109.80  4939.0  105.41
  4997.0   97.67  4997.3   97.17  5001.0   97.67  5039.0  108.51  5059.0  118.31
  5122.6  118.07  5144.9  119.19  5187.8  112.99  5329.8  126.04  5372.8  135.43
  5393.6  137.25  5407.9  140.93  5436.6  143.28  5564.2  147.20  5767.3  147.63
#Mann=9,-1,0
  3941.1    0.04       0  4227.0    0.05       0  4570.4    0.12       0
  4697.5    0.05       0  4838.6    0.12       0  4924.3    0.05       0
  4997.0    0.05       0  5001.0    0.05       0  5122.6    0.12       0
Bank Sta=4997,5001
Exp/Cntr=0.3,0.1

Type RM Length L Ch R = 1,588,0,0,0
BEGIN DESCRIPTION:
LGII2936
END DESCRIPTION:
XS GIS Cut Line= 4
      2558907.47     13536150.62      2558107.46     13536791.74
      2558088.36     13537116.39      2558569.92     13537597.46
#Sta/Elev= 30
  3841.5  136.70  4178.1  125.57  4365.9  118.81  4636.4  118.22  4686.0  111.08
  4700.6  114.25  4706.8  117.02  4735.6  115.07  4770.9  118.02  4879.5  116.43
  4970.1  116.46  4989.5  103.67  4994.5  106.84  5000.2  100.42  5008.2   95.88
  5008.5   95.38  5012.2   95.88  5090.4  103.67  5120.4  116.81  5193.6  116.85
  5337.1  116.37  5358.3  108.56  5372.4  106.31  5400.7  115.34  5506.8  121.92
  5556.3  128.28  5619.9  140.46  5685.3  145.11  5693.9  145.26  5872.6  146.27
#Mann=9,-1,0
  3841.5    0.04       0  4178.1    0.05       0  4700.6    0.12       0
  4879.5    0.05       0  5008.2    0.05       0  5012.2    0.05       0
  5193.6    0.12       0  5685.3    0.05       0  5693.9    0.12       0
Bank Sta=5008.2,5012.2
Exp/Cntr=0.3,0.1

Chan Stop Cuts=-1