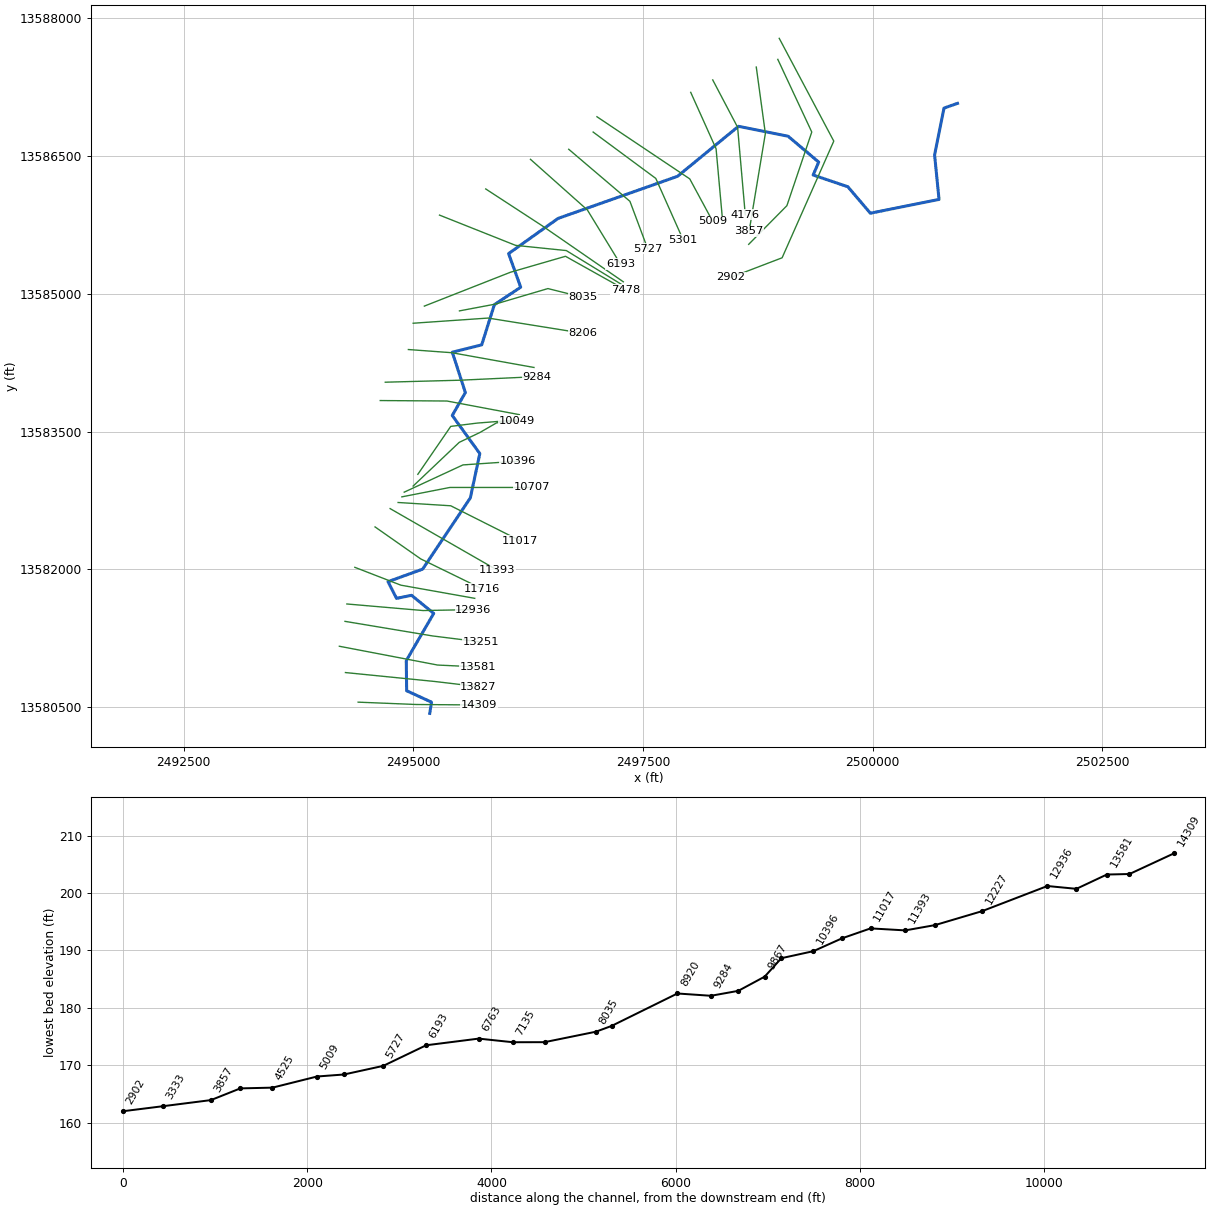
--- LOST CREEK.prj (project) ---

Proj Title=LOST CREEK Base Level Engineering
Current Plan=p01
Default Exp/Contr=0.3,0.1
English Units
Geom File=g01
Flow File=f01
Plan File=p01
Y Axis Title=Elevation
X Axis Title(PF)=Main Channel Distance
X Axis Title(XS)=Station
BEGIN DESCRIPTION:
LOST CREEK
END DESCRIPTION:
DSS Export Rating Curves= 0
DSS Export Rating Curve Sorted= 0
DSS Export Volume Flow Curves= 0
DXF OffsetX= 0
DXF OffsetY= 0
DXF ScaleX= 1
DXF ScaleY= 10

--- LOST CREEK.p01 (plan) ---

Plan Title=Multiple Run
Short Identifier=Multiple
Geom File=g01
Flow File=f01
Subcritical Flow
K Sum by GR= 0
Std Step Tol= 0.01
Critical Tol= 0.01
Num of Std Step Trials= 20
Max Error Tol= 0.3
Flow Tol Ratio= 0.001
Split Flow NTrial= 30
Split Flow Tol= 0.02
Split Flow Ratio= 0.02
Log Output Level= 0
Friction Slope Method= 1
Unsteady Friction Slope Method= 2
Unsteady Bridges Friction Slope Method= 1
Parabolic Critical Depth
Global Vel Dist=  1 , 1 , 1
Global Log Level= 0
CheckData=True
Encroach Param= -1, 0, 0, 0
BEGIN DESCRIPTION:
Multiple Run
END DESCRIPTION:

--- LOST CREEK.f01 (steady flow) ---

Flow Title=Multiple
Number of Profiles=7
Profile Names=10-year,25-year,50-year,1pct_min,100-year,1pct_plu,500-year
River Rch & RM= LOST CREEK,Reach-1,14309
     794    1298    1759    1154    2303    4595    3910
River Rch & RM= LOST CREEK,Reach-1,9581
    1434    2415    3339    2230    4449    8877    7832
River Rch & RM= LOST CREEK,Reach-1,4525
    1715    2913    4051    2720    5427   10829    9658
Boundary for River Rch & Prof#=LOST CREEK,Reach-1,1
Up Type=0
Dn Type=3
Dn Slope=0.005
Boundary for River Rch & Prof#=LOST CREEK,Reach-1,2
Up Type=0
Dn Type=3
Dn Slope=0.005
Boundary for River Rch & Prof#=LOST CREEK,Reach-1,3
Up Type=0
Dn Type=3
Dn Slope=0.005
Boundary for River Rch & Prof#=LOST CREEK,Reach-1,4
Up Type=0
Dn Type=3
Dn Slope=0.005
Boundary for River Rch & Prof#=LOST CREEK,Reach-1,5
Up Type=0
Dn Type=3
Dn Slope=0.005
Boundary for River Rch & Prof#=LOST CREEK,Reach-1,6
Up Type=0
Dn Type=3
Dn Slope=0.005
Boundary for River Rch & Prof#=LOST CREEK,Reach-1,7
Up Type=0
Dn Type=3
Dn Slope=0.005

--- LOST CREEK.g01 (geometry) ---

Geom Title=Existing Conditions

River Reach=LOST CREEK,Reach-1
Reach XY= 30
      2495179.84     13580429.84      2495199.07     13580552.17
      2494928.43     13580676.23      2494924.61     13581004.87
      2495223.22     13581518.92      2494981.73     13581715.85
      2494818.54     13581682.64      2494725.52     13581864.55
      2495102.30     13582001.09      2495621.63     13582776.74
      2495725.04     13583259.66      2495425.00     13583675.00
      2495567.67     13583924.90      2495425.55     13584364.37
      2495745.57     13584444.23      2495883.02     13584881.34
      2496170.04     13585072.46      2496038.34     13585438.30
      2496576.73     13585821.63      2497877.45     13586280.47
      2498540.39     13586824.92      2499081.06     13586716.86
      2499414.17     13586435.32      2499353.93     13586294.43
      2499731.07     13586166.87      2499976.50     13585878.46
      2500723.99     13586028.61      2500675.61     13586514.38
      2500778.42     13587023.78      2500925.00     13587075.00

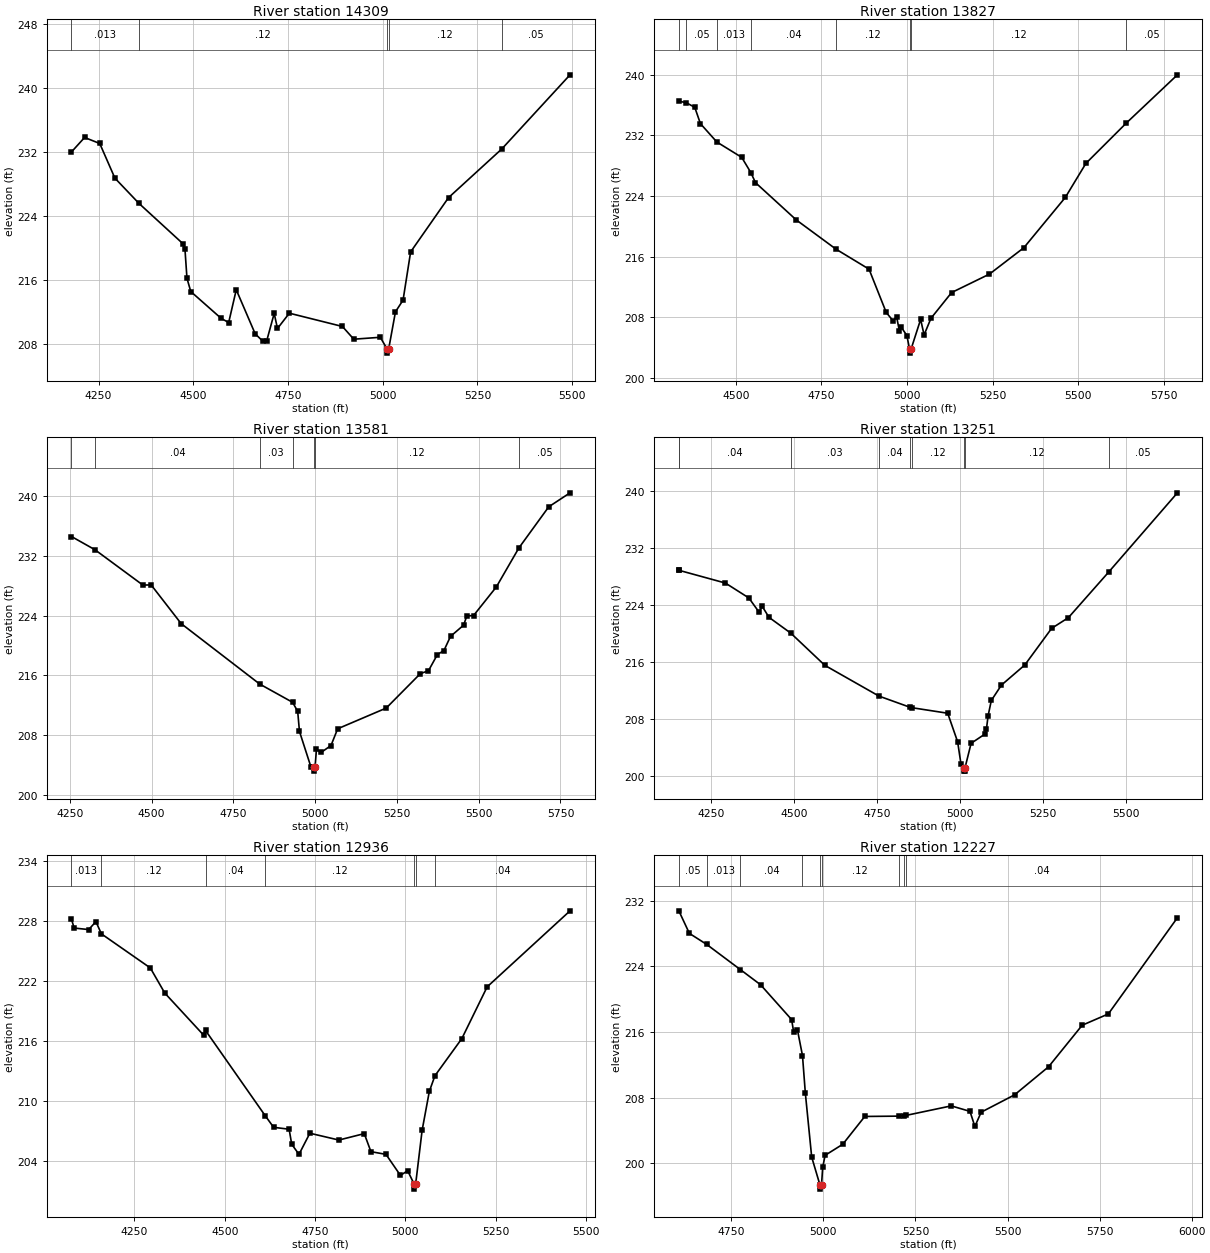
Type RM Length L Ch R = 1,14309,482,482,482
BEGIN DESCRIPTION:
LGII4478
END DESCRIPTION:
XS GIS Cut Line= 3
      2494400.45     13580552.06      2495035.07     13580526.47
      2495715.71     13580521.35
#Sta/Elev= 30
  4178.6  232.03  4213.2  233.84  4253.2  233.09  4293.2  228.76  4356.8  225.60
  4473.1  220.55  4478.1  219.90  4483.4  216.25  4493.4  214.59  4573.5  211.24
  4593.5  210.71  4613.5  214.81  4663.5  209.30  4683.6  208.38  4693.6  208.38
  4713.6  211.85  4722.3  209.97  4753.6  211.88  4893.7  210.22  4923.7  208.63
  4993.7  208.87  5011.7  207.39  5011.9  206.89  5015.7  207.39  5033.7  212.06
  5053.7  213.51  5073.7  219.54  5173.7  226.32  5314.6  232.42  5494.4  241.67
#Mann=5,-1,0
  4178.6   0.013       0  4356.8    0.12       0  5011.7    0.05       0
  5015.7    0.12       0  5314.6    0.05       0
Bank Sta=5011.7,5015.7
Exp/Cntr=0.3,0.1

Type RM Length L Ch R = 1,13827,246,246,246
BEGIN DESCRIPTION:
LGII4477
END DESCRIPTION:
XS GIS Cut Line= 3
      2494262.27     13580874.48      2495234.67     13580777.24
      2495710.31     13580720.98
#Sta/Elev= 30
  4333.6  236.48  4354.7  236.30  4380.1  235.68  4396.6  233.53  4444.6  231.11
  4517.2  229.09  4543.8  227.09  4557.4  225.76  4676.5  220.85  4792.8  216.99
  4889.1  214.36  4939.3  208.66  4959.4  207.55  4969.5  208.11  4978.0  206.18
  4983.1  206.72  4999.6  205.62  5007.6  203.80  5007.9  203.30  5011.7  203.80
  5039.8  207.74  5049.9  205.70  5070.0  207.89  5130.3  211.28  5240.8  213.71
  5341.4  217.19  5462.4  223.81  5522.6  228.30  5640.4  233.60  5789.8  239.96
#Mann=8,-1,0
  4333.6   0.013       0  4354.7    0.05       0  4444.6   0.013       0
  4543.8    0.04       0  4792.8    0.12       0  5007.6    0.05       0
  5011.7    0.12       0  5640.4    0.05       0
Bank Sta=5007.6,5011.7
Exp/Cntr=0.3,0.1

Type RM Length L Ch R = 1,13581,330,330,330
BEGIN DESCRIPTION:
LGII4476
END DESCRIPTION:
XS GIS Cut Line= 3
      2494195.73     13581161.07      2495265.37     13580956.36
      2495700.03     13580935.90
#Sta/Elev= 30
  4255.1  234.57  4327.0  232.80  4473.4  228.08  4498.7  228.10  4590.4  222.93
  4830.5  214.85  4931.1  212.41  4946.7  211.20  4952.1  208.52  4987.4  203.74
  4995.6  203.71  4995.8  203.21  4999.7  203.71  5004.1  206.13  5018.0  205.70
  5048.5  206.63  5068.9  208.87  5217.4  211.64  5321.6  216.24  5346.5  216.63
  5373.8  218.79  5393.8  219.33  5413.9  221.22  5453.9  222.72  5463.9  223.97
  5484.2  224.00  5554.0  227.83  5622.9  233.04  5714.2  238.54  5779.3  240.41
#Mann=7,-1,0
  4255.1   0.013       0  4327.0    0.04       0  4830.5    0.03       0
  4931.1    0.12       0  4995.6    0.05       0  4999.7    0.12       0
  5622.9    0.05       0
Bank Sta=4995.6,4999.7
Exp/Cntr=0.3,0.1

Type RM Length L Ch R = 1,13251,315,315,315
BEGIN DESCRIPTION:
LGII4475
END DESCRIPTION:
XS GIS Cut Line= 3
      2494257.17     13581432.31      2495209.08     13581273.66
      2495740.71     13581207.20
#Sta/Elev= 30
  4152.7  228.90  4153.8  228.91  4292.9  227.13  4363.4  225.04  4393.8  223.07
  4403.9  223.84  4424.2  222.31  4489.8  220.09  4592.0  215.58  4755.0  211.26
  4847.8  209.70  4855.2  209.62  4962.0  208.85  4991.9  204.84  5002.1  201.68
  5010.2  201.22  5010.4  200.72  5014.0  200.72  5014.3  201.22  5032.5  204.63
  5073.0  205.89  5078.6  206.63  5083.7  208.51  5093.3  210.64  5123.7  212.80
  5194.2  215.63  5274.9  220.77  5325.3  222.27  5446.5  228.67  5653.5  239.80
#Mann=9,-1,0
  4152.7   0.013       0  4153.8    0.04       0  4489.8    0.03       0
  4755.0    0.04       0  4847.8    0.03       0  4855.2    0.12       0
  5010.2    0.05       0  5014.3    0.12       0  5446.5    0.05       0
Bank Sta=5010.2,5014.3
Exp/Cntr=0.3,0.1

Type RM Length L Ch R = 1,12936,709,709,709
BEGIN DESCRIPTION:
LGII4474
END DESCRIPTION:
XS GIS Cut Line= 3
      2494277.62     13581621.67      2495106.72     13581550.02
      2495654.34     13581560.25
#Sta/Elev= 30
  4075.7  228.16  4083.1  227.27  4123.3  227.12  4143.3  227.91  4158.6  226.69
  4293.9  223.29  4334.0  220.78  4441.5  216.58  4446.7  217.05  4612.1  208.53
  4635.2  207.38  4678.1  207.19  4685.3  205.69  4705.4  204.68  4735.5  206.79
  4815.8  206.11  4886.1  206.75  4904.5  204.95  4946.2  204.68  4986.2  202.58
  5006.2  203.05  5024.1  201.71  5024.4  201.21  5028.3  201.71  5046.2  207.08
  5066.2  210.97  5081.7  212.53  5156.2  216.24  5226.2  221.40  5455.6  228.99
#Mann=7,-1,0
  4075.7   0.013       0  4158.6    0.12       0  4446.7    0.04       0
  4612.1    0.12       0  5024.1    0.05       0  5028.3    0.12       0
  5081.7    0.04       0
Bank Sta=5024.1,5028.3
Exp/Cntr=0.3,0.1

Type RM Length L Ch R = 1,12227,511,511,511
BEGIN DESCRIPTION:
LGII4473
END DESCRIPTION:
XS GIS Cut Line= 3
      2494364.64     13582020.85      2494866.19     13581826.37
      2495669.68     13581683.08
#Sta/Elev= 30
  4607.3  230.76  4635.9  228.01  4683.1  226.66  4774.5  223.59  4829.2  221.75
  4913.6  217.50  4919.0  216.02  4929.5  216.22  4943.1  213.11  4950.9  208.51
  4968.1  200.74  4990.6  197.33  4990.8  196.83  4994.8  197.33  4998.0  199.48
  5004.5  200.95  5052.5  202.30  5112.3  205.69  5204.3  205.73  5217.7  205.80
  5223.5  205.81  5347.2  206.98  5398.0  206.31  5411.3  204.47  5428.4  206.21
  5519.0  208.32  5611.3  211.74  5702.7  216.81  5773.8  218.19  5961.4  229.92
#Mann=9,-1,0
  4607.3    0.05       0  4683.1   0.013       0  4774.5    0.04       0
  4943.1    0.12       0  4990.6    0.05       0  4994.8    0.12       0
  5204.3    0.04       0  5217.7    0.12       0  5223.5    0.04       0
Bank Sta=4990.6,4994.8
Exp/Cntr=0.3,0.1

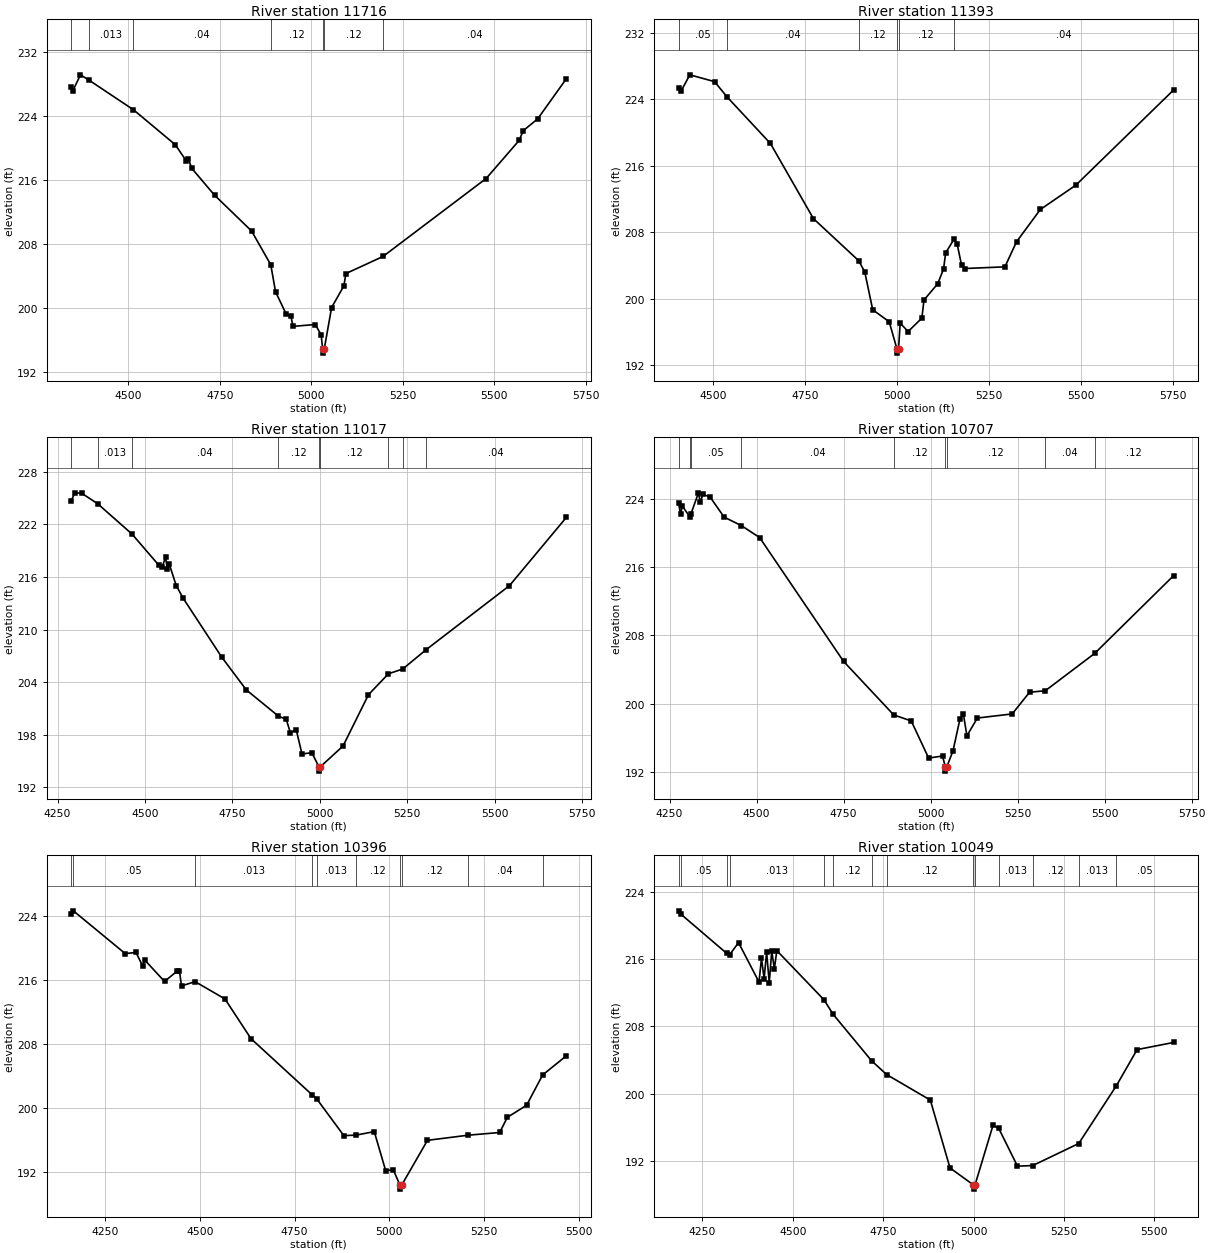
Type RM Length L Ch R = 1,11716,323,323,323
BEGIN DESCRIPTION:
LGII4472
END DESCRIPTION:
XS GIS Cut Line= 3
      2494584.74     13582460.96      2495081.13     13582112.97
      2495750.77     13581785.82
#Sta/Elev= 30
  4344.8  227.57  4348.8  227.12  4369.8  229.13  4392.0  228.50  4514.5  224.77
  4628.7  220.41  4658.3  218.42  4664.4  218.67  4673.1  217.49  4735.9  214.11
  4837.0  209.64  4889.4  205.43  4902.4  202.06  4931.3  199.29  4944.2  199.02
  4950.3  197.74  5011.0  197.97  5026.9  196.68  5031.1  194.90  5031.4  194.40
  5035.3  194.90  5055.5  200.09  5088.9  202.79  5094.5  204.33  5195.7  206.46
  5477.3  216.19  5567.4  220.94  5578.6  222.16  5618.0  223.63  5696.3  228.64
#Mann=7,-1,0
  4344.8    0.05       0  4392.0   0.013       0  4514.5    0.04       0
  4889.4    0.12       0  5031.1    0.05       0  5035.3    0.12       0
  5195.7    0.04       0
Bank Sta=5031.1,5035.3
Exp/Cntr=0.3,0.1

Type RM Length L Ch R = 1,11393,376,376,376
BEGIN DESCRIPTION:
LGII4471
END DESCRIPTION:
XS GIS Cut Line= 2
      2494748.48     13582660.57      2495915.30     13581990.16
#Sta/Elev= 30
  4405.2  225.41  4412.7  225.07  4435.8  226.96  4503.0  226.14  4537.4  224.28
  4654.9  218.70  4771.8  209.66  4895.0  204.59  4911.3  203.25  4932.9  198.70
  4977.8  197.25  4998.8  193.98  4999.1  193.48  5003.1  193.98  5007.6  197.08
  5029.2  196.08  5066.5  197.69  5072.3  199.87  5109.7  201.83  5125.5  203.60
  5131.2  205.54  5153.6  207.16  5162.4  206.61  5174.4  204.08  5184.4  203.66
  5292.3  203.86  5323.8  206.87  5388.6  210.76  5484.9  213.68  5750.9  225.14
#Mann=6,-1,0
  4405.2    0.05       0  4537.4    0.04       0  4895.0    0.12       0
  4998.8    0.05       0  5003.1    0.12       0  5153.6    0.04       0
Bank Sta=4998.8,5003.1
Exp/Cntr=0.3,0.1

Type RM Length L Ch R = 1,11017,310,310,310
BEGIN DESCRIPTION:
LGII4470
END DESCRIPTION:
XS GIS Cut Line= 3
      2494835.47     13582727.10      2495408.67     13582691.27
      2496160.47     13582312.82
#Sta/Elev= 30
  4289.4  224.69  4298.9  225.61  4319.0  225.56  4364.4  224.38  4463.1  220.90
  4539.4  217.36  4549.4  217.13  4559.0  218.27  4564.0  216.91  4569.5  217.49
  4589.5  215.02  4609.6  213.56  4719.3  206.87  4789.9  203.11  4880.9  200.14
  4904.4  199.73  4916.1  198.20  4932.8  198.56  4949.2  195.79  4977.5  195.93
  4997.6  194.33  4997.9  193.83  5001.9  194.33  5066.7  196.70  5139.5  202.56
  5196.6  204.95  5237.4  205.49  5304.1  207.69  5542.5  215.00  5705.4  222.80
#Mann=9,-1,0
  4289.4    0.05       0  4364.4   0.013       0  4463.1    0.04       0
  4880.9    0.12       0  4997.6    0.05       0  5001.9    0.12       0
  5196.6    0.04       0  5237.4    0.05       0  5304.1    0.04       0
Bank Sta=4997.6,5001.9
Exp/Cntr=0.3,0.1

Type RM Length L Ch R = 1,10707,311,311,311
BEGIN DESCRIPTION:
LGII4469
END DESCRIPTION:
XS GIS Cut Line= 3
      2494876.41     13582788.51      2495398.43     13582890.86
      2496288.87     13582890.86
#Sta/Elev= 30
  4275.8  223.45  4281.5  222.23  4286.6  223.15  4308.2  221.88  4311.0  222.20
  4333.0  224.70  4338.1  223.59  4345.7  224.51  4366.1  224.22  4406.8  221.85
  4456.3  220.86  4508.7  219.46  4749.8  204.96  4894.1  198.68  4944.3  197.98
  4994.3  193.63  5034.3  193.87  5042.1  192.60  5042.4  192.10  5046.5  192.60
  5064.3  194.48  5084.3  198.21  5094.3  198.74  5104.3  196.24  5134.3  198.32
  5234.3  198.80  5284.3  201.34  5329.6  201.52  5471.1  205.88  5698.2  215.00
#Mann=9,-1,0
  4275.8    0.05       0  4308.2   0.013       0  4311.0    0.05       0
  4456.3    0.04       0  4894.1    0.12       0  5042.1    0.05       0
  5046.5    0.12       0  5329.6    0.04       0  5471.1    0.12       0
Bank Sta=5042.1,5046.5
Exp/Cntr=0.3,0.1

Type RM Length L Ch R = 1,10396,347,347,347
BEGIN DESCRIPTION:
LGII4468
END DESCRIPTION:
XS GIS Cut Line= 3
      2494902.05     13582839.70      2495541.73     13583136.52
      2496140.24     13583177.44
#Sta/Elev= 30
  4161.3  224.21  4166.7  224.60  4303.5  219.26  4331.9  219.41  4349.3  217.71
  4354.8  218.47  4407.1  215.78  4440.2  217.07  4446.4  217.05  4451.9  215.23
  4487.7  215.76  4566.4  213.60  4635.1  208.64  4796.3  201.63  4808.8  201.10
  4879.8  196.54  4911.9  196.60  4960.0  197.04  4990.0  192.18  5010.1  192.27
  5027.9  190.36  5028.2  189.86  5032.3  190.36  5100.3  195.95  5207.1  196.59
  5290.7  196.93  5310.8  198.82  5361.6  200.33  5403.9  204.11  5466.4  206.50
#Mann=10,-1,0
  4161.3   0.013       0  4166.7    0.05       0  4487.7   0.013       0
  4796.3    0.05       0  4808.8   0.013       0  4911.9    0.12       0
  5027.9    0.05       0  5032.3    0.12       0  5207.1    0.04       0
  5403.9   0.013       0
Bank Sta=5027.9,5032.3
Exp/Cntr=0.3,0.1

Type RM Length L Ch R = 1,10049,182,182,182
BEGIN DESCRIPTION:
LGII4467
END DESCRIPTION:
XS GIS Cut Line= 5
      2494999.22     13582906.19      2495500.79     13583382.17
      2495725.97     13583489.64      2495908.17     13583595.02
      2496125.64     13583614.54
#Sta/Elev= 30
  4183.9  221.71  4189.6  221.34  4316.7  216.67  4325.6  216.52  4349.8  217.93
  4406.4  213.25  4413.3  216.07  4420.6  213.64  4427.5  216.82  4434.8  213.15
  4441.7  216.94  4448.9  214.82  4455.8  216.98  4585.8  211.16  4611.8  209.40
  4717.8  203.90  4759.4  202.26  4880.5  199.22  4934.9  191.16  4999.7  189.14
  5000.0  188.64  5004.2  189.14  5053.9  196.22  5069.7  195.87  5121.6  191.37
  5163.8  191.44  5291.1  194.06  5394.8  200.89  5452.7  205.22  5553.7  206.07
#Mann=14,-1,0
  4183.9   0.013       0  4189.6    0.05       0  4316.7    0.04       0
  4325.6   0.013       0  4585.8    0.05       0  4611.8    0.12       0
  4717.8   0.013       0  4759.4    0.12       0  4999.7    0.05       0
  5004.2    0.12       0  5069.7   0.013       0  5163.8    0.12       0
  5291.1   0.013       0  5394.8    0.05       0
Bank Sta=4999.7,5004.2
Exp/Cntr=0.3,0.1

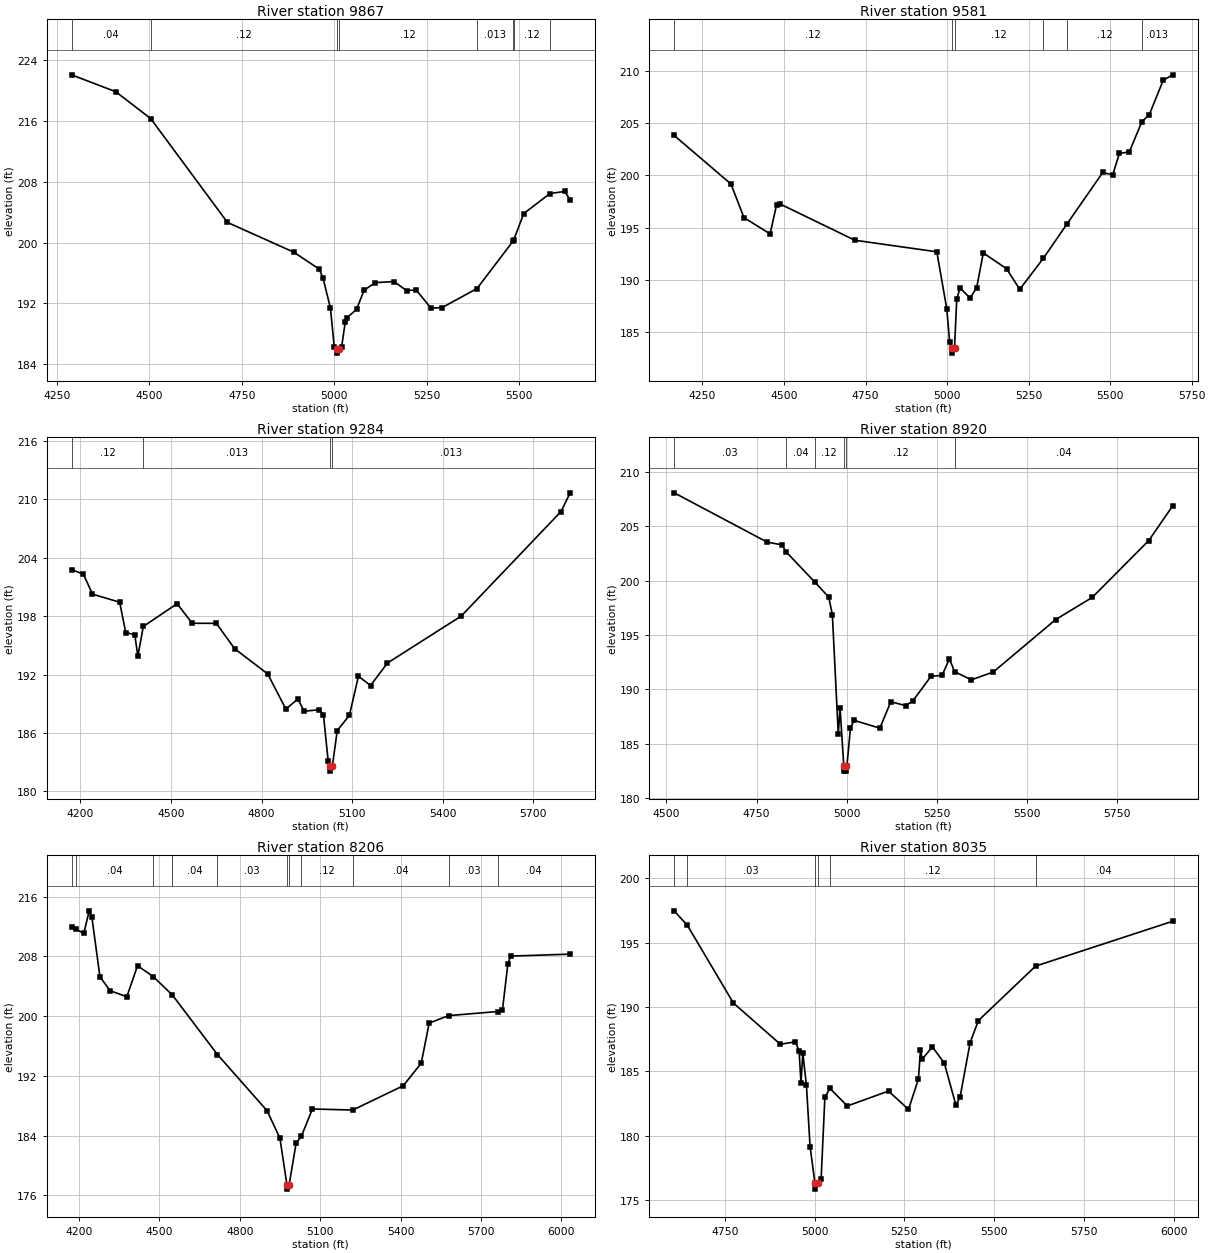
Type RM Length L Ch R = 1,9867,286,286,286
BEGIN DESCRIPTION:
LGII4465
END DESCRIPTION:
XS GIS Cut Line= 4
      2495050.43     13583034.16      2495408.67     13583556.17
      2495695.26     13583592.00      2496119.99     13583625.68
#Sta/Elev= 30
  4289.6  222.11  4409.2  219.88  4503.7  216.33  4711.0  202.65  4890.3  198.73
  4959.3  196.49  4969.4  195.32  4989.6  191.32  4999.6  186.29  5007.5  185.92
  5007.8  185.42  5012.0  185.92  5019.8  186.29  5029.5  189.49  5034.6  190.11
  5060.1  191.18  5080.3  193.70  5110.1  194.71  5160.9  194.86  5195.8  193.66
  5221.3  193.76  5261.4  191.34  5291.5  191.43  5385.7  193.93  5484.2  200.25
  5484.5  200.28  5512.2  203.82  5582.6  206.45  5622.6  206.74  5637.6  205.64
#Mann=8,-1,0
  4289.6    0.04       0  4503.7    0.12       0  5007.5    0.05       0
  5012.0    0.12       0  5385.7   0.013       0  5484.2    0.05       0
  5484.5    0.12       0  5582.6   0.013       0
Bank Sta=5007.5,5012
Exp/Cntr=0.3,0.1

Type RM Length L Ch R = 1,9581,297,297,297
BEGIN DESCRIPTION:
LGII4466
END DESCRIPTION:
XS GIS Cut Line= 3
      2494641.03     13583837.65      2495367.73     13583832.53
      2496155.86     13583684.12
#Sta/Elev= 30
  4163.3  203.83  4337.3  199.18  4377.3  195.95  4457.3  194.39  4477.3  197.18
  4487.3  197.27  4717.3  193.78  4968.6  192.67  4999.2  187.18  5008.0  183.98
  5016.1  183.45  5016.6  182.95  5022.9  183.45  5029.7  188.13  5039.9  189.21
  5070.6  188.23  5090.8  189.23  5111.1  192.56  5182.3  191.05  5222.9  189.07
  5295.6  192.06  5368.5  195.38  5477.4  200.28  5508.0  200.05  5528.3  202.11
  5558.8  202.25  5597.4  205.16  5619.9  205.81  5662.9  209.14  5692.0  209.65
#Mann=6,-1,0
  4163.3    0.12       0  5016.1    0.05       0  5022.9    0.12       0
  5295.6    0.04       0  5368.5    0.12       0  5597.4   0.013       0
Bank Sta=5016.1,5022.9
Exp/Cntr=0.3,0.1

Type RM Length L Ch R = 1,9284,364,364,364
BEGIN DESCRIPTION:
Mapping XS b0628a78
END DESCRIPTION:
XS GIS Cut Line= 3
      2494695.82     13584037.51      2495511.76     13584059.21
      2496345.12     13584098.27
#Sta/Elev= 30
  4171.2  202.78  4210.4  202.31  4240.4  200.26  4330.4  199.43  4350.4  196.32
  4380.5  196.09  4390.5  193.88  4408.6  196.94  4520.5  199.28  4570.5  197.27
  4650.5  197.26  4710.6  194.67  4820.6  192.06  4880.6  188.46  4920.6  189.50
  4940.6  188.24  4991.6  188.39  5005.0  187.86  5020.7  183.09  5027.0  182.59
  5027.5  182.09  5034.4  182.59  5050.7  186.26  5090.8  187.81  5120.8  191.83
  5160.9  190.88  5216.9  193.19  5461.2  198.01  5791.5  208.74  5821.7  210.66
#Mann=4,-1,0
  4171.2    0.12       0  4408.6   0.013       0  5027.0    0.03       0
  5034.4   0.013       0
Bank Sta=5027,5034.4
Exp/Cntr=0.3,0.1

Type RM Length L Ch R = 1,8920,714,714,714
BEGIN DESCRIPTION:
Mapping XS 3d4d3cce
END DESCRIPTION:
XS GIS Cut Line= 3
      2494947.50     13584393.41      2495420.62     13584358.69
      2496314.72     13584198.10
#Sta/Elev= 30
  4521.4  208.09  4779.6  203.55  4819.7  203.31  4831.8  202.66  4910.9  199.90
  4950.0  198.50  4960.1  196.89  4976.5  185.91  4981.5  188.28  4991.8  182.99
  4992.3  182.49  4998.7  182.49  4999.2  182.99  5000.6  182.99  5010.4  186.50
  5020.6  187.16  5091.7  186.44  5122.2  188.87  5163.0  188.52  5183.1  188.94
  5233.9  191.22  5264.4  191.29  5284.7  192.82  5299.2  191.64  5345.7  190.89
  5406.6  191.61  5579.4  196.43  5681.0  198.47  5837.7  203.70  5904.2  206.90
#Mann=6,-1,0
  4521.4    0.03       0  4831.8    0.04       0  4910.9    0.12       0
  4991.8    0.05       0  4999.2    0.12       0  5299.2    0.04       0
Bank Sta=4991.8,4999.2
Exp/Cntr=0.3,0.1

Type RM Length L Ch R = 1,8206,171,171,171
BEGIN DESCRIPTION:
Mapping XS ccfadafa
END DESCRIPTION:
XS GIS Cut Line= 3
      2494999.56     13584679.87      2495815.58     13584736.29
      2496844.27     13584571.36
#Sta/Elev= 30
  4172.9  211.95  4190.7  211.62  4218.4  211.07  4238.5  214.10  4248.5  213.27
  4278.6  205.27  4316.7  203.41  4378.8  202.59  4418.9  206.75  4477.8  205.29
  4549.3  202.81  4717.0  194.86  4902.4  187.32  4950.2  183.64  4976.5  177.34
  4977.0  176.84  4984.0  177.34  5010.5  183.00  5029.9  183.90  5071.3  187.57
  5221.9  187.43  5410.1  190.68  5477.1  193.70  5506.8  199.07  5579.4  200.07
  5762.6  200.62  5780.2  200.84  5800.5  207.03  5810.6  208.04  6032.7  208.30
#Mann=11,-1,0
  4172.9    0.12       0  4190.7    0.04       0  4477.8    0.03       0
  4549.3    0.04       0  4717.0    0.03       0  4976.5    0.03       0
  4984.0    0.03       0  5029.9    0.12       0  5221.9    0.04       0
  5579.4    0.03       0  5762.6    0.04       0
Bank Sta=4976.5,4984
Exp/Cntr=0.3,0.1

Type RM Length L Ch R = 1,8035,557,557,557
BEGIN DESCRIPTION:
Mapping XS 65d9a2f7
END DESCRIPTION:
XS GIS Cut Line= 4
      2495503.10     13584814.42      2495893.71     13584888.20
      2496466.62     13585057.47      2496848.55     13584961.99
#Sta/Elev= 30
  4609.1  197.48  4646.1  196.34  4773.9  190.31  4904.8  187.10  4946.9  187.29
  4957.0  186.58  4962.3  184.08  4967.4  186.40  4977.4  183.92  4987.6  179.14
  5000.9  176.33  5001.4  175.83  5008.5  176.33  5018.4  176.63  5028.8  182.97
  5042.9  183.66  5091.4  182.30  5206.1  183.46  5261.7  182.03  5289.5  184.41
  5295.0  186.62  5300.2  185.95  5328.3  186.90  5361.6  185.62  5393.8  182.37
  5405.3  182.99  5433.4  187.23  5456.3  188.94  5615.7  193.18  5997.7  196.67
#Mann=6,-1,0
  4609.1    0.04       0  4646.1    0.03       0  5000.9    0.03       0
  5008.5    0.03       0  5042.9    0.12       0  5615.7    0.04       0
Bank Sta=5000.9,5008.5
Exp/Cntr=0.3,0.1

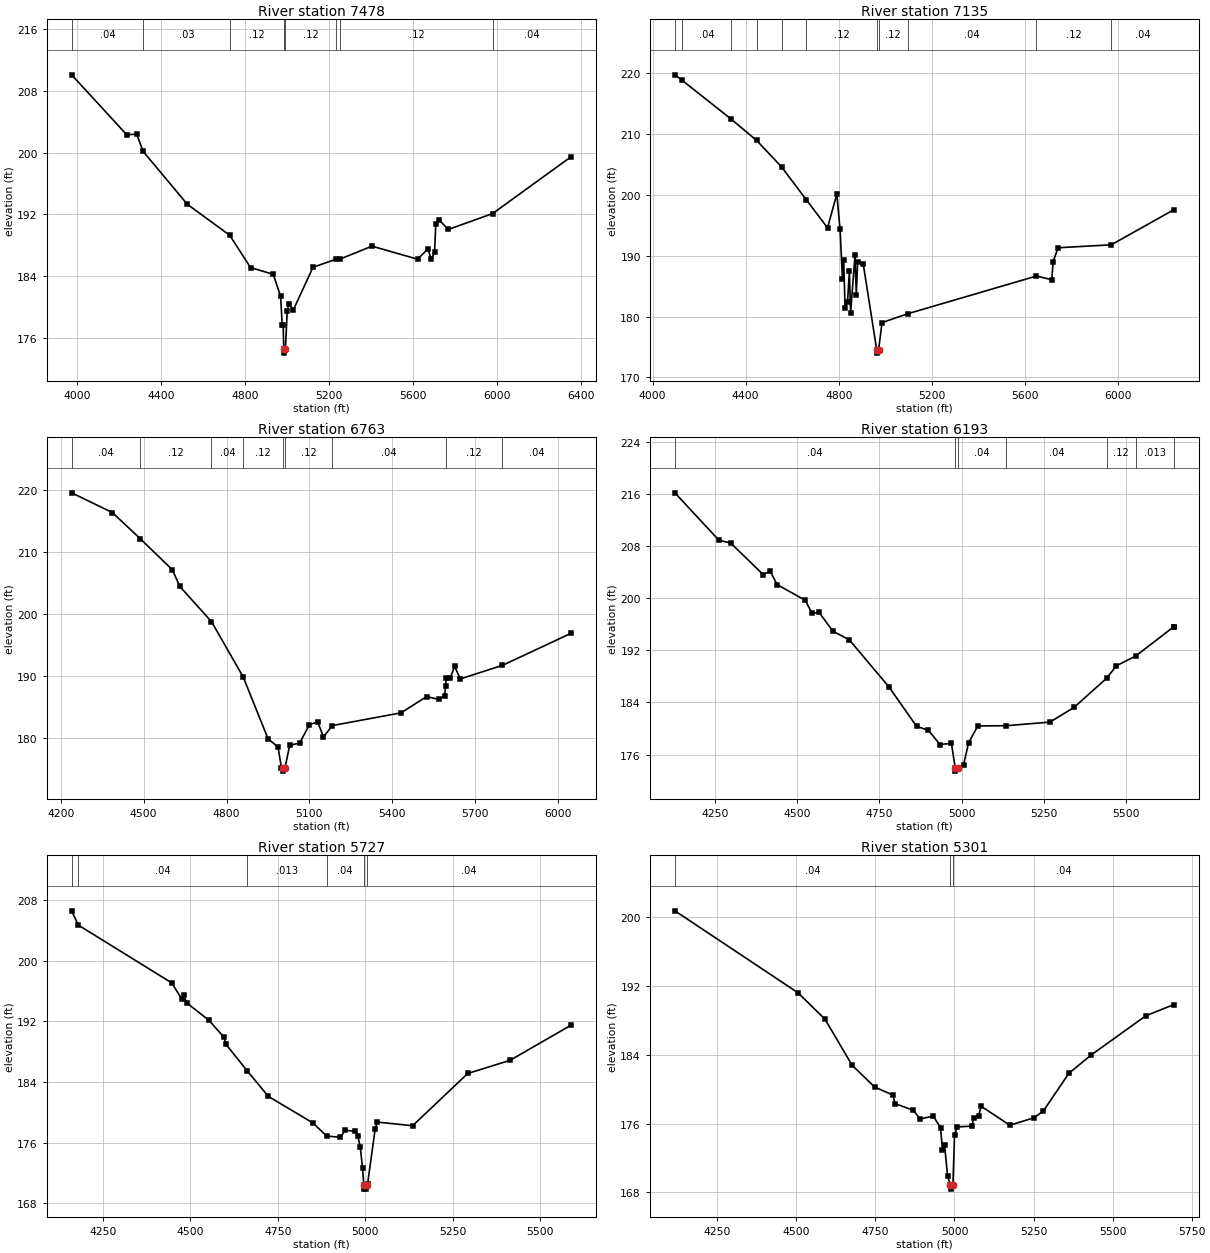
Type RM Length L Ch R = 1,7478,343,343,343
BEGIN DESCRIPTION:
Mapping XS 90c0c9d0
END DESCRIPTION:
XS GIS Cut Line= 4
      2495121.10     13584866.49      2496058.64     13585235.43
      2496657.60     13585409.04      2497308.63     13585044.46
#Sta/Elev= 30
  3974.6  210.07  4236.7  202.32  4284.8  202.37  4315.1  200.15  4525.9  193.29
  4727.3  189.29  4826.6  185.10  4934.9  184.22  4970.1  181.35  4977.5  177.59
  4982.1  177.59  4984.9  174.51  4985.4  174.01  4992.6  174.51  5001.5  179.49
  5009.6  180.41  5029.8  179.57  5124.1  185.13  5235.4  186.20  5254.7  186.22
  5405.2  187.87  5622.1  186.18  5671.5  187.52  5687.2  186.15  5703.1  187.08
  5708.9  190.78  5724.8  191.27  5768.2  190.03  5979.4  192.09  6351.9  199.43
#Mann=8,-1,0
  3974.6    0.04       0  4315.1    0.03       0  4727.3    0.12       0
  4984.9    0.05       0  4992.6    0.12       0  5235.4    0.04       0
  5254.7    0.12       0  5979.4    0.04       0
Bank Sta=4984.9,4992.6
Exp/Cntr=0.3,0.1

Type RM Length L Ch R = 1,7135,372,372,372
BEGIN DESCRIPTION:
Mapping XS 493e0b28
END DESCRIPTION:
XS GIS Cut Line= 4
      2495286.10     13585857.81      2496115.06     13585527.96
      2496666.28     13585471.54      2497260.42     13585107.24
#Sta/Elev= 30
  4096.1  219.78  4125.8  218.92  4337.5  212.50  4447.0  208.99  4554.1  204.63
  4661.1  199.19  4751.4  194.62  4791.3  200.14  4805.2  194.42  4815.5  186.20
  4820.9  189.38  4826.8  181.38  4837.5  182.48  4845.2  187.53  4850.6  180.66
  4869.5  190.12  4874.9  183.57  4880.6  188.97  4904.5  188.73  4962.8  174.50
  4963.3  174.00  4970.6  174.50  4985.5  179.02  5095.1  180.47  5648.2  186.68
  5714.2  186.08  5720.1  189.07  5741.4  191.33  5970.0  191.82  6239.3  197.61
#Mann=11,-1,0
  4096.1    0.03       0  4125.8    0.04       0  4337.5    0.03       0
  4447.0    0.04       0  4554.1    0.03       0  4661.1    0.12       0
  4962.8    0.05       0  4970.6    0.12       0  5095.1    0.04       0
  5648.2    0.12       0  5970.0    0.04       0
Bank Sta=4962.8,4970.6
Exp/Cntr=0.3,0.1

Type RM Length L Ch R = 1,6763,570,570,570
BEGIN DESCRIPTION:
Mapping XS 137bac4d
END DESCRIPTION:
XS GIS Cut Line= 3
      2495789.54     13586142.55      2496401.52     13585743.24
      2497286.97     13585131.24
#Sta/Elev= 30
  4239.3  219.47  4386.7  216.30  4487.9  212.07  4604.0  207.07  4631.1  204.38
  4745.6  198.72  4860.5  189.79  4950.3  179.85  4986.4  178.51  4999.0  175.14
  5003.9  175.13  5004.4  174.63  5011.7  175.13  5028.7  178.80  5064.6  179.14
  5100.4  182.13  5130.1  182.55  5151.1  180.14  5183.3  181.97  5431.6  184.02
  5524.2  186.63  5568.8  186.20  5589.7  186.79  5593.0  188.32  5595.8  189.61
  5610.7  189.67  5625.5  191.52  5646.5  189.49  5799.0  191.67  6046.4  196.82
#Mann=9,-1,0
  4239.3    0.04       0  4487.9    0.12       0  4745.6    0.04       0
  4860.5    0.12       0  5003.9    0.05       0  5011.7    0.12       0
  5183.3    0.04       0  5593.0    0.12       0  5799.0    0.04       0
Bank Sta=5003.9,5011.7
Exp/Cntr=0.3,0.1

Type RM Length L Ch R = 1,6193,466,466,466
BEGIN DESCRIPTION:
Mapping XS 55c53aae
END DESCRIPTION:
XS GIS Cut Line= 3
      2496276.20     13586465.69      2496895.96     13585913.63
      2497255.35     13585325.07
#Sta/Elev= 30
  4127.3  216.16  4261.2  208.89  4297.2  208.46  4395.8  203.63  4417.6  204.14
  4438.5  202.08  4523.8  199.69  4544.7  197.70  4566.4  197.81  4608.2  194.94
  4658.4  193.60  4778.8  186.40  4863.2  180.33  4899.2  179.74  4934.3  177.55
  4969.1  177.74  4980.6  173.97  4981.1  173.47  4988.5  173.97  5005.9  174.38
  5021.4  177.82  5049.4  180.40  5136.1  180.44  5269.1  180.99  5342.3  183.24
  5441.8  187.73  5471.2  189.62  5530.2  191.13  5646.6  195.64  5646.9  195.64
#Mann=7,-1,0
  4127.3    0.04       0  4980.6    0.05       0  4988.5    0.04       0
  5136.1    0.04       0  5441.8    0.12       0  5530.2   0.013       0
  5646.6    0.04       0
Bank Sta=4980.6,4988.5
Exp/Cntr=0.3,0.1

Type RM Length L Ch R = 1,5727,426,426,426
BEGIN DESCRIPTION:
Mapping XS ee039334
END DESCRIPTION:
XS GIS Cut Line= 3
      2496692.80     13586575.12      2497359.50     13586007.38
      2497552.20     13585491.80
#Sta/Elev= 30
  4160.8  206.56  4179.9  204.68  4446.2  197.08  4474.8  195.00  4481.3  195.42
  4489.0  194.45  4552.7  192.15  4595.6  189.93  4602.1  188.95  4662.8  185.45
  4722.9  182.10  4850.3  178.60  4889.1  176.89  4928.3  176.70  4942.5  177.65
  4971.1  177.48  4978.0  176.93  4985.4  175.47  4992.0  172.61  4995.7  170.38
  4996.2  169.88  5003.2  169.88  5003.7  170.38  5006.2  170.52  5028.2  177.87
  5034.5  178.71  5135.1  178.24  5292.4  185.12  5413.6  186.86  5586.9  191.47
#Mann=6,-1,0
  4160.8    0.05       0  4179.9    0.04       0  4662.8   0.013       0
  4889.1    0.04       0  4995.7    0.04       0  5003.7    0.04       0
Bank Sta=4995.7,5003.7
Exp/Cntr=0.3,0.1

Type RM Length L Ch R = 1,5301,292,292,292
BEGIN DESCRIPTION:
Mapping XS f03f148e
END DESCRIPTION:
XS GIS Cut Line= 3
      2496958.48     13586762.58      2497640.75     13586257.38
      2497937.62     13585590.74
#Sta/Elev= 30
  4115.7  200.76  4504.9  191.23  4590.5  188.15  4676.1  182.80  4747.0  180.27
  4805.5  179.32  4811.7  178.34  4870.2  177.54  4891.0  176.55  4932.7  176.87
  4955.8  175.55  4962.0  172.90  4968.7  173.47  4978.2  169.87  4987.0  168.88
  4987.5  168.38  4995.1  168.88  5000.1  174.69  5008.8  175.62  5054.8  175.71
  5060.7  176.63  5076.7  176.94  5084.0  178.03  5175.2  175.81  5251.9  176.69
  5280.8  177.46  5361.5  181.84  5431.2  183.96  5604.8  188.54  5694.4  189.86
#Mann=3,-1,0
  4115.7    0.04       0  4987.0    0.04       0  4995.1    0.04       0
Bank Sta=4987,4995.1
Exp/Cntr=0.3,0.1

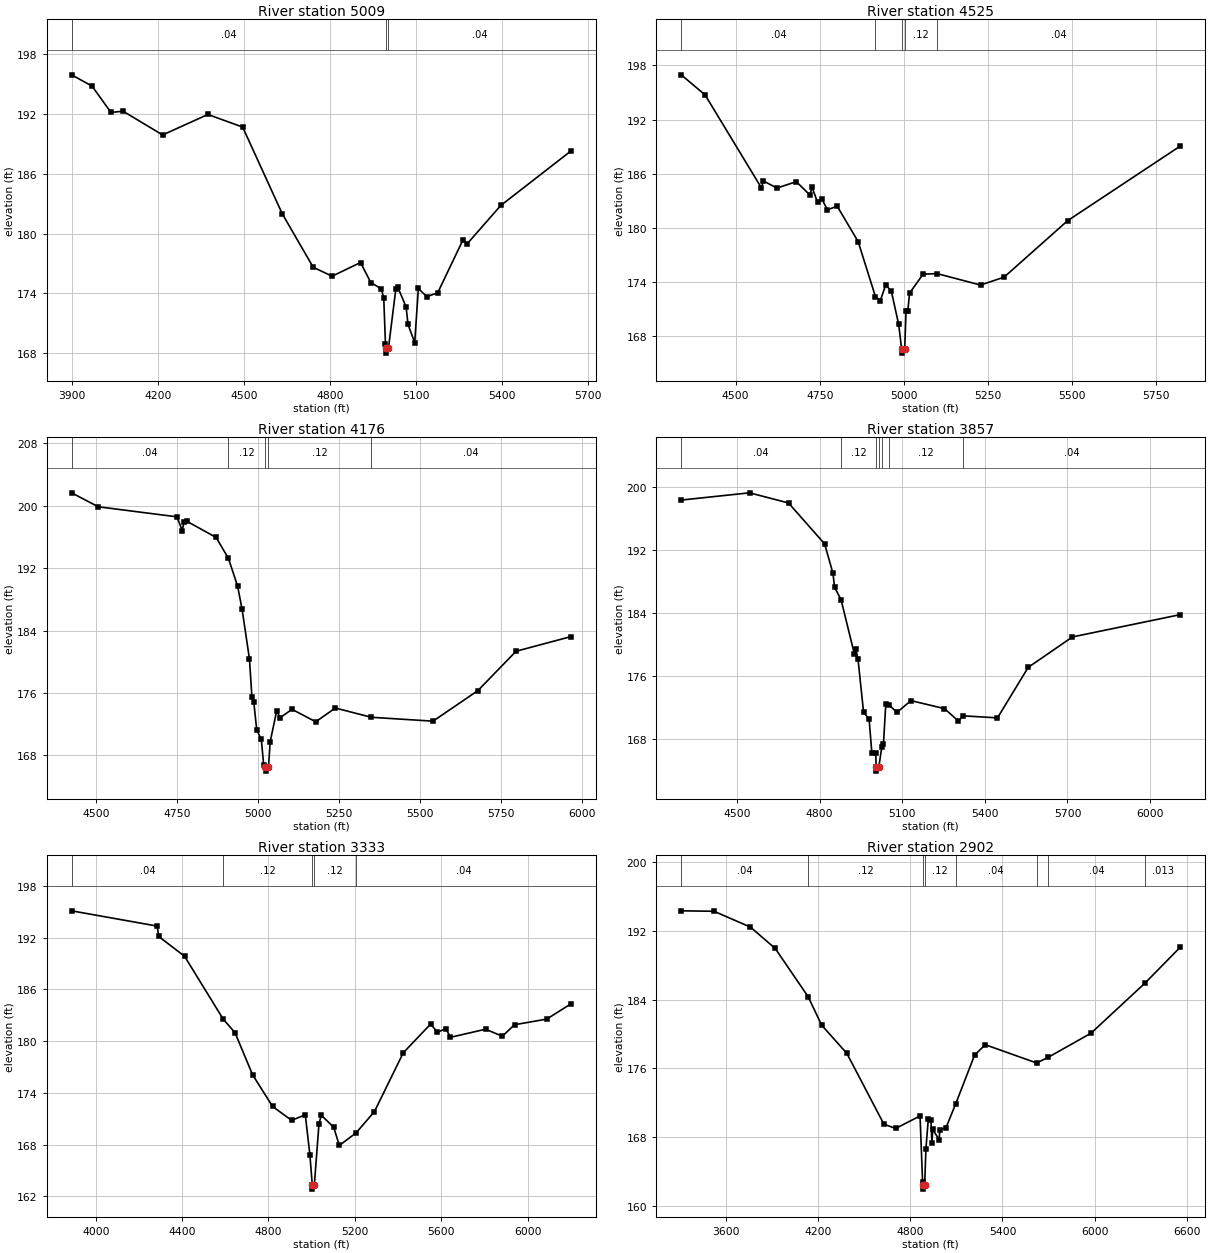
Type RM Length L Ch R = 1,5009,484,484,484
BEGIN DESCRIPTION:
Mapping XS c34036fb
END DESCRIPTION:
XS GIS Cut Line= 3
      2497000.16     13586929.24      2498010.55     13586252.18
      2498259.92     13585789.80
#Sta/Elev= 30
  3897.5  195.89  3968.8  194.76  4034.8  192.12  4076.8  192.25  4214.9  189.87
  4372.8  191.92  4494.1  190.66  4632.1  181.99  4740.2  176.63  4806.1  175.73
  4905.3  177.10  4941.3  175.09  4977.3  174.48  4986.3  173.58  4992.3  168.97
  4994.7  168.53  4995.2  168.03  5002.8  168.53  5028.4  174.43  5034.9  174.67
  5064.4  172.64  5071.0  170.90  5094.4  169.09  5107.1  174.50  5136.3  173.69
  5174.4  174.06  5262.0  179.32  5278.2  179.00  5394.6  182.81  5639.1  188.26
#Mann=3,-1,0
  3897.5    0.04       0  4994.7    0.04       0  5002.8    0.04       0
Bank Sta=4994.7,5002.8
Exp/Cntr=0.3,0.1

Type RM Length L Ch R = 1,4525,349,349,349
BEGIN DESCRIPTION:
Mapping XS c38e4234
END DESCRIPTION:
XS GIS Cut Line= 3
      2498020.98     13587194.84      2498297.00     13586580.30
      2498369.92     13585772.97
#Sta/Elev= 30
  4338.3  196.96  4409.3  194.73  4576.9  184.41  4582.4  185.19  4623.1  184.40
  4680.5  185.11  4721.4  183.61  4726.9  184.53  4743.7  182.81  4755.5  183.24
  4773.2  181.98  4801.8  182.40  4864.3  178.46  4915.7  172.37  4930.1  171.91
  4946.3  173.65  4963.0  172.96  4984.9  169.27  4993.4  166.59  4993.9  166.09
  5002.8  166.59  5006.7  170.78  5012.0  170.78  5017.3  172.75  5057.5  174.85
  5099.3  174.91  5228.2  173.64  5298.4  174.52  5487.1  180.78  5822.6  189.07
#Mann=5,-1,0
  4338.3    0.04       0  4915.7    0.12       0  4993.4    0.05       0
  5002.8    0.12       0  5099.3    0.04       0
Bank Sta=4993.4,5002.8
Exp/Cntr=0.3,0.1

Type RM Length L Ch R = 1,4176,319,319,319
BEGIN DESCRIPTION:
Mapping XS d333edcd
END DESCRIPTION:
XS GIS Cut Line= 3
      2498260.55     13587330.30      2498531.38     13586814.68
      2498614.71     13585861.53
#Sta/Elev= 30
  4425.8  201.67  4507.9  199.88  4750.5  198.59  4766.9  196.83  4772.5  197.99
  4781.9  198.00  4871.4  195.94  4909.2  193.26  4937.6  189.69  4951.4  186.71
  4974.0  180.38  4981.7  175.45  4987.3  174.87  4996.6  171.21  5010.6  170.04
  5017.9  166.75  5023.2  166.46  5023.7  165.96  5032.7  166.46  5038.0  169.73
  5058.1  173.71  5068.1  172.80  5105.2  173.89  5178.5  172.29  5238.8  174.06
  5349.7  172.87  5539.9  172.37  5678.3  176.29  5796.0  181.34  5965.0  183.22
#Mann=5,-1,0
  4425.8    0.04       0  4909.2    0.12       0  5023.2    0.05       0
  5032.7    0.12       0  5349.7    0.04       0
Bank Sta=5023.2,5032.7
Exp/Cntr=0.3,0.1

Type RM Length L Ch R = 1,3857,524,524,524
BEGIN DESCRIPTION:
Mapping XS 98d02a5b
END DESCRIPTION:
XS GIS Cut Line= 3
      2498734.50     13587470.95      2498833.46     13586746.97
      2498656.44     13585679.66
#Sta/Elev= 30
  4297.6  198.38  4545.8  199.30  4687.1  198.01  4818.3  192.81  4848.6  189.05
  4854.4  187.30  4878.0  185.70  4926.6  178.77  4931.7  179.42  4939.5  178.14
  4959.6  171.43  4979.8  170.51  4989.9  166.17  5003.9  166.18  5005.4  164.42
  5005.9  163.92  5014.9  164.42  5025.7  166.95  5031.8  167.33  5040.4  172.47
  5050.2  172.39  5081.0  171.39  5131.7  172.88  5253.3  171.87  5304.0  170.29
  5321.3  170.95  5445.9  170.69  5557.4  177.11  5718.1  180.98  6110.2  183.82
#Mann=7,-1,0
  4297.6    0.04       0  4878.0    0.12       0  5005.4    0.05       0
  5014.9    0.12       0  5025.7    0.03       0  5050.2    0.12       0
  5321.3    0.04       0
Bank Sta=5005.4,5014.9
Exp/Cntr=0.3,0.1

Type RM Length L Ch R = 1,3333,431,431,431
BEGIN DESCRIPTION:
Mapping XS 0ce9e99a
END DESCRIPTION:
XS GIS Cut Line= 4
      2498968.90     13587554.22      2499338.67     13586762.59
      2499067.84     13585960.51      2498651.84     13585539.32
#Sta/Elev= 30
  3888.4  195.10  4284.9  193.33  4291.5  192.13  4411.3  189.84  4590.2  182.56
  4645.4  180.97  4726.4  176.11  4819.1  172.43  4907.4  170.82  4970.7  171.46
  4991.8  166.86  5003.1  163.35  5003.6  162.85  5012.6  163.35  5034.0  170.39
  5044.6  171.42  5102.2  170.02  5128.4  167.91  5206.4  169.38  5291.0  171.84
  5424.5  178.65  5551.2  181.98  5582.9  181.02  5621.7  181.46  5642.9  180.44
  5805.5  181.38  5883.4  180.57  5939.8  181.90  6088.4  182.55  6200.7  184.31
#Mann=5,-1,0
  3888.4    0.04       0  4590.2    0.12       0  5003.1    0.05       0
  5012.6    0.12       0  5206.4    0.04       0
Bank Sta=5003.1,5012.6
Exp/Cntr=0.3,0.1

Type RM Length L Ch R = 1,2902,0,0,0
BEGIN DESCRIPTION:
Mapping XS e40250d7
END DESCRIPTION:
XS GIS Cut Line= 4
      2498984.50     13587783.43      2499578.25     13586663.63
      2499015.75     13585392.80      2498460.17     13585179.91
#Sta/Elev= 30
  3307.4  194.30  3520.7  194.25  3758.4  192.41  3919.7  189.93  4133.7  184.34
  4222.4  181.02  4386.5  177.74  4628.1  169.51  4704.6  169.03  4863.2  170.48
  4879.6  162.86  4883.6  162.48  4884.1  161.98  4893.2  162.48  4901.5  166.67
  4917.2  170.17  4934.3  169.99  4940.4  167.30  4945.9  168.91  4987.0  167.73
  4992.5  168.85  5032.7  169.13  5095.9  171.90  5218.6  177.55  5288.4  178.75
  5622.7  176.63  5698.4  177.29  5977.0  180.09  6330.0  185.93  6559.6  190.10
#Mann=8,-1,0
  3307.4    0.04       0  4133.7    0.12       0  4883.6    0.05       0
  4893.2    0.12       0  5095.9    0.04       0  5622.7   0.013       0
  5698.4    0.04       0  6330.0   0.013       0
Bank Sta=4883.6,4893.2
Exp/Cntr=0.3,0.1

Chan Stop Cuts=-1