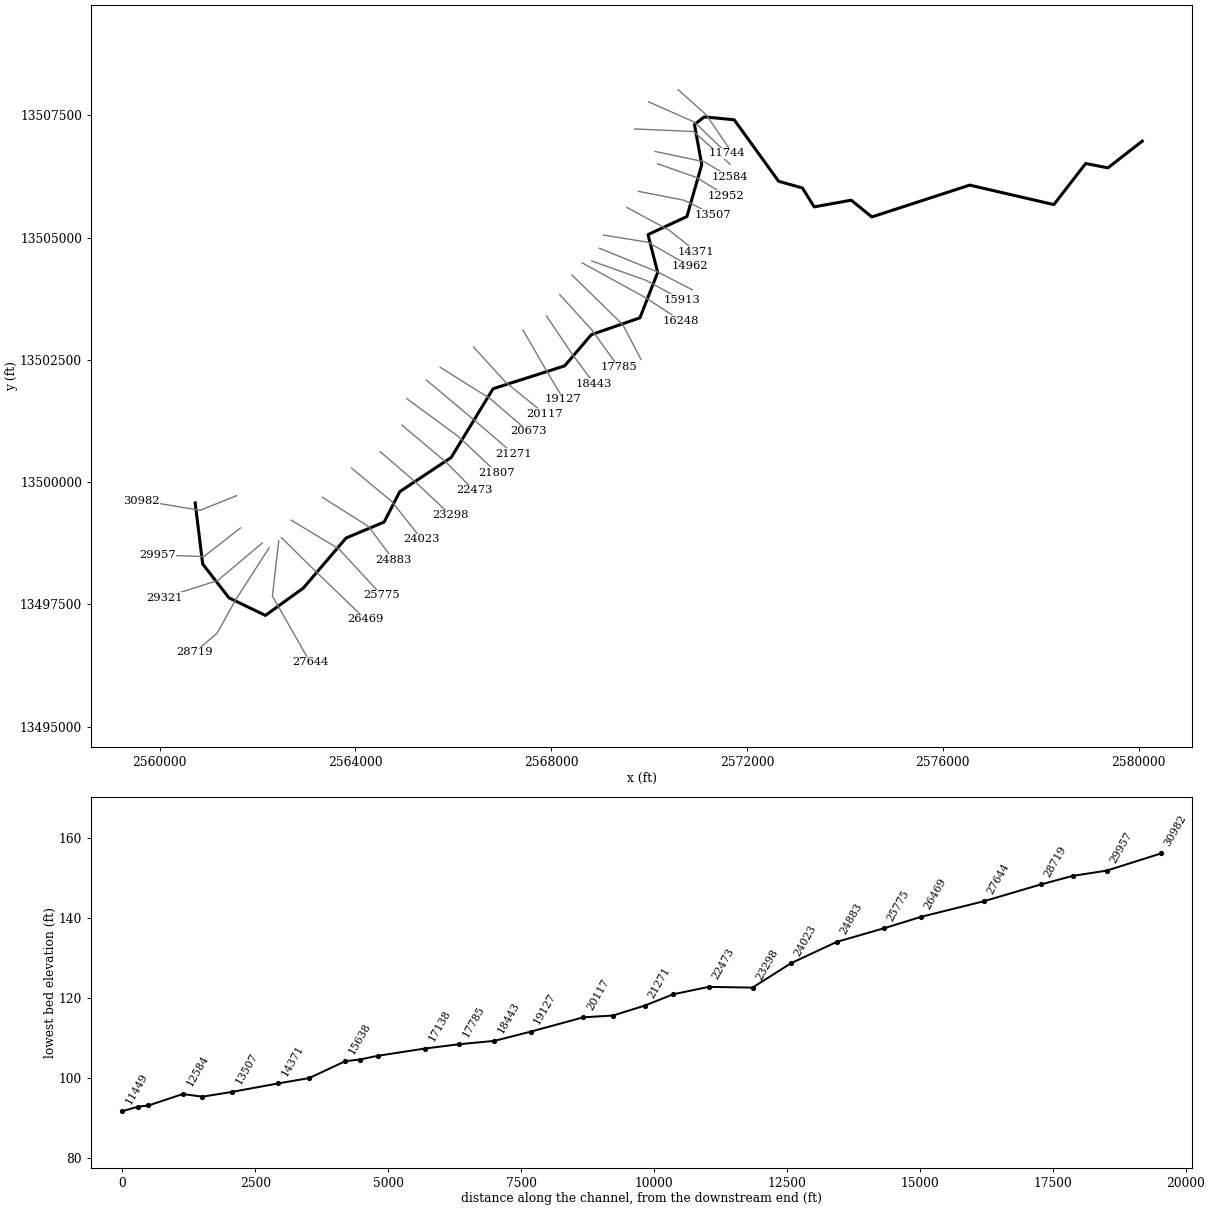
--- MISSION CREEK.prj (project) ---

Proj Title=MISSION CREEK Base Level Engineering
Current Plan=p01
Default Exp/Contr=0.3,0.1
English Units
Geom File=g01
Flow File=f01
Plan File=p01
Y Axis Title=Elevation
X Axis Title(PF)=Main Channel Distance
X Axis Title(XS)=Station
BEGIN DESCRIPTION:
MISSION CREEK
END DESCRIPTION:
DSS Export Rating Curves= 0
DSS Export Rating Curve Sorted= 0
DSS Export Volume Flow Curves= 0
DXF OffsetX= 0
DXF OffsetY= 0
DXF ScaleX= 1
DXF ScaleY= 10

--- MISSION CREEK.p01 (plan) ---

Plan Title=Multiple Run
Short Identifier=Multiple
Geom File=g01
Flow File=f01
Subcritical Flow
K Sum by GR= 0
Std Step Tol= 0.01
Critical Tol= 0.01
Num of Std Step Trials= 20
Max Error Tol= 0.3
Flow Tol Ratio= 0.001
Split Flow NTrial= 30
Split Flow Tol= 0.02
Split Flow Ratio= 0.02
Log Output Level= 0
Friction Slope Method= 1
Unsteady Friction Slope Method= 2
Unsteady Bridges Friction Slope Method= 1
Parabolic Critical Depth
Global Vel Dist=  1 , 1 , 1
Global Log Level= 0
CheckData=True
Encroach Param= -1, 0, 0, 0
BEGIN DESCRIPTION:
Multiple Run
END DESCRIPTION:

--- MISSION CREEK.f01 (steady flow) ---

Flow Title=Multiple
Number of Profiles=7
Profile Names=10-year,25-year,50-year,1pct_min,100-year,1pct_plu,500-year
River Rch & RM= MISSION CREEK,Reach-1,30982
     612     956    1255     797    1591    3174    2525
River Rch & RM= MISSION CREEK,Reach-1,29957
     722    1139    1506     962    1920    3831    3085
River Rch & RM= MISSION CREEK,Reach-1,27644
    1125    1822    2452    1594    3180    6344    5286
River Rch & RM= MISSION CREEK,Reach-1,21271
    1406    2304    3127    2047    4085    8150    6893
River Rch & RM= MISSION CREEK,Reach-1,20117
    1541    2535    3448    2261    4512    9002    7642
River Rch & RM= MISSION CREEK,Reach-1,16248
    1817    3009    4110    2706    5400   10774    9220
River Rch & RM= MISSION CREEK,Reach-1,10058
    2113    3510    4806    3170    6325   12619   10834
River Rch & RM= MISSION CREEK,Reach-1,6166
    2259    3764    5166    3414    6813   13593   11719
Boundary for River Rch & Prof#=MISSION CREEK,Reach-1,1
Up Type=0
Dn Type=3
Dn Slope=0.005
Boundary for River Rch & Prof#=MISSION CREEK,Reach-1,2
Up Type=0
Dn Type=3
Dn Slope=0.005
Boundary for River Rch & Prof#=MISSION CREEK,Reach-1,3
Up Type=0
Dn Type=3
Dn Slope=0.005
Boundary for River Rch & Prof#=MISSION CREEK,Reach-1,4
Up Type=0
Dn Type=3
Dn Slope=0.005
Boundary for River Rch & Prof#=MISSION CREEK,Reach-1,5
Up Type=0
Dn Type=3
Dn Slope=0.005
Boundary for River Rch & Prof#=MISSION CREEK,Reach-1,6
Up Type=0
Dn Type=3
Dn Slope=0.005
Boundary for River Rch & Prof#=MISSION CREEK,Reach-1,7
Up Type=0
Dn Type=3
Dn Slope=0.005

--- MISSION CREEK.g01 (geometry) ---

Geom Title=Existing Conditions
Program Version=4.10

River Reach=MISSION CREEK   ,Reach-1
Reach XY= 30
        2560725.       13499575.      2560878.45     13498326.25
       2561414.9     13497635.39      2562159.95     13497275.33
      2562934.97     13497835.13      2563807.95     13498858.52
        2564585.     13499185.07      2564904.35     13499805.58
      2565955.57     13500504.91      2566811.36     13501911.56
      2568273.54     13502378.54      2568818.66     13503016.98
      2569811.89     13503361.76      2570175.05     13504290.34
      2569976.62     13505063.19      2570772.38     13505433.46
      2571074.93     13506495.03      2570926.04     13507314.57
      2571126.55     13507471.25      2571738.24     13507411.39
      2572644.59     13506154.42      2573131.07     13506016.87
      2573372.55     13505630.47      2574128.41     13505767.23
      2574549.96      13505424.5      2576549.61     13506075.41
      2578269.15     13505677.06      2578918.83     13506517.14
       2579373.5     13506428.47        2580075.       13506975.

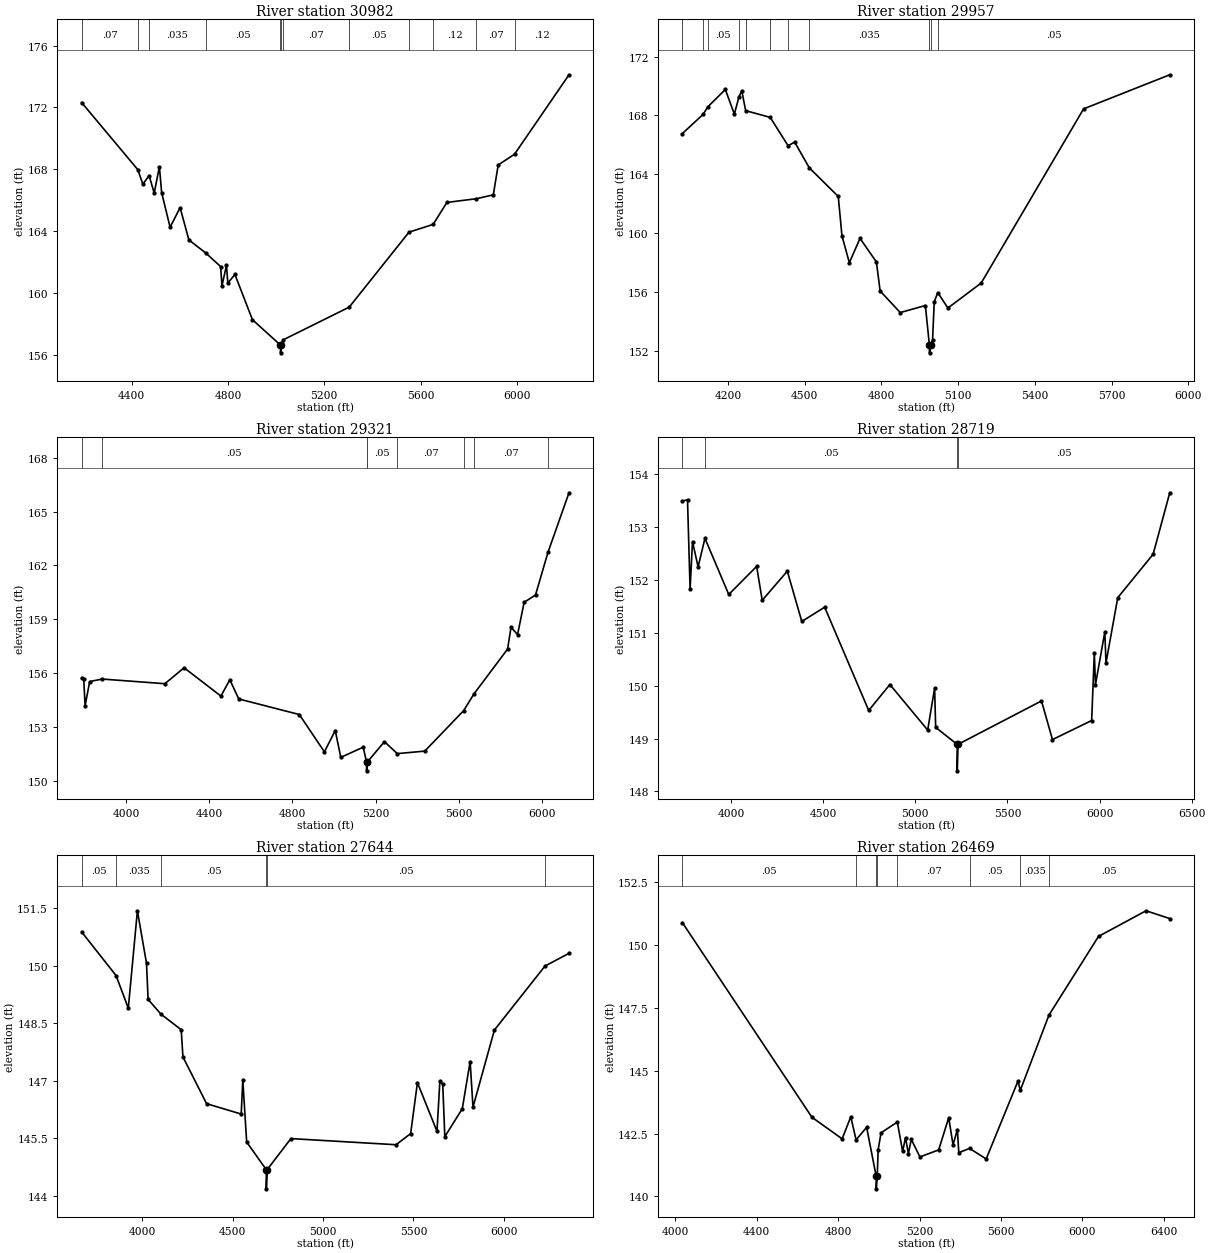
Type RM Length L Ch R = 1 ,30982   ,1025,1025,1025
BEGIN DESCRIPTION:
MISSION CREEK 57.0
END DESCRIPTION:
XS GIS Cut Line= 3
      2561574.98     13499724.99        2560825.       13499425.
        2559625.       13499625.
#Sta/Elev= 30
  4192.3  172.32  4425.5  167.99  4446.7  167.05  4472.9   167.6  4493.8  166.47
  4515.4  168.17  4524.8   166.5  4559.8  164.27  4601.5  165.53  4637.9  163.45
  4708.3   162.6  4769.8  161.73  4775.2  160.49  4794.1  161.81  4799.5  160.66
  4829.1  161.22  4901.8   158.3  5018.3  156.66  5018.5  156.16  5022.4  156.66
  5029.7     157  5303.8  159.11  5552.1  163.95  5652.2  164.45  5709.7  165.87
  5832.4  166.11  5902.3  166.36  5922.6  168.29  5990.3  168.98  6216.6  174.11
#Mann= 12 ,-1 , 0
  4192.3     .07       0  4425.5     .05       0  4472.9    .035       0
  4708.3     .05       0  5018.3     .05       0  5022.4     .05       0
  5029.7     .07       0  5303.8     .05       0  5552.1     .07       0
  5652.2     .12       0  5832.4     .07       0  5990.3     .12       0
Bank Sta=5018.3,5022.4
XS Rating Curve= 0 ,0
Exp/Cntr=0.3,0.1

Type RM Length L Ch R = 1 ,29957   ,636,636,636
BEGIN DESCRIPTION:
Mapping XS f9dfa1cd
END DESCRIPTION:
XS GIS Cut Line= 3
      2561650.75     13499064.73      2560902.06      13498478.8
      2559948.63      13498511.3
#Sta/Elev= 30
  4022.3  166.77  4103.8  168.08  4121.4  168.58  4190.3  169.77  4225.6  168.09
  4243.5  169.27  4254.5  169.69  4269.7  168.33  4365.7  167.87  4435.6  165.94
  4461.3  166.19  4518.3  164.44  4631.6  162.49    4646  159.82  4674.9  157.98
  4716.6  159.64  4780.8  158.03  4795.2  156.06  4873.9  154.59    4972  155.07
  4987.9  152.35  4988.2  151.85  4992.3  152.35  5000.1  152.72  5006.7  155.32
  5020.5  155.95  5060.1   154.9  5190.2   156.6  5590.4  168.45    5927  170.77
#Mann= 11 ,-1 , 0
  4022.3    .035       0  4103.8     .07       0  4121.4     .05       0
  4243.5    .035       0  4269.7     .07       0  4365.7    .035       0
  4435.6     .07       0  4518.3    .035       0  4987.9    .035       0
  4992.3    .035       0  5020.5     .05       0
Bank Sta=4987.9,4992.3
XS Rating Curve= 0 ,0
Exp/Cntr=0.3,0.1

Type RM Length L Ch R = 1 ,29321   ,602,602,602
BEGIN DESCRIPTION:
Mapping XS cade9f00
END DESCRIPTION:
XS GIS Cut Line= 3
      2562096.21     13498758.02      2561184.73      13497987.6
      2560089.45     13497640.58
#Sta/Elev= 30
    3787  155.72  3797.3  155.64  3803.8  154.17  3825.9  155.52  3885.9  155.66
  4187.3   155.4  4279.6  156.29  4456.5  154.71  4499.4  155.62  4542.2  154.55
  4833.4  153.68  4953.9   151.6    5006  152.79  5032.6  151.29  5140.4  151.86
  5156.3  151.04  5156.6  150.54  5160.8  151.04  5242.5  152.17    5304   151.5
  5436.3  151.64  5623.3   153.9    5672  154.82  5834.2  157.33  5850.8  158.55
  5882.3  158.14  5913.8  159.94  5968.6  160.35  6028.2  162.72  6129.4  166.05
#Mann= 8 ,-1 , 0
    3787    .035       0  3885.9     .05       0  5156.3     .05       0
  5160.8     .05       0    5304     .07       0  5623.3     .05       0
    5672     .07       0  6028.2    .035       0
Bank Sta=5156.3,5160.8
XS Rating Curve= 0 ,0
Exp/Cntr=0.3,0.1

Type RM Length L Ch R = 1 ,28719   ,1075,1075,1075
BEGIN DESCRIPTION:
Mapping XS 9f03d5e5
END DESCRIPTION:
XS GIS Cut Line= 4
      2562237.23     13498660.32      2561553.65     13497596.98
      2561173.88     13496913.38       2560719.1     13496523.57
#Sta/Elev= 30
  3735.9  153.48  3763.9  153.51  3777.9  151.82    3791  152.72  3821.4  152.24
  3858.5  152.78  3987.8  151.72  4139.1  152.25  4169.4  151.61  4305.5  152.16
  4384.2  151.21  4508.2  151.48  4747.3  149.53  4862.2  150.02  5067.3  149.16
    5105  149.95  5110.7  149.21  5227.4  148.89  5227.7  148.39    5232  148.89
    5685  149.71  5744.5  148.98  5957.3  149.34  5971.6  150.61  5978.1  150.02
  6028.6  151.01  6035.2  150.43  6098.9  151.66    6291  152.48    6381  153.64
#Mann= 4 ,-1 , 0
  3735.9    .035       0  3858.5     .05       0  5227.4     .05       0
    5232     .05       0
Bank Sta=5227.4,5232
XS Rating Curve= 0 ,0
Exp/Cntr=0.3,0.1

Type RM Length L Ch R = 1 ,27644   ,1175,1175,1175
BEGIN DESCRIPTION:
Mapping XS b61bab9a
END DESCRIPTION:
XS GIS Cut Line= 3
      2562432.56     13498801.39      2562302.35     13497672.93
      2563071.81     13496318.26
#Sta/Elev= 30
  3665.6  150.88  3856.3  149.74  3923.7  148.89    3974  151.43  4024.4  150.06
  4033.1  149.12  4105.1  148.73    4216  148.33  4225.7  147.62  4356.5   146.4
  4547.8  146.13  4556.6  147.02    4578   145.4  4686.3  144.68  4686.7  144.18
  4691.2  144.68  4822.5  145.49  5403.6  145.33  5484.3  145.62  5521.8  146.95
  5629.9  145.68  5645.8  146.99  5661.7  146.91  5673.2  145.54  5769.8  146.27
  5813.1   147.5  5828.9  146.31  5947.2  148.32    6227  149.99  6359.5  150.32
#Mann= 6 ,-1 , 0
  3665.6     .05       0  3856.3    .035       0  4105.1     .05       0
  4686.3     .05       0  4691.2     .05       0    6227    .035       0
Bank Sta=4686.3,4691.2
XS Rating Curve= 0 ,0
Exp/Cntr=0.3,0.1

Type RM Length L Ch R = 1 ,26469   ,694,694,694
BEGIN DESCRIPTION:
Mapping XS 6fadafb1
END DESCRIPTION:
XS GIS Cut Line= 3
      2562486.82      13498866.5      2563213.81     13498150.36
      2564200.61      13497196.1
#Sta/Elev= 30
  4035.4   150.9  4671.6  143.15    4820  142.29  4862.5  143.17  4888.4  142.25
  4940.3  142.75  4987.2   140.8  4987.6   140.3  4992.3   140.8  4996.9  141.86
    5011  142.53    5091  142.96    5117  141.79  5131.2  142.34  5145.3   141.7
  5159.5  142.27  5201.9  141.57    5294  141.85  5343.4  143.13  5364.5  142.05
  5385.8  142.66  5392.8  141.74  5445.8  141.91  5527.3  141.49    5683  144.58
  5695.2  144.23  5835.7  147.22  6078.9  150.35  6312.2  151.37  6428.6  151.06
#Mann= 8 ,-1 , 0
  4035.4     .05       0  4888.4     .12       0  4987.2     .05       0
  4992.3     .12       0    5091     .07       0  5445.8     .05       0
  5695.2    .035       0  5835.7     .05       0
Bank Sta=4987.2,4992.3
XS Rating Curve= 0 ,0
Exp/Cntr=0.3,0.1

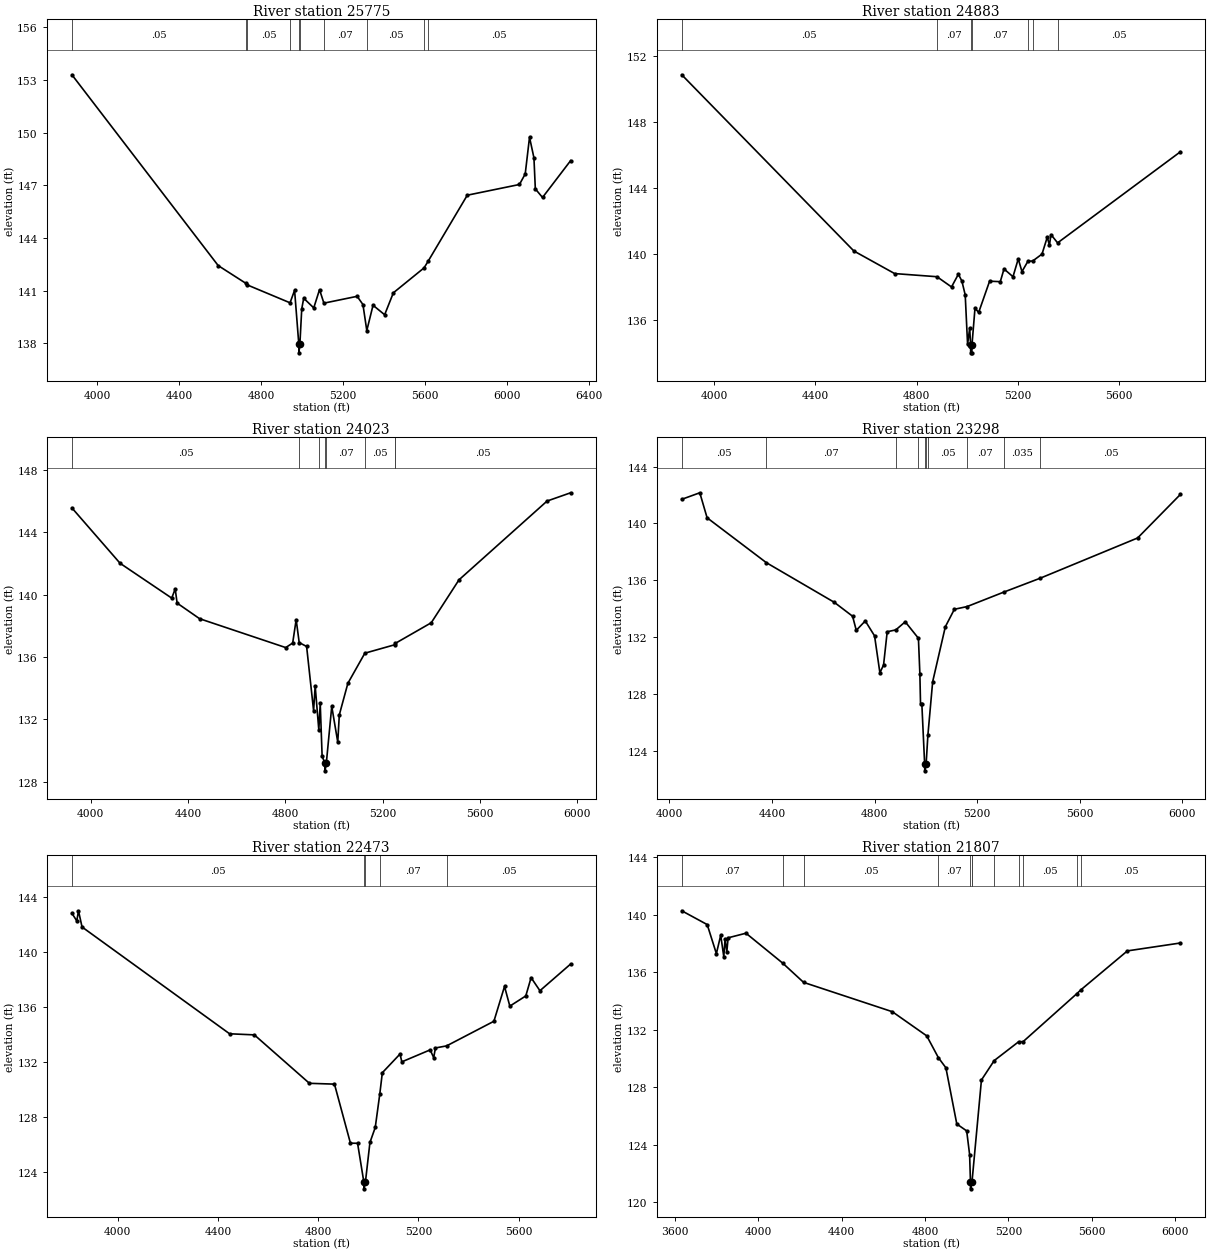
Type RM Length L Ch R = 1 ,25775   ,892,892,892
BEGIN DESCRIPTION:
Mapping XS bd12a922
END DESCRIPTION:
XS GIS Cut Line= 3
      2562682.12     13499224.59      2563658.69     13498638.64
      2564537.56     13497683.82
#Sta/Elev= 30
  3875.5  153.29  4590.2  142.42    4724  141.42    4730  141.33  4941.2   140.3
  4963.4  141.01    4984  137.95  4984.4  137.45  4989.3  137.95  4998.4  139.96
    5008  140.56    5057  140.01  5085.3  141.05  5106.6  140.28    5269  140.67
  5297.4   140.2  5316.2  138.72  5346.7  140.16  5403.4  139.62    5446  140.87
    5596  142.29  5615.4  142.66  5807.2  146.43  6061.9  147.04  6090.2  147.64
  6111.2  149.73  6132.8  148.56  6139.6  146.79  6174.7   146.3  6312.1   148.4
#Mann= 10 ,-1 , 0
  3875.5     .05       0    4724     .12       0    4730     .05       0
  4941.2     .12       0    4984     .05       0  4989.3     .12       0
  5106.6     .07       0  5316.2     .05       0    5596    .035       0
  5615.4     .05       0
Bank Sta=4984,4989.3
XS Rating Curve= 0 ,0
Exp/Cntr=0.3,0.1

Type RM Length L Ch R = 1 ,24883   ,860,860,860
BEGIN DESCRIPTION:
Mapping XS 77bde514
END DESCRIPTION:
XS GIS Cut Line= 3
      2563322.33     13499691.15      2564266.33     13499094.37
      2564776.32     13498410.77
#Sta/Elev= 30
  3871.9  150.87  4551.5   140.2  4712.7  138.83  4879.9  138.64  4937.3  138.02
  4964.4  138.79  4978.2  138.38  4991.4  137.54  5000.8  134.54  5009.1  135.53
  5012.6  134.53    5013  134.03  5017.7  134.03  5018.2  134.53    5030  136.73
  5044.6  136.48  5087.7  138.37    5130  138.34  5144.6  139.11  5180.1  138.64
  5200.9  139.72  5215.5  138.95  5239.2  139.58  5257.7  139.59  5294.7  140.01
  5315.6  141.04  5323.9  140.54  5330.2  141.19  5356.3  140.69  5841.6  146.21
#Mann= 7 ,-1 , 0
  3871.9     .05       0  4879.9     .07       0  5012.6     .05       0
  5018.2     .07       0  5239.2     .05       0  5257.7    .035       0
  5356.3     .05       0
Bank Sta=5012.6,5018.2
XS Rating Curve= 0 ,0
Exp/Cntr=0.3,0.1

Type RM Length L Ch R = 1 ,24023   ,725,725,725
BEGIN DESCRIPTION:
Mapping XS 6185c52a
END DESCRIPTION:
XS GIS Cut Line= 3
       2563919.1     13500287.95      2564743.76     13499604.36
      2565350.69     13498834.85
#Sta/Elev= 30
  3922.2  145.55  4120.4     142  4332.7  139.77    4347  140.36  4354.9  139.45
  4447.3  138.45  4801.5   136.6  4830.2  136.89  4844.5  138.39    4857  136.92
  4887.5  136.67  4916.2  132.56  4922.7  134.14  4937.7  131.32  4943.5  133.02
  4951.3  129.63  4962.7   129.2  4963.2   128.7  4968.6   129.2  4990.9  132.83
  5015.6  130.54    5022  132.29  5057.2  134.31    5127  136.24  5249.8  136.78
  5252.4  136.87  5400.1  138.19  5514.2  140.94  5876.5  145.99  5973.4  146.52
#Mann= 8 ,-1 , 0
  3922.2     .05       0    4857     .12       0  4937.7     .07       0
  4962.7     .05       0  4968.6     .07       0    5127     .05       0
  5249.8    .035       0  5252.4     .05       0
Bank Sta=4962.7,4968.6
XS Rating Curve= 0 ,0
Exp/Cntr=0.3,0.1

Type RM Length L Ch R = 1 ,23298   ,825,825,825
BEGIN DESCRIPTION:
Mapping XS 5ff2c972
END DESCRIPTION:
XS GIS Cut Line= 3
      2564505.02     13500624.34      2565210.34     13500016.68
      2565948.16     13499322.26
#Sta/Elev= 30
  4048.5   141.7  4118.8  142.16  4147.3   140.4  4378.4  137.24  4643.2  134.45
  4714.5  133.47  4728.8  132.48  4763.9  133.14  4800.1  132.09  4820.9  129.49
  4835.2  130.04  4849.4  132.38    4883  132.51  4919.7  133.08  4971.1  131.92
  4976.7  129.44  4979.3  127.31  4984.4  127.31  4995.3  123.09  4995.8  122.59
  5001.2  123.09    5008   125.1  5026.6  128.86    5076  132.73  5111.2  133.96
  5160.6  134.15    5304  135.17  5446.2  136.15  5825.7  138.98  5992.7  142.05
#Mann= 10 ,-1 , 0
  4048.5     .05       0  4378.4     .07       0    4883     .05       0
  4971.1     .07       0  4995.3     .05       0  5001.2     .07       0
    5008     .05       0  5160.6     .07       0    5304    .035       0
  5446.2     .05       0
Bank Sta=4995.3,5001.2
XS Rating Curve= 0 ,0
Exp/Cntr=0.3,0.1

Type RM Length L Ch R = 1 ,22473   ,666,666,666
BEGIN DESCRIPTION:
Mapping XS 7e7f83c0
END DESCRIPTION:
XS GIS Cut Line= 3
      2564949.95     13501166.83      2565839.68     13500418.16
      2566425.58     13499832.25
#Sta/Elev= 30
  3816.7   142.8  3836.3  142.24  3842.9  142.98  3857.2   141.8  4446.3  134.04
  4545.2  133.96    4765  130.44  4865.1  130.38  4928.8  126.09  4957.4  126.08
  4982.3  123.27  4982.8  122.77  4988.7  123.27  5006.7  126.14  5027.9  127.23
  5046.1  129.67  5056.2  131.21  5126.9  132.57    5134     132  5247.1  132.87
  5261.3  132.31  5268.3  133.01  5312.8  133.16  5501.7  134.95  5544.1  137.48
  5565.3  136.05    5629  136.79  5650.2  138.12  5685.5  137.17  5808.1  139.11
#Mann= 5 ,-1 , 0
  3816.7     .05       0  4982.3     .05       0  4988.7     .05       0
  5046.1     .07       0  5312.8     .05       0
Bank Sta=4982.3,4988.7
XS Rating Curve= 0 ,0
Exp/Cntr=0.3,0.1

Type RM Length L Ch R = 1 ,21807   ,536,536,536
BEGIN DESCRIPTION:
Mapping XS 643fc3ea
END DESCRIPTION:
XS GIS Cut Line= 3
      2565047.58     13501709.39      2566110.94     13500928.14
       2566891.1     13500191.33
#Sta/Elev= 30
  3633.1  140.26  3755.2   139.3  3799.2  137.28    3820  138.56  3834.7  137.07
  3840.9  138.29  3849.3   137.4  3855.5  138.38  3941.2   138.7  4117.2  136.62
  4217.6  135.28  4643.3  133.24  4808.4  131.56  4864.4  130.04  4900.3  129.34
  4952.6  125.43    5000  124.95  5014.1   123.3  5018.1  121.42  5018.6  120.92
  5024.6  121.42  5025.8  121.45  5070.8  128.49    5132  129.84  5249.2  131.15
  5270.9  131.16  5528.1  134.49  5548.6  134.77    5771  137.47  6025.7  138.02
#Mann= 12 ,-1 , 0
  3633.1     .07       0  4117.2     .12       0  4217.6     .05       0
  4864.4     .07       0  5018.1     .05       0  5024.6     .07       0
  5025.8     .12       0    5132     .05       0  5249.2     .07       0
  5270.9     .05       0  5528.1    .035       0  5548.6     .05       0
Bank Sta=5018.1,5024.6
XS Rating Curve= 0 ,0
Exp/Cntr=0.3,0.1

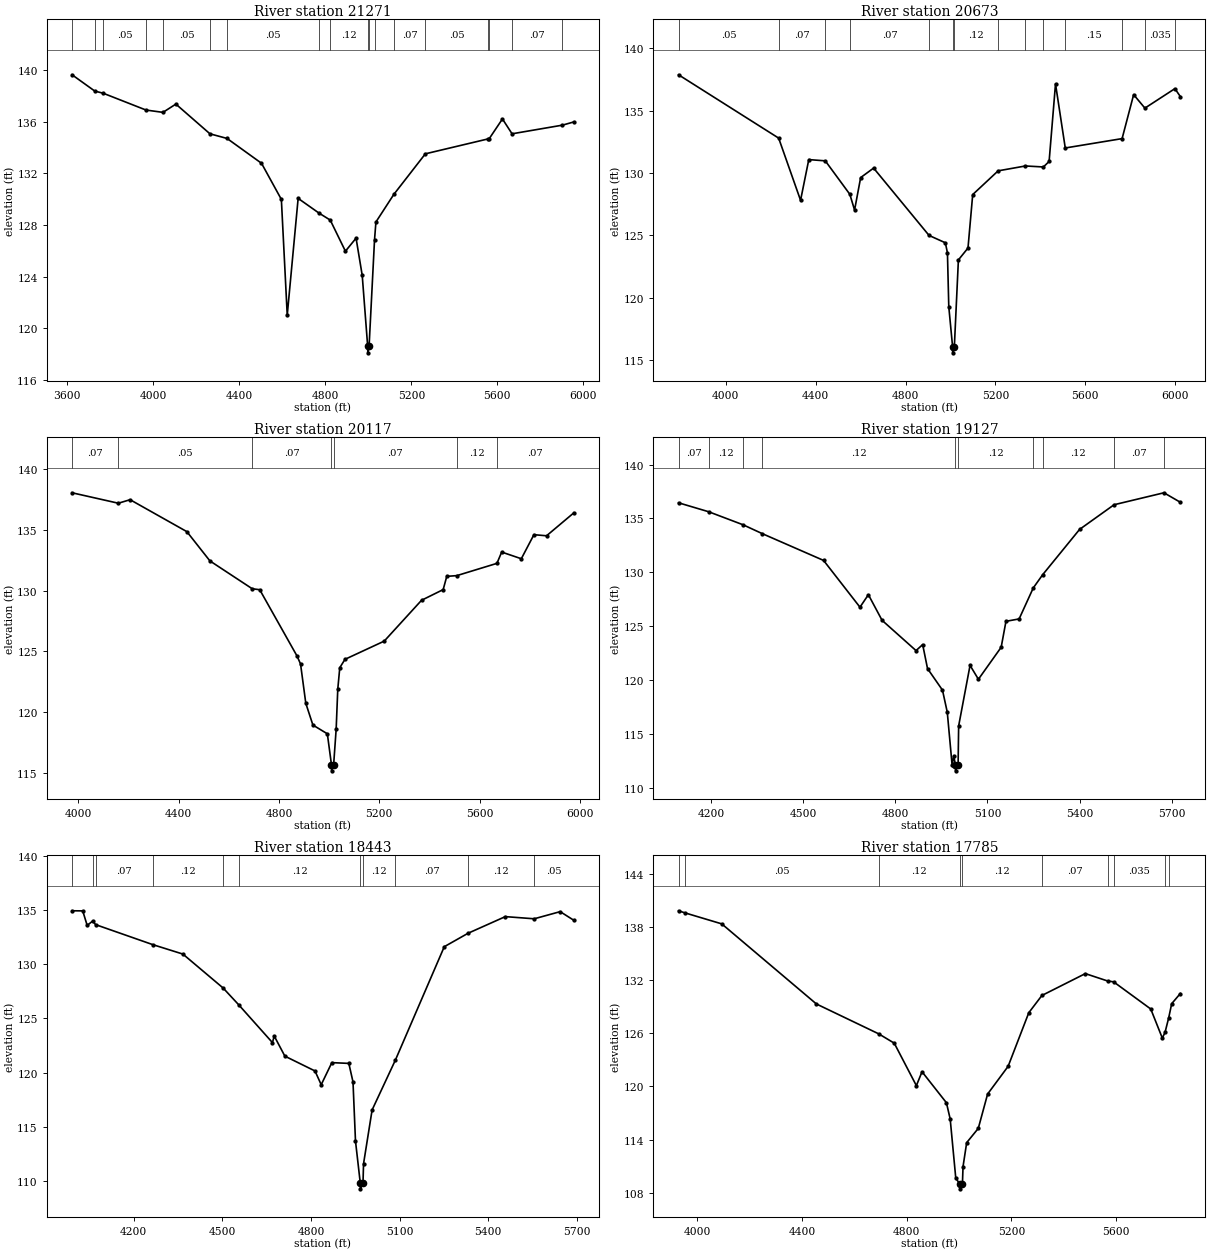
Type RM Length L Ch R = 1 ,21271   ,598,598,598
BEGIN DESCRIPTION:
Mapping XS 2d2fe8a8
END DESCRIPTION:
XS GIS Cut Line= 3
      2565449.03     13502089.18      2566534.12     13501177.71
       2567228.6     13500580.89
#Sta/Elev= 30
  3622.8  139.62  3728.2  138.36  3767.6  138.19  3966.5  136.89  4045.3  136.71
  4105.4  137.35  4263.7  135.05  4343.3  134.69  4503.4  132.77  4595.8  129.97
  4623.1  121.01  4673.8  130.05  4770.8  128.91    4823  128.37  4893.6  125.96
  4943.1  126.97  4971.7  124.09  4997.1  118.59  4997.6  118.09  5003.6  118.59
  5028.9  126.84  5035.4  128.22  5118.7  130.36  5265.2   133.5  5558.2  134.66
    5560  134.62  5623.6   136.2  5668.3  135.05  5902.5  135.72  5955.6  135.97
#Mann= 18 ,-1 , 0
  3622.8     .05       0  3728.2     .07       0  3767.6     .05       0
  3966.5     .07       0  4045.3     .05       0  4263.7     .07       0
  4343.3     .05       0  4770.8     .07       0    4823     .12       0
  4997.1     .05       0  5003.6     .12       0  5028.9     .05       0
  5118.7     .07       0  5265.2     .05       0  5558.2    .035       0
    5560     .05       0  5668.3     .07       0  5902.5     .05       0
Bank Sta=4997.1,5003.6
XS Rating Curve= 0 ,0
Exp/Cntr=0.3,0.1

Type RM Length L Ch R = 1 ,20673   ,556,556,556
BEGIN DESCRIPTION:
Mapping XS 99bdbdfe
END DESCRIPTION:
XS GIS Cut Line= 3
      2565731.15     13502349.59      2566751.14     13501709.39
      2567531.22     13501037.65
#Sta/Elev= 30
  3789.6  137.86  4235.3  132.79  4332.8  127.81  4369.4  131.07  4442.9  130.97
  4552.2  128.29  4573.2  127.03  4600.3  129.63    4658  130.39  4904.7     125
  4977.3  124.41  4986.6  123.61  4992.6  119.29  5009.5   116.1    5010   115.6
  5017.4   116.1  5035.4  123.04  5078.1  123.99  5099.1  128.27  5212.3  130.17
  5333.9  130.56  5413.7  130.48  5439.2  130.92  5467.7  137.13  5511.1     132
  5764.1  132.75  5815.5  136.27  5865.6  135.19  5999.1  136.75  6023.3  136.12
#Mann= 14 ,-1 , 0
  3789.6     .05       0  4235.3     .07       0  4442.9     .05       0
  4552.2     .07       0  4904.7     .12       0  5009.5     .05       0
  5017.4     .12       0  5212.3     .07       0  5333.9     .12       0
  5413.7     .07       0  5511.1     .15       0  5764.1     .05       0
  5865.6    .035       0  5999.1     .05       0
Bank Sta=5009.5,5017.4
XS Rating Curve= 0 ,0
Exp/Cntr=0.3,0.1

Type RM Length L Ch R = 1 ,20117   ,990,990,990
BEGIN DESCRIPTION:
Mapping XS 1220858e
END DESCRIPTION:
XS GIS Cut Line= 3
      2566414.78     13502761.89      2567065.81     13502045.76
      2567868.73     13501394.74
#Sta/Elev= 30
  3974.8  138.05  4159.4  137.19  4206.3  137.48  4432.7  134.85  4524.7  132.44
  4693.4  130.15  4723.3  130.07  4871.9  124.62  4886.1  123.96  4907.1  120.72
  4935.4  118.93    4993  118.21  5009.5  115.66    5010  115.16  5018.1  115.66
  5028.2  118.59  5034.6  121.88  5042.6  123.65  5063.4  124.34    5220  125.84
  5368.7   129.2    5455  130.08  5469.4  131.17  5509.4  131.23  5669.5  132.24
  5688.4  133.17  5766.7  132.62    5817   134.6  5867.4  134.51  5976.3   136.4
#Mann= 7 ,-1 , 0
  3974.8     .07       0  4159.4     .05       0  4693.4     .07       0
  5009.5     .05       0  5018.1     .07       0  5509.4     .12       0
  5669.5     .07       0
Bank Sta=5009.5,5018.1
XS Rating Curve= 0 ,0
Exp/Cntr=0.3,0.1

Type RM Length L Ch R = 1 ,19127   ,684,684,684
BEGIN DESCRIPTION:
Mapping XS a9bcd8d8
END DESCRIPTION:
XS GIS Cut Line= 3
      2567423.85     13503109.17      2567836.21     13502392.98
       2568248.1     13501699.27
#Sta/Elev= 30
  4094.6  136.45  4192.6  135.62  4304.6  134.41  4367.7  133.58  4566.7   131.1
  4685.1  126.76  4712.5  127.92  4757.1  125.54  4867.6  122.73  4889.2  123.29
    4905  121.06  4953.7  119.06  4969.3  117.01  4984.9  112.14  4990.7  112.98
  4995.6  112.07  4996.1  111.57  5004.5  112.07  5006.3  115.74  5043.4  121.36
  5070.6  120.07  5144.7  123.04  5160.3  125.45  5203.1  125.67  5249.2  128.55
  5279.9  129.78  5399.9  133.98  5512.2  136.27  5674.5  137.38  5727.8   136.5
#Mann= 10 ,-1 , 0
  4094.6     .07       0  4192.6     .12       0  4304.6     .07       0
  4367.7     .12       0  4995.6     .05       0  5004.5     .12       0
  5249.2     .07       0  5279.9     .12       0  5512.2     .07       0
  5674.5    .035       0
Bank Sta=4995.6,5004.5
XS Rating Curve= 0 ,0
Exp/Cntr=0.3,0.1

Type RM Length L Ch R = 1 ,18443   ,658,658,658
BEGIN DESCRIPTION:
Mapping XS 1339a2ac
END DESCRIPTION:
XS GIS Cut Line= 3
      2567901.32     13503402.08      2568411.29     13502642.55
      2568877.88      13502013.2
#Sta/Elev= 30
  3991.3  134.95  4027.4  134.94  4042.4   133.6  4061.1     134    4071  133.67
  4264.7  131.82  4366.4  130.95  4502.7  127.81  4555.4  126.26  4669.5  122.77
  4675.5  123.38  4711.5  121.52  4813.5  120.15  4834.5  118.88  4870.5  120.92
    4928  120.85  4942.1  119.14  4950.5  113.68  4966.9  109.76  4967.4  109.26
  4975.9  109.76  4977.8  111.58  5006.8  116.55  5085.8  121.17    5251  131.63
  5331.3  132.87  5457.6  134.41  5555.4  134.21  5643.3  134.87  5689.6  134.07
#Mann= 11 ,-1 , 0
  3991.3     .12       0  4061.1     .05       0    4071     .07       0
  4264.7     .12       0  4502.7     .07       0  4555.4     .12       0
  4966.9     .05       0  4975.9     .12       0  5085.8     .07       0
  5331.3     .12       0  5555.4     .05       0
Bank Sta=4966.9,4975.9
XS Rating Curve= 0 ,0
Exp/Cntr=0.3,0.1

Type RM Length L Ch R = 1 ,17785   ,647,647,647
BEGIN DESCRIPTION:
Mapping XS db74f427
END DESCRIPTION:
XS GIS Cut Line= 3
      2568172.59     13503836.12      2568834.47     13503109.13
      2569376.85      13502349.8
#Sta/Elev= 30
  3928.5  139.85  3952.3  139.62  4093.6  138.37    4455  129.32  4693.2  125.94
  4752.3  124.89  4836.8  120.09  4858.4  121.66  4951.5  118.16  4965.9  116.33
  4987.2  109.65  5003.4  108.93  5003.9  108.43  5012.6  108.93    5015  110.95
  5028.9  113.65  5073.2  115.26  5108.8  119.14  5187.1  122.27  5266.1  128.33
  5316.2  130.28    5482  132.75  5566.8  131.92    5590  131.82  5731.9  128.75
  5776.1  125.46  5786.5  126.12  5800.6  127.78  5811.8  129.35  5844.8   130.5
#Mann= 10 ,-1 , 0
  3928.5     .07       0  3952.3     .05       0  4693.2     .12       0
  5003.4     .05       0  5012.6     .12       0  5316.2     .07       0
  5566.8     .12       0    5590    .035       0  5786.5     .07       0
  5800.6     .12       0
Bank Sta=5003.4,5012.6
XS Rating Curve= 0 ,0
Exp/Cntr=0.3,0.1

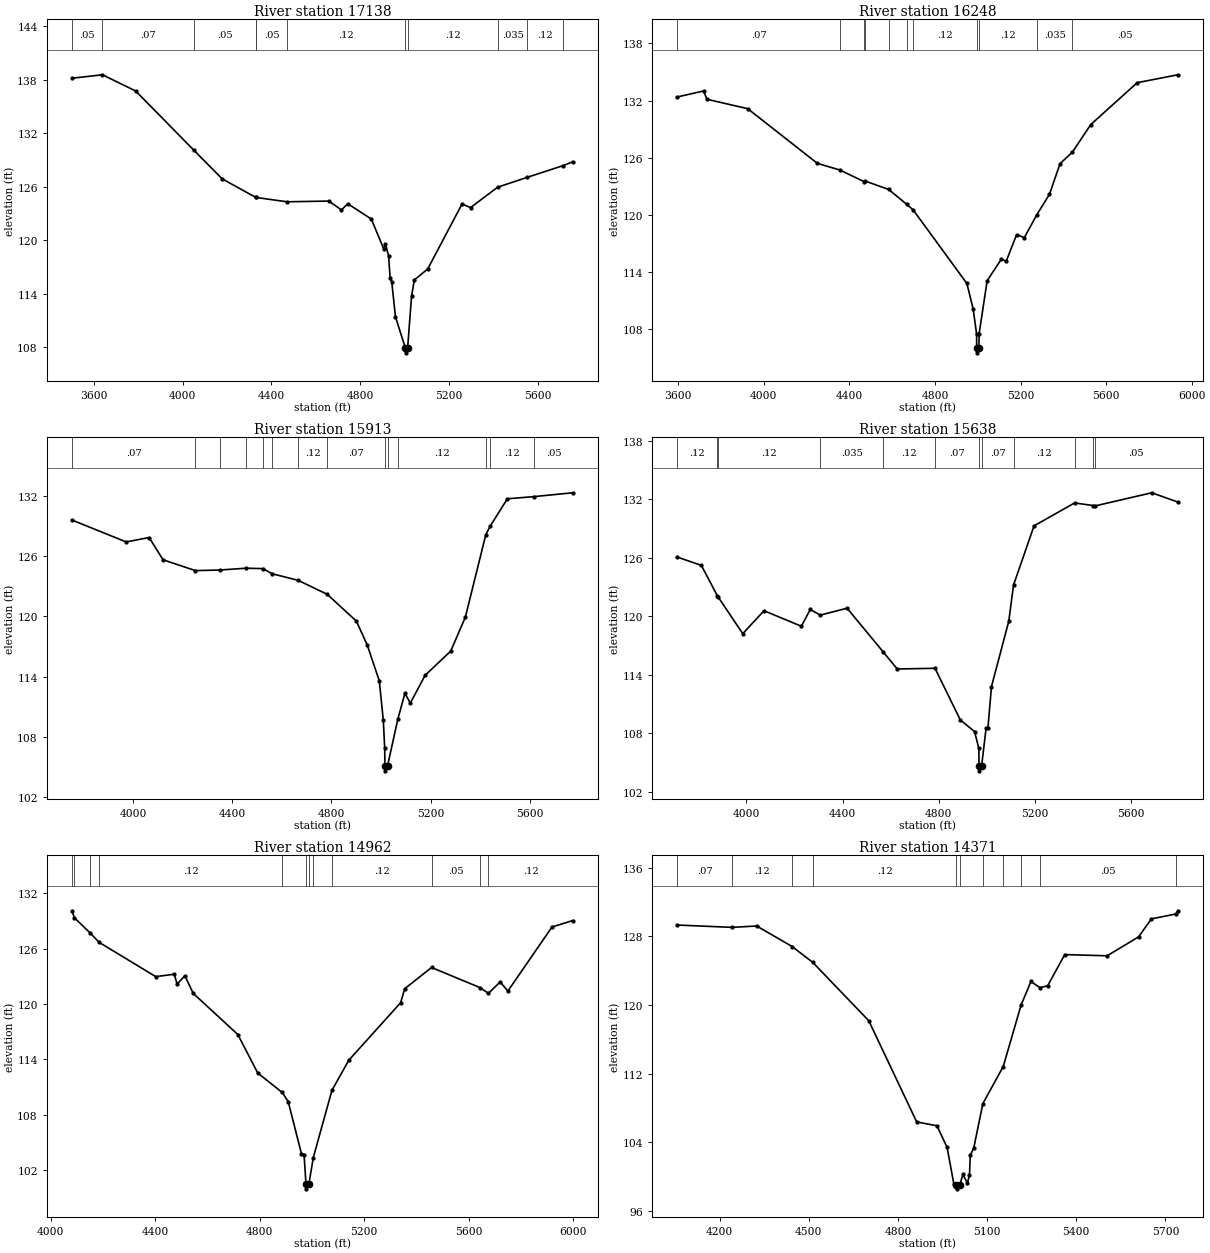
Type RM Length L Ch R = 1 ,17138   ,890,890,890
BEGIN DESCRIPTION:
Mapping XS fa0a9996
END DESCRIPTION:
XS GIS Cut Line= 3
      2568422.18     13504237.57      2569463.81     13503217.64
      2569832.74     13502512.33
#Sta/Elev= 30
  3502.4  138.18  3639.5  138.57    3789  136.75  4049.4  130.14  4178.1  126.89
  4329.1  124.81  4329.7   124.8  4470.6  124.31  4658.8  124.39  4715.4  123.39
  4743.7  124.09  4849.9  122.37  4906.3  118.98  4913.4   119.6  4927.6  118.21
  4934.6   115.7  4941.7  115.32  4958.5   111.4  5003.6  107.85  5004.1  107.35
  5013.1  107.85  5030.9  113.68  5043.1  115.52  5103.7  116.77  5258.2  124.06
  5296.7  123.66  5418.6  125.95  5552.2  127.06  5714.4  128.38  5756.2   128.8
#Mann= 11 ,-1 , 0
  3502.4     .05       0  3639.5     .07       0  4049.4     .05       0
  4329.1     .07       0  4329.7     .05       0  4470.6     .12       0
  5003.6     .05       0  5013.1     .12       0  5418.6    .035       0
  5552.2     .12       0  5714.4     .07       0
Bank Sta=5003.6,5013.1
XS Rating Curve= 0 ,0
Exp/Cntr=0.3,0.1

Type RM Length L Ch R = 1 ,16248   ,335,335,335
BEGIN DESCRIPTION:
Mapping XS 13d92709
END DESCRIPTION:
XS GIS Cut Line= 3
      2568628.33     13504487.15      2569930.39     13503771.02
      2570646.51     13503304.46
#Sta/Elev= 30
  3594.9  132.38  3717.9  133.01    3734  132.14  3924.4  131.15  4250.2  125.41
  4355.7  124.71  4469.7  123.48  4473.1  123.56  4583.6  122.67  4667.8  121.11
  4697.5  120.54  4949.2   112.8  4978.5  110.13  4994.6  107.49    4995  106.02
  4995.5  105.52  5005.6  106.02  5006.3  107.52  5043.9  113.08  5110.3  115.36
    5133  115.13  5181.9  117.94  5217.7  117.61  5276.4  120.02  5335.2  122.16
  5384.8  125.38  5442.8   126.6  5528.2  129.48  5745.5  133.88  5935.6  134.71
#Mann= 11 ,-1 , 0
  3594.9     .07       0  4355.7     .05       0  4469.7     .12       0
  4473.1     .05       0  4583.6     .07       0  4667.8     .05       0
  4697.5     .12       0    4995     .05       0  5005.6     .12       0
  5276.4    .035       0  5442.8     .05       0
Bank Sta=4995,5005.6
XS Rating Curve= 0 ,0
Exp/Cntr=0.3,0.1

Type RM Length L Ch R = 1 ,15913   ,275,275,275
BEGIN DESCRIPTION:
Mapping XS 4f37ed0d
END DESCRIPTION:
XS GIS Cut Line= 3
      2568825.79     13504524.06      2569945.58     13504124.76
      2570674.75     13503725.45
#Sta/Elev= 30
  3753.1   129.6  3971.7  127.42  4064.2  127.86  4120.5  125.64    4251  124.56
  4349.6  124.62    4455   124.8  4523.3  124.76  4560.4  124.25  4665.8  123.59
  4782.7   122.2  4900.4  119.53  4944.5  117.14    4993  113.57  5009.2  109.66
  5014.9  106.83  5015.7   105.1  5016.2   104.6  5026.4   105.1  5067.8  109.75
  5096.4  112.33  5118.2  111.35  5177.9  114.12  5281.3  116.54  5340.3  119.92
  5422.8  128.14  5440.6     129  5509.8  131.72  5618.2  131.94  5773.3  132.32
#Mann= 14 ,-1 , 0
  3753.1     .07       0    4251     .05       0  4349.6     .07       0
    4455     .05       0  4523.3     .12       0  4560.4     .05       0
  4665.8     .12       0  4782.7     .07       0  5015.7     .05       0
  5026.4     .07       0  5067.8     .12       0  5422.8    .035       0
  5440.6     .12       0  5618.2     .05       0
Bank Sta=5015.7,5026.4
XS Rating Curve= 0 ,0
Exp/Cntr=0.3,0.1

Type RM Length L Ch R = 1 ,15638   ,676,676,676
BEGIN DESCRIPTION:
Mapping XS ed9cf0d6
END DESCRIPTION:
XS GIS Cut Line= 3
      2568982.02     13504784.48      2570179.96     13504298.37
      2570881.54     13503934.58
#Sta/Elev= 30
    3712  126.08  3812.3  125.23  3878.9  122.12  3881.7  122.01  3984.7  118.23
  4073.2  120.58  4228.5  118.99  4265.6  120.71  4307.2  120.13  4418.7  120.84
    4570  116.33  4627.6  114.61  4784.6  114.68  4890.1  109.38  4949.1   108.2
  4967.1  106.46  4967.8  104.67  4968.3  104.17  4978.5  104.67  4997.3  108.56
  5004.8  108.57  5019.6  112.81  5091.6  119.51  5111.3  123.21  5196.6  129.28
  5365.6  131.63  5443.1  131.36  5448.4  131.31  5686.4  132.67  5795.1  131.72
#Mann= 12 ,-1 , 0
    3712     .12       0  3878.9     .07       0  3881.7     .12       0
  4307.2    .035       0    4570     .12       0  4784.6     .07       0
  4967.8     .05       0  4978.5     .07       0  5111.3     .12       0
  5365.6     .05       0  5443.1     .07       0  5448.4     .05       0
Bank Sta=4967.8,4978.5
XS Rating Curve= 0 ,0
Exp/Cntr=0.3,0.1

Type RM Length L Ch R = 1 ,14962   ,591,591,591
BEGIN DESCRIPTION:
Mapping XS 4db2922f
END DESCRIPTION:
XS GIS Cut Line= 3
      2569068.87     13505053.57       2569980.3     13504906.01
      2570839.64     13504411.23
#Sta/Elev= 30
  4082.1  130.11  4091.3  129.35  4150.9  127.72  4185.7  126.69  4402.3  122.97
  4473.3  123.23  4484.2  122.16  4513.8  123.07  4545.8  121.15  4716.4  116.69
  4792.5  112.52    4886  110.41  4908.9  109.43  4959.5  103.79  4969.6  103.68
  4977.1  100.46  4977.6   99.96  4988.1  100.46  5004.9  103.34  5076.3  110.64
  5140.6   113.9  5338.9  120.14  5354.7  121.66  5457.3  123.96  5641.7  121.79
  5674.8  121.16  5719.7  122.39  5749.3  121.41    5918  128.35    5997  129.05
#Mann= 12 ,-1 , 0
  4082.1     .07       0  4091.3     .12       0  4150.9     .05       0
  4185.7     .12       0    4886    .035       0  4977.1    .035       0
  4988.1    .035       0  5004.9     .07       0  5076.3     .12       0
  5457.3     .05       0  5641.7     .07       0  5674.8     .12       0
Bank Sta=4977.1,4988.1
XS Rating Curve= 0 ,0
Exp/Cntr=0.3,0.1

Type RM Length L Ch R = 1 ,14371   ,864,864,864
BEGIN DESCRIPTION:
Mapping XS 23b9e041
END DESCRIPTION:
XS GIS Cut Line= 3
      2569546.26     13505617.82      2570414.33     13505149.06
      2570960.63     13504715.49
#Sta/Elev= 30
  4057.7  129.31  4242.1  129.04    4325   129.2  4444.1  126.81  4513.7  124.96
    4702  118.17  4863.2  106.39  4931.4  105.94  4965.5  103.42  4988.2   99.16
  4997.1    99.1  4997.6    98.6  5008.3    99.1  5018.9  100.28  5033.7   99.26
  5040.8  100.21  5043.3  102.49  5055.2  103.36  5085.7  108.52  5154.3  112.84
  5214.1  119.97  5247.4  122.74  5277.8  122.02  5303.5  122.23  5361.2  125.87
  5503.8  125.73  5609.5  127.93  5652.8  130.03  5734.5  130.59  5741.7  130.97
#Mann= 11 ,-1 , 0
  4057.7     .07       0  4242.1     .12       0  4444.1     .07       0
  4513.7     .12       0  4997.1     .05       0  5008.3     .12       0
  5085.7     .07       0  5154.3     .12       0  5214.1     .07       0
  5277.8     .05       0  5734.5     .07       0
Bank Sta=4997.1,5008.3
XS Rating Curve= 0 ,0
Exp/Cntr=0.3,0.1

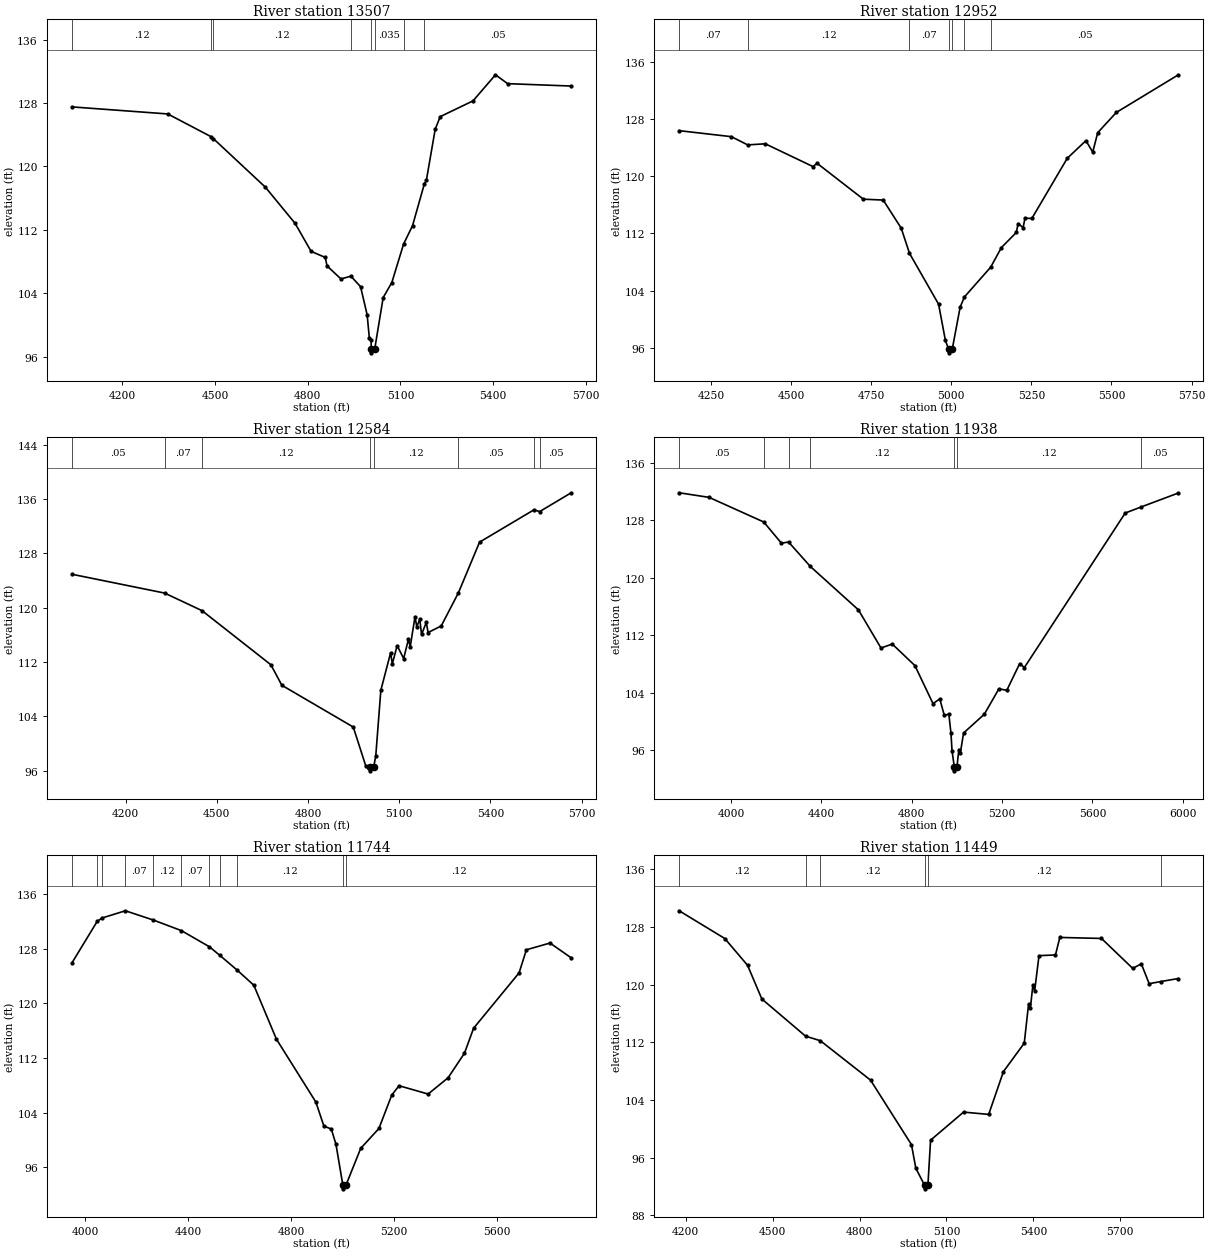
Type RM Length L Ch R = 1 ,13507   ,555,555,555
BEGIN DESCRIPTION:
Mapping XS 7c4d5825
END DESCRIPTION:
XS GIS Cut Line= 3
      2569780.69     13505947.66      2570718.15     13505765.38
      2571308.46     13505470.23
#Sta/Elev= 30
  4037.4  127.51  4347.4  126.62  4488.1  123.74  4494.8  123.51  4663.2  117.38
  4759.3  112.82    4811  109.29  4856.8  108.52  4862.6  107.45  4907.7  105.81
  4939.8  106.16  4971.1  104.83  4992.4  101.27  4999.5   98.33  5005.1    98.1
  5005.7   96.99  5006.2   96.49  5016.9   96.99  5044.2  103.46  5072.1  105.35
  5110.4  110.23  5139.2  112.53  5176.9  117.73  5183.9  118.25  5212.5  124.69
  5228.7  126.28  5334.9  128.27  5407.5  131.56  5446.7  130.44  5652.4  130.14
#Mann= 8 ,-1 , 0
  4037.4     .12       0  4488.1     .07       0  4494.8     .12       0
  4939.8    .035       0  5005.7    .035       0  5016.9    .035       0
  5110.4     .12       0  5176.9     .05       0
Bank Sta=5005.7,5016.9
XS Rating Curve= 0 ,0
Exp/Cntr=0.3,0.1

Type RM Length L Ch R = 1 ,12952   ,368,368,368
BEGIN DESCRIPTION:
Mapping XS 50331da1
END DESCRIPTION:
XS GIS Cut Line= 3
       2570171.3      13506511.9      2570961.21     13506234.13
      2571577.56     13505860.84
#Sta/Elev= 30
  4150.9  126.39  4313.8  125.55  4364.7   124.4  4419.8  124.55  4568.2  121.37
  4581.4  121.82  4725.7   116.8  4787.6  116.68  4843.8  112.75  4869.6  109.23
  4960.4  102.11  4981.6   97.06  4991.7    95.8  4992.2    95.3    5003    95.8
  5027.7  101.69  5041.2  103.13  5123.1  107.29  5156.4  110.03  5202.9  112.14
  5208.7  113.39  5224.2  112.82  5230.1  114.15  5251.4   114.1  5361.9  122.52
  5420.1  124.99  5441.5  123.39    5457  126.11  5515.1  128.94  5708.8  134.21
#Mann= 7 ,-1 , 0
  4150.9     .07       0  4364.7     .12       0  4869.6     .07       0
  4991.7     .05       0    5003     .07       0  5041.2     .12       0
  5123.1     .05       0
Bank Sta=4991.7,5003
XS Rating Curve= 0 ,0
Exp/Cntr=0.3,0.1

Type RM Length L Ch R = 1 ,12584   ,646,646,646
BEGIN DESCRIPTION:
Mapping XS 5032afce
END DESCRIPTION:
XS GIS Cut Line= 3
      2570119.18     13506763.65      2571117.46     13506555.31
      2571655.63     13506242.83
#Sta/Elev= 30
  4023.4  124.91  4328.2  122.14  4451.3  119.55  4677.8  111.58  4713.8  108.56
  4948.7  102.41  4989.6   96.72  5004.3   96.46  5004.8   95.96  5015.7   96.46
  5022.8    98.2  5039.4  107.82  5071.5  113.34  5077.2  111.71    5093   114.4
  5114.5   112.5  5130.2  115.34    5136  114.22  5151.8  118.67  5157.6  117.17
  5167.5   118.3  5173.3  116.05    5189  117.82  5194.8  116.33  5237.9  117.29
  5294.4  122.16  5364.1  129.64    5543   134.4  5561.8  134.14  5665.5  136.91
#Mann= 8 ,-1 , 0
  4023.4     .05       0  4328.2     .07       0  4451.3     .12       0
  5004.3     .05       0  5015.7     .12       0  5294.4     .05       0
    5543     .07       0  5561.8     .05       0
Bank Sta=5004.3,5015.7
XS Rating Curve= 0 ,0
Exp/Cntr=0.3,0.1

Type RM Length L Ch R = 1 ,11938   ,194,194,194
BEGIN DESCRIPTION:
Mapping XS a683ad6b
END DESCRIPTION:
XS GIS Cut Line= 3
      2569702.55     13507223.71      2570909.12     13507171.63
      2571655.63     13506503.25
#Sta/Elev= 30
    3771  131.83  3903.6  131.19  4145.4  127.76  4223.9   124.8    4255  124.98
  4351.5  121.57  4564.2  115.53  4664.3  110.21  4714.3  110.76  4814.4  107.76
  4894.5  102.47  4924.5  103.11  4944.5  100.83  4964.6     101  4974.1   98.33
  4978.7   95.91    4989    93.6  4989.5    93.1  5000.4    93.6  5008.9   96.06
  5015.6    95.6  5029.8   98.37  5121.8  100.99  5186.1  104.52  5221.2  104.32
  5278.1  108.03    5299  107.49  5745.3  129.01  5817.1  129.87  5980.7   131.8
#Mann= 7 ,-1 , 0
    3771     .05       0  4145.4     .12       0    4255     .07       0
  4351.5     .12       0    4989     .05       0  5000.4     .12       0
  5817.1     .05       0
Bank Sta=4989,5000.4
XS Rating Curve= 0 ,0
Exp/Cntr=0.3,0.1

Type RM Length L Ch R = 1 ,11744   ,295,295,295
BEGIN DESCRIPTION:
Mapping XS 983745d8
END DESCRIPTION:
XS GIS Cut Line= 3
      2569989.01     13507779.26      2570926.48      13507362.6
      2571585.66     13506729.44
#Sta/Elev= 30
    3949  125.95  4047.5  132.06  4066.9  132.54  4156.5  133.59  4265.4  132.23
  4374.3  130.68  4483.3  128.31  4523.7  127.05  4592.2  124.85  4655.8  122.67
  4743.5  114.77  4896.7  105.55    4928  102.02  4956.8  101.59  4974.9   99.36
  5001.8   93.32  5002.3   92.82  5013.3   93.32    5071   98.75  5141.8  101.67
  5191.5  106.55  5219.8  107.94    5333  106.72  5410.7  109.11  5474.2  112.71
  5509.7  116.37  5686.5  124.49  5714.8  127.87  5806.6  128.86  5888.9  126.69
#Mann= 11 ,-1 , 0
    3949     .12       0  4047.5    .035       0  4066.9     .12       0
  4156.5     .07       0  4265.4     .12       0  4374.3     .07       0
  4483.3     .12       0  4523.7     .07       0  4592.2     .12       0
  5001.8     .05       0  5013.3     .12       0
Bank Sta=5001.8,5013.3
XS Rating Curve= 0 ,0
Exp/Cntr=0.3,0.1

Type RM Length L Ch R = 1 ,11449   ,313,313,313
BEGIN DESCRIPTION:
Mapping XS 1f1a296f
END DESCRIPTION:
XS GIS Cut Line= 3
      2570587.93     13508031.01      2571169.54     13507510.17
       2571698.7     13506729.44
#Sta/Elev= 30
  4177.1  130.25  4334.7   126.4  4413.3  122.68  4462.6  118.01  4613.5  112.85
  4664.5  112.22  4837.9  106.75  4979.3   97.79  4994.3   94.52  5024.5   92.16
    5025   91.66    5036   92.16  5045.2   98.41  5159.1  102.31  5245.9  101.99
  5296.8  107.93  5368.7  111.88  5383.6  117.29  5389.7  116.69  5398.6  119.99
  5404.6  119.12  5419.6  124.02  5476.5  124.12  5491.5  126.55  5635.3  126.41
  5743.1  122.26    5773  122.88    5800  120.13  5840.5  120.43    5901  120.85
#Mann= 6 ,-1 , 0
  4177.1     .12       0  4613.5     .07       0  4664.5     .12       0
  5024.5     .05       0    5036     .12       0  5840.5     .05       0
Bank Sta=5024.5,5036
XS Rating Curve= 0 ,0
Exp/Cntr=0.3,0.1