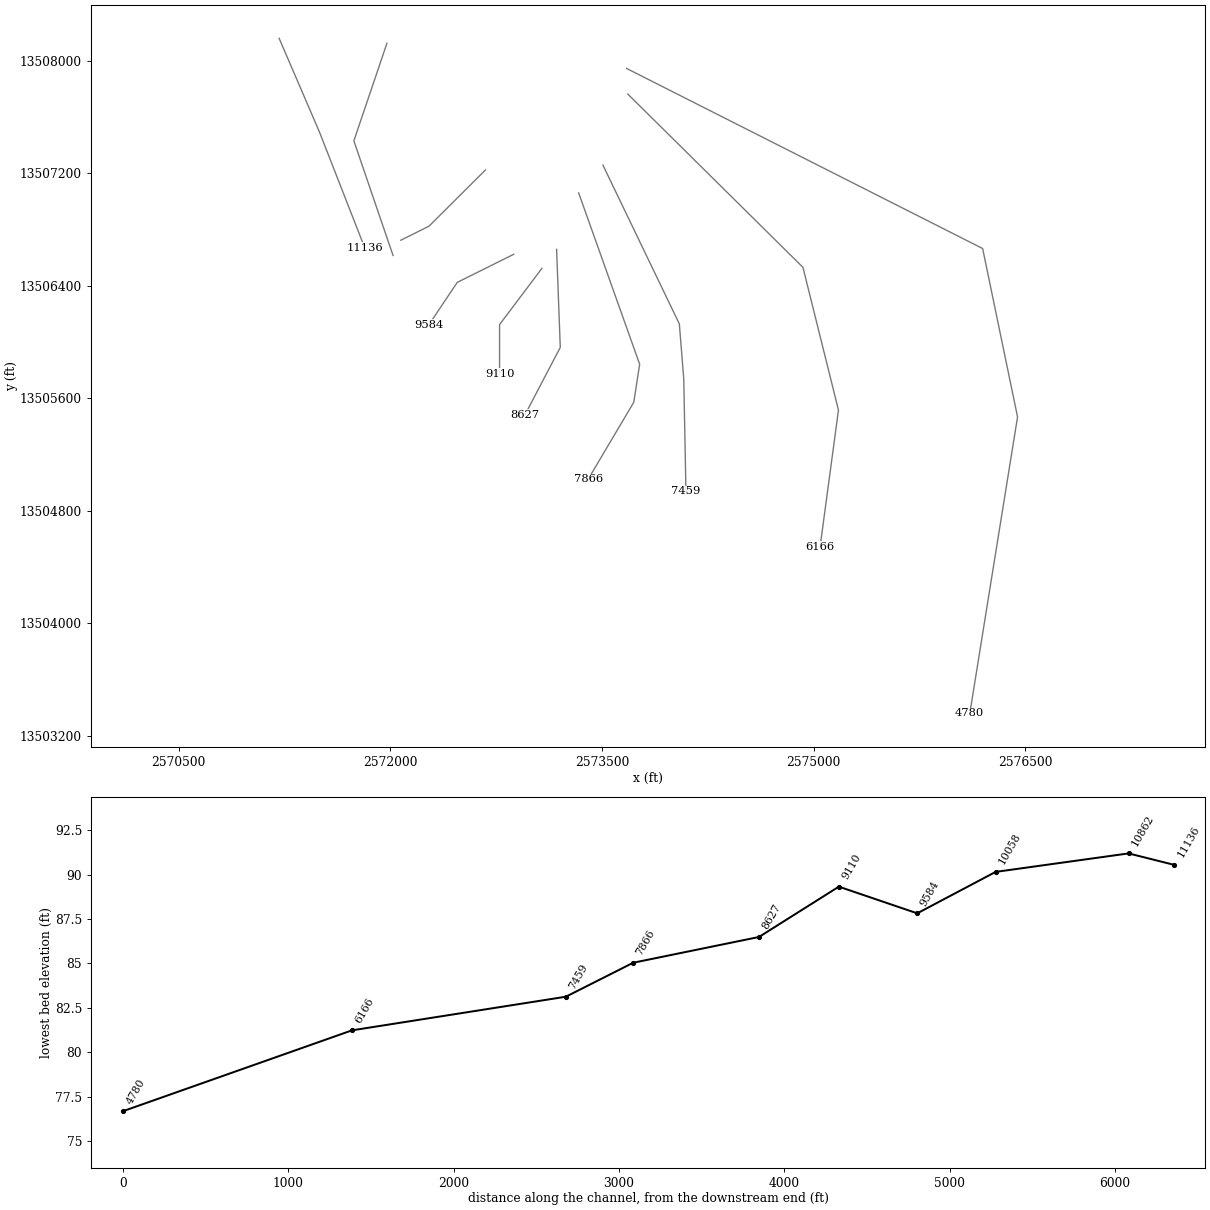
HEC-RAS study MISSION CREEK.prj: MISSION CREEK Base Level Engineering

--- MISSION CREEK.g01 (geometry) --- (continued)

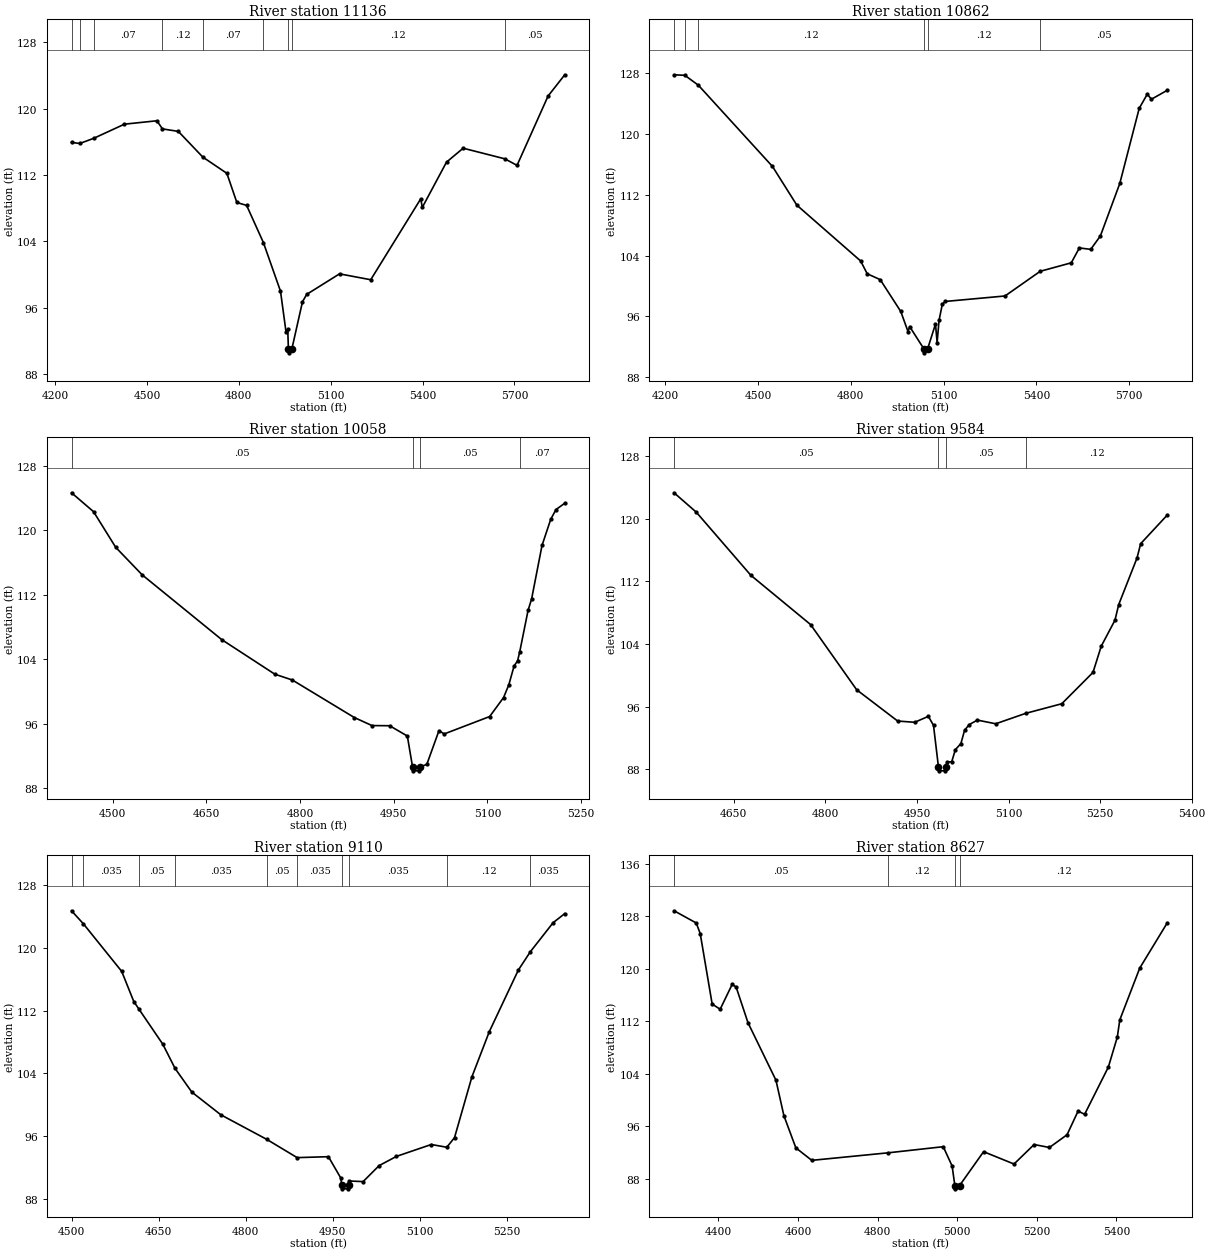
Type RM Length L Ch R = 1 ,11136   ,274,274,274
BEGIN DESCRIPTION:
Mapping XS 291b2ca8
END DESCRIPTION:
XS GIS Cut Line= 3
      2571212.96     13508161.17       2571499.4     13507492.81
      2571819.95     13506669.78
#Sta/Elev= 30
  4253.8  115.94  4280.8  115.81    4326  116.43  4426.6  118.14  4532.5  118.55
  4550.7  117.57  4602.5  117.27  4682.4  114.17    4761  112.21  4793.6  108.69
  4825.5  108.34  4880.2  103.86  4936.1   97.99  4954.2   93.06  4959.7   93.42
  4961.9   91.05  4962.4   90.55  4973.4   91.05  5007.8    96.7  5021.5    97.6
  5128.8  100.08  5230.7   99.37  5393.8  109.12  5399.2  108.11  5478.1  113.56
  5532.5  115.24  5668.5  113.96  5708.4  113.17  5809.8  121.54  5864.2   124.1
#Mann= 9 ,-1 , 0
  4253.8     .07       0  4280.8     .12       0    4326     .07       0
  4550.7     .12       0  4682.4     .07       0  4880.2     .12       0
  4961.9     .05       0  4973.4     .12       0  5668.5     .05       0
Bank Sta=4961.9,4973.4
XS Rating Curve= 0 ,0
Exp/Cntr=0.3,0.1

Type RM Length L Ch R = 1 ,10862   ,804,804,804
BEGIN DESCRIPTION:
Mapping XS 4a0104c8
END DESCRIPTION:
XS GIS Cut Line= 3
      2571976.84     13508126.51      2571742.46     13507432.05
       2572020.1     13506616.46
#Sta/Elev= 30
  4228.8  127.82  4263.6  127.75  4307.5  126.44    4547  115.74  4625.8  110.64
    4832  103.29  4853.1  101.61  4895.3  100.83  4961.7   96.64  4985.1   93.99
  4990.4   94.65  5036.8   91.69  5037.3   91.19  5048.3   91.69  5073.9   94.98
  5079.2   92.54  5085.4   95.47    5096   97.59  5105.3   97.96  5298.7   98.68
  5412.4  101.93  5512.9  103.05    5539  105.01  5575.7  104.82    5607  106.59
  5669.7   113.5  5732.5   123.4  5758.5  125.26    5772   124.6  5823.3  125.78
#Mann= 6 ,-1 , 0
  4228.8     .12       0  4263.6     .07       0  4307.5     .12       0
  5036.8     .05       0  5048.3     .12       0  5412.4     .05       0
Bank Sta=5036.8,5048.3
XS Rating Curve= 0 ,0
Exp/Cntr=0.3,0.1

Type RM Length L Ch R = 1 ,10058   ,474,474,474
BEGIN DESCRIPTION:
MISSION CREEK 14.0
END DESCRIPTION:
XS GIS Cut Line= 3
      2572674.99     13507224.99        2572275.       13506825.
      2572074.98     13506724.99
#Sta/Elev= 30
  4434.4  124.67  4469.7  122.32  4505.1   117.9  4547.5  114.48  4674.8  106.44
  4759.7  102.15  4787.9  101.42  4886.9   96.77  4915.2   95.77  4943.5   95.75
  4971.8   94.47  4980.1   90.65  4980.6   90.15  4991.2   90.15  4991.7   90.65
  5002.9   90.94  5022.4   95.14  5030.8   94.73  5103.5   96.89  5125.8   99.25
  5134.2  100.84  5142.6  103.16  5148.2  103.81  5151.7  104.95    5165  110.08
  5170.6  111.47  5187.3  118.13  5201.3  121.39  5209.7  122.59  5223.7  123.37
#Mann= 4 ,-1 , 0
  4434.4     .05       0  4980.1     .05       0  4991.7     .05       0
  5151.7     .07       0
Bank Sta=4980.1,4991.7
XS Rating Curve= 0 ,0
Exp/Cntr=0.3,0.1

Type RM Length L Ch R = 1 ,9584    ,474,474,474
BEGIN DESCRIPTION:
MISSION CREEK 13.0
END DESCRIPTION:
XS GIS Cut Line= 3
      2572875.01       13506625.        2572475.       13506425.
      2572274.99     13506124.98
#Sta/Elev= 30
  4552.2  123.33  4588.5  120.86    4678  112.79  4775.8   106.5  4851.3   98.17
  4918.4   94.18  4946.3   94.02  4968.7   94.78  4977.1   93.63  4985.2   88.32
  4985.7   87.82  4996.4   87.82  4996.9   88.32  4999.4   88.97  5006.9   88.97
  5012.9   90.52    5022   91.31    5028      93  5035.5   93.72    5049    94.3
    5079   93.83    5128   95.16  5187.2   96.39  5238.3  100.39  5251.8  103.74
  5274.3  107.06  5280.4  109.05  5310.4     115  5316.4  116.83    5360  120.49
#Mann= 4 ,-1 , 0
  4552.2     .05       0  4985.2     .05       0  4996.9     .05       0
    5128     .12       0
Bank Sta=4985.2,4996.9
XS Rating Curve= 0 ,0
Exp/Cntr=0.3,0.1

Type RM Length L Ch R = 1 ,9110    ,483,483,483
BEGIN DESCRIPTION:
MISSION CREEK 12.0
END DESCRIPTION:
XS GIS Cut Line= 3
      2573075.01     13506525.01        2572775.       13506125.
        2572775.     13505775.02
#Sta/Elev= 30
  4499.9  124.69  4520.4  123.03  4586.4  116.98  4607.2  113.15  4615.9   112.2
  4657.2  107.72  4678.4  104.63  4707.2  101.63  4757.2   98.74  4836.4   95.61
  4888.7   93.29  4942.6   93.41  4963.5   90.75  4965.8   89.82  4966.3   89.32
  4977.2   89.32  4977.7   89.82    4978   90.32  5002.4   90.24  5029.9   92.27
  5059.9   93.45  5119.9   94.96  5146.6   94.61  5159.9   95.83  5189.9  103.57
  5219.9  109.32  5269.9  117.15  5290.7  119.49  5329.9  123.18  5349.9  124.33
#Mann= 10 ,-1 , 0
  4499.9     .05       0  4520.4    .035       0  4615.9     .05       0
  4678.4    .035       0  4836.4     .05       0  4888.7    .035       0
  4965.8    .035       0  4977.7    .035       0  5146.6     .12       0
  5290.7    .035       0
Bank Sta=4965.8,4977.7
XS Rating Curve= 0 ,0
Exp/Cntr=0.3,0.1

Type RM Length L Ch R = 1 ,8627    ,761,761,761
BEGIN DESCRIPTION:
Mapping XS 3c3f19f1
END DESCRIPTION:
XS GIS Cut Line= 3
      2573179.09     13506660.67      2573205.13      13505962.8
      2572955.14     13505483.65
#Sta/Elev= 30
  4288.9  128.85  4344.6  126.99  4354.6  125.38  4384.6  114.64  4404.7  113.85
  4434.7  117.62  4444.7  117.25  4474.7  111.78  4544.8  103.04  4564.8   97.63
  4594.8   92.73  4634.8   90.83  4826.9   91.98    4965   92.91  4987.3   89.96
  4994.1   86.99  4994.6   86.49    5006   86.99  5066.3   92.15  5142.7   90.27
  5193.2   93.24  5231.7   92.79  5275.9   94.73  5303.6   98.33  5320.1   97.85
  5379.6  105.03  5402.1   109.6  5408.4  112.23  5458.5  120.12  5527.7  127.02
#Mann= 4 ,-1 , 0
  4288.9     .05       0  4826.9     .12       0  4994.1     .05       0
    5006     .12       0
Bank Sta=4994.1,5006
XS Rating Curve= 0 ,0
Exp/Cntr=0.3,0.1

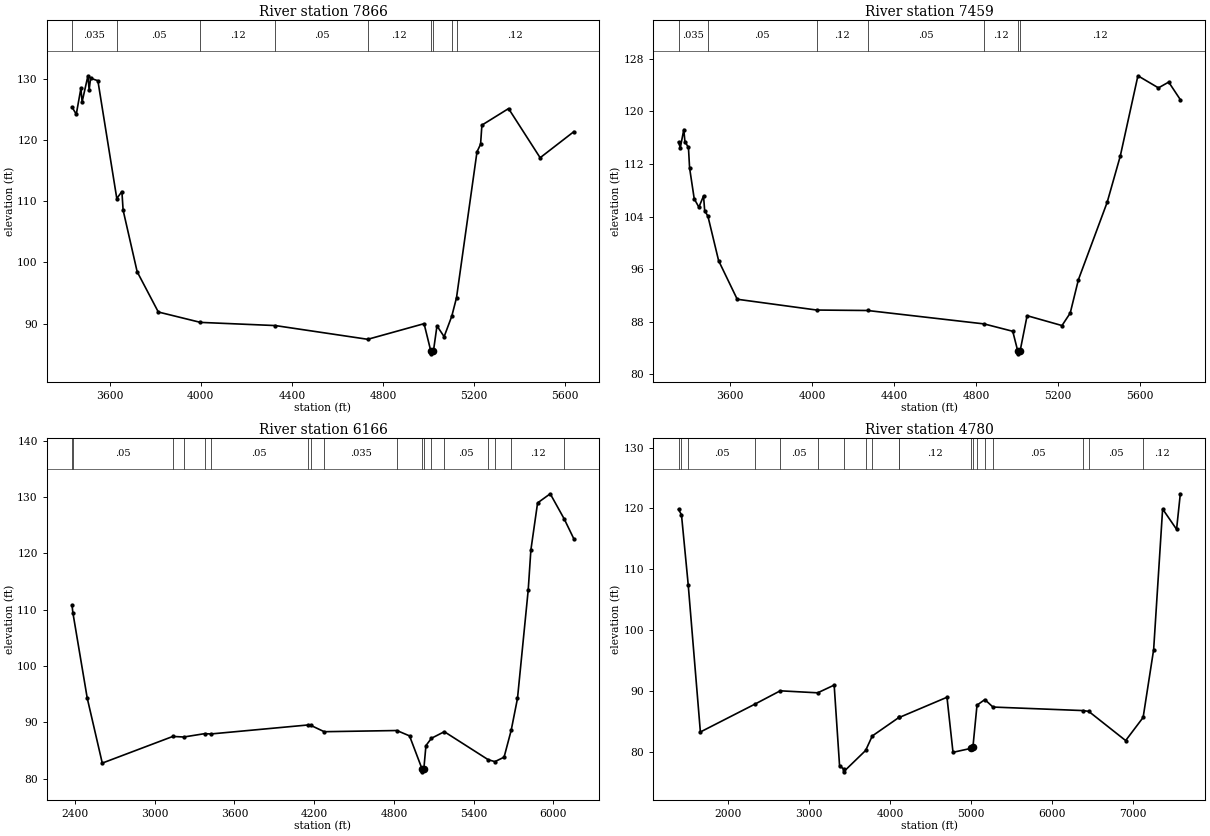
Type RM Length L Ch R = 1 ,7866    ,407,407,407
BEGIN DESCRIPTION:
Mapping XS adfd8107
END DESCRIPTION:
XS GIS Cut Line= 4
      2573335.34     13507061.74      2573767.63     13505843.01
      2573725.96     13505572.18      2573403.06     13505025.34
#Sta/Elev= 30
  3435.6  125.43  3454.1  124.27  3474.4  128.52  3479.7  126.29  3505.2  130.57
  3510.5  128.27    3517  130.17  3548.9  129.76  3631.9  110.47  3654.3  111.62
  3659.6  108.57  3721.3   98.48  3814.1   91.89  3999.1   90.19  4327.4   89.67
  4733.3   87.42  4980.4   89.98  5009.7   85.54  5010.2   85.04  5021.7   85.54
  5037.1   89.62  5068.4   87.85    5102    91.2  5122.8   94.23  5212.7  118.12
  5228.4  119.36  5234.2  122.49  5351.2   125.2  5489.8  117.15  5637.8  121.42
#Mann= 9 ,-1 , 0
  3435.6    .035       0  3631.9     .05       0  3999.1     .12       0
  4327.4     .05       0  4733.3     .12       0  5009.7     .05       0
  5021.7     .12       0    5102     .07       0  5122.8     .12       0
Bank Sta=5009.7,5021.7
XS Rating Curve= 0 ,0
Exp/Cntr=0.3,0.1

Type RM Length L Ch R = 1 ,7459    ,1293,1293,1293
BEGIN DESCRIPTION:
Mapping XS ef630f23
END DESCRIPTION:
XS GIS Cut Line= 4
      2573507.22     13507259.66      2574048.88     13506129.47
      2574080.13     13505738.85      2574095.72     13504938.36
#Sta/Elev= 30
  3349.3  115.31  3357.9  114.45    3375  117.24  3380.5  115.37  3397.6  114.52
  3403.2  111.39  3425.8   106.7  3448.5  105.43  3471.2  107.14  3476.7   104.9
  3492.6  104.05  3544.7   97.29  3635.3   91.43  4022.7   89.79  4270.6   89.72
  4838.8   87.68  4978.3   86.56  5002.1   83.63  5002.6   83.13  5014.6   83.63
  5048.3   88.93  5218.3   87.43  5258.4   89.33  5298.4   94.41  5438.4  106.16
  5502.4   113.2  5588.4  125.41  5688.4  123.57  5738.4  124.45  5795.1  121.78
#Mann= 7 ,-1 , 0
  3349.3    .035       0  3492.6     .05       0  4022.7     .12       0
  4270.6     .05       0  4838.8     .12       0  5002.1     .05       0
  5014.6     .12       0
Bank Sta=5002.1,5014.6
XS Rating Curve= 0 ,0
Exp/Cntr=0.3,0.1

Type RM Length L Ch R = 1 ,6166    ,1386,1386,1386
BEGIN DESCRIPTION:
Mapping XS 0e679484
END DESCRIPTION:
XS GIS Cut Line= 4
      2573683.44     13507764.87      2574924.75     13506532.25
      2575176.48     13505516.62      2575046.27     13504544.41
#Sta/Elev= 30
  2377.6  110.75  2383.5   109.5  2491.8   94.31  2604.9   82.79    3136   87.52
  3218.2   87.42  3374.6   88.01  3422.1   87.96  4151.4   89.55  4174.6   89.48
  4275.4   88.36    4822   88.57  4917.4   87.62  5011.9   81.74  5012.4   81.24
    5025   81.74    5041    85.9  5082.5    87.2  5179.4   88.36    5509    83.4
  5559.6   83.05    5629   83.84  5682.5   88.61  5729.9   94.26  5810.6  113.48
  5830.7   120.6  5881.2  128.95  5976.3  130.57  6081.9  126.09  6154.2  122.57
#Mann= 18 ,-1 , 0
  2377.6    .035       0  2383.5     .05       0    3136     .07       0
  3218.2     .12       0  3374.6     .07       0  3422.1     .05       0
  4151.4     .12       0  4174.6     .07       0  4275.4    .035       0
    4822     .12       0  5011.9     .05       0    5025     .12       0
  5082.5     .07       0  5179.4     .05       0    5509     .07       0
  5559.6     .05       0  5682.5     .12       0  6081.9     .05       0
Bank Sta=5011.9,5025
XS Rating Curve= 0 ,0
Exp/Cntr=0.3,0.1

Type RM Length L Ch R = 1 ,4780    ,0,0,0
BEGIN DESCRIPTION:
Mapping XS 611be9c8
END DESCRIPTION:
XS GIS Cut Line= 4
      2573674.78     13507947.16      2576198.18     13506665.93
      2576445.58     13505468.01      2576107.15     13503359.33
#Sta/Elev= 30
  1393.1  119.83  1429.5  118.94  1512.3  107.47  1662.5   83.24  2332.1    87.8
  2647.6   90.01  3109.2   89.68  3312.6   90.95  3379.4   77.65    3428   77.19
  3428.5   76.69  3700.4    80.2  3782.8   82.59  4114.6   85.66  4117.8   85.64
    4704   88.95  4778.3    79.9  5000.1   80.55  5024.4   80.82  5074.3   87.65
  5170.9   88.57    5271   87.34  6383.5   86.76  6452.1   86.63  6907.8   81.83
  7123.2   85.63  7252.9   96.78  7363.6   119.9  7535.7  116.56    7582   122.4
#Mann= 19 ,-1 , 0
  1393.1     .12       0  1429.5    .035       0  1512.3     .05       0
  2332.1     .12       0  2647.6     .05       0  3109.2     .12       0
    3428     .07       0  3700.4     .07       0  3782.8     .05       0
  4114.6     .07       0  4117.8     .12       0  5000.1     .05       0
  5024.4     .05       0  5074.3     .05       0  5170.9    .035       0
    5271     .05       0  6383.5     .07       0  6452.1     .05       0
  7123.2     .12       0
Bank Sta=5000.1,5024.4
XS Rating Curve= 0 ,0
Exp/Cntr=0.3,0.1

Chan Stop Cuts=-1
Use User Specified Reach Order=0
Composite Channel Slope=5