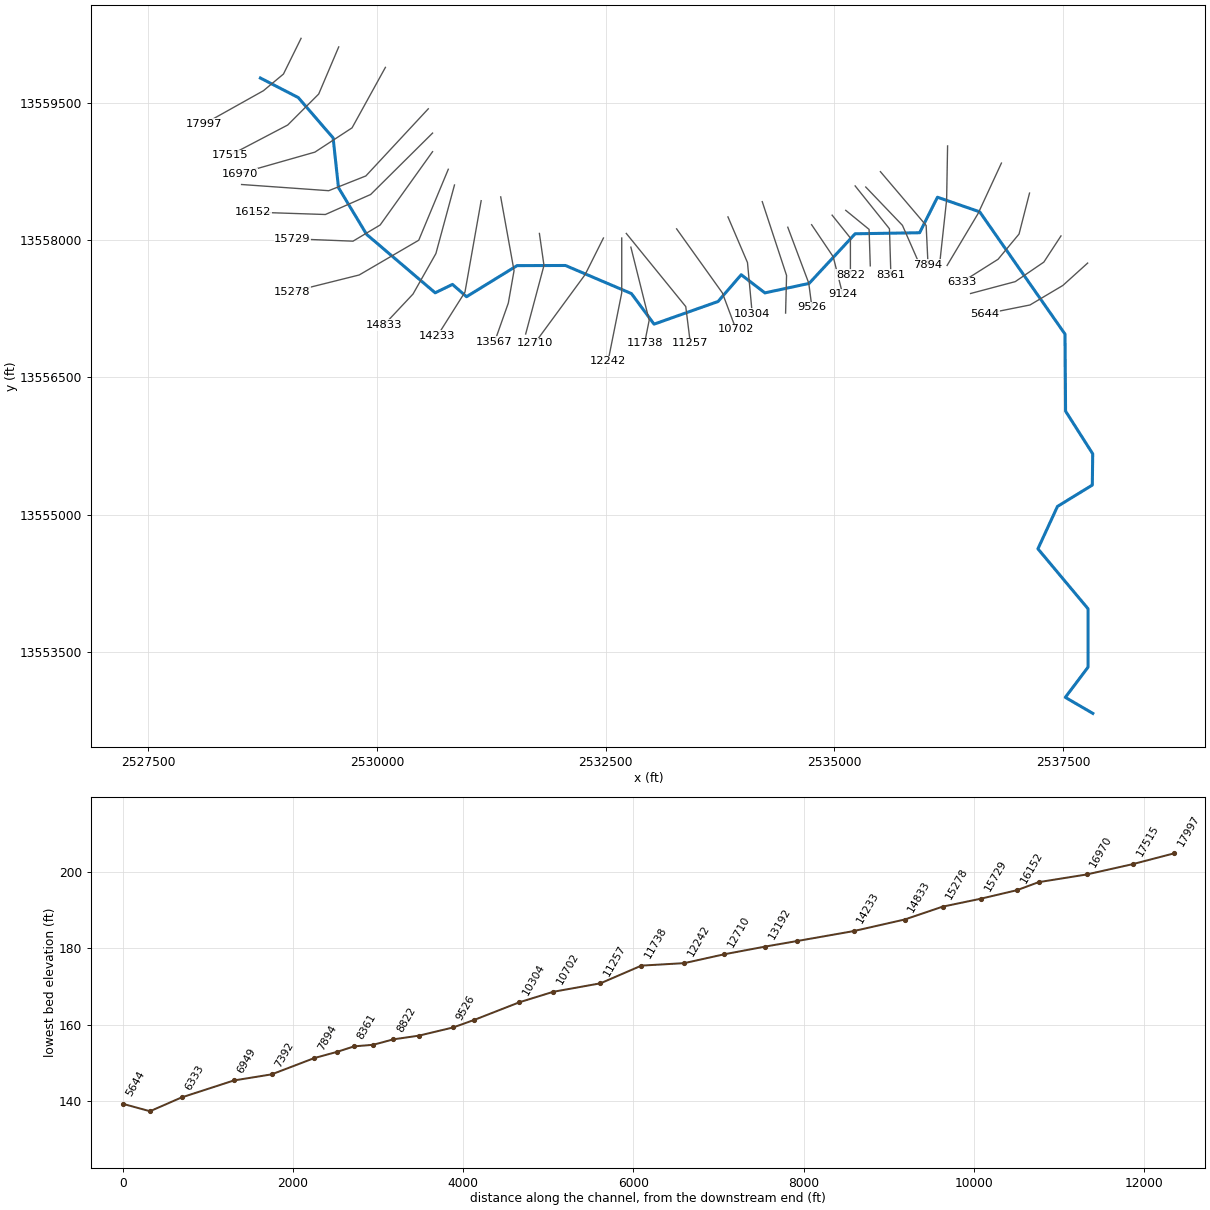
--- NORTH FORK CREEK.prj (project) ---

Proj Title=NORTH FORK CREEK Base Level Engineering
Current Plan=p01
Default Exp/Contr=0.3,0.1
English Units
Geom File=g01
Flow File=f01
Plan File=p01
Y Axis Title=Elevation
X Axis Title(PF)=Main Channel Distance
X Axis Title(XS)=Station
BEGIN DESCRIPTION:
NORTH FORK CREEK
END DESCRIPTION:
DSS Export Rating Curves= 0
DSS Export Rating Curve Sorted= 0
DSS Export Volume Flow Curves= 0
DXF OffsetX= 0
DXF OffsetY= 0
DXF ScaleX= 1
DXF ScaleY= 10

--- NORTH FORK CREEK.p01 (plan) ---

Plan Title=Multiple Run
Short Identifier=Multiple
Geom File=g01
Flow File=f01
Subcritical Flow
K Sum by GR= 0
Std Step Tol= 0.01
Critical Tol= 0.01
Num of Std Step Trials= 20
Max Error Tol= 0.3
Flow Tol Ratio= 0.001
Split Flow NTrial= 30
Split Flow Tol= 0.02
Split Flow Ratio= 0.02
Log Output Level= 0
Friction Slope Method= 1
Unsteady Friction Slope Method= 2
Unsteady Bridges Friction Slope Method= 1
Parabolic Critical Depth
Global Vel Dist=  1 , 1 , 1
Global Log Level= 0
CheckData=True
Encroach Param= -1, 0, 0, 0
BEGIN DESCRIPTION:
Multiple Run
END DESCRIPTION:

--- NORTH FORK CREEK.f01 (steady flow) ---

Flow Title=Multiple
Number of Profiles=7
Profile Names=10-year,25-year,50-year,1pct_min,100-year,1pct_plu,500-year
River Rch & RM= NORTH FORK CREEK,Reach-1,17997
     689    1111    1492     971    1938    3866    3233
River Rch & RM= NORTH FORK CREEK,Reach-1,13567
     901    1473    1997    1310    2614    5215    4432
River Rch & RM= NORTH FORK CREEK,Reach-1,7392
    1398    2340    3222    2144    4277    8534    7470
River Rch & RM= NORTH FORK CREEK,Reach-1,4472
    1631    2750    3805    2543    5073   10123    8938
River Rch & RM= NORTH FORK CREEK,Reach-1,2390
    1770    2998    4161    2788    5563   11100    9856
River Rch & RM= NORTH FORK CREEK,Reach-1,1610
    1827    3098    4304    2887    5760   11492   10221
Boundary for River Rch & Prof#=NORTH FORK CREEK,Reach-1,1
Up Type=0
Dn Type=3
Dn Slope=0.005
Boundary for River Rch & Prof#=NORTH FORK CREEK,Reach-1,2
Up Type=0
Dn Type=3
Dn Slope=0.005
Boundary for River Rch & Prof#=NORTH FORK CREEK,Reach-1,3
Up Type=0
Dn Type=3
Dn Slope=0.005
Boundary for River Rch & Prof#=NORTH FORK CREEK,Reach-1,4
Up Type=0
Dn Type=3
Dn Slope=0.005
Boundary for River Rch & Prof#=NORTH FORK CREEK,Reach-1,5
Up Type=0
Dn Type=3
Dn Slope=0.005
Boundary for River Rch & Prof#=NORTH FORK CREEK,Reach-1,6
Up Type=0
Dn Type=3
Dn Slope=0.005
Boundary for River Rch & Prof#=NORTH FORK CREEK,Reach-1,7
Up Type=0
Dn Type=3
Dn Slope=0.005

--- NORTH FORK CREEK.g01 (geometry) ---

Geom Title=Existing Conditions
Program Version=4.10

River Reach=NORTH FORK CREEK,Reach-1
Reach XY= 30
        2528725.       13559775.      2529138.57     13559561.53
      2529519.92     13559119.96      2529578.45     13558576.25
      2529886.04     13558064.65      2530635.63      13557425.6
      2530825.09     13557517.71      2530978.23     13557382.83
       2531530.7     13557723.08      2532059.79     13557724.49
      2532781.19     13557417.15       2533028.4     13557082.78
      2533727.75     13557330.42      2533981.12     13557623.18
      2534240.24     13557424.84      2534723.75     13557528.45
       2535226.5     13558071.39      2535931.48     13558082.69
      2536126.55     13558471.25      2536588.34     13558311.35
      2537521.25     13556973.45      2537527.24     13556130.93
       2537823.8      13555664.5      2537819.54     13555322.55
      2537438.45     13555088.63        2537225.       13554625.
      2537772.94     13553969.14      2537772.94     13553330.85
      2537524.49     13552999.96        2537825.       13552825.

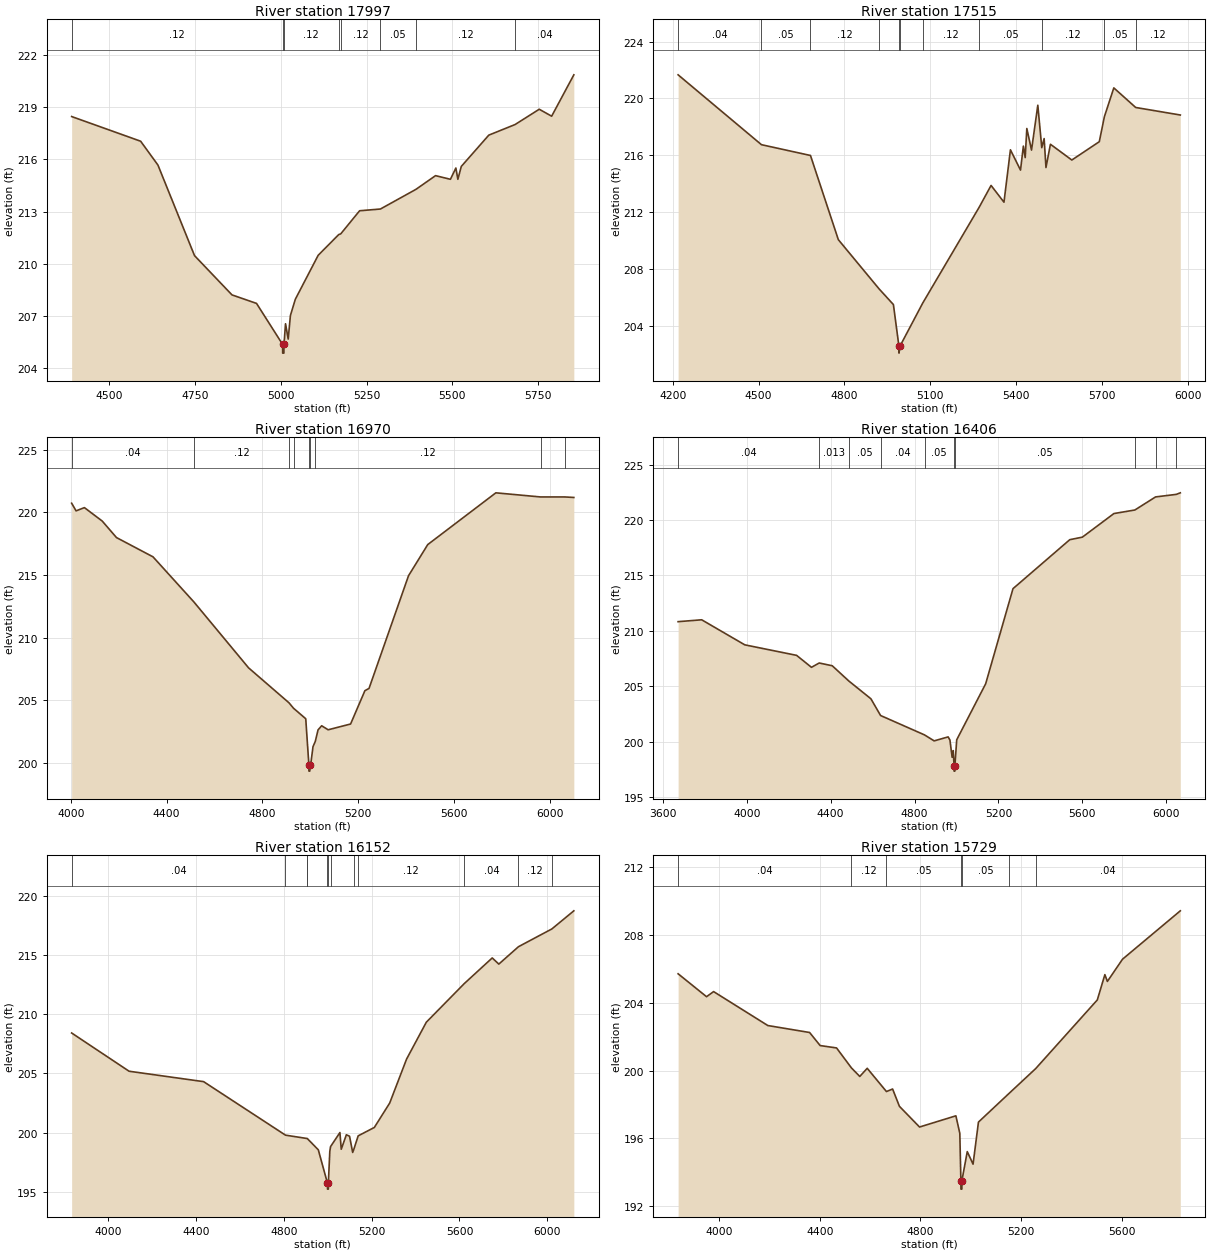
Type RM Length L Ch R = 1 ,17997   ,482,482,482
BEGIN DESCRIPTION:
Mapping XS 4334a5b6
END DESCRIPTION:
XS GIS Cut Line= 4
      2529169.62     13560209.33       2528976.9     13559818.66
      2528758.15     13559636.37      2528108.54     13559272.59
#Sta/Elev= 30
  4389.7  218.47    4591  217.05  4641.4  215.68  4748.1  210.47  4857.4  208.21
    4929  207.72  5005.1  205.36  5005.3  204.86  5008.8  204.86  5009.1  205.36
  5013.6  206.55  5021.4  205.67  5027.9  207.03  5042.2  207.96  5108.9  210.49
  5168.8  211.68  5174.6  211.72  5229.7  213.05  5290.4  213.15  5393.9  214.28
  5451.2  215.07  5494.6  214.86  5510.5  215.51  5516.3  214.86  5526.3   215.6
  5606.5   217.4  5683.2  218.01  5753.7  218.89  5789.9  218.49  5854.6  220.87
#Mann= 8 ,-1 , 0
  4389.7     .12       0  5005.1     .05       0  5009.1     .12       0
  5168.8     .05       0  5174.6     .12       0  5290.4     .05       0
  5393.9     .12       0  5683.2     .04       0
Bank Sta=5005.1,5009.1
XS Rating Curve= 0 ,0
Exp/Cntr=0.3,0.1

Type RM Length L Ch R = 1 ,17515   ,545,545,545
BEGIN DESCRIPTION:
Mapping XS 891a7dce
END DESCRIPTION:
XS GIS Cut Line= 4
      2529581.07     13560115.56      2529362.31     13559599.91
      2529023.77     13559261.37      2528389.19     13558928.48
#Sta/Elev= 30
    4219  221.66  4510.3  216.74  4681.7  215.98  4779.1  210.05  4921.3  206.59
  4971.6  205.48  4990.8  202.56  4991.1  202.06  4994.8  202.56  5074.5   205.6
  5271.3  212.33    5313  213.87  5358.1  212.69  5380.7  216.38  5415.9  214.95
  5425.9  216.64  5432.3  215.83    5438  217.88  5454.4  216.36  5476.4  219.52
  5490.2  216.53  5498.5  217.17  5504.9  215.13  5520.5  216.77  5595.3  215.66
  5691.3  216.95  5709.1  218.71  5742.1  220.74  5818.6  219.36  5974.5  218.83
#Mann= 11 ,-1 , 0
    4219     .04       0  4510.3     .05       0  4681.7     .12       0
  4921.3     .05       0  4990.8     .05       0  4994.8     .05       0
  5074.5     .12       0  5271.3     .05       0  5490.2     .12       0
  5709.1     .05       0  5818.6     .12       0
Bank Sta=4990.8,4994.8
XS Rating Curve= 0 ,0
Exp/Cntr=0.3,0.1

Type RM Length L Ch R = 1 ,16970   ,564,564,564
BEGIN DESCRIPTION:
Mapping XS e02cba76
END DESCRIPTION:
XS GIS Cut Line= 4
       2530091.5     13559891.61       2529726.9     13559230.12
      2529320.65      13558964.5      2528498.83     13558730.43
#Sta/Elev= 30
  4003.8  220.72  4022.3  220.11    4057  220.37  4131.2   219.3  4190.8  217.98
  4343.3  216.44  4513.9  212.84  4742.1  207.58  4910.7  204.79  4929.4  204.36
  4980.5  203.52  4993.6  199.84  4993.9  199.34  4997.4  199.34  4997.6  199.84
  5001.6  199.92  5010.7  201.29  5020.3  201.71  5031.8  202.63  5046.9  202.96
    5074  202.64  5167.6   203.1  5227.3  205.76  5244.5  205.94  5409.2  214.93
  5489.5  217.42  5773.7  221.55  5960.4  221.22  6061.8  221.22    6099  221.18
#Mann= 9 ,-1 , 0
  4003.8     .04       0  4513.9     .12       0  4910.7     .05       0
  4929.4     .04       0  4993.6     .04       0  4997.6     .04       0
  5020.3     .12       0  5960.4    .013       0  6061.8     .12       0
Bank Sta=4993.6,4997.6
XS Rating Curve= 0 ,0
Exp/Cntr=0.3,0.1

Type RM Length L Ch R = 1 ,16406   ,254,254,254
BEGIN DESCRIPTION:
Mapping XS 9116d84e
END DESCRIPTION:
XS GIS Cut Line= 4
      2530560.25     13559438.47      2529877.94     13558704.08
      2529471.69     13558542.62      2528519.28     13558610.28
#Sta/Elev= 30
  3672.9  210.82  3785.4  210.99  3990.6  208.73  4237.8  207.78  4308.7   206.7
  4345.6  207.09  4407.9  206.84  4485.9  205.48  4592.1  203.86  4638.3  202.35
  4847.7   200.6  4893.7  200.06  4960.4  200.42    4969  200.13  4979.3  198.58
  4984.7  199.18  4988.6  197.83  4988.8  197.33  4992.3  197.33  4992.6  197.83
  5001.3  200.16  5139.2  205.21  5269.6   213.8  5540.3  218.22  5600.4  218.45
  5750.8  220.58  5850.7   220.9  5949.4  222.08  6048.2  222.31  6067.3  222.45
#Mann= 10 ,-1 , 0
  3672.9     .04       0  4345.6    .013       0  4485.9     .05       0
  4638.3     .04       0  4847.7     .05       0  4988.6     .05       0
  4992.6     .05       0  5850.7     .05       0  5949.4     .12       0
  6048.2    .013       0
Bank Sta=4988.6,4992.6
XS Rating Curve= 0 ,0
Exp/Cntr=0.3,0.1

Type RM Length L Ch R = 1 ,16152   ,423,423,423
BEGIN DESCRIPTION:
Mapping XS 3e861c5e
END DESCRIPTION:
XS GIS Cut Line= 4
      2530607.07      13559172.8      2529930.02     13558500.96
      2529435.23     13558282.21      2528643.57     13558308.25
#Sta/Elev= 30
    3834  208.42  4095.5  205.19  4434.9  204.31  4807.8  199.79  4904.6  199.51
  4906.8  199.51  4957.3  198.55    4999  195.73  4999.3  195.23  5002.8  195.23
    5003  195.73  5009.6  198.41    5013  198.82  5055.7  200.01  5061.7   198.6
    5085  199.82  5099.5   199.7  5113.8  198.33  5119.3  198.61  5138.8  199.73
  5212.4  200.44  5282.3   202.5  5359.1  206.21  5449.1  209.33  5621.8  212.59
  5749.3  214.76  5779.3  214.24  5868.8  215.71  6020.9  217.21  6120.9  218.74
#Mann= 12 ,-1 , 0
    3834     .04       0  4807.8    .013       0  4904.6     .05       0
  4906.8    .013       0    4999     .03       0    5003    .013       0
    5013     .12       0  5119.3     .05       0  5138.8     .12       0
  5621.8     .04       0  5868.8     .12       0  6020.9     .05       0
Bank Sta=4999,5003
XS Rating Curve= 0 ,0
Exp/Cntr=0.3,0.1

Type RM Length L Ch R = 1 ,15729   ,451,451,451
BEGIN DESCRIPTION:
Mapping XS 7d20b879
END DESCRIPTION:
XS GIS Cut Line= 4
      2530607.08     13558969.67      2530034.19     13558167.62
      2529737.31     13557990.54      2529075.84     13558016.58
#Sta/Elev= 30
    3838   205.7  3950.8  204.35  3978.9  204.65  4194.1  202.65  4359.9  202.24
  4401.8  201.47  4466.9  201.33  4526.1  200.15  4559.1  199.65  4588.6  200.13
  4664.9  198.76  4689.4  198.91  4716.4  197.89  4796.3  196.67  4940.5  197.33
  4956.1   196.3  4960.4  193.51  4960.7  193.01  4964.2  193.01  4964.4  193.51
  4985.7  195.22  5008.7  194.48  5030.1  196.96  5151.5  198.65  5257.1  200.11
  5501.9  204.16  5531.9  205.65  5541.9  205.25    5602  206.56  5831.3  209.41
#Mann= 7 ,-1 , 0
    3838     .04       0  4526.1     .12       0  4664.9     .05       0
  4960.4     .05       0  4964.4     .05       0  5151.5    .013       0
  5257.1     .04       0
Bank Sta=4960.4,4964.4
XS Rating Curve= 0 ,0
Exp/Cntr=0.3,0.1

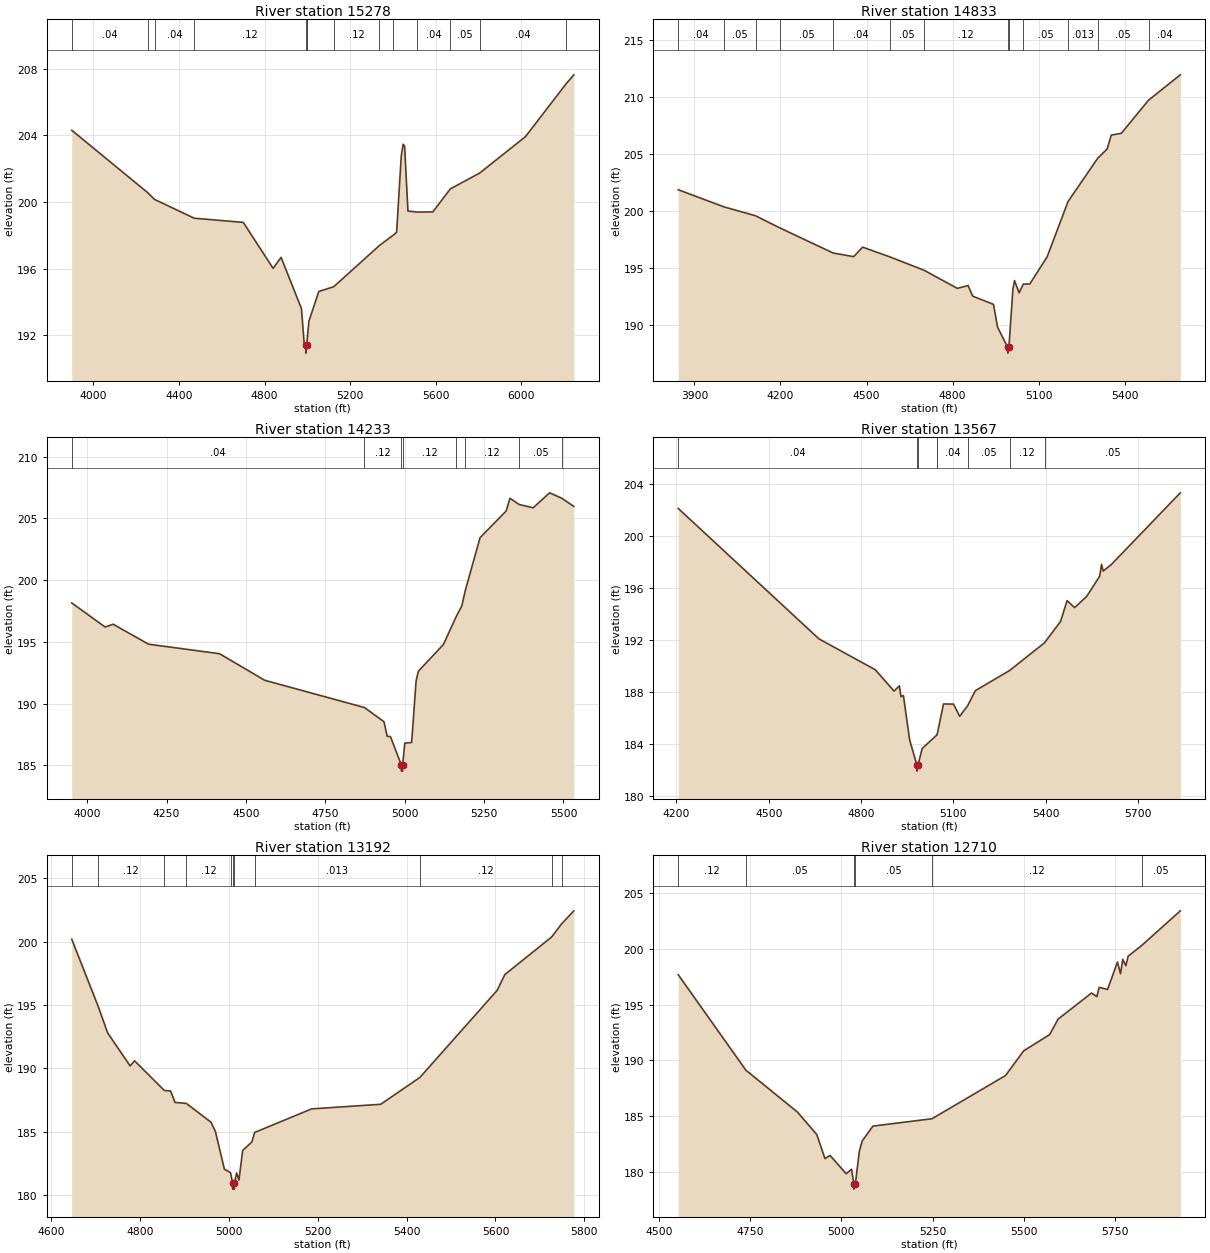
Type RM Length L Ch R = 1 ,15278   ,445,445,445
BEGIN DESCRIPTION:
Mapping XS dc5d379d
END DESCRIPTION:
XS GIS Cut Line= 4
      2530778.99     13558777.02      2530456.06     13558000.96
      2529805.02     13557620.75      2529075.86     13557438.46
#Sta/Elev= 30
  3898.9   204.3  4253.4  200.56  4285.6  200.15  4471.3  199.02  4700.2  198.77
  4839.8  196.01    4877  196.67  4972.3  193.59  4984.5  191.55  4992.4  191.42
  4992.7  190.92  4996.4  191.42  4996.8  191.44    5007  192.84  5053.1  194.62
  5123.3  194.91  5336.3  197.38  5401.8  198.01  5416.9  198.18  5438.4  202.73
  5447.1  203.46  5454.1  203.36  5469.8  199.45  5514.1  199.39  5586.2   199.4
  5667.7  200.78  5804.8  201.73  6019.1  203.92  6208.8  207.09    6245  207.63
#Mann= 14 ,-1 , 0
  3898.9     .04       0  4253.4     .05       0  4285.6     .04       0
  4471.3     .12       0  4992.4     .05       0  4996.4     .12       0
  4996.8     .05       0  5123.3     .12       0  5336.3    .013       0
  5401.8     .05       0  5514.1     .04       0  5667.7     .05       0
  5804.8     .04       0  6208.8     .05       0
Bank Sta=4992.4,4996.4
XS Rating Curve= 0 ,0
Exp/Cntr=0.3,0.1

Type RM Length L Ch R = 1 ,14833   ,600,600,600
BEGIN DESCRIPTION:
Mapping XS 06889380
END DESCRIPTION:
XS GIS Cut Line= 4
      2530846.68     13558605.09      2530643.56     13557855.12
      2530393.56     13557412.41      2530075.84     13557073.86
#Sta/Elev= 30
  3843.7  201.87    4004  200.36    4113  199.59  4199.9   198.5  4383.2  196.33
  4455.1  196.01  4486.3  196.84    4580     196  4700.3  194.82  4816.4  193.23
  4853.9  193.48  4869.9  192.55  4942.4  191.83  4956.5  189.84    4992  188.06
  4992.3  187.56    4996  188.06  5009.9  193.14  5015.7  193.91  5031.6  192.84
  5046.4  193.61  5068.7  193.61  5129.1  195.98  5202.1  200.83  5305.7  204.63
  5338.5  205.44  5352.7  206.65  5387.9  206.81  5482.7  209.71  5593.4  211.93
#Mann= 13 ,-1 , 0
  3843.7     .04       0    4004     .05       0    4113     .04       0
  4199.9     .05       0  4383.2     .04       0    4580     .05       0
  4700.3     .12       0    4992     .05       0    4996     .12       0
  5046.4     .05       0  5202.1    .013       0  5305.7     .05       0
  5482.7     .04       0
Bank Sta=4992,4996
XS Rating Curve= 0 ,0
Exp/Cntr=0.3,0.1

Type RM Length L Ch R = 1 ,14233   ,666,666,666
BEGIN DESCRIPTION:
Mapping XS 62346866
END DESCRIPTION:
XS GIS Cut Line= 3
      2531138.35     13558433.24      2530961.27     13557433.25
      2530659.61     13556954.75
#Sta/Elev= 30
  3951.5  198.15  4056.6   196.2  4081.7  196.43  4193.4  194.81  4416.9  194.04
    4559  191.89  4873.3  189.68  4934.8  188.53    4945  187.35  4955.1  187.33
  4989.4  185.03  4989.6  184.53  4993.1  184.53  4993.4  185.03  5000.4   186.8
  5021.9  186.85  5035.9  191.84  5043.1  192.62    5122  194.79  5162.8  197.08
  5179.7   197.9  5191.1  199.19  5237.4  203.44  5319.6   205.6  5331.5  206.63
    5361  206.12  5404.5  205.86  5456.3  207.07  5494.2  206.64  5532.7  205.97
#Mann= 8 ,-1 , 0
  3951.5     .04       0  4873.3     .12       0  4989.4     .05       0
  4993.4     .12       0  5162.8     .03       0  5191.1     .12       0
    5361     .05       0  5494.2     .12       0
Bank Sta=4989.4,4993.4
XS Rating Curve= 0 ,0
Exp/Cntr=0.3,0.1

Type RM Length L Ch R = 1 ,13567   ,375,375,375
BEGIN DESCRIPTION:
Mapping XS 14fc1e8c
END DESCRIPTION:
XS GIS Cut Line= 4
       2531351.9     13558474.87      2531497.73     13557667.62
      2531435.23     13557313.46      2531284.84     13556888.22
#Sta/Elev= 30
  4206.1   202.1  4663.3  192.08  4846.2  189.71  4907.1  188.07  4924.5  188.47
  4929.6  187.64  4937.6  187.73  4957.9  184.31    4981  182.42  4981.3  181.92
  4985.3  182.42  4998.6  183.66  5046.8  184.71  5046.9  184.71  5067.8  187.08
  5100.2  187.07  5120.5  186.13  5146.8  186.97  5171.2   188.1  5282.5  189.65
    5396  191.78  5448.1  193.42  5469.3  195.02  5493.8  194.48  5532.9  195.34
  5575.3   196.9  5581.2  197.81  5586.5  197.29  5612.1  197.77  5837.1   203.3
#Mann= 8 ,-1 , 0
  4206.1     .04       0    4981     .04       0  4985.3     .04       0
  5046.8     .05       0  5046.9     .04       0  5146.8     .05       0
  5282.5     .12       0    5396     .05       0
Bank Sta=4981,4985.3
XS Rating Curve= 0 ,0
Exp/Cntr=0.3,0.1

Type RM Length L Ch R = 1 ,13192   ,482,482,482
BEGIN DESCRIPTION:
NORTH FORK CREEK 28.0
END DESCRIPTION:
XS GIS Cut Line= 3
        2531775.     13558075.02        2531825.       13557725.
        2531625.     13556974.99
#Sta/Elev= 30
  4646.5  200.18  4706.1  194.87  4727.3  192.79  4777.8  190.19  4787.9  190.59
  4854.8  188.25  4868.8  188.21  4878.9  187.31  4904.4  187.23  4959.7  185.75
  4969.8  185.01    4990  182.04  5003.7  181.77  5008.3  180.97  5008.6  180.47
  5012.3  180.47  5012.6  180.97  5017.5  181.75  5022.7  181.18  5031.1  183.52
  5051.8  184.19    5058  184.94  5186.4   186.8  5341.6  187.16  5429.9  189.28
  5603.6  196.14    5621  197.39  5726.4  200.36  5748.7  201.39  5776.3  202.42
#Mann= 11 ,-1 , 0
  4646.5     .05       0  4706.1     .12       0  4854.8    .013       0
  4904.4     .12       0  5003.7     .05       0  5008.3     .05       0
  5012.6     .05       0    5058    .013       0  5429.9     .12       0
  5726.4     .05       0  5748.7    .013       0
Bank Sta=5008.3,5012.6
XS Rating Curve= 0 ,0
Exp/Cntr=0.3,0.1

Type RM Length L Ch R = 1 ,12710   ,468,468,468
BEGIN DESCRIPTION:
NORTH FORK CREEK 27.0
END DESCRIPTION:
XS GIS Cut Line= 3
      2532474.99     13558024.98        2532275.       13557625.
      2531725.02     13556875.03
#Sta/Elev= 30
  4552.4  197.67  4738.1  189.11  4879.4  185.36  4932.5  183.34  4954.9  181.19
  4968.8  181.47  5013.1  179.83  5027.8  180.23    5034  178.95  5034.3  178.45
  5038.4  178.95  5049.2  181.86  5057.1  182.77  5086.4   184.1  5248.4  184.76
    5450  188.63  5500.1  190.85  5571.1   192.3  5594.3  193.69  5686.1  196.03
  5700.8  195.71    5707  196.54  5730.1  196.35  5757.2  198.81  5765.6  197.76
  5771.8  199.04  5780.3  198.48  5786.5  199.33  5823.6  200.29  5929.6   203.4
#Mann= 6 ,-1 , 0
  4552.4     .12       0  4738.1     .05       0    5034     .05       0
  5038.4     .05       0  5248.4     .12       0  5823.6     .05       0
Bank Sta=5034,5038.4
XS Rating Curve= 0 ,0
Exp/Cntr=0.3,0.1

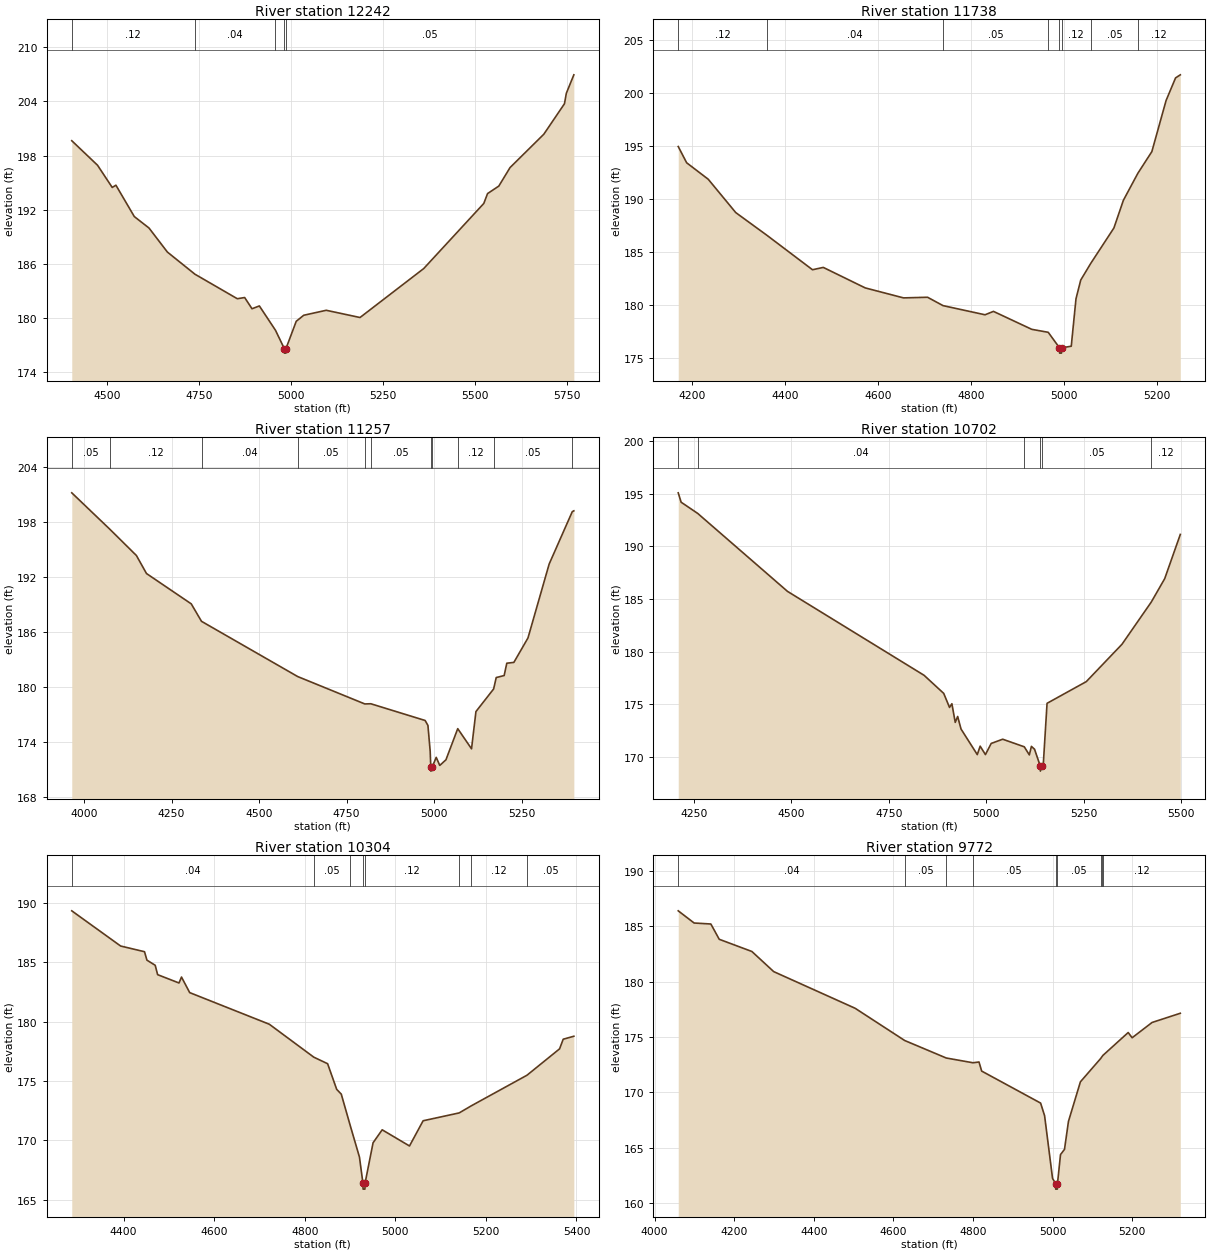
Type RM Length L Ch R = 1 ,12242   ,504,504,504
BEGIN DESCRIPTION:
NORTH FORK CREEK 26.0
END DESCRIPTION:
XS GIS Cut Line= 3
        2532675.     13558025.02        2532675.       13557425.
      2532524.99     13556674.97
#Sta/Elev= 30
  4404.6  199.64  4474.6  196.93  4514.6  194.47  4524.6  194.72  4574.6  191.25
  4614.6  189.98  4664.6  187.32  4739.5  184.87  4854.6  182.16  4874.6  182.29
  4894.6  181.05  4914.6  181.36  4958.4  178.67  4982.4  176.64  4982.7  176.14
  4986.6  176.14  4986.9  176.64  5014.8  179.66  5035.2  180.33  5096.4  180.88
  5188.2  180.08  5361.5   185.5  5524.7   192.7  5534.9  193.79  5565.5  194.62
  5596.1  196.67  5687.9  200.36    5744  203.73  5749.1  204.89  5769.5  206.93
#Mann= 5 ,-1 , 0
  4404.6     .12       0  4739.5     .04       0  4958.4     .05       0
  4982.4     .05       0  4986.9     .05       0
Bank Sta=4982.4,4986.9
XS Rating Curve= 0 ,0
Exp/Cntr=0.3,0.1

Type RM Length L Ch R = 1 ,11738   ,481,481,481
BEGIN DESCRIPTION:
NORTH FORK CREEK 25.0
END DESCRIPTION:
XS GIS Cut Line= 3
      2532774.99     13557925.05        2532975.       13557125.
        2532925.     13556875.02
#Sta/Elev= 30
  4170.4  194.94  4188.5  193.41  4234.9  191.86  4294.1  188.72  4360.9  186.59
  4459.1  183.34  4482.3  183.56  4572.5  181.63  4654.9  180.69  4706.5  180.75
  4739.9  179.96  4830.1   179.1  4848.2  179.42  4930.6  177.73    4966  177.45
  4990.2  175.99  4990.5  175.49  4994.4  175.49  4994.8  175.99  5015.5  176.14
  5025.7  180.61  5035.9  182.37  5057.6  183.95  5107.2  187.27  5127.6  189.88
  5158.7  192.42  5188.8  194.46  5219.4  199.27  5239.8   201.4    5250  201.69
#Mann= 8 ,-1 , 0
  4170.4     .12       0  4360.9     .04       0  4739.9     .05       0
    4966     .12       0  4990.2     .05       0  4994.8     .12       0
  5057.6     .05       0  5158.7     .12       0
Bank Sta=4990.2,4994.8
XS Rating Curve= 0 ,0
Exp/Cntr=0.3,0.1

Type RM Length L Ch R = 1 ,11257   ,555,555,555
BEGIN DESCRIPTION:
NORTH FORK CREEK 24.0
END DESCRIPTION:
XS GIS Cut Line= 3
      2532724.98     13558075.02        2533375.       13557275.
        2533425.     13556875.02
#Sta/Elev= 30
  3964.9  201.14  4073.6  197.18  4149.5  194.32  4178.3  192.36  4306.1  189.06
  4335.4  187.16  4610.1  181.15  4801.8  178.17  4818.9  178.19  4974.1  176.37
  4982.1  175.83  4988.5  173.03  4990.2  171.36  4990.5  170.86  4994.8  171.36
  5005.8  172.36  5015.9  171.48  5033.5  172.09  5067.2  175.48  5106.6  173.29
  5119.2  177.34  5169.7   179.8  5177.1  181.04  5199.8  181.26  5207.3   182.6
  5227.5  182.69  5267.8  185.35  5328.3  193.39  5394.3  199.09  5398.8  199.18
#Mann= 11 ,-1 , 0
  3964.9     .05       0  4073.6     .12       0  4335.4     .04       0
  4610.1     .05       0  4801.8     .04       0  4818.9     .05       0
  4990.2     .05       0  4994.8     .05       0  5067.2     .12       0
  5169.7     .05       0  5394.3     .04       0
Bank Sta=4990.2,4994.8
XS Rating Curve= 0 ,0
Exp/Cntr=0.3,0.1

Type RM Length L Ch R = 1 ,10702   ,398,398,398
BEGIN DESCRIPTION:
NORTH FORK CREEK 23.0
END DESCRIPTION:
XS GIS Cut Line= 3
      2533274.99     13558125.01        2533775.       13557425.
      2533924.98     13557025.04
#Sta/Elev= 30
  4209.8  195.07  4217.2  194.18  4259.9  193.11    4490  185.71  4840.2  177.74
  4890.6  176.02  4905.4  174.69  4911.5  175.04  4920.1  173.27  4926.3  173.83
  4934.9  172.64  4976.6  170.21    4984  171.01  4997.5  170.21  5012.3  171.27
  5041.8  171.67  5097.1  170.95  5110.1  170.18  5115.4  170.99  5123.4  170.72
    5138  169.14  5138.4  168.64  5142.7  169.14  5145.7  169.19  5155.5  175.08
  5256.1  177.14  5347.7  180.69  5422.8   184.7  5457.2  186.92  5497.2  191.12
#Mann= 6 ,-1 , 0
  4209.8     .05       0  4259.9     .04       0  5097.1     .05       0
    5138     .04       0  5142.7     .05       0  5422.8     .12       0
Bank Sta=5138,5142.7
XS Rating Curve= 0 ,0
Exp/Cntr=0.3,0.1

Type RM Length L Ch R = 1 ,10304   ,532,532,532
BEGIN DESCRIPTION:
Mapping XS d7573d53
END DESCRIPTION:
XS GIS Cut Line= 3
      2533836.28     13558256.14      2534049.81     13557756.16
       2534101.9     13557193.64
#Sta/Elev= 30
  4285.6  189.31  4393.5  186.35  4446.2  185.87  4451.6  185.16  4469.8  184.73
  4475.2  183.94  4522.4  183.24  4527.9  183.74    4546  182.43  4721.8  179.77
    4820     177  4850.5  176.45  4870.6  174.29  4880.7  173.89    4900  171.31
  4920.8   168.6  4928.5   166.4  4928.9   165.9  4932.9   165.9  4933.2   166.4
  4950.9   169.8    4971  170.89  5031.3  169.53  5061.4  171.65    5141  172.31
  5167.9  172.91  5290.7  175.48  5362.7   177.7  5370.7  178.51  5394.2  178.76
#Mann= 8 ,-1 , 0
  4285.6     .04       0    4820     .05       0    4900     .12       0
  4928.5     .05       0  4933.2     .12       0    5141     .05       0
  5167.9     .12       0  5290.7     .05       0
Bank Sta=4928.5,4933.2
XS Rating Curve= 0 ,0
Exp/Cntr=0.3,0.1

Type RM Length L Ch R = 1 ,9772    ,246,246,246
BEGIN DESCRIPTION:
Mapping XS 8887e58e
END DESCRIPTION:
XS GIS Cut Line= 3
      2534211.26     13558422.87       2534476.9     13557615.54
      2534466.48     13557204.08
#Sta/Elev= 30
  4059.6   186.4  4099.5   185.3  4141.6  185.21  4162.6  183.83  4244.6  182.73
  4299.5  180.91  4504.1   177.6  4628.6  174.69    4733  173.11  4800.2  172.68
  4815.3  172.75    4822  171.93  4970.1  169.04  4980.1   167.9  5000.1  162.24
  5007.7  161.77    5008  161.27  5012.1  161.27  5012.5  161.77  5020.1  164.39
  5030.1  164.86  5040.1  167.39  5070.1  170.96  5120.9  173.06  5123.7   173.2
  5126.5  173.34  5190.1  175.41  5200.1  174.94  5250.2  176.32  5321.1  177.15
#Mann= 9 ,-1 , 0
  4059.6     .04       0  4628.6     .05       0    4733     .04       0
  4800.2     .05       0  5007.7     .05       0  5012.5     .05       0
  5120.9     .12       0  5123.7     .05       0  5126.5     .12       0
Bank Sta=5007.7,5012.5
XS Rating Curve= 0 ,0
Exp/Cntr=0.3,0.1

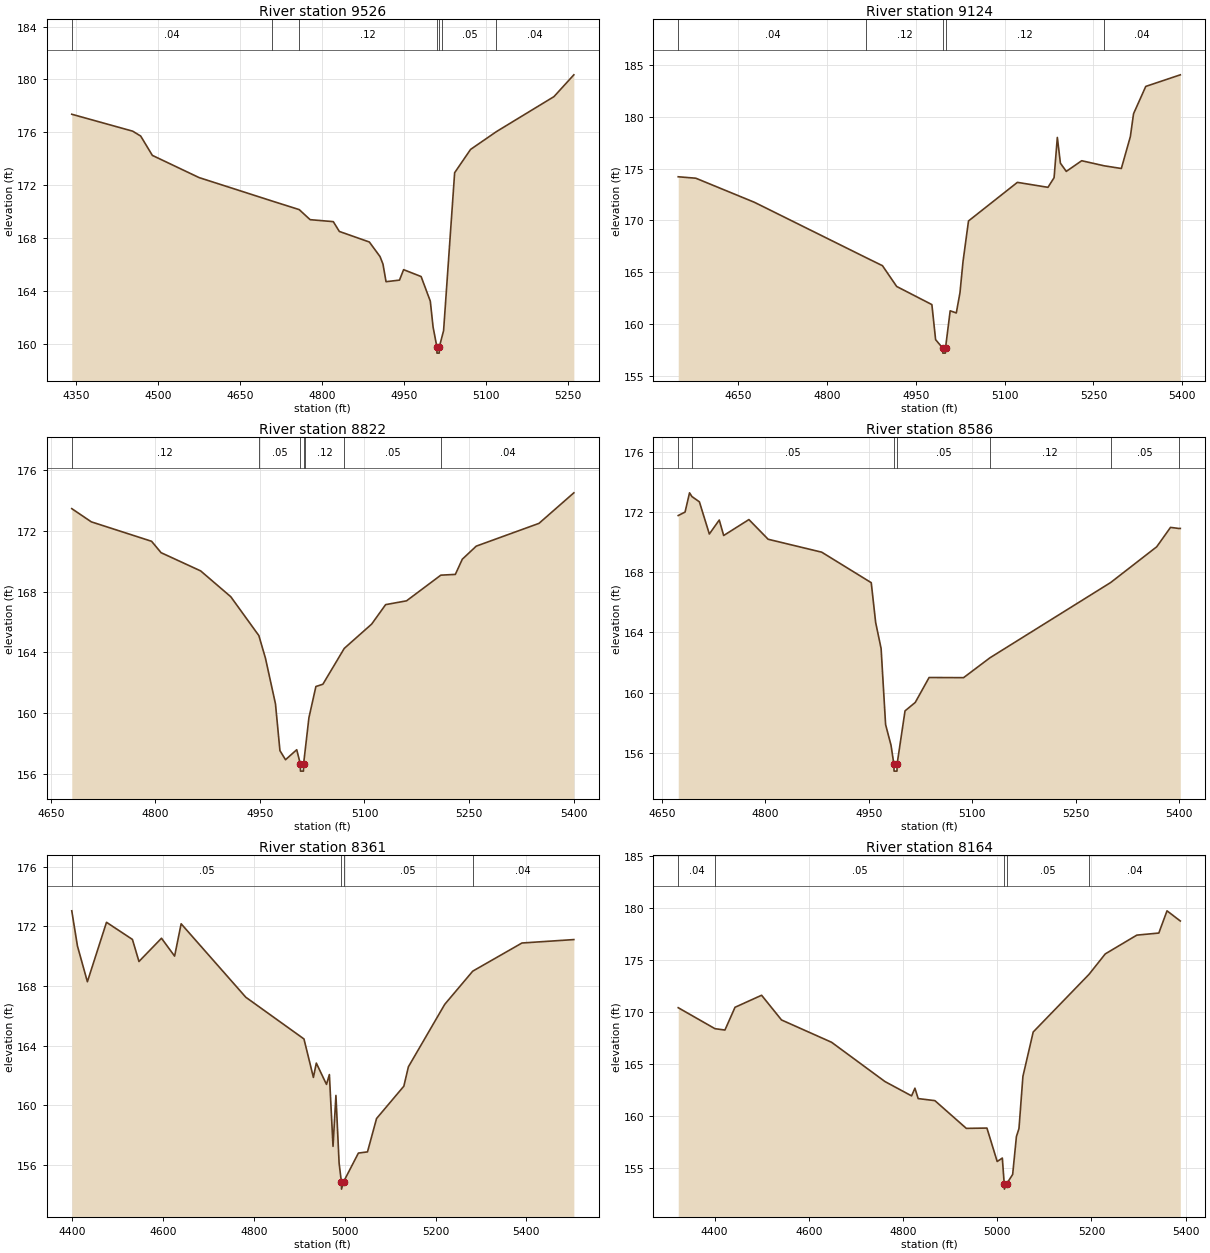
Type RM Length L Ch R = 1 ,9526    ,402,402,402
BEGIN DESCRIPTION:
Mapping XS c906b339
END DESCRIPTION:
XS GIS Cut Line= 3
      2534490.36     13558142.95      2534719.52     13557531.87
      2534754.11     13557268.97
#Sta/Elev= 30
  4342.7  177.37  4454.1  176.09  4468.7  175.72    4490  174.26  4575.5  172.58
  4708.8  170.81  4758.5  170.16  4778.4   169.4  4820.8  169.25  4831.8  168.51
  4886.7  167.71  4906.2  166.61  4911.6  166.04  4917.2  164.71  4941.8  164.83
  4949.3  165.62  4981.3   165.1  4998.1  163.24  5003.2  161.28    5010  159.81
  5010.3  159.31  5014.4  159.31  5014.8  159.81  5020.1  160.65  5022.4  161.01
  5042.6  172.95  5071.7  174.71  5119.1  176.06  5224.1   178.7  5260.5  180.35
#Mann= 7 ,-1 , 0
  4342.7     .04       0  4708.8     .05       0  4758.5     .12       0
    5010     .05       0  5014.8     .12       0  5020.1     .05       0
  5119.1     .04       0
Bank Sta=5010,5014.8
XS Rating Curve= 0 ,0
Exp/Cntr=0.3,0.1

Type RM Length L Ch R = 1 ,9124    ,302,302,302
BEGIN DESCRIPTION:
Mapping XS 57f398a1
END DESCRIPTION:
XS GIS Cut Line= 3
      2534750.79     13558170.73      2534986.88     13557820.07
      2535090.64     13557408.48
#Sta/Elev= 30
  4549.4  174.21  4579.1  174.07  4678.1  171.74  4866.9  166.38    4894  165.62
    4918  163.61  4977.4  161.86  4983.7  158.47  4995.5  157.67  4995.9  157.17
  5000.1  157.17  5000.4  157.67  5008.3  161.26  5018.6  161.05  5024.8     163
  5029.9     166  5039.2  169.94  5121.7  173.67  5173.3  173.19  5183.6  174.12
  5189.1  178.01  5194.3  175.52  5204.2  174.73  5230.2  175.76  5268.1  175.27
  5297.1  175.01  5312.3  178.09  5317.7   180.3  5338.3  182.94  5396.6  184.06
#Mann= 5 ,-1 , 0
  4549.4     .04       0  4866.9     .12       0  4995.5     .05       0
  5000.4     .12       0  5268.1     .04       0
Bank Sta=4995.5,5000.4
XS Rating Curve= 0 ,0
Exp/Cntr=0.3,0.1

Type RM Length L Ch R = 1 ,8822    ,236,236,236
BEGIN DESCRIPTION:
NORTH FORK CREEK 19.0
END DESCRIPTION:
XS GIS Cut Line= 3
      2534974.99     13558275.02        2535175.       13558025.
        2535175.     13557624.98
#Sta/Elev= 30
  4680.1  173.47  4708.1   172.6  4794.6  171.32  4808.2  170.57    4865  169.37
  4908.2  167.67  4948.5  165.11  4957.9  163.63  4972.3  160.62  4978.7  157.54
  4986.7  156.94  5002.8   157.6  5007.8  156.69  5008.2  156.19  5012.4  156.19
  5012.7  156.69  5015.2  157.68  5020.3  159.71  5030.3  161.76  5040.3  161.91
    5071  164.27  5110.3  165.87  5130.3  167.15  5160.3   167.4  5209.5  169.09
  5230.3  169.14  5240.3  170.14  5260.3     171  5350.3   172.5  5400.3  174.51
#Mann= 7 ,-1 , 0
  4680.1     .12       0  4948.5     .05       0  5007.8     .05       0
  5012.7     .05       0  5015.2     .12       0    5071     .05       0
  5209.5     .04       0
Bank Sta=5007.8,5012.7
XS Rating Curve= 0 ,0
Exp/Cntr=0.3,0.1

Type RM Length L Ch R = 1 ,8586    ,225,225,225
BEGIN DESCRIPTION:
Mapping XS a8237b03
END DESCRIPTION:
XS GIS Cut Line= 3
      2535123.96     13558327.63      2535379.17     13558119.29
      2535392.19     13557720.85
#Sta/Elev= 30
  4673.7  171.78  4683.6  172.01  4690.1  173.29  4693.6  173.04  4704.4  172.69
  4718.8  170.55  4733.2  171.48  4739.6  170.45  4776.2  171.51  4804.1   170.2
  4881.8  169.34  4953.6  167.31    4960  164.66  4967.9  162.93  4974.4  157.87
  4982.3  156.49  4986.3  155.27  4986.7  154.77  4990.9  154.77  4991.2  155.27
  5002.6  158.78  5017.4  159.34  5037.5     161  5087.5  160.99  5125.7  162.31
  5300.8  167.32  5367.6   169.7  5387.6  170.99  5399.4  170.92  5401.8  170.92
#Mann= 7 ,-1 , 0
  4673.7     .04       0  4693.6     .05       0  4986.3     .05       0
  4991.2     .05       0  5125.7     .12       0  5300.8     .05       0
  5399.4     .04       0
Bank Sta=4986.3,4991.2
XS Rating Curve= 0 ,0
Exp/Cntr=0.3,0.1

Type RM Length L Ch R = 1 ,8361    ,197,197,197
BEGIN DESCRIPTION:
Mapping XS 85819047
END DESCRIPTION:
XS GIS Cut Line= 3
      2535226.87     13558594.74       2535601.9     13558125.96
      2535617.52     13557620.74
#Sta/Elev= 30
  4398.8  173.04  4411.3  170.68  4433.2  168.28  4475.3  172.27  4532.4  171.12
  4546.8  169.64  4596.4   171.2  4625.3     170  4639.7  172.17  4782.1  167.24
  4910.2  164.44    4931  161.86  4937.4  162.82  4959.8  161.39  4966.2  162.05
  4974.2  157.23  4980.6  160.65  4987.6  156.11  4992.5  154.86  4992.9  154.36
  4997.5  154.86  5030.1  156.78  5050.1  156.86  5070.1   159.1  5130.2  161.27
  5140.2  162.57  5220.2  166.76  5281.9  168.99  5390.3  170.88  5504.6  171.11
#Mann= 4 ,-1 , 0
  4398.8     .05       0  4992.5     .05       0  4997.5     .05       0
  5281.9     .04       0
Bank Sta=4992.5,4997.5
XS Rating Curve= 0 ,0
Exp/Cntr=0.3,0.1

Type RM Length L Ch R = 1 ,8164    ,270,270,270
BEGIN DESCRIPTION:
Mapping XS 4e283dd3
END DESCRIPTION:
XS GIS Cut Line= 3
      2535342.71     13558582.84      2535743.75     13558163.56
      2535938.68     13557719.13
#Sta/Elev= 30
    4323  170.41    4401  168.39  4422.1  168.26  4443.5  170.45  4499.9  171.61
  4542.2  169.23  4648.5  167.08  4761.7   163.3  4818.2  161.92  4825.3  162.66
  4832.2  161.66  4867.7  161.46  4934.4  158.79  4978.1  158.82  4999.9   155.6
  5010.8  155.93  5014.8  153.44  5015.2  152.94  5019.8  153.44  5032.7  154.35
  5040.7  158.01  5046.1  158.77  5054.5   163.8  5076.3  168.07  5194.9  173.63
  5229.2  175.59  5296.2   177.4  5342.9   177.6  5360.3  179.74  5388.5  178.76
#Mann= 5 ,-1 , 0
    4323     .04       0    4401     .05       0  5014.8     .05       0
  5019.8     .05       0  5194.9     .04       0
Bank Sta=5014.8,5019.8
XS Rating Curve= 0 ,0
Exp/Cntr=0.3,0.1

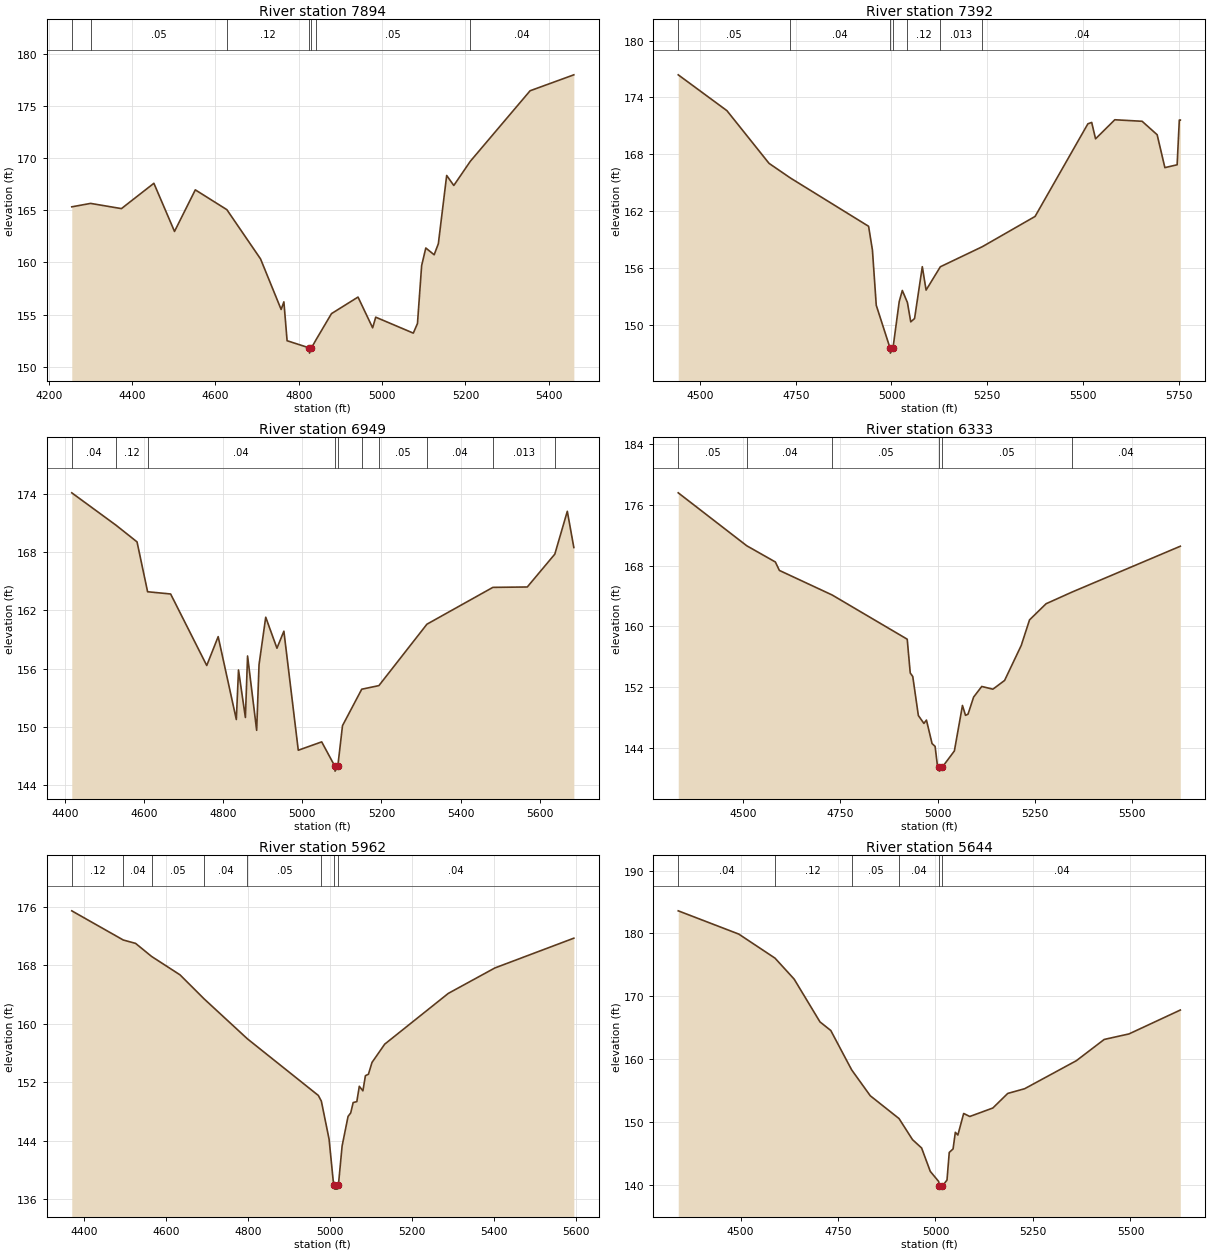
Type RM Length L Ch R = 1 ,7894    ,502,502,502
BEGIN DESCRIPTION:
Mapping XS ae29a673
END DESCRIPTION:
XS GIS Cut Line= 3
      2535502.95     13558750.94      2536002.94     13558162.41
      2536023.77     13557730.15
#Sta/Elev= 30
  4255.1  165.34  4300.3  165.67  4374.3  165.17  4452.2   167.6  4501.7  162.98
  4551.6  166.97  4627.3  165.07  4708.2  160.34  4757.6  155.49  4764.2  156.22
  4771.9  152.49  4825.3   151.8  4825.7   151.3  4830.3   151.8  4841.3  152.58
  4878.4  155.09  4942.1  156.68  4977.2  153.73  4984.6  154.75  5074.8  153.22
  5084.8  154.14  5094.8   159.7  5104.8  161.39  5124.9  160.74  5134.9   161.8
  5154.9  168.35    5172  167.39  5211.6  169.71  5355.1  176.48  5460.1  178.01
#Mann= 7 ,-1 , 0
  4255.1     .04       0  4300.3     .05       0  4627.3     .12       0
  4825.3     .05       0  4830.3     .12       0  4841.3     .05       0
  5211.6     .04       0
Bank Sta=4825.3,4830.3
XS Rating Curve= 0 ,0
Exp/Cntr=0.3,0.1

Type RM Length L Ch R = 1 ,7392    ,443,443,443
BEGIN DESCRIPTION:
Mapping XS eca166dd
END DESCRIPTION:
XS GIS Cut Line= 3
      2536237.31     13559032.17       2536226.9     13558443.66
      2536148.77      13557724.9
#Sta/Elev= 30
  4442.9  176.39  4570.1  172.61  4680.1  167.05  4735.8  165.51  4940.2  160.41
  4950.2  157.91  4960.2  152.08  4996.5  147.53    4997  147.03  5003.8  147.53
  5020.2  152.47  5028.3  153.64  5041.6  152.37  5050.3  150.33  5060.3  150.68
  5080.5  156.15  5090.4  153.68  5127.6  156.14  5237.4  158.26  5375.1  161.45
    5513  171.22    5523  171.37  5533.1  169.64  5583.4  171.65  5654.7  171.49
    5694  170.07  5714.2   166.6  5746.2   166.9  5751.9  171.62  5754.5  171.62
#Mann= 7 ,-1 , 0
  4442.9     .05       0  4735.8     .04       0  4996.5     .04       0
  5003.8     .04       0  5041.6     .12       0  5127.6    .013       0
  5237.4     .04       0
Bank Sta=4996.5,5003.8
XS Rating Curve= 0 ,0
Exp/Cntr=0.3,0.1

Type RM Length L Ch R = 1 ,6949    ,616,616,616
BEGIN DESCRIPTION:
Mapping XS d4f547a5
END DESCRIPTION:
XS GIS Cut Line= 3
      2536825.87     13558844.74      2536570.65     13558292.62
      2536232.12     13557724.94
#Sta/Elev= 30
  4417.3  174.08  4529.1  170.75  4582.3  169.03    4609   163.9  4667.2  163.67
  4758.5  156.31  4787.4  159.28  4833.3  150.75  4838.8  155.85  4856.2  150.96
  4861.7  157.29  4884.7  149.64  4890.7   156.4  4907.6  161.28    4936  158.09
  4953.5  159.84  4989.9  147.59  5049.1  148.45  5082.4  145.94  5082.9  145.44
  5089.8  145.94  5101.7  150.12  5150.3  153.87  5193.7  154.24  5315.1  160.56
  5481.8  164.35  5568.8  164.39  5638.4  167.77    5670  172.18  5686.5  168.45
#Mann= 10 ,-1 , 0
  4417.3     .04       0  4529.1     .12       0    4609     .04       0
  5082.4     .04       0  5089.8     .04       0  5150.3     .12       0
  5193.7     .05       0  5315.1     .04       0  5481.8    .013       0
  5638.4     .04       0
Bank Sta=5082.4,5089.8
XS Rating Curve= 0 ,0
Exp/Cntr=0.3,0.1

Type RM Length L Ch R = 1 ,6333    ,371,371,371
BEGIN DESCRIPTION:
Mapping XS f18a03d2
END DESCRIPTION:
XS GIS Cut Line= 4
      2537133.15     13558516.58      2537018.56     13558068.66
       2536789.4     13557792.62      2536393.55     13557542.61
#Sta/Elev= 30
    4334  177.57    4510  170.61  4583.4  168.48  4593.8  167.37  4729.3  164.14
    4922  158.33  4929.8  153.89  4936.3  153.42  4950.6   148.3  4964.9  147.26
  4971.4   147.7  4985.8  144.61  4993.6  144.25  5000.1   141.5  5004.2  141.49
  5004.7  140.99  5011.7  141.49  5043.1  143.64  5063.9  149.62  5071.7  148.32
  5078.2  148.48  5092.5  150.72  5113.4  152.12    5142  151.76  5172.1  152.91
  5214.9  157.52  5236.1  160.87  5278.6  162.99    5345  164.52  5623.3  170.55
#Mann= 6 ,-1 , 0
    4334     .05       0    4510     .04       0  4729.3     .05       0
  5004.2     .05       0  5011.7     .05       0    5345     .04       0
Bank Sta=5004.2,5011.7
XS Rating Curve= 0 ,0
Exp/Cntr=0.3,0.1

Type RM Length L Ch R = 1 ,5962    ,318,318,318
BEGIN DESCRIPTION:
Mapping XS eb543456
END DESCRIPTION:
XS GIS Cut Line= 4
      2537476.91     13558047.85       2537289.4     13557761.37
       2536976.9     13557547.83      2536488.66     13557417.98
#Sta/Elev= 30
  4369.5  175.43  4495.3  171.44  4525.3  170.98  4564.5  169.19  4633.8  166.68
  4693.3  163.36  4798.6  157.92  4971.6  150.19    4979  149.41  4997.9   144.2
  5007.9  138.55    5011  137.88  5011.5  137.38  5018.1  137.38  5018.6  137.88
  5020.9  138.07  5029.7  143.28  5044.2  147.32  5050.7   147.8  5056.7  149.22
  5065.6  149.34  5071.7  151.44  5080.5  150.82  5086.6  152.89    5094  153.09
  5102.7   154.7  5133.7   157.2    5289  164.14  5402.8  167.62  5595.6  171.69
#Mann= 8 ,-1 , 0
  4369.5     .12       0  4495.3     .04       0  4564.5     .05       0
  4693.3     .04       0  4798.6     .05       0    4979     .04       0
    5011     .04       0  5018.6     .04       0
Bank Sta=5011,5018.6
XS Rating Curve= 0 ,0
Exp/Cntr=0.3,0.1

Type RM Length L Ch R = 1 ,5644    ,260,260,260
BEGIN DESCRIPTION:
Mapping XS 57bc2f4c
END DESCRIPTION:
XS GIS Cut Line= 4
      2537768.59     13557750.98      2537497.73     13557506.16
      2537138.36     13557292.62      2536643.59     13557193.67
#Sta/Elev= 30
  4340.2   183.6  4495.4   179.9  4588.4  176.07  4637.4  172.74  4703.8  165.92
  4731.4  164.56    4785  158.29  4832.7  154.17  4906.5  150.54  4941.1  147.18
  4964.4  145.86  4986.6  142.14  5008.1  140.53  5010.1  139.81  5010.6  139.31
  5017.7  139.81  5029.5  140.75  5035.3  145.15  5045.1  145.71  5050.9  148.35
  5057.4  147.92  5072.3  151.35  5087.9  150.87  5147.1  152.22  5185.3  154.54
  5228.7  155.29  5361.3  159.75  5432.7  163.13  5496.3  164.01  5627.9  167.81
#Mann= 6 ,-1 , 0
  4340.2     .04       0  4588.4     .12       0    4785     .05       0
  4906.5     .04       0  5010.1     .04       0  5017.7     .04       0
Bank Sta=5010.1,5017.7
XS Rating Curve= 0 ,0
Exp/Cntr=0.3,0.1