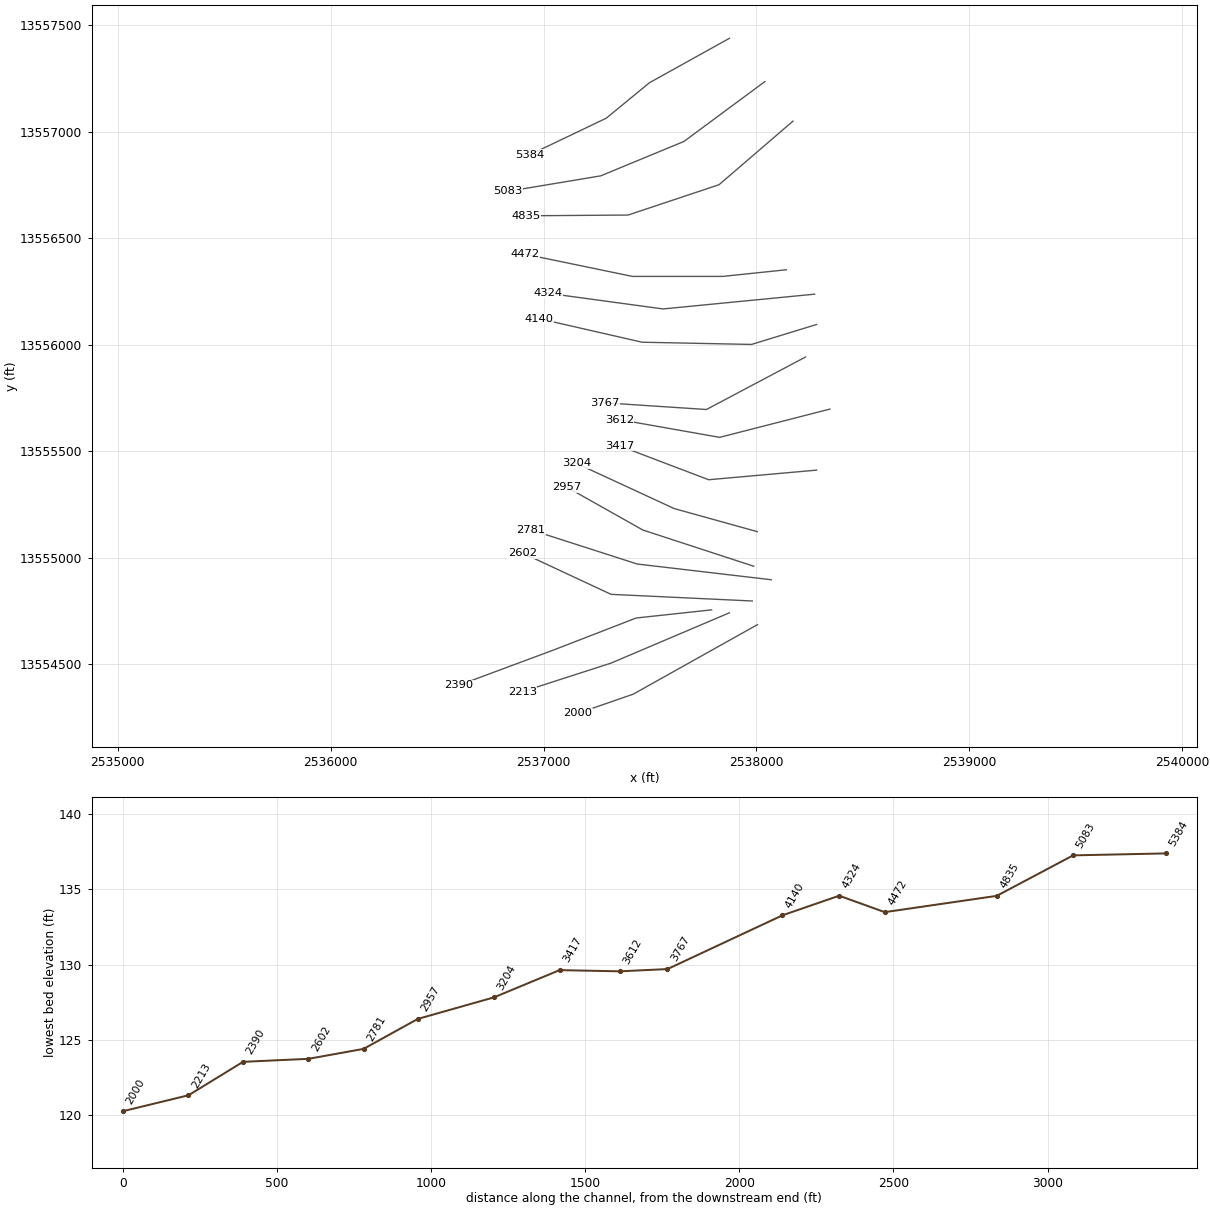
HEC-RAS study NORTH FORK CREEK.prj: NORTH FORK CREEK Base Level Engineering

--- NORTH FORK CREEK.g01 (geometry) --- (continued)

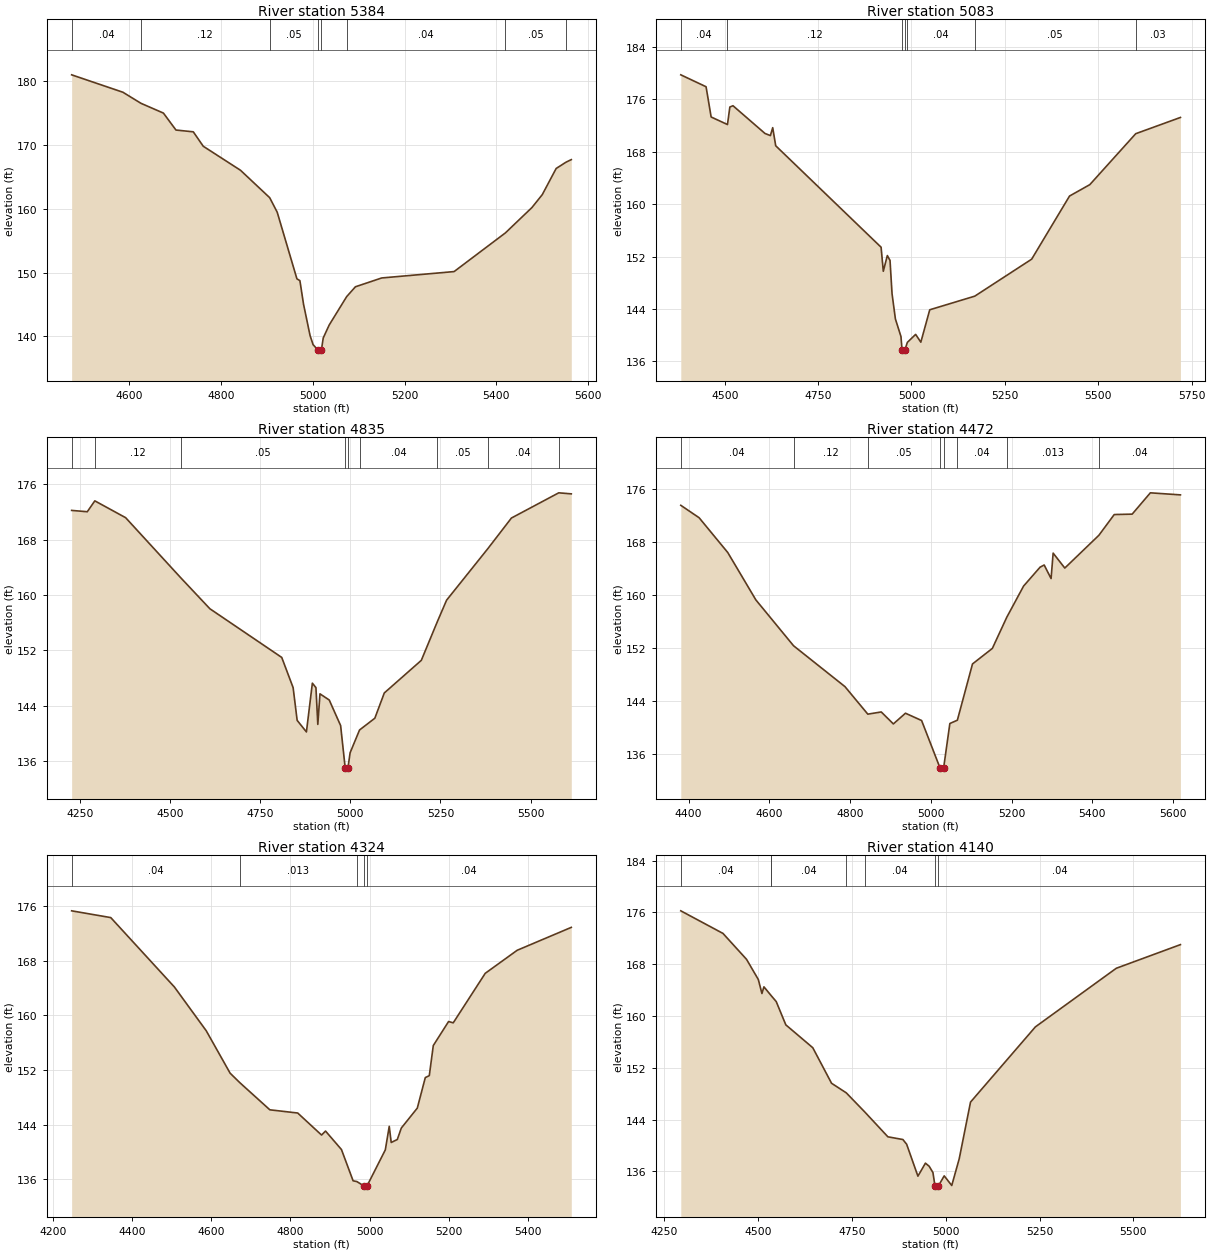
Type RM Length L Ch R = 1 ,5384    ,301,301,301
BEGIN DESCRIPTION:
Mapping XS a9cc7074
END DESCRIPTION:
XS GIS Cut Line= 4
      2537872.75     13557438.47      2537497.73     13557230.12
      2537294.61     13557063.46      2536935.25     13556891.59
#Sta/Elev= 30
  4473.8  181.03  4585.6   178.3  4625.1  176.56    4674  175.03  4701.4  172.37
  4739.2  172.09  4760.9  169.83  4842.2  166.06  4905.9  161.76  4922.3  159.48
  4965.3  149.03  4971.8  148.75  4979.7  145.06    4994  140.13  5000.5  138.72
    5011  137.88  5011.5  137.38  5018.7  137.88  5022.7  139.76  5035.7  141.79
  5073.8  146.24    5093  147.79  5150.4  149.17  5308.2  150.17  5420.2  156.24
    5478  160.21  5500.6  162.24  5530.9  166.34  5552.4  167.33  5563.9  167.73
#Mann= 8 ,-1 , 0
  4473.8     .04       0  4625.1     .12       0  4905.9     .05       0
    5011     .05       0  5018.7     .05       0  5073.8     .04       0
  5420.2     .05       0  5552.4     .03       0
Bank Sta=5011,5018.7
XS Rating Curve= 0 ,0
Exp/Cntr=0.3,0.1

Type RM Length L Ch R = 1 ,5083    ,248,248,248
BEGIN DESCRIPTION:
Mapping XS a1b940fe
END DESCRIPTION:
XS GIS Cut Line= 4
       2538039.4     13557235.33      2537659.19     13556954.08
      2537268.56     13556792.62        2536832.     13556719.86
#Sta/Elev= 30
  4382.1  179.75  4449.8  177.93  4463.4  173.31  4507.1  172.16  4513.5  174.83
  4521.9  175.03  4607.5   170.8  4622.1  170.47  4628.3  171.68  4636.3  168.92
  4918.6  153.42  4924.5  149.75  4935.3  152.15  4942.5  151.41  4947.9  146.33
  4956.9  142.47  4971.8  139.78  4974.7  137.75  4975.2  137.25  4982.5  137.75
  4988.9  138.89  5011.1  140.11    5025  138.92  5048.9  143.87  5169.5  145.95
  5321.9   151.6  5423.3  161.24  5477.6  162.98  5600.6  170.76  5720.3  173.24
#Mann= 7 ,-1 , 0
  4382.1     .04       0  4507.1     .12       0  4974.7     .04       0
  4982.5     .12       0  4988.9     .04       0  5169.5     .05       0
  5600.6     .03       0
Bank Sta=4974.7,4982.5
XS Rating Curve= 0 ,0
Exp/Cntr=0.3,0.1

Type RM Length L Ch R = 1 ,4835    ,363,363,363
BEGIN DESCRIPTION:
Mapping XS b571df1c
END DESCRIPTION:
XS GIS Cut Line= 4
      2538171.37     13557049.59      2537824.12     13556750.96
      2537397.04     13556608.59      2536918.94     13556605.13
#Sta/Elev= 30
  4226.7  172.21  4270.1  172.02    4291  173.59  4376.5  171.16  4529.1   162.5
  4610.2  158.01  4809.6  150.98  4841.2  146.62  4852.4  141.89  4878.1  140.22
  4894.6  147.26  4904.5  146.62  4909.7  141.31  4915.7  145.72  4941.4  144.83
    4973  141.14  4985.6  135.06  4986.1  134.56  4993.4  135.06  4999.3  137.21
  5025.5   140.5  5067.9   142.2  5094.2  145.85  5196.9  150.56    5241   156.1
  5266.9  159.24  5381.5  166.69  5446.9  171.11  5578.2  174.75    5613   174.6
#Mann= 9 ,-1 , 0
  4226.7     .05       0    4291     .12       0  4529.1     .05       0
  4985.6     .05       0  4993.4     .05       0  5025.5     .04       0
    5241     .05       0  5381.5     .04       0  5578.2     .05       0
Bank Sta=4985.6,4993.4
XS Rating Curve= 0 ,0
Exp/Cntr=0.3,0.1

Type RM Length L Ch R = 1 ,4472    ,148,148,148
BEGIN DESCRIPTION:
Mapping XS e138348c
END DESCRIPTION:
XS GIS Cut Line= 4
      2538140.12     13556351.65      2537841.48      13556320.4
      2537417.87      13556320.4      2536914.41     13556424.56
#Sta/Elev= 30
  4380.5  173.51  4425.9  171.64  4496.9   166.4  4566.6  159.26  4659.9  152.36
  4787.2  146.21  4843.9  142.06  4877.2  142.39  4907.2  140.59  4937.2   142.2
  4977.2   141.1  5022.7  133.98  5023.2  133.48  5031.8  133.98  5047.2  140.65
  5065.8  141.15  5103.3  149.62  5152.5  151.96  5188.2  156.65  5229.9  161.35
  5270.7  164.19  5280.9  164.52    5298  162.48  5303.1  166.31    5332  164.06
  5416.5     169  5454.5  172.12  5498.9  172.18    5544  175.39  5618.5  175.08
#Mann= 8 ,-1 , 0
  4380.5     .04       0  4659.9     .12       0  4843.9     .05       0
  5022.7     .05       0  5031.8     .05       0  5065.8     .04       0
  5188.2    .013       0  5416.5     .04       0
Bank Sta=5022.7,5031.8
XS Rating Curve= 0 ,0
Exp/Cntr=0.3,0.1

Type RM Length L Ch R = 1 ,4324    ,184,184,184
BEGIN DESCRIPTION:
Mapping XS 5b7f5d6b
END DESCRIPTION:
XS GIS Cut Line= 3
      2538273.37     13556237.07      2537561.53     13556167.62
      2537019.54     13556241.33
#Sta/Elev= 30
  4247.5  175.27  4346.3  174.28  4507.1  164.13  4587.5  157.73  4647.8  151.53
  4672.5  150.13  4748.2  146.17  4818.6   145.7  4878.8  142.48  4888.9  143.06
  4929.1  140.36  4958.5  135.79  4968.2  135.67  4984.9  135.07  4985.4  134.57
    4994  135.07  5039.9  140.31  5049.8  143.75  5054.8  141.39  5070.2  141.83
  5080.3   143.5  5120.7  146.42  5140.9  150.88    5151  151.17  5161.1  155.57
  5199.7  159.08  5211.5  158.89  5292.3  166.13    5373   169.5  5509.7  172.85
#Mann= 5 ,-1 , 0
  4247.5     .04       0  4672.5    .013       0  4968.2     .04       0
  4984.9     .04       0    4994     .04       0
Bank Sta=4984.9,4994
XS Rating Curve= 0 ,0
Exp/Cntr=0.3,0.1

Type RM Length L Ch R = 1 ,4140    ,373,373,373
BEGIN DESCRIPTION:
Mapping XS d5964960
END DESCRIPTION:
XS GIS Cut Line= 4
      2538282.41     13556094.69       2537976.9     13556000.96
      2537463.01     13556011.37      2536978.47     13556122.12
#Sta/Elev= 30
  4294.7  176.25  4407.1  172.76  4469.8  168.76  4501.2  165.64  4510.8  163.48
  4516.1  164.51  4535.9  163.12  4548.8  162.24  4574.4  158.64  4646.2  155.11
  4696.2  149.62  4735.4  148.14  4784.6  145.19  4846.2  141.35  4886.2  140.93
  4896.2   140.2  4926.2  135.27  4946.2  137.28  4956.2   136.8  4966.2  135.83
  4971.6  133.77  4972.1  133.27  4980.8  133.77  4996.2  135.32  5016.3  133.83
  5036.3  137.98  5066.3  146.71  5239.1  158.33  5454.5  167.38  5625.3  171.03
#Mann= 7 ,-1 , 0
  4294.7     .04       0  4535.9    .013       0  4535.9     .04       0
  4735.4     .05       0  4784.6     .04       0  4971.6     .04       0
  4980.8     .04       0
Bank Sta=4971.6,4980.8
XS Rating Curve= 0 ,0
Exp/Cntr=0.3,0.1

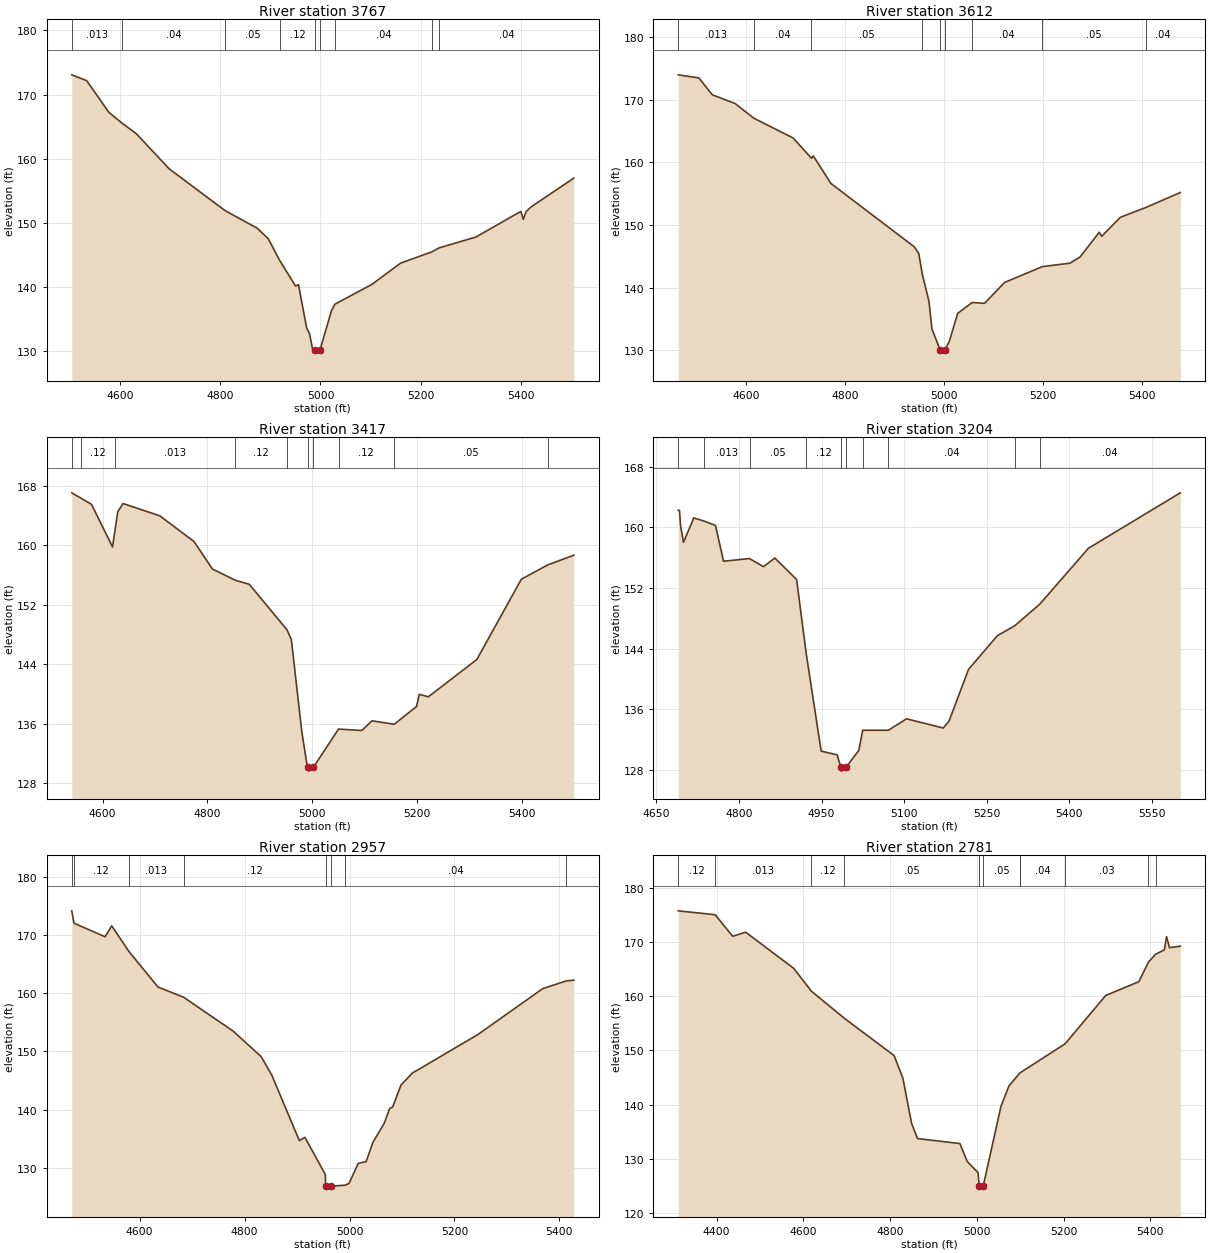
Type RM Length L Ch R = 1 ,3767    ,155,155,155
BEGIN DESCRIPTION:
Mapping XS 3916c71d
END DESCRIPTION:
XS GIS Cut Line= 3
      2538230.37     13555941.93      2537765.09      13555695.4
      2537289.67     13555726.63
#Sta/Elev= 30
  4503.2  173.08  4533.1  172.17  4577.2  167.24  4603.1  165.58  4631.8  163.93
  4697.8  158.43  4809.4  151.92  4873.7  149.17  4895.7  147.54    4919  144.09
  4950.4  140.14  4956.1  140.38  4972.4  133.64  4978.1  132.74  4984.6  130.21
  4989.8   130.2  4990.3   129.7    4999   130.2  5022.1  136.32  5028.7  137.32
  5102.5   140.4  5160.1  143.73  5222.9  145.49    5237   146.1  5310.4  147.79
  5400.3  151.79  5405.3  150.55  5410.7  151.76  5420.7  152.49  5506.2  156.98
#Mann= 9 ,-1 , 0
  4503.2    .013       0  4603.1     .04       0  4809.4     .05       0
    4919     .12       0  4989.8     .05       0    4999     .12       0
  5028.7     .04       0  5222.9     .05       0    5237     .04       0
Bank Sta=4989.8,4999
XS Rating Curve= 0 ,0
Exp/Cntr=0.3,0.1

Type RM Length L Ch R = 1 ,3612    ,195,195,195
BEGIN DESCRIPTION:
Mapping XS 78a0e5d7
END DESCRIPTION:
XS GIS Cut Line= 3
      2538345.28     13555697.41      2537827.09      13555564.6
      2537355.74     13555647.94
#Sta/Elev= 30
    4463  173.96  4504.6  173.47  4531.8  170.77  4577.7  169.39  4615.4  167.05
  4694.9  163.88    4732  160.65  4735.7  161.02  4771.3  156.62  4939.6  146.51
  4948.5  145.47  4955.9  142.09  4969.1  137.84  4975.2  133.41  4991.8  130.05
  4992.3  129.55  5001.1  130.05  5010.2  131.41  5027.2   135.9  5056.5  137.63
  5081.3  137.49  5121.9  140.83    5198  143.35  5253.8  143.91  5274.2  144.89
    5313  148.84    5318   148.2  5355.5  151.22  5407.6  152.81  5476.6  155.18
#Mann= 9 ,-1 , 0
    4463    .013       0  4615.4     .04       0    4732     .05       0
  4955.9     .12       0  4991.8     .05       0  5001.1     .12       0
  5056.5     .04       0    5198     .05       0  5407.6     .04       0
Bank Sta=4991.8,5001.1
XS Rating Curve= 0 ,0
Exp/Cntr=0.3,0.1

Type RM Length L Ch R = 1 ,3417    ,213,213,213
BEGIN DESCRIPTION:
Mapping XS 38a520e2
END DESCRIPTION:
XS GIS Cut Line= 3
      2538282.47     13555410.68      2537775.51     13555365.54
      2537355.41     13555525.25
#Sta/Elev= 30
  4541.2  167.03  4557.9  166.35  4578.8  165.49    4619  159.76  4623.9  162.07
    4629  164.48  4639.1  165.59  4709.3  163.94  4774.5  160.49  4809.7  156.79
  4853.4  155.28    4880  154.74  4951.9  148.64  4960.3  147.33  4980.4  134.88
  4990.4  130.42    4993  130.13  4993.5  129.63  5002.3  130.13  5050.4  135.28
  5094.9  135.09  5114.3  136.39  5156.7  135.93  5199.3  138.31  5204.6  139.95
  5221.9  139.62  5314.4  144.63  5399.4  155.42  5449.7  157.34  5499.6  158.65
#Mann= 10 ,-1 , 0
  4541.2     .04       0  4557.9     .12       0  4623.9    .013       0
  4853.4     .12       0  4951.9     .05       0    4993     .05       0
  5002.3     .05       0  5050.4     .12       0  5156.7     .05       0
  5449.7     .04       0
Bank Sta=4993,5002.3
XS Rating Curve= 0 ,0
Exp/Cntr=0.3,0.1

Type RM Length L Ch R = 1 ,3204    ,247,247,247
BEGIN DESCRIPTION:
Mapping XS 64379f82
END DESCRIPTION:
XS GIS Cut Line= 3
      2538004.27     13555121.61      2537613.62     13555230.12
      2537153.54      13555442.8
#Sta/Elev= 30
  4689.6  162.26  4691.8  162.26    4694  160.15  4699.2  158.04  4717.9  161.26
  4736.9  160.83  4757.3  160.26  4771.9  155.54  4819.1  155.89  4844.5  154.82
  4865.2  155.96  4904.7  153.12    4922  143.42  4949.3  130.46  4978.4  129.97
  4985.1  128.32  4985.6  127.82  4994.5  128.32  5017.8  130.57  5024.8  133.22
  5071.4  133.22  5104.5  134.73  5171.2  133.51  5181.7  134.43  5217.1  141.26
  5269.8  145.73  5300.8     147  5346.5  149.87    5435  157.25  5601.9  164.57
#Mann= 10 ,-1 , 0
  4689.6     .12       0  4736.9    .013       0  4819.1     .05       0
    4922     .12       0  4985.1     .05       0  4994.5     .12       0
  5024.8     .05       0  5071.4     .04       0  5300.8     .05       0
  5346.5     .04       0
Bank Sta=4985.1,4994.5
XS Rating Curve= 0 ,0
Exp/Cntr=0.3,0.1

Type RM Length L Ch R = 1 ,2957    ,176,176,176
BEGIN DESCRIPTION:
Mapping XS 0461f016
END DESCRIPTION:
XS GIS Cut Line= 3
      2537987.29      13554959.3      2537466.48     13555129.43
      2537110.18     13555330.06
#Sta/Elev= 30
  4470.7  174.13  4474.9  172.01  4534.2  169.68  4546.8  171.56  4579.3   167.2
  4635.1  161.05  4683.7  159.32  4778.2   153.5  4831.6  149.12  4851.8  145.96
  4904.4  134.71    4915  135.27  4953.9   128.9  4954.5  126.89    4955  126.39
  4963.9  126.89    4992  127.07  4999.1  127.38  5016.7  130.82  5031.8  131.11
  5044.6  134.42  5066.2  137.69  5076.4  140.21  5082.2  140.48  5098.1  144.24
  5119.8   146.3    5244  152.87  5368.3  160.79  5413.2  162.11  5427.5  162.23
#Mann= 8 ,-1 , 0
  4470.7     .04       0  4474.9     .12       0  4579.3    .013       0
  4683.7     .12       0  4954.5     .04       0  4963.9     .12       0
    4992     .04       0  5413.2     .05       0
Bank Sta=4954.5,4963.9
XS Rating Curve= 0 ,0
Exp/Cntr=0.3,0.1

Type RM Length L Ch R = 1 ,2781    ,179,179,179
BEGIN DESCRIPTION:
Mapping XS 7cca0313
END DESCRIPTION:
XS GIS Cut Line= 3
      2538069.35     13554895.92        2537440.     13554969.71
      2536941.34     13555130.15
#Sta/Elev= 30
  4311.4  175.77  4396.5  175.05    4437  171.07  4466.8  171.83  4577.6  165.16
  4618.6  160.92  4694.5  155.93  4809.1  149.05  4829.3  144.88  4849.4  136.53
  4863.1  133.74  4960.8  132.81  4977.6  129.51  5002.8  127.43    5005   124.9
  5005.5   124.4  5014.4   124.9  5055.4  139.68  5073.9  143.45  5099.1  145.86
  5099.5  145.87  5203.4  151.23    5297  160.15  5373.1  162.68  5395.5   166.3
  5411.9  167.76    5432  168.55  5437.3     171    5444  168.96  5468.9  169.25
#Mann= 11 ,-1 , 0
  4311.4     .12       0  4396.5    .013       0  4618.6     .12       0
  4694.5     .05       0    5005     .05       0  5014.4     .05       0
  5099.1     .12       0  5099.5     .04       0  5203.4     .03       0
  5395.5     .04       0  5411.9     .05       0
Bank Sta=5005,5014.4
XS Rating Curve= 0 ,0
Exp/Cntr=0.3,0.1

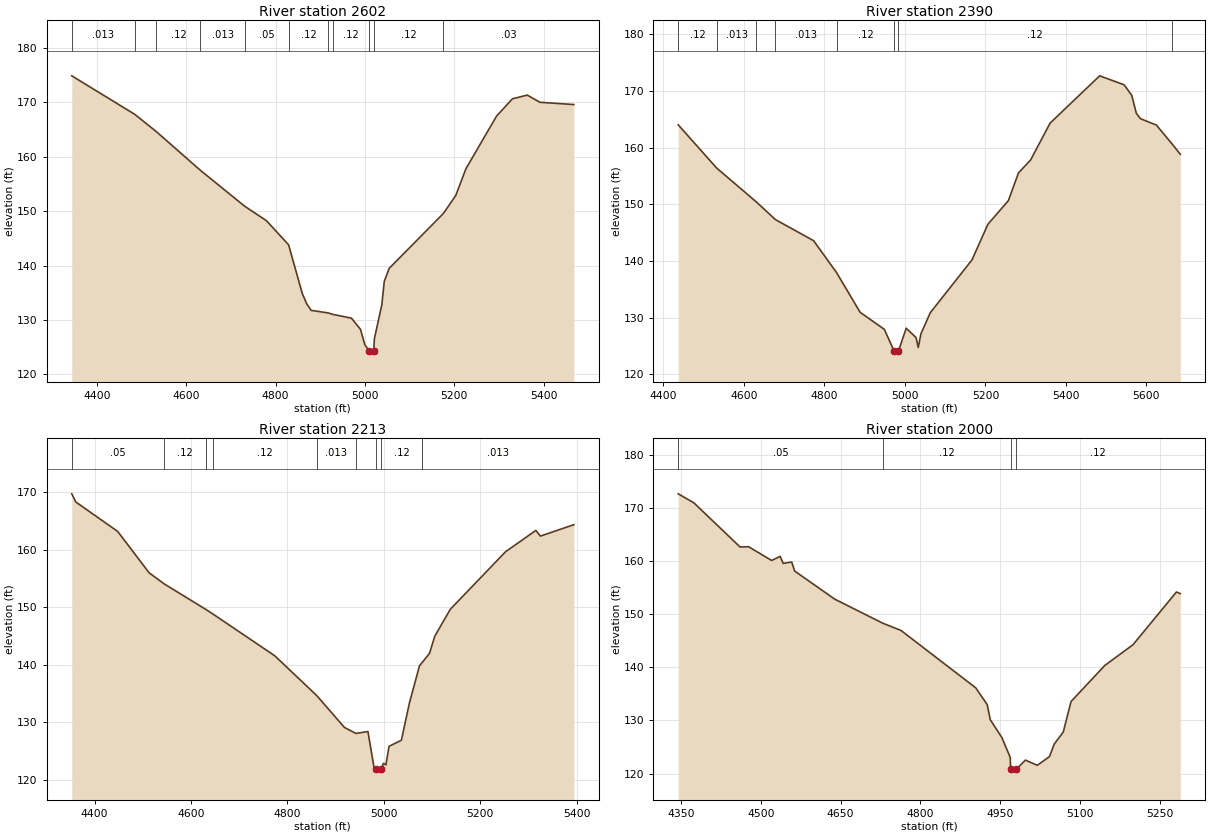
Type RM Length L Ch R = 1 ,2602    ,212,212,212
BEGIN DESCRIPTION:
Mapping XS 0c417b82
END DESCRIPTION:
XS GIS Cut Line= 3
      2537980.33      13554796.1      2537317.17     13554827.34
      2536900.51     13555021.79
#Sta/Elev= 30
  4343.9  174.88  4484.6  167.82  4533.4  164.61    4632   157.5  4730.6  150.94
  4779.7  148.25  4829.2  143.83  4859.8  134.88  4869.8  132.98  4879.8  131.78
  4917.7  131.31  4927.8  131.05  4969.9  130.35    4990   128.3    5000  125.45
  5010.2  124.24  5010.7  123.74  5019.6  124.24  5021.2  126.56  5037.8  132.79
  5043.3   137.1  5054.3   139.5  5175.6  149.59  5203.3  152.89  5226.1  157.81
  5294.7  167.49  5330.2  170.66  5363.3  171.34  5391.7  170.02  5467.6   169.6
#Mann= 11 ,-1 , 0
  4343.9    .013       0  4484.6     .05       0  4533.4     .12       0
    4632    .013       0  4730.6     .05       0  4829.2     .12       0
  4917.7     .05       0  4927.8     .12       0  5010.2     .05       0
  5019.6     .12       0  5175.6     .03       0
Bank Sta=5010.2,5019.6
XS Rating Curve= 0 ,0
Exp/Cntr=0.3,0.1

Type RM Length L Ch R = 1 ,2390    ,177,177,177
BEGIN DESCRIPTION:
Mapping XS 37075e83
END DESCRIPTION:
XS GIS Cut Line= 4
      2537789.38     13554754.43      2537435.23     13554716.23
      2537049.81     13554566.93      2536601.85     13554400.24
#Sta/Elev= 30
  4436.7     164  4532.3  156.37  4630.9  150.39  4678.2  147.28    4773  143.56
  4830.1  137.93  4888.8  130.91  4948.6  127.93  4973.4  124.04  4973.9  123.54
  4983.7  124.04  5003.1  128.11  5027.7  126.45    5033  124.71  5039.8  127.14
    5063  130.85  5166.6  140.17  5206.1  146.45  5257.1  150.64  5282.1  155.52
  5312.4  157.82  5360.7  164.31  5483.8  172.65  5544.5  171.07  5563.5  169.21
  5574.8  166.07  5584.8   165.1  5624.9  163.95  5662.7  160.72  5684.2  158.81
#Mann= 8 ,-1 , 0
  4436.7     .12       0  4532.3    .013       0  4630.9     .05       0
  4678.2    .013       0  4830.1     .12       0  4973.4     .05       0
  4983.7     .12       0  5662.7     .05       0
Bank Sta=4973.4,4983.7
XS Rating Curve= 0 ,0
Exp/Cntr=0.3,0.1

Type RM Length L Ch R = 1 ,2213    ,213,213,213
BEGIN DESCRIPTION:
Mapping XS efb74c33
END DESCRIPTION:
XS GIS Cut Line= 3
       2537872.7     13554740.52      2537317.17     13554504.43
      2536900.02     13554369.97
#Sta/Elev= 30
  4352.5  169.72  4360.9   168.3  4447.8  163.18    4513  155.99  4543.9  154.08
  4630.3  149.64  4646.3  148.77  4773.8  141.55  4860.7  134.65  4918.4  129.09
  4942.1  128.05  4967.1  128.38  4979.4  122.31  4984.8  121.82  4985.3  121.32
  4995.1  121.82  4999.2  122.85  5004.4  122.57  5010.9  125.81  5036.5  126.86
    5053  133.28    5074  139.79  5080.1  140.43    5095     142  5105.8  144.96
  5137.9  149.63  5252.6  159.64  5315.6  163.36    5325  162.37  5394.4  164.35
#Mann= 9 ,-1 , 0
  4352.5     .05       0  4543.9     .12       0  4630.3     .05       0
  4646.3     .12       0  4860.7    .013       0  4942.1     .12       0
  4984.8     .05       0  4995.1     .12       0  5080.1    .013       0
Bank Sta=4984.8,4995.1
XS Rating Curve= 0 ,0
Exp/Cntr=0.3,0.1

Type RM Length L Ch R = 1 ,2000    ,160,160,160
BEGIN DESCRIPTION:
Mapping XS 99f71962
END DESCRIPTION:
XS GIS Cut Line= 3
      2538004.63     13554684.96      2537421.34     13554358.59
      2537160.93     13554268.32
#Sta/Elev= 30
  4344.9  172.74  4374.3  171.04  4461.1  162.72  4477.1  162.77  4520.5  160.17
  4536.5  160.95  4542.2  159.62  4558.2  159.88  4563.9  158.17  4639.2  152.88
  4729.3  148.35  4763.7  146.98  4904.1  136.17  4925.8     133  4931.6  130.15
  4953.3   126.8  4969.2  123.02  4969.8  120.76  4970.3  120.26  4980.1  120.76
  4997.6  122.53    5020  121.55    5043   123.2  5051.8  125.54  5068.8  127.82
  5083.5  133.58    5147  140.38  5199.9  144.28  5281.5  154.22  5288.9  153.93
#Mann= 4 ,-1 , 0
  4344.9     .05       0  4729.3     .12       0  4969.8     .05       0
  4980.1     .12       0
Bank Sta=4969.8,4980.1
XS Rating Curve= 0 ,0
Exp/Cntr=0.3,0.1