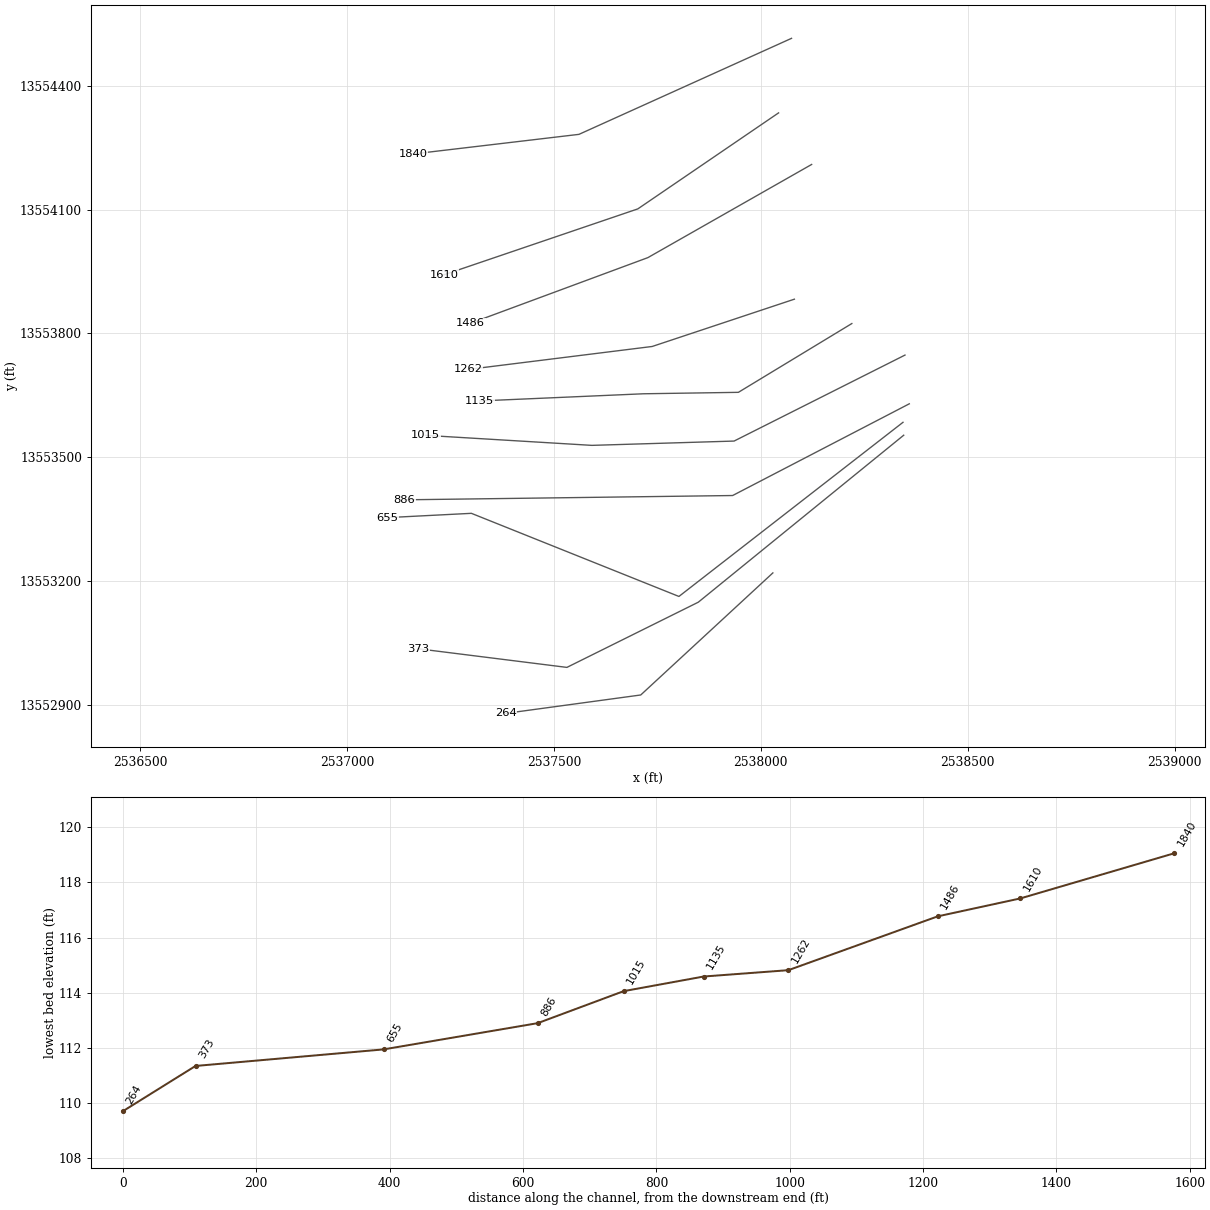
HEC-RAS study NORTH FORK CREEK.prj: NORTH FORK CREEK Base Level Engineering

--- NORTH FORK CREEK.g01 (geometry) --- (continued)

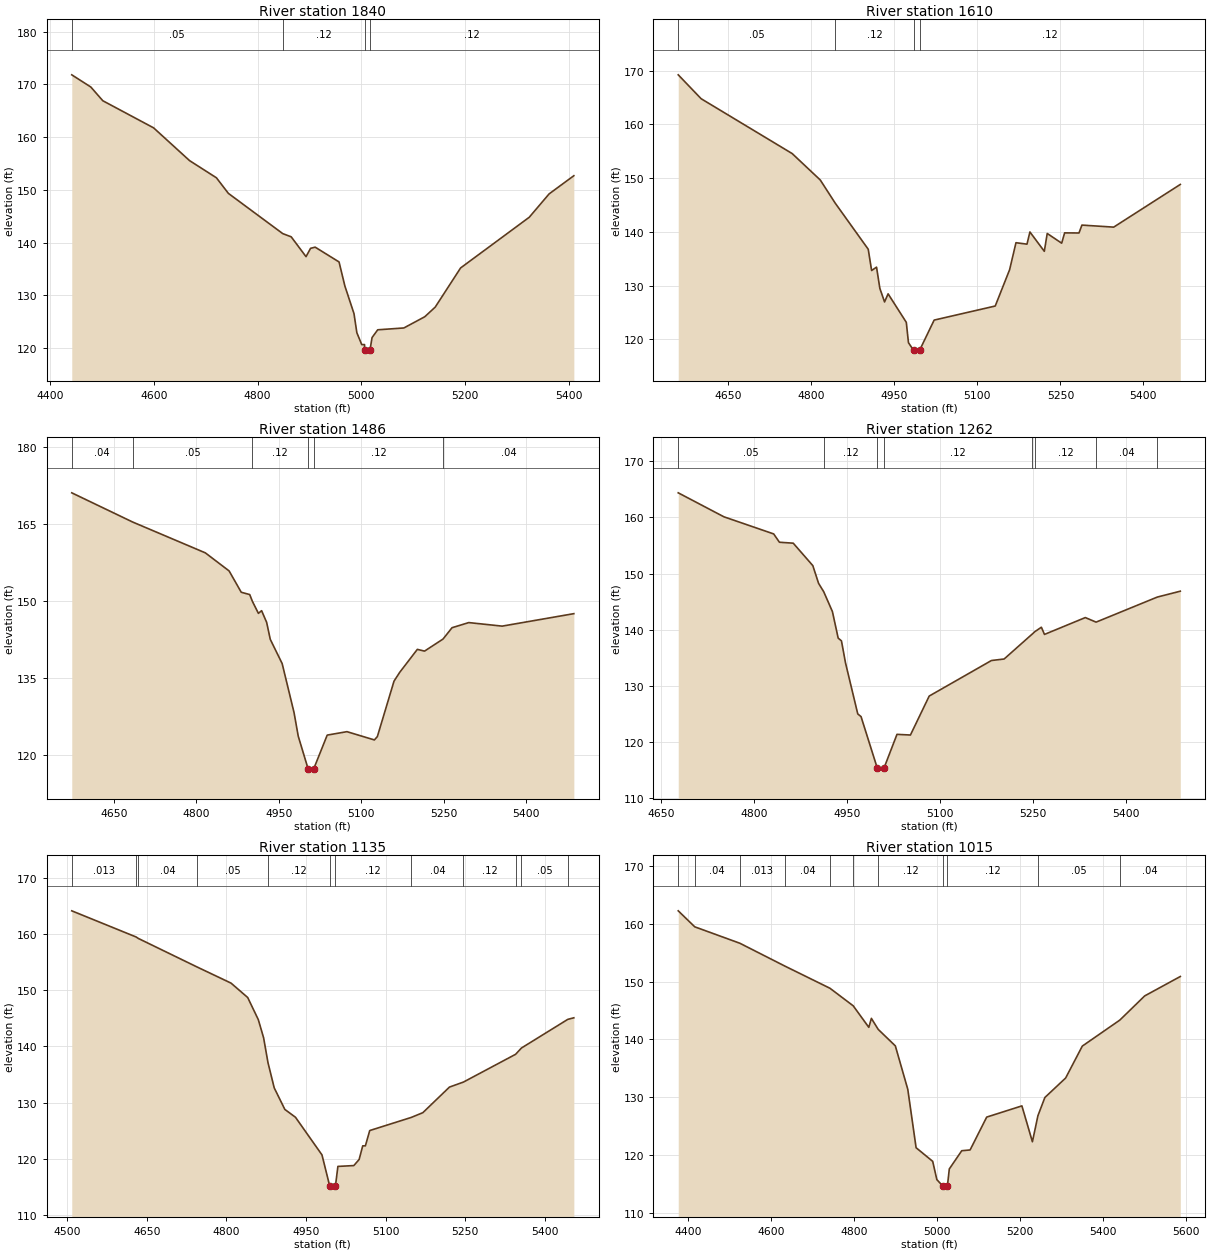
Type RM Length L Ch R = 1 ,1840    ,230,230,230
BEGIN DESCRIPTION:
Mapping XS 406e2685
END DESCRIPTION:
XS GIS Cut Line= 3
      2538074.13     13554514.85      2537560.23     13554282.21
      2537159.73     13554234.76
#Sta/Elev= 30
  4442.1  171.79  4478.8  169.48  4501.9  166.88  4599.8  161.74  4669.1  155.53
  4720.8  152.28  4743.9  149.32  4848.6   141.7  4864.9  141.09  4893.5  137.33
  4902.2  138.91  4911.1  139.13  4957.1  136.33  4968.3  131.78  4985.9  126.53
  4991.4  122.92  5000.8  120.67  5006.2  120.67  5006.3  119.55  5006.8  119.05
  5016.6  119.55  5020.7     122  5031.6  123.47    5082  123.82  5122.2  125.94
  5142.4  127.77  5191.3  135.19  5323.6   144.8  5361.9  149.23  5409.5  152.67
#Mann= 4 ,-1 , 0
  4442.1     .05       0  4848.6     .12       0  5006.3     .05       0
  5016.6     .12       0
Bank Sta=5006.3,5016.6
XS Rating Curve= 0 ,0
Exp/Cntr=0.3,0.1

Type RM Length L Ch R = 1 ,1610    ,124,124,124
BEGIN DESCRIPTION:
Mapping XS d6e51fd7
END DESCRIPTION:
XS GIS Cut Line= 3
      2538042.86     13554334.28      2537702.59     13554101.65
      2537233.84     13553941.93
#Sta/Elev= 30
  4559.3  169.24  4600.7  164.79  4765.2  154.58    4816  149.66    4843  145.35
  4902.7  136.76  4908.8   132.8  4917.7  133.43  4923.7  129.47  4932.2  126.95
  4938.6  128.46  4971.5  123.15  4975.4  119.36  4984.8  117.92  4985.3  117.42
  4995.4  117.92  5021.8  123.57  5132.2  126.19  5158.2  132.95  5169.7  137.98
  5189.6  137.71  5194.9  139.98  5220.9  136.38  5226.2   139.7  5252.3  137.89
  5257.6  139.81  5283.6  139.79  5288.9  141.26  5346.3  140.88  5466.7  148.83
#Mann= 4 ,-1 , 0
  4559.3     .05       0    4843     .12       0  4984.8     .05       0
  4995.4     .12       0
Bank Sta=4984.8,4995.4
XS Rating Curve= 0 ,0
Exp/Cntr=0.3,0.1

Type RM Length L Ch R = 1 ,1486    ,224,224,224
BEGIN DESCRIPTION:
Mapping XS b7f25732
END DESCRIPTION:
XS GIS Cut Line= 3
      2538122.76     13554209.31       2537726.9     13553983.59
      2537298.14     13553824.54
#Sta/Elev= 30
  4573.7  171.01  4684.4  165.32  4816.6  159.31  4859.8  155.79  4881.9  151.63
  4897.3  151.18    4902   149.9  4913.1  147.52  4918.9  148.04    4928  145.79
  4934.7  142.45  4956.3  137.73  4977.9  128.18  4985.5   123.6  5003.3  117.27
  5003.8  116.77  5013.9  117.27  5038.2  123.79  5074.1  124.46    5124  122.85
  5129.4   123.5  5159.7  134.31  5170.1  136.03  5202.1   140.5  5215.2  140.16
  5248.8  142.51  5265.2  144.72  5295.6  145.72  5356.4  145.03  5486.7  147.46
#Mann= 6 ,-1 , 0
  4573.7     .04       0  4684.4     .05       0    4902     .12       0
  5003.3     .05       0  5013.9     .12       0  5248.8     .04       0
Bank Sta=5003.3,5013.9
XS Rating Curve= 0 ,0
Exp/Cntr=0.3,0.1

Type RM Length L Ch R = 1 ,1262    ,127,127,127
BEGIN DESCRIPTION:
Mapping XS 96c18827
END DESCRIPTION:
XS GIS Cut Line= 3
      2538081.06      13553882.9      2537737.31     13553768.32
      2537292.91     13553712.77
#Sta/Elev= 30
  4677.4  164.39  4751.1  160.12  4831.4  157.07  4840.7  155.59    4863  155.42
  4894.6  151.42  4903.9  148.26  4912.2  146.77  4926.2  143.24  4935.5  138.51
  4940.8  138.02  4947.3  134.11  4967.1  125.01  4972.4  124.53  4998.7  115.32
  4999.2  114.82  5009.3  115.32  5030.4  121.37  5052.1  121.25  5082.4  128.19
  5182.8  134.52  5203.3  134.79    5249  139.27  5252.9  139.66  5263.4  140.45
  5268.4  139.17  5334.3  142.17  5351.7  141.36  5450.4  145.82  5487.6  146.87
#Mann= 8 ,-1 , 0
  4677.4     .05       0  4912.2     .12       0  4998.7     .05       0
  5009.3     .12       0    5249     .04       0  5252.9     .12       0
  5351.7     .04       0  5450.4     .05       0
Bank Sta=4998.7,5009.3
XS Rating Curve= 0 ,0
Exp/Cntr=0.3,0.1

Type RM Length L Ch R = 1 ,1135    ,120,120,120
BEGIN DESCRIPTION:
Mapping XS 8ed9d237
END DESCRIPTION:
XS GIS Cut Line= 4
      2538219.93     13553823.86      2537945.65     13553657.21
      2537716.48     13553653.73       2537320.7     13553636.37
#Sta/Elev= 30
  4508.4   164.1  4629.6  159.45  4633.8  159.19  4743.9  154.14  4808.6  151.24
    4840  148.68    4860  144.74    4870   141.5  4878.2   137.1    4890   132.6
    4910  128.77    4930  127.38    4980  120.68  4994.7  115.09  4995.2  114.59
  5005.3  115.09    5010  118.63    5040  118.78    5050  119.86  5056.8  122.29
  5061.8  122.29    5070  125.01  5148.4  127.35  5170.1  128.19  5220.2  132.74
  5246.7  133.64    5345  138.58  5355.9  139.69  5443.3  144.79  5454.7  145.07
#Mann= 12 ,-1 , 0
  4508.4    .013       0  4629.6     .05       0  4633.8     .04       0
  4743.9     .05       0  4878.2     .12       0  4994.7     .05       0
  5005.3     .12       0  5148.4     .04       0  5246.7     .12       0
    5345     .04       0  5355.9     .05       0  5443.3     .04       0
Bank Sta=4994.7,5005.3
XS Rating Curve= 0 ,0
Exp/Cntr=0.3,0.1

Type RM Length L Ch R = 1 ,1015    ,129,129,129
BEGIN DESCRIPTION:
Mapping XS 072a4aef
END DESCRIPTION:
XS GIS Cut Line= 4
       2538348.4     13553747.47      2537935.23     13553539.15
      2537591.48     13553528.73      2537189.33       13553553.
#Sta/Elev= 30
    4377  162.24  4416.8  159.47  4525.4  156.63    4634  152.67  4742.6  148.83
  4798.6  145.79  4836.1  142.07  4842.3  143.62  4858.8  141.71    4900  138.86
    4930  131.34    4950  121.23    4990  118.87    5000  115.71  5014.7  114.56
  5015.2  114.06  5025.4  114.56    5030  117.55    5060  120.71  5080.1  120.84
  5120.1  126.53  5204.9  128.47  5230.2  122.26  5243.5  126.77  5260.2  129.92
  5310.3   133.3  5350.4  138.82  5440.9  143.33  5500.7  147.51  5586.5  150.87
#Mann= 11 ,-1 , 0
    4377     .05       0  4416.8     .04       0  4525.4    .013       0
    4634     .04       0  4742.6     .05       0  4798.6     .04       0
  4858.8     .12       0  5014.7     .05       0  5025.4     .12       0
  5243.5     .05       0  5440.9     .04       0
Bank Sta=5014.7,5025.4
XS Rating Curve= 0 ,0
Exp/Cntr=0.3,0.1

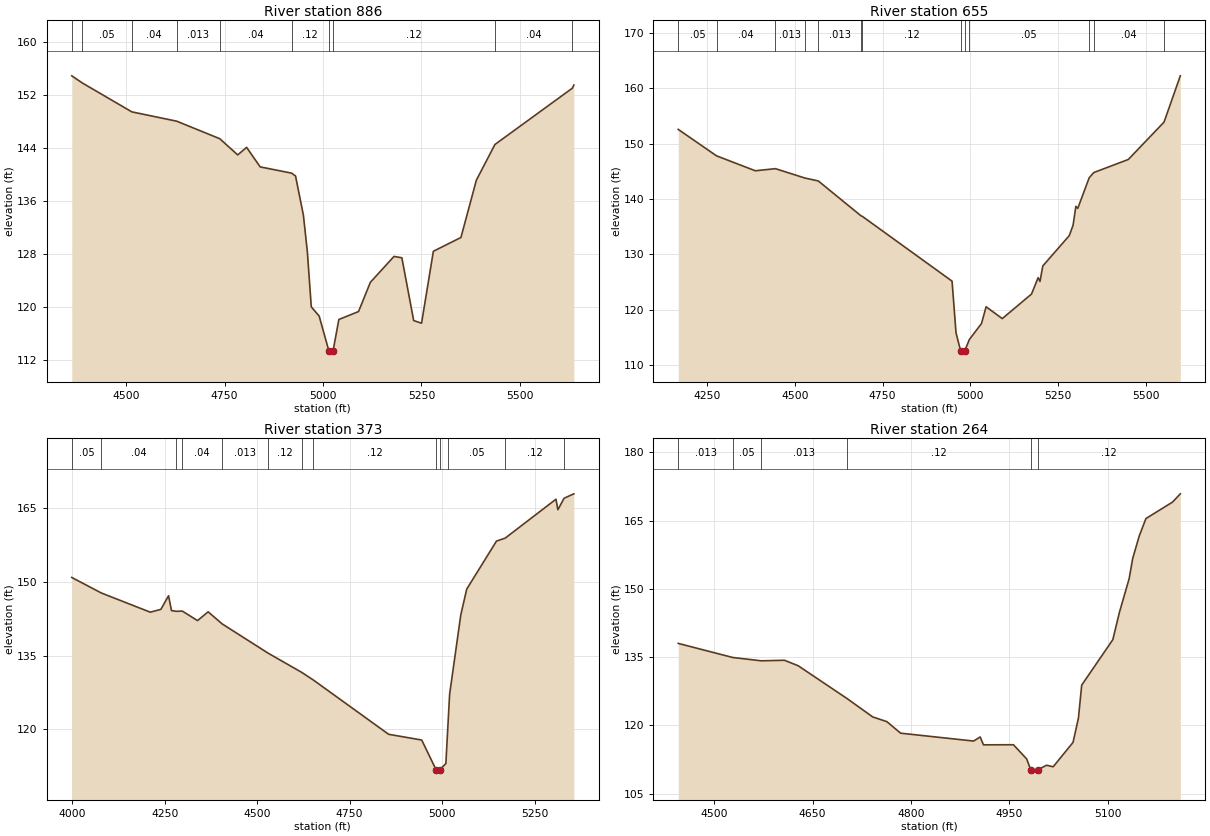
Type RM Length L Ch R = 1 ,886     ,231,231,231
BEGIN DESCRIPTION:
Mapping XS 80177b68
END DESCRIPTION:
XS GIS Cut Line= 3
      2538358.83     13553629.42      2537931.76     13553407.21
      2537138.35     13553396.81
#Sta/Elev= 30
    4362  154.92  4388.6  153.85  4514.4  149.48  4628.5  148.07  4737.7  145.43
  4783.4  142.98    4806  144.12  4840.4  141.17  4920.1  140.23  4930.2   139.8
  4950.2  133.87  4960.2  128.36  4970.2  120.04  4990.2  118.65  5014.8   113.4
  5015.3   112.9  5025.5   113.4  5040.2  118.13  5090.2  119.33  5120.2  123.74
  5180.2  127.65  5200.2  127.45  5230.2  117.97  5250.2  117.57  5280.2  128.43
  5350.2  130.51  5389.4  139.17  5436.5  144.55  5633.2  153.06  5636.9  153.53
#Mann= 10 ,-1 , 0
    4362     .04       0  4388.6     .05       0  4514.4     .04       0
  4628.5    .013       0  4737.7     .04       0  4920.1     .12       0
  5014.8     .05       0  5025.5     .12       0  5436.5     .04       0
  5633.2     .12       0
Bank Sta=5014.8,5025.5
XS Rating Curve= 0 ,0
Exp/Cntr=0.3,0.1

Type RM Length L Ch R = 1 ,655     ,282,282,282
BEGIN DESCRIPTION:
Mapping XS a53cd38a
END DESCRIPTION:
XS GIS Cut Line= 4
      2538343.62      13553584.6      2537801.91     13553162.69
      2537300.18     13553364.08      2537097.01     13553353.66
#Sta/Elev= 30
  4167.9  152.57    4277  147.79  4387.5  145.09    4445  145.47  4528.6  143.78
    4567  143.25  4688.9  136.94  4692.5  136.85  4948.2  125.14  4959.5  115.79
    4973  112.45  4973.5  111.95  4983.7  112.45  4997.6   114.6  5032.1  117.48
  5045.2  120.51  5091.3  118.37  5174.6  122.81  5193.5  125.77  5198.8  125.09
  5206.8  127.89  5282.2  133.37    5293  135.24    5301  138.66  5306.4  138.29
  5338.9  143.82  5352.1  144.77  5450.4  147.13  5552.3  153.89  5598.6  162.25
#Mann= 13 ,-1 , 0
  4167.9     .05       0    4277     .04       0    4445    .013       0
  4528.6     .04       0    4567    .013       0  4688.9     .04       0
  4692.5     .12       0    4973     .05       0  4983.7     .12       0
  4997.6     .05       0  5338.9     .12       0  5352.1     .04       0
  5552.3     .12       0
Bank Sta=4973,4983.7
XS Rating Curve= 0 ,0
Exp/Cntr=0.3,0.1

Type RM Length L Ch R = 1 ,373     ,109,109,109
BEGIN DESCRIPTION:
Mapping XS 4b540e17
END DESCRIPTION:
XS GIS Cut Line= 4
      2538345.32     13553553.33      2537848.79     13553148.81
      2537531.08     13552990.82      2537171.68     13553035.96
#Sta/Elev= 30
  3998.7  150.83  4078.6  147.68  4210.9  143.79  4239.6  144.36  4260.4  147.12
  4268.3  144.12  4281.4  143.96  4297.6  144.01  4338.7  142.08  4367.4  143.86
  4405.4  141.41  4529.5  135.48  4620.9  131.56  4651.7  130.04  4855.5  119.02
  4944.9  117.86  4983.6  111.85  4984.1  111.35  4994.3  111.85  5010.2  113.09
  5015.2  120.04  5020.3  127.13  5050.5  143.23  5066.6  148.47  5147.1  158.21
  5170.5   158.8  5307.9   166.7    5313  164.57  5329.8  166.89  5356.2  167.79
#Mann= 13 ,-1 , 0
  3998.7     .05       0  4078.6     .04       0  4281.4    .013       0
  4297.6     .04       0  4405.4    .013       0  4529.5     .12       0
  4620.9    .013       0  4651.7     .12       0  4983.6     .05       0
  4994.3     .12       0  5015.2     .05       0  5170.5     .12       0
  5329.8     .04       0
Bank Sta=4983.6,4994.3
XS Rating Curve= 0 ,0
Exp/Cntr=0.3,0.1

Type RM Length L Ch R = 1 ,264     ,0,0,0
BEGIN DESCRIPTION:
NORTH FORK CREEK 1.0
END DESCRIPTION:
XS GIS Cut Line= 3
      2538029.01     13553219.73      2537709.58     13552923.99
      2537383.13     13552879.42
#Sta/Elev= 30
  4445.4  138.01  4528.5  134.91  4571.9  134.18  4607.3   134.3  4628.2  133.09
  4702.5  125.89  4741.6  121.85  4763.2  120.81  4784.2  118.27  4895.4  116.54
  4905.3  117.44  4910.4  115.71    4956  115.73  4976.2  112.61  4982.4  110.21
  4982.9  109.71  4993.1  110.21  5006.5  111.23  5016.5  110.88  5046.8  116.25
    5055  121.58    5060  128.84  5107.4  138.83  5117.5  144.86  5132.3  152.26
  5137.7  156.71  5147.8  161.69  5157.8  165.45  5198.2  169.06  5210.2  170.89
#Mann= 6 ,-1 , 0
  4445.4    .013       0  4528.5     .05       0  4571.9    .013       0
  4702.5     .12       0  4982.4     .05       0  4993.1     .12       0
Bank Sta=4982.4,4993.1
XS Rating Curve= 0 ,0
Exp/Cntr=0.3,0.1

Chan Stop Cuts=-1
Use User Specified Reach Order=0
Composite Channel Slope=5