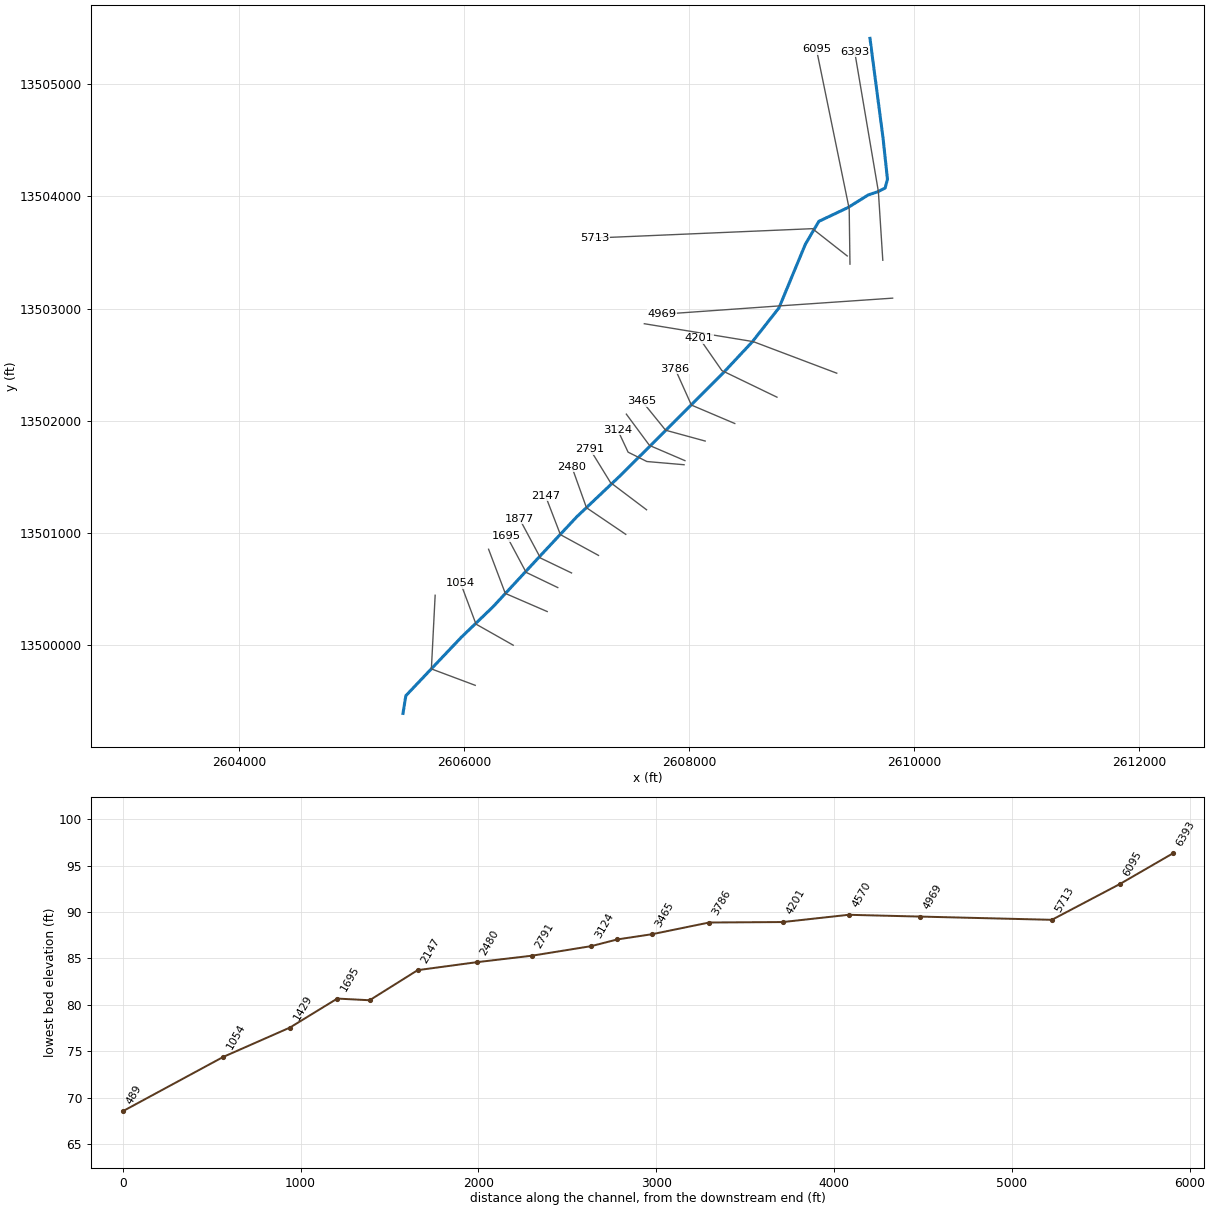
--- NORTH OUTFALL.prj (project) ---

Proj Title=NORTH OUTFALL Base Level Engineering
Current Plan=p01
Default Exp/Contr=0.3,0.1
English Units
Geom File=g01
Flow File=f01
Plan File=p01
Y Axis Title=Elevation
X Axis Title(PF)=Main Channel Distance
X Axis Title(XS)=Station
BEGIN DESCRIPTION:
NORTH OUTFALL
END DESCRIPTION:
DSS Export Rating Curves= 0
DSS Export Rating Curve Sorted= 0
DSS Export Volume Flow Curves= 0
DXF OffsetX= 0
DXF OffsetY= 0
DXF ScaleX= 1
DXF ScaleY= 10

--- NORTH OUTFALL.p01 (plan) ---

Plan Title=Multiple Run
Short Identifier=Multiple
Geom File=g01
Flow File=f01
Subcritical Flow
K Sum by GR= 0
Std Step Tol= 0.01
Critical Tol= 0.01
Num of Std Step Trials= 20
Max Error Tol= 0.3
Flow Tol Ratio= 0.001
Split Flow NTrial= 30
Split Flow Tol= 0.02
Split Flow Ratio= 0.02
Log Output Level= 0
Friction Slope Method= 1
Unsteady Friction Slope Method= 2
Unsteady Bridges Friction Slope Method= 1
Parabolic Critical Depth
Global Vel Dist=  1 , 1 , 1
Global Log Level= 0
CheckData=True
Encroach Param= -1, 0, 0, 0
BEGIN DESCRIPTION:
Multiple Run
END DESCRIPTION:

--- NORTH OUTFALL.f01 (steady flow) ---

Flow Title=Multiple
Number of Profiles=7
Profile Names=10-year,25-year,50-year,1pct_min,100-year,1pct_plu,500-year
River Rch & RM= NORTH OUTFALL,Reach-1,6393
     341     490     607     363     723    1443    1016
River Rch & RM= NORTH OUTFALL,Reach-1,4969
     976    1551    2063    1325    2643    5274    4287
Boundary for River Rch & Prof#=NORTH OUTFALL,Reach-1,1
Up Type=0
Dn Type=3
Dn Slope=0.005
Boundary for River Rch & Prof#=NORTH OUTFALL,Reach-1,2
Up Type=0
Dn Type=3
Dn Slope=0.005
Boundary for River Rch & Prof#=NORTH OUTFALL,Reach-1,3
Up Type=0
Dn Type=3
Dn Slope=0.005
Boundary for River Rch & Prof#=NORTH OUTFALL,Reach-1,4
Up Type=0
Dn Type=3
Dn Slope=0.005
Boundary for River Rch & Prof#=NORTH OUTFALL,Reach-1,5
Up Type=0
Dn Type=3
Dn Slope=0.005
Boundary for River Rch & Prof#=NORTH OUTFALL,Reach-1,6
Up Type=0
Dn Type=3
Dn Slope=0.005
Boundary for River Rch & Prof#=NORTH OUTFALL,Reach-1,7
Up Type=0
Dn Type=3
Dn Slope=0.005

--- NORTH OUTFALL.g01 (geometry) ---

Geom Title=Existing Conditions
Program Version=4.10

River Reach=NORTH OUTFALL   ,Reach-1
Reach XY= 30
      2609604.91     13505405.73      2609720.65     13504521.21
      2609760.36      13504151.2      2609739.53     13504073.08
      2609679.63     13504041.83      2609588.49     13504010.58
       2609408.8      13503898.6      2609198.15      13503798.6
      2609150.99      13503776.2      2609031.19     13503573.08
       2608796.1     13503005.37      2608558.74     13502702.74
      2608494.16      13502633.6      2608292.62     13502417.88
      2607588.94     13501714.13      2607377.28      13501503.7
      2607000.96     13501147.05      2606943.96     13501086.04
      2606704.08     13500829.34      2606256.17     13500344.96
      2606066.93     13500162.73      2606013.04     13500110.85
      2605974.92     13500074.13      2605885.36     13499979.58
      2605849.91     13499942.17      2605730.95     13499816.57
      2605686.92      13499770.1      2605533.29      13499607.9
      2605480.68     13499552.37      2605455.07     13499395.03

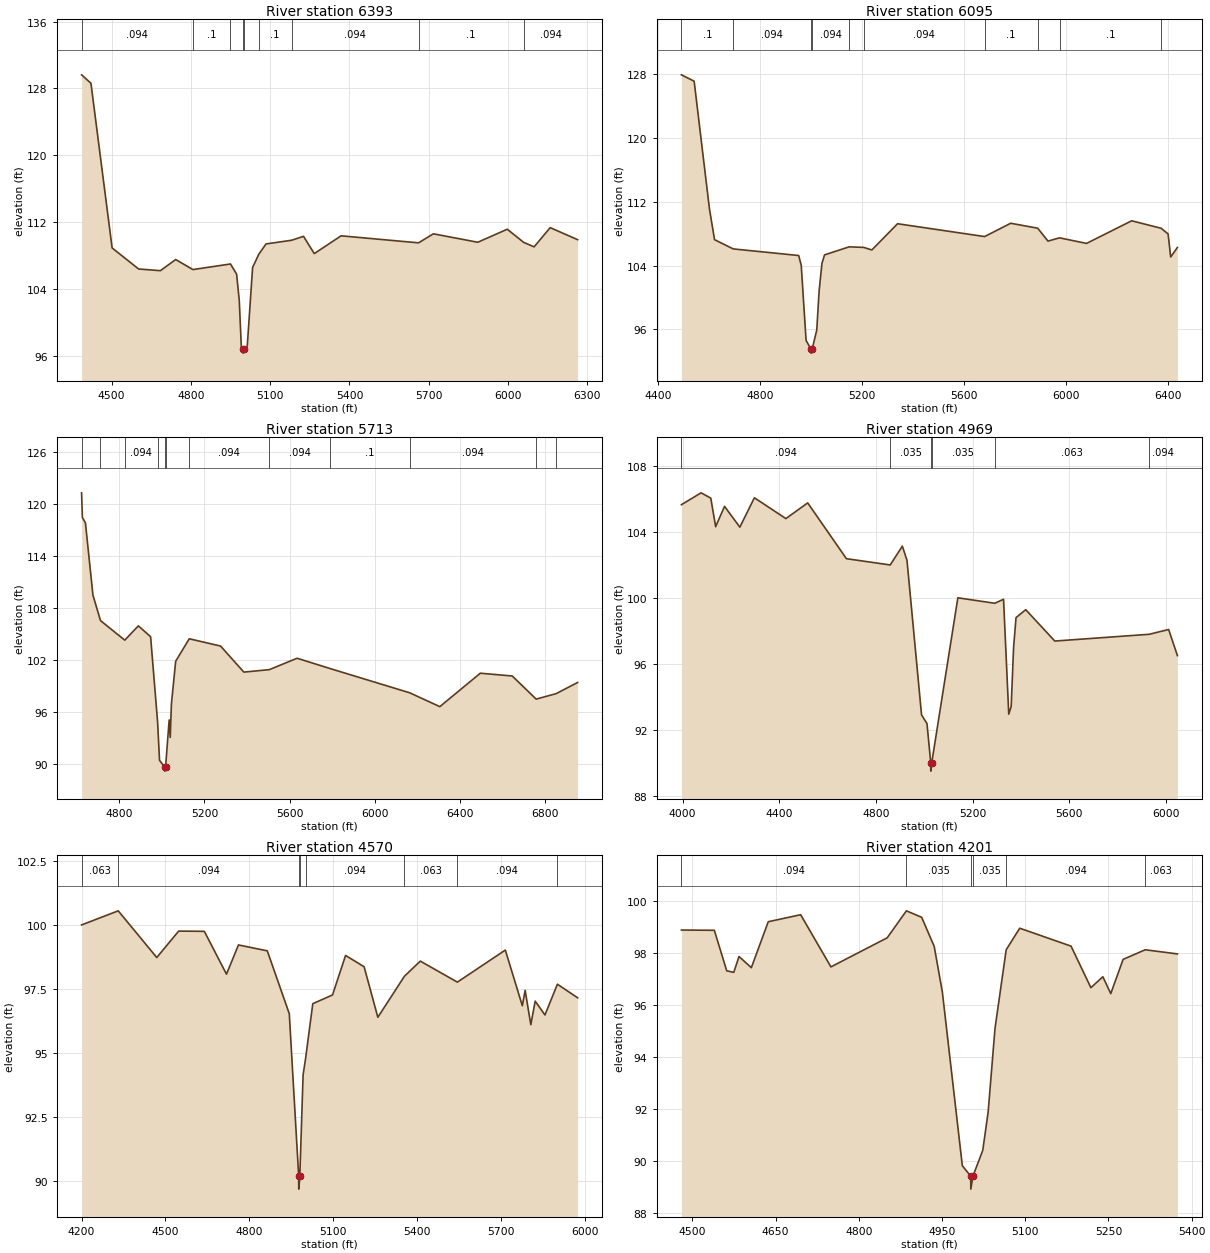
Type RM Length L Ch R = 1 ,6393    ,298,298,298
BEGIN DESCRIPTION:
Mapping XS 8301de4b
END DESCRIPTION:
XS GIS Cut Line= 3
      2609718.92     13503429.69      2609679.63     13504041.83
      2609468.93     13505287.33
#Sta/Elev= 30
  4386.6  129.62    4422  128.61  4502.1   108.9  4602.4  106.38  4684.8  106.18
  4742.6  107.51    4808  106.31  4949.9  106.98  4973.1  105.76  4983.1  102.62
  4991.2   96.84  4996.9   96.81  4997.2   96.31  5001.3   96.81  5013.4   97.16
  5033.6  106.56  5057.1  108.15  5084.4  109.38  5181.1  109.82  5226.3  110.29
  5266.9  108.22  5368.3  110.35  5661.4  109.51  5717.7  110.59  5885.6  109.58
  5997.1  111.14  6058.9  109.57  6098.6  109.03  6159.4  111.33  6263.2  109.89
#Mann= 9 ,-1 , 0
  4386.6    .094       0    4808      .1       0  4949.9    .094       0
  4996.9    .035       0  5001.3    .094       0  5057.1      .1       0
  5181.1    .094       0  5661.4      .1       0  6058.9    .094       0
Bank Sta=4996.9,5001.3
XS Rating Curve= 0 ,0
Exp/Cntr=0.3,0.1

Type RM Length L Ch R = 1 ,6095    ,382,382,382
BEGIN DESCRIPTION:
Mapping XS 3e6e69aa
END DESCRIPTION:
XS GIS Cut Line= 3
      2609427.25     13503395.04      2609420.31     13503888.06
      2609128.81     13505310.84
#Sta/Elev= 30
  4490.9  127.94  4540.9  127.14  4600.9  111.12  4620.9  107.25  4694.3  106.09
  4950.9  105.26  4960.9  104.03  4979.9   94.61  4998.9   93.51  4999.2   93.01
  5003.7   93.51  5021.7   95.89  5031.1  100.85  5042.1  104.26  5052.3  105.34
  5148.9  106.35  5205.9  106.28  5237.9  105.96  5338.7  109.25  5680.1  107.64
  5782.4  109.31  5888.3  108.69  5928.6  107.07  5973.9  107.48  6079.9  106.78
  6256.8  109.62  6372.6  108.68  6399.7  107.97  6409.9  105.08  6436.3  106.27
#Mann= 10 ,-1 , 0
  4490.9      .1       0  4694.3    .094       0  4998.9    .035       0
  5003.7    .094       0  5148.9      .1       0  5205.9    .094       0
  5680.1      .1       0  5888.3    .035       0  5973.9      .1       0
  6372.6    .094       0
Bank Sta=4998.9,5003.7
XS Rating Curve= 0 ,0
Exp/Cntr=0.3,0.1

Type RM Length L Ch R = 1 ,5713    ,744,744,744
BEGIN DESCRIPTION:
Mapping XS c88d6142
END DESCRIPTION:
XS GIS Cut Line= 3
      2609402.95     13503467.92      2609093.92     13503710.98
      2607158.18     13503627.72
#Sta/Elev= 30
    4623  121.31  4626.6  118.47    4641  117.84  4676.3   109.5  4711.8  106.55
  4825.9  104.29  4889.6  105.94  4947.3  104.69    4980   94.88  4989.3    90.4
    5013   89.66  5013.3   89.16  5017.8   89.66  5034.5   95.08  5039.5   93.05
  5045.1   96.94  5065.1  101.85  5128.9  104.45    5276  103.61  5385.4   100.6
  5504.7  100.88  5635.7   102.2  5789.2  101.02  6164.6   98.21  6306.3   96.61
  6496.5  100.47  6646.6  100.15  6758.9   97.48  6852.8   98.11  6953.7    99.4
#Mann= 12 ,-1 , 0
    4623      .1       0  4711.8    .035       0  4825.9    .094       0
    4980    .094       0    5013    .035       0  5017.8    .094       0
  5128.9    .094       0  5504.7    .094       0  5789.2      .1       0
  6164.6    .094       0  6758.9    .035       0  6852.8    .094       0
Bank Sta=5013,5017.8
XS Rating Curve= 0 ,0
Exp/Cntr=0.3,0.1

Type RM Length L Ch R = 1 ,4969    ,399,399,399
BEGIN DESCRIPTION:
Mapping XS 6fc7f85b
END DESCRIPTION:
XS GIS Cut Line= 3
      2609806.34     13503092.35      2608795.02      13503022.9
      2607758.84      13502949.2
#Sta/Elev= 30
  3994.9  105.65  4076.4  106.37  4116.5  106.05  4136.6  104.32  4173.4  105.55
  4236.8  104.29  4296.9  106.07  4427.3  104.81  4517.5  105.76  4677.8  102.38
    4859     102  4909.2  103.14  4928.4  102.28  4988.6   92.92  5011.1   92.39
  5026.7   90.01  5026.9   89.51  5030.7   90.01  5138.9  100.01  5291.4   99.68
  5327.9   99.92  5349.5   92.96  5359.5   93.43  5369.5   97.01  5379.6   98.81
  5419.7   99.29    5540   97.39  5930.6    97.8  6011.1   98.09  6047.4   96.51
#Mann= 6 ,-1 , 0
  3994.9    .094       0    4859    .035       0  5026.7    .035       0
  5030.7    .035       0  5291.4    .063       0  5930.6    .094       0
Bank Sta=5026.7,5030.7
XS Rating Curve= 0 ,0
Exp/Cntr=0.3,0.1

Type RM Length L Ch R = 1 ,4570    ,369,369,369
BEGIN DESCRIPTION:
Mapping XS 9953f363
END DESCRIPTION:
XS GIS Cut Line= 3
      2609309.77     13502424.08      2608567.56     13502705.33
      2607599.79     13502864.59
#Sta/Elev= 30
  4200.2     100  4331.3  100.55  4469.1   98.73  4547.5   99.76  4639.3   99.75
  4718.6   98.08  4761.4   99.22  4864.5   98.99  4943.2   96.54  4976.9    90.2
  4977.1    89.7  4980.9    90.2  4992.6   94.15  5001.6    94.8  5027.3   96.93
  5097.9   97.27  5144.6   98.81  5210.9   98.37    5260    96.4  5355.2      98
    5412   98.59  5544.5   97.77  5716.1   99.02  5776.9   96.85    5787   97.45
  5807.3   96.11  5822.9   97.03  5857.9   96.49  5902.4   97.69  5974.7   97.16
#Mann= 8 ,-1 , 0
  4200.2    .063       0  4331.3    .094       0  4976.9    .035       0
  4980.9    .094       0  5001.6    .094       0  5355.2    .063       0
  5544.5    .094       0  5902.4     .05       0
Bank Sta=4976.9,4980.9
XS Rating Curve= 0 ,0
Exp/Cntr=0.3,0.1

Type RM Length L Ch R = 1 ,4201    ,415,415,415
BEGIN DESCRIPTION:
Mapping XS 77fbe3de
END DESCRIPTION:
XS GIS Cut Line= 3
       2608778.5     13502210.54      2608288.92     13502447.52
      2608089.21     13502735.41
#Sta/Elev= 30
  4480.1    98.9  4539.5   98.89  4561.8   97.33  4574.5   97.27    4584   97.88
  4606.2   97.45  4636.7   99.22  4695.1   99.49  4749.7   97.48  4851.1    98.6
  4885.8   99.64  4913.3   99.39  4935.9   98.27  4950.6   96.51  4986.6   89.82
  5001.7   89.42  5001.9   88.92  5005.7   89.42  5023.4   90.41  5033.1   91.88
  5045.5   95.11  5065.7   98.14  5090.1   98.97  5182.6   98.28  5218.4   96.68
    5240    97.1  5254.2   96.45  5276.5   97.77  5316.4   98.14  5374.4   97.98
#Mann= 6 ,-1 , 0
  4480.1    .094       0  4885.8    .035       0  5001.7    .035       0
  5005.7    .035       0  5065.7    .094       0  5316.4    .063       0
Bank Sta=5001.7,5005.7
XS Rating Curve= 0 ,0
Exp/Cntr=0.3,0.1

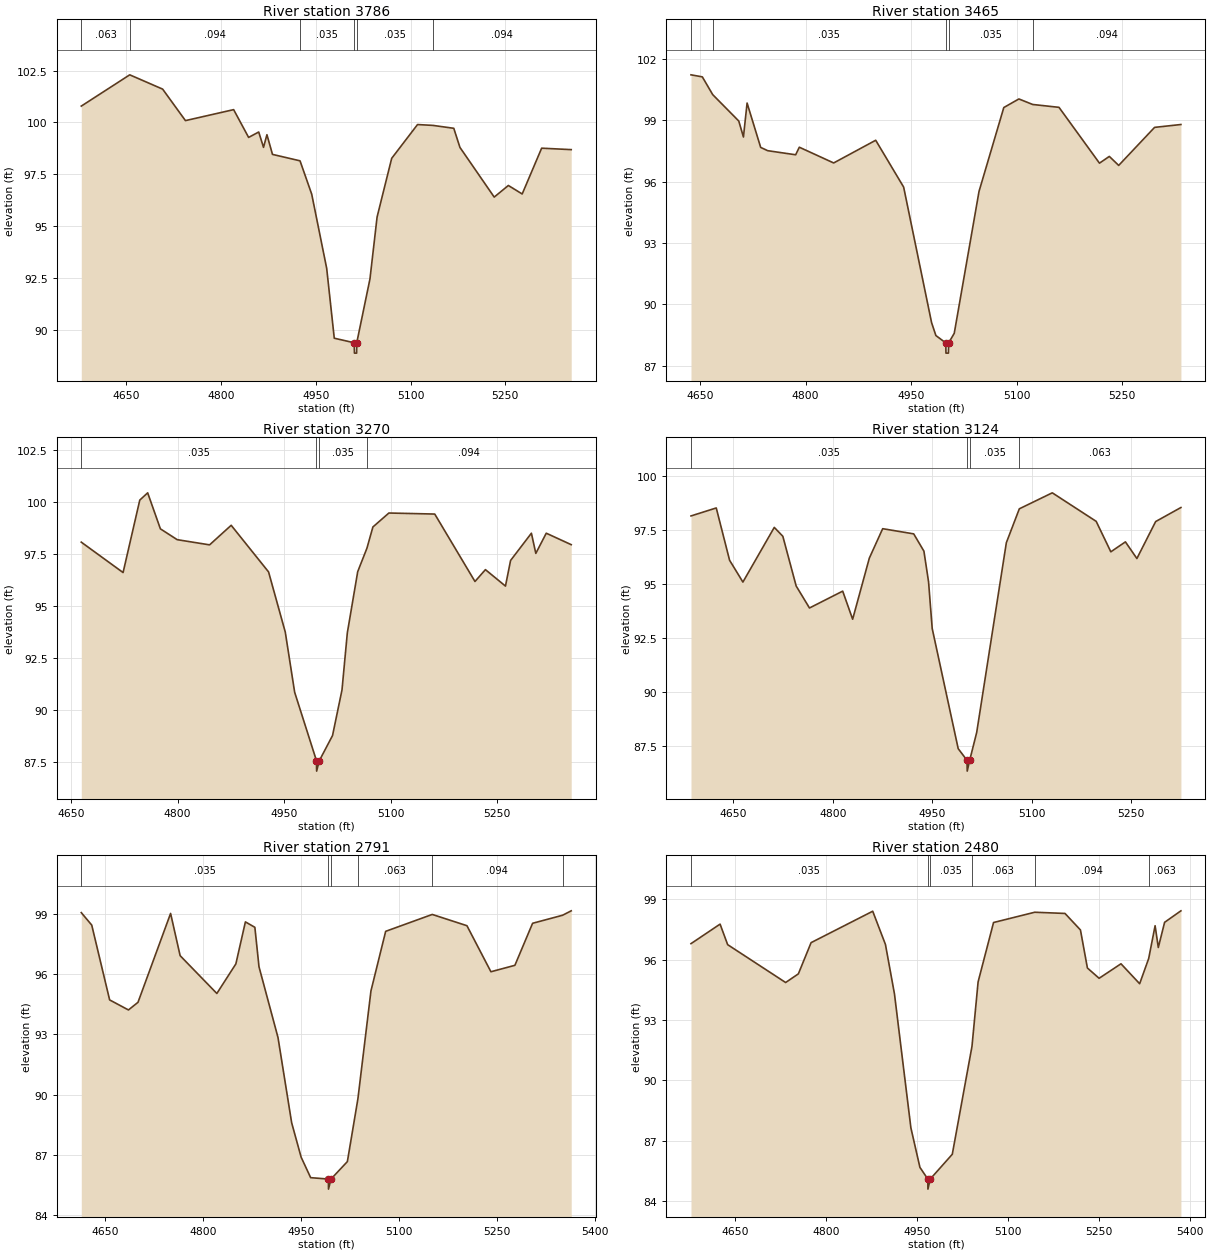
Type RM Length L Ch R = 1 ,3786    ,321,321,321
BEGIN DESCRIPTION:
Mapping XS 6a366606
END DESCRIPTION:
XS GIS Cut Line= 3
      2608403.49     13501976.17      2608018.08     13502140.23
      2607872.23     13502465.78
#Sta/Elev= 30
  4578.8  100.79  4655.5   102.3  4707.6  101.61  4743.7  100.09    4820  100.62
  4843.7   99.28  4859.7   99.54  4867.3    98.8  4872.7   99.41  4881.5   98.46
  4925.1   98.15  4943.6   96.54  4967.3   92.96  4979.3   89.59  5010.9   89.37
  5011.2   88.87  5014.7   88.87  5014.9   89.37  5035.8   92.45  5047.1   95.44
  5070.2   98.27  5111.1    99.9  5135.3   99.86  5168.5   99.72  5178.2    98.8
  5232.5    96.4  5254.9   96.96  5276.8   96.55  5307.6   98.76  5354.4   98.69
#Mann= 6 ,-1 , 0
  4578.8    .063       0  4655.5    .094       0  4925.1    .035       0
  5010.9    .035       0  5014.9    .035       0  5135.3    .094       0
Bank Sta=5010.9,5014.9
XS Rating Curve= 0 ,0
Exp/Cntr=0.3,0.1

Type RM Length L Ch R = 1 ,3465    ,195,195,195
BEGIN DESCRIPTION:
Mapping XS 3d42ca22
END DESCRIPTION:
XS GIS Cut Line= 3
       2608140.5     13501819.91      2607788.92     13501916.27
      2607580.59     13502174.07
#Sta/Elev= 30
  4637.2  101.22  4653.3  101.12  4668.1  100.25  4705.1   98.96  4711.7   98.18
  4716.9   99.84  4736.2   97.67  4746.2   97.51  4785.9   97.31  4791.1   97.68
  4839.9   96.91  4899.6   98.02  4939.3   95.73    4979    89.1  4985.1   88.47
  4999.2   88.11  4999.4   87.61  5002.9   87.61  5003.2   88.11  5011.2   88.58
  5046.4   95.52  5081.6   99.62    5103  100.04  5122.6   99.77    5160   99.63
  5217.5    96.9  5231.5   97.23  5244.8   96.79  5295.8   98.65  5333.2   98.79
#Mann= 5 ,-1 , 0
  4637.2    .094       0  4668.1    .035       0  4999.2    .035       0
  5003.2    .035       0  5122.6    .094       0
Bank Sta=4999.2,5003.2
XS Rating Curve= 0 ,0
Exp/Cntr=0.3,0.1

Type RM Length L Ch R = 1 ,3270    ,146,146,146
BEGIN DESCRIPTION:
Mapping XS 1114f630
END DESCRIPTION:
XS GIS Cut Line= 3
      2607960.81     13501645.43      2607645.69     13501780.85
      2607439.99     13502059.45
#Sta/Elev= 30
  4664.6   98.05  4723.4   96.59  4746.9  100.07    4758  100.42  4775.9   98.69
  4799.5   98.17  4845.1   97.92  4875.5   98.86  4928.1   96.62  4951.6   93.73
  4964.8   90.84  4995.5   87.55  4995.7   87.05  4999.5   87.55  5018.1   88.76
  5031.4   90.95  5038.9   93.69  5053.5   96.63  5066.5   97.76  5074.9   98.78
  5097.4   99.45  5161.9    99.4  5218.5   96.16  5233.2   96.73  5261.4   95.94
  5268.6   97.17  5297.9   98.48  5304.1   97.51  5318.8   98.48  5353.9   97.93
#Mann= 4 ,-1 , 0
  4664.6    .035       0  4995.5    .035       0  4999.5    .035       0
  5066.5    .094       0
Bank Sta=4995.5,4999.5
XS Rating Curve= 0 ,0
Exp/Cntr=0.3,0.1

Type RM Length L Ch R = 1 ,3124    ,333,333,333
BEGIN DESCRIPTION:
Mapping XS 007e61a0
END DESCRIPTION:
XS GIS Cut Line= 4
      2607952.99     13501608.98      2607622.25     13501637.63
      2607455.58     13501720.96      2607362.16     13501920.78
#Sta/Elev= 30
    4586   98.14  4624.1   98.51  4644.2   96.09  4664.3   95.08  4711.6   97.61
  4724.5    97.2  4744.6    94.9  4764.7   93.88  4814.8   94.66  4829.8   93.36
    4855   96.19  4875.1   97.55  4921.9   97.31  4937.3   96.51  4944.3   95.09
  4949.8   92.93    4989   87.37  5002.3   86.83  5002.6   86.33  5006.3   86.83
  5016.9   88.12  5061.6    96.9  5081.2   98.47  5130.9   99.21  5197.1   97.89
  5219.2   96.48  5241.2   96.94  5258.5   96.17  5286.8   97.88  5324.9   98.53
#Mann= 4 ,-1 , 0
    4586    .035       0  5002.3    .035       0  5006.3    .035       0
  5081.2    .063       0
Bank Sta=5002.3,5006.3
XS Rating Curve= 0 ,0
Exp/Cntr=0.3,0.1

Type RM Length L Ch R = 1 ,2791    ,311,311,311
BEGIN DESCRIPTION:
Mapping XS 360ec4ca
END DESCRIPTION:
XS GIS Cut Line= 3
      2607619.62     13501207.95      2607299.33     13501450.13
      2607117.05     13501746.99
#Sta/Elev= 30
  4613.4   99.05  4629.4   98.43  4656.8   94.71  4685.6   94.21  4700.2   94.59
  4750.1   99.01  4764.7   96.91  4820.9   95.03    4850    96.5  4864.6   98.59
  4879.1   98.32  4885.4   96.36  4914.5   92.84  4935.4    88.6  4949.9   86.89
  4964.5   85.87  4991.6    85.8  4991.8    85.3  4995.6    85.8  5020.7   86.67
  5036.8   89.79  5056.8   95.16  5079.3   98.12  5150.6   98.96  5203.7    98.4
  5240.4   96.11  5277.1   96.43  5304.2   98.52  5350.1   98.92  5363.3   99.14
#Mann= 6 ,-1 , 0
  4613.4    .035       0  4991.6    .035       0  4995.6    .035       0
  5036.8    .063       0  5150.6    .094       0  5350.1    .063       0
Bank Sta=4991.6,4995.6
XS Rating Curve= 0 ,0
Exp/Cntr=0.3,0.1

Type RM Length L Ch R = 1 ,2480    ,333,333,333
BEGIN DESCRIPTION:
Mapping XS 1d030f31
END DESCRIPTION:
XS GIS Cut Line= 3
      2607434.72     13500989.21      2607085.79     13501226.17
      2606955.72     13501590.35
#Sta/Elev= 30
  4577.2   96.79  4625.2   97.76  4637.7   96.74  4733.4   94.86  4754.4   95.29
  4775.4   96.84  4877.1    98.4  4898.1   96.75    4913   94.29  4940.1   87.64
    4955   85.68    4968    85.1  4968.2    84.6    4972    85.1  5008.4   86.33
  5040.9   91.69    5051   94.89  5076.5   97.84  5144.5   98.35  5194.4   98.29
  5219.9   97.47  5231.4   95.58  5250.7   95.07  5286.8   95.79  5317.6    94.8
  5332.5   96.05  5343.1   97.68  5348.4    96.6  5358.8   97.85  5385.7   98.42
#Mann= 6 ,-1 , 0
  4577.2    .035       0    4968    .035       0    4972    .035       0
  5040.9    .063       0  5144.5    .094       0  5332.5    .063       0
Bank Sta=4968,4972
XS Rating Curve= 0 ,0
Exp/Cntr=0.3,0.1

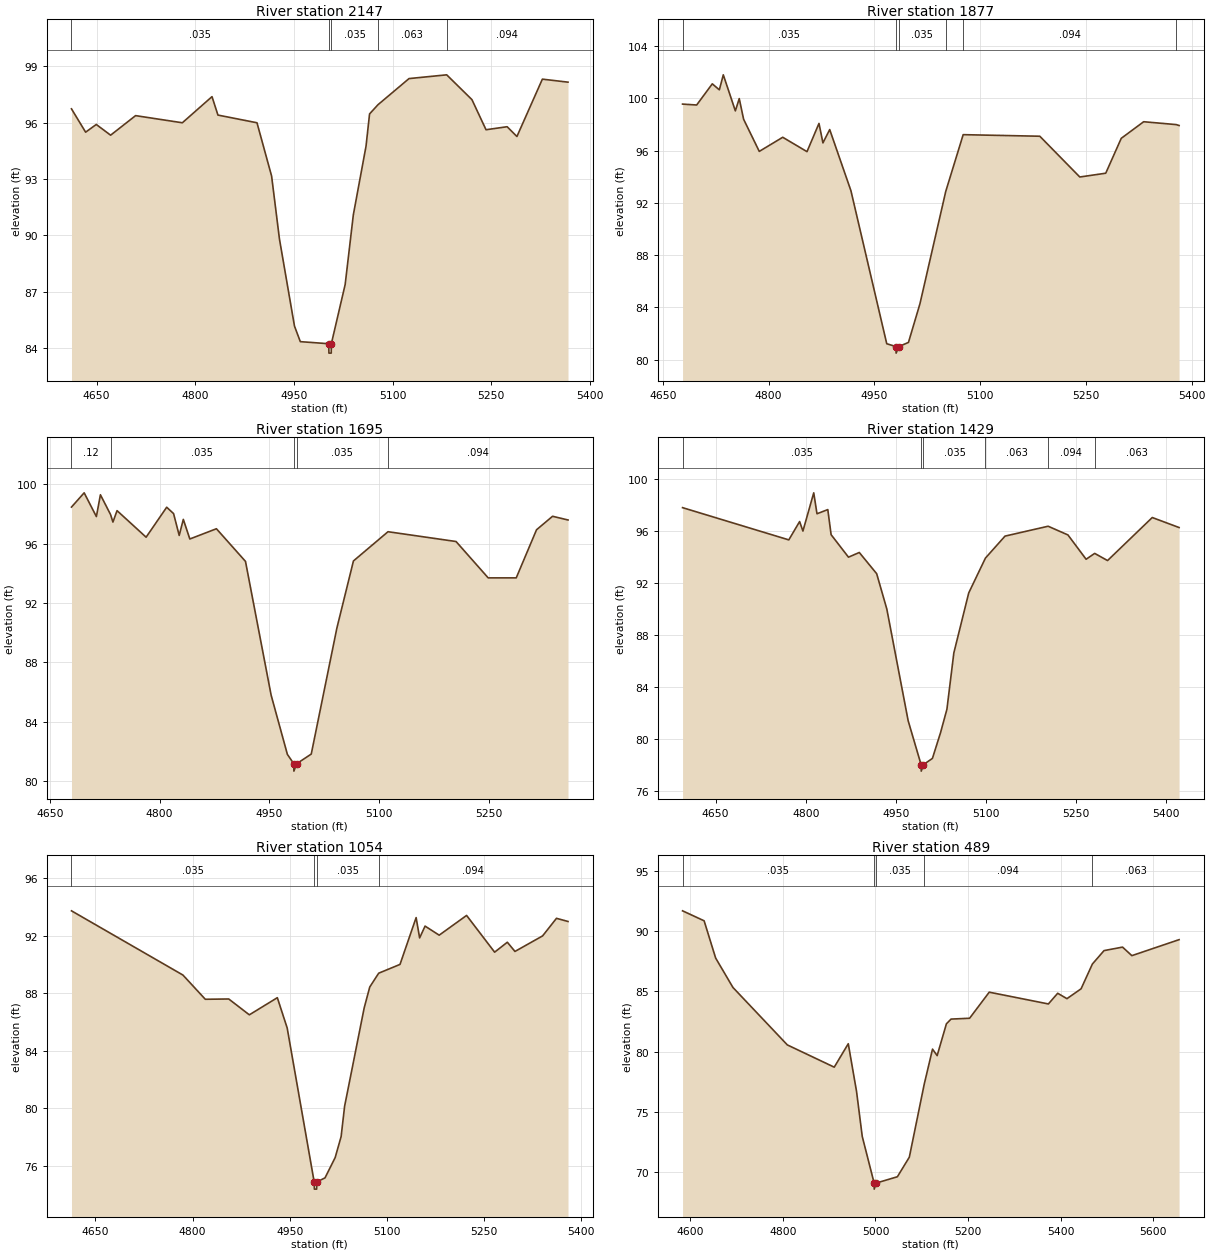
Type RM Length L Ch R = 1 ,2147    ,270,270,270
BEGIN DESCRIPTION:
Mapping XS 9dd2d2bf
END DESCRIPTION:
XS GIS Cut Line= 3
      2607192.58     13500801.68      2606854.02     13500986.58
      2606721.78     13501331.44
#Sta/Elev= 30
  4611.8   96.73  4633.3   95.49  4649.5    95.9  4671.3   95.33  4709.3   96.37
  4780.4   95.99  4825.5   97.38  4834.5    96.4  4893.9   95.99  4916.1   93.16
  4928.1    89.8  4950.9   85.18  4959.8   84.35    5003   84.24  5003.3   83.74
  5006.8   83.74    5007   84.24    5028   87.39  5040.4   91.09  5059.7   94.74
  5065.1   96.46  5077.9   96.95  5125.1   98.34  5182.4   98.54  5220.8   97.22
  5242.2   95.62  5274.3   95.78  5289.2   95.26  5327.9   98.31  5366.9   98.15
#Mann= 5 ,-1 , 0
  4611.8    .035       0    5003    .035       0    5007    .035       0
  5077.9    .063       0  5182.4    .094       0
Bank Sta=5003,5007
XS Rating Curve= 0 ,0
Exp/Cntr=0.3,0.1

Type RM Length L Ch R = 1 ,1877    ,182,182,182
BEGIN DESCRIPTION:
Mapping XS 2b4c6998
END DESCRIPTION:
XS GIS Cut Line= 3
      2606953.02     13500645.42      2606676.94     13500778.25
      2606489.73     13501129.27
#Sta/Elev= 30
    4678   99.56    4698   99.49  4720.2  101.11  4730.2  100.65  4735.8   101.8
  4752.9   99.04  4758.4   99.98  4764.6    98.4  4786.8   95.94  4820.1   97.02
  4854.5   95.92  4871.5   98.08  4877.1   96.59  4886.7   97.61  4916.8   92.93
  4967.6   81.22  4980.7      81  4980.9    80.5  4984.7      81  4998.4   81.32
  5014.7   84.28  5051.3   92.88    5076   97.22  5184.7    97.1  5241.4   93.98
  5278.2   94.27  5300.2   96.94    5332   98.21  5378.2   97.99  5382.2   97.92
#Mann= 6 ,-1 , 0
    4678    .035       0  4980.7    .035       0  4984.7    .035       0
  5051.3    .063       0    5076    .094       0  5378.2    .063       0
Bank Sta=4980.7,4984.7
XS Rating Curve= 0 ,0
Exp/Cntr=0.3,0.1

Type RM Length L Ch R = 1 ,1695    ,266,266,266
BEGIN DESCRIPTION:
Mapping XS ffd201d6
END DESCRIPTION:
XS GIS Cut Line= 3
      2606830.57     13500515.23      2606549.33     13500650.65
      2606377.43      13500973.6
#Sta/Elev= 30
  4679.7   98.47    4697   99.43  4713.7   97.83  4719.2    99.3  4733.1   97.96
  4736.3   97.46  4741.9   98.23  4781.6   96.44  4809.7   98.46  4819.1   98.03
  4826.8   96.56  4832.4   97.64  4841.3   96.32  4877.6   97.01  4917.3   94.81
  4952.3    85.8  4974.5   81.81  4983.2   81.18  4983.4   80.68  4987.2   81.18
  5007.1   81.83  5042.1   90.32  5064.7   94.84  5111.9   96.81  5204.8   96.15
  5248.7    93.7    5287    93.7  5314.7   96.94  5336.6   97.85  5357.7    97.6
#Mann= 5 ,-1 , 0
  4679.7     .12       0  4733.1    .035       0  4983.2    .035       0
  4987.2    .035       0  5111.9    .094       0
Bank Sta=4983.2,4987.2
XS Rating Curve= 0 ,0
Exp/Cntr=0.3,0.1

Type RM Length L Ch R = 1 ,1429    ,375,375,375
BEGIN DESCRIPTION:
Mapping XS 6587f0d1
END DESCRIPTION:
XS GIS Cut Line= 3
      2606736.83     13500301.69      2606364.44     13500463.15
        2606216.     13500856.37
#Sta/Elev= 30
  4594.9   97.83  4771.7   95.35  4789.7   96.76  4795.2   96.03  4813.2   98.97
  4818.6   97.36  4836.6   97.68  4842.1   95.75    4871   94.02    4889   94.38
  4917.9   92.75  4934.8   90.03  4970.3   81.44  4991.8   78.06  4992.1   77.56
  4995.8   78.06  5010.7   78.54  5024.2   80.52  5034.8   82.32  5046.3   86.65
  5071.1   91.27  5098.9   93.95  5131.5   95.64  5203.2    96.4  5236.2   95.73
  5266.4   93.86  5280.7   94.31  5302.1   93.76  5376.5   97.07  5421.1    96.3
#Mann= 6 ,-1 , 0
  4594.9    .035       0  4991.8    .035       0  4995.8    .035       0
  5098.9    .063       0  5203.2    .094       0  5280.7    .063       0
Bank Sta=4991.8,4995.8
XS Rating Curve= 0 ,0
Exp/Cntr=0.3,0.1

Type RM Length L Ch R = 1 ,1054    ,565,565,565
BEGIN DESCRIPTION:
Mapping XS a2340c07
END DESCRIPTION:
XS GIS Cut Line= 3
      2606434.71     13500002.23      2606104.02     13500189.71
      2605968.61     13500551.67
#Sta/Elev= 30
    4613   93.72  4785.1   89.26  4819.6   87.58  4855.8    87.6  4887.6    86.5
  4930.8   87.69    4946   85.59  4987.7    74.9    4988    74.4  4991.5    74.4
  4991.7    74.9  5004.4   75.18  5020.1   76.59  5029.3   78.05  5034.7   80.16
  5064.9   86.98  5073.5   88.43  5087.3   89.39  5120.2      90  5145.1   93.25
  5150.5   91.84  5158.9   92.66  5180.7   92.03    5223    93.4  5266.3   90.85
  5285.9   91.54  5297.7    90.9  5340.4   91.98  5361.8    93.2  5379.6   92.98
#Mann= 4 ,-1 , 0
    4613    .035       0  4987.7    .035       0  4991.7    .035       0
  5087.3    .094       0
Bank Sta=4987.7,4991.7
XS Rating Curve= 0 ,0
Exp/Cntr=0.3,0.1

Type RM Length L Ch R = 1 ,489     ,0,0,0
BEGIN DESCRIPTION:
NORTH OUTFALL 1.0
END DESCRIPTION:
XS GIS Cut Line= 3
      2606096.92     13499644.85      2605707.58     13499791.03
        2605741.     13500446.91
#Sta/Elev= 30
  4583.2   91.71  4629.8   90.88  4654.7   87.78  4692.1   85.33  4809.6   80.55
  4910.9    78.7  4941.2   80.65  4959.1   76.67  4971.4   72.93  4997.1   69.05
  4997.3   68.55  5001.1   69.05  5047.3   69.58  5073.1   71.21  5105.2   77.27
  5123.2    80.2  5133.2   79.66  5153.2   82.31  5163.3    82.7  5203.3   82.77
  5245.7   84.94  5373.5   83.96  5393.6   84.85  5413.6    84.4  5444.1   85.22
  5468.5   87.28  5493.7    88.4  5533.7   88.69  5553.8   87.98  5655.8   89.31
#Mann= 5 ,-1 , 0
  4583.2    .035       0  4997.1    .035       0  5001.1    .035       0
  5105.2    .094       0  5468.5    .063       0
Bank Sta=4997.1,5001.1
XS Rating Curve= 0 ,0
Exp/Cntr=0.3,0.1

Chan Stop Cuts=-1
Use User Specified Reach Order=0
Composite Channel Slope=5