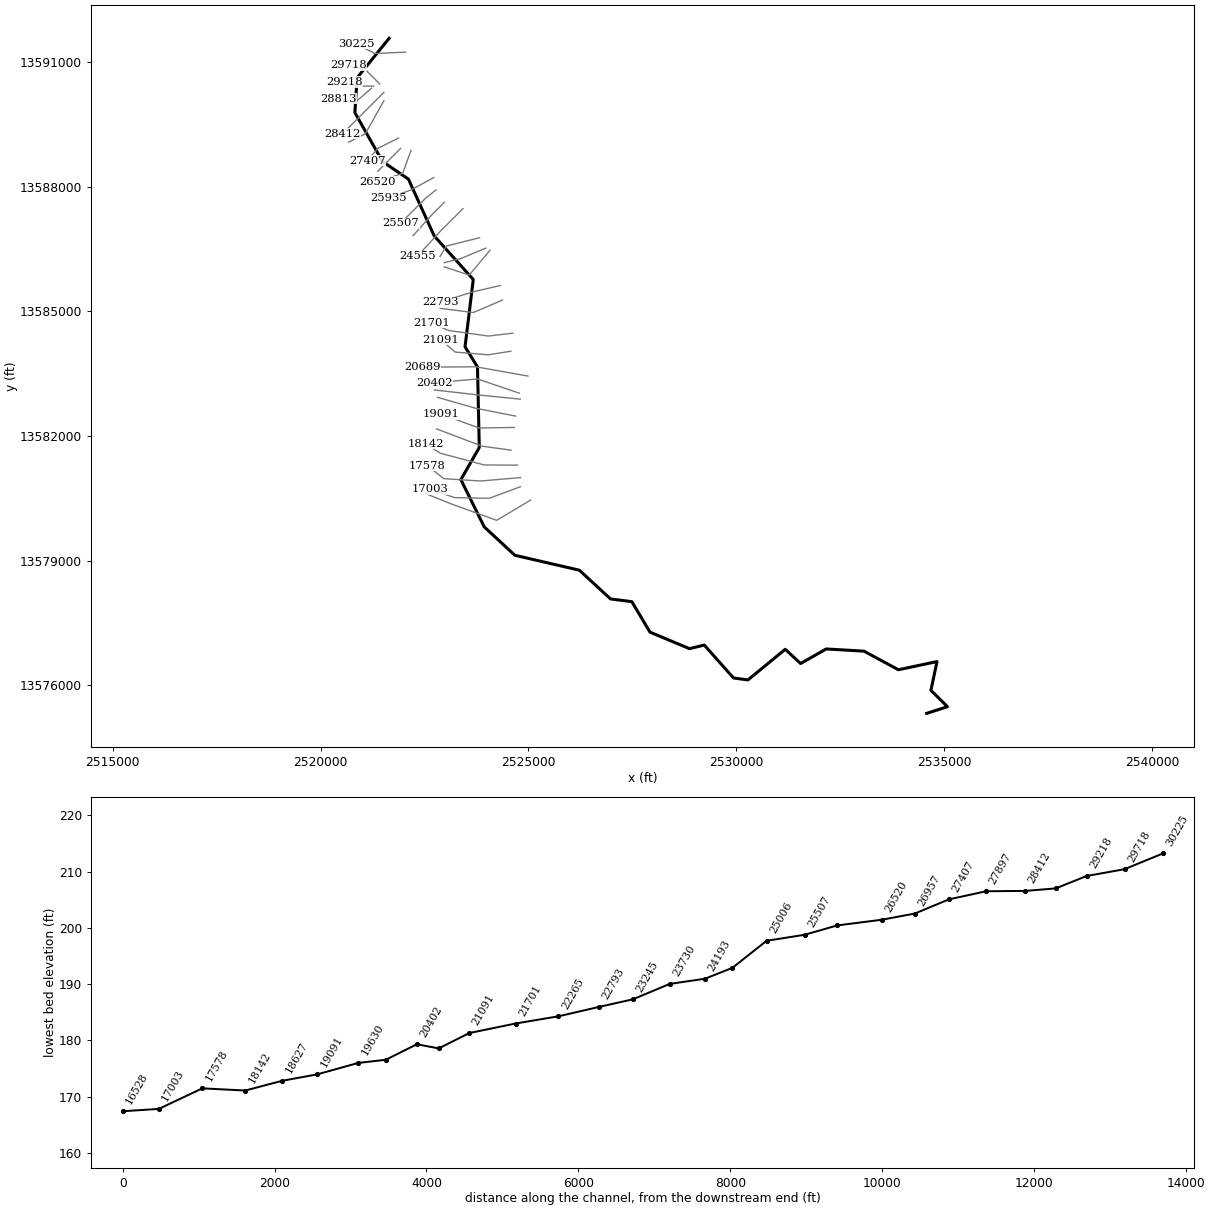
--- OAXLEY BRANCH.prj (project) ---

Proj Title=OAXLEY BRANCH Base Level Engineering
Current Plan=p01
Default Exp/Contr=0.3,0.1
English Units
Geom File=g01
Flow File=f01
Plan File=p01
Y Axis Title=Elevation
X Axis Title(PF)=Main Channel Distance
X Axis Title(XS)=Station
BEGIN DESCRIPTION:
OAXLEY BRANCH
END DESCRIPTION:
DSS Export Rating Curves= 0
DSS Export Rating Curve Sorted= 0
DSS Export Volume Flow Curves= 0
DXF OffsetX= 0
DXF OffsetY= 0
DXF ScaleX= 1
DXF ScaleY= 10

--- OAXLEY BRANCH.p01 (plan) ---

Plan Title=Multiple Run
Short Identifier=Multiple
Geom File=g01
Flow File=f01
Subcritical Flow
K Sum by GR= 0
Std Step Tol= 0.01
Critical Tol= 0.01
Num of Std Step Trials= 20
Max Error Tol= 0.3
Flow Tol Ratio= 0.001
Split Flow NTrial= 30
Split Flow Tol= 0.02
Split Flow Ratio= 0.02
Log Output Level= 0
Friction Slope Method= 1
Unsteady Friction Slope Method= 2
Unsteady Bridges Friction Slope Method= 1
Parabolic Critical Depth
Global Vel Dist=  1 , 1 , 1
Global Log Level= 0
CheckData=True
Encroach Param= -1, 0, 0, 0
BEGIN DESCRIPTION:
Multiple Run
END DESCRIPTION:

--- OAXLEY BRANCH.f01 (steady flow) ---

Flow Title=Multiple
Number of Profiles=7
Profile Names=10-year,25-year,50-year,1pct_min,100-year,1pct_plu,500-year
River Rch & RM= OAXLEY BRANCH,Reach-1,30225
    1022    1708    2350    1566    3125    6235    5473
River Rch & RM= OAXLEY BRANCH,Reach-1,28813
    1148    1920    2644    1761    3513    7009    6146
River Rch & RM= OAXLEY BRANCH,Reach-1,22793
    1550    2630    3655    2454    4897    9770    8714
River Rch & RM= OAXLEY BRANCH,Reach-1,20402
    1690    2876    4004    2692    5371   10717    9584
River Rch & RM= OAXLEY BRANCH,Reach-1,17578
    1750    2971    4130    2771    5528   11030    9823
Boundary for River Rch & Prof#=OAXLEY BRANCH,Reach-1,1
Up Type=0
Dn Type=3
Dn Slope=0.005
Boundary for River Rch & Prof#=OAXLEY BRANCH,Reach-1,2
Up Type=0
Dn Type=3
Dn Slope=0.005
Boundary for River Rch & Prof#=OAXLEY BRANCH,Reach-1,3
Up Type=0
Dn Type=3
Dn Slope=0.005
Boundary for River Rch & Prof#=OAXLEY BRANCH,Reach-1,4
Up Type=0
Dn Type=3
Dn Slope=0.005
Boundary for River Rch & Prof#=OAXLEY BRANCH,Reach-1,5
Up Type=0
Dn Type=3
Dn Slope=0.005
Boundary for River Rch & Prof#=OAXLEY BRANCH,Reach-1,6
Up Type=0
Dn Type=3
Dn Slope=0.005
Boundary for River Rch & Prof#=OAXLEY BRANCH,Reach-1,7
Up Type=0
Dn Type=3
Dn Slope=0.005

--- OAXLEY BRANCH.g01 (geometry) ---

Geom Title=Existing Conditions

River Reach=OAXLEY BRANCH,Reach-1
Reach XY= 30
      2521648.55     13591575.00      2520878.53     13590623.55
      2520826.04     13589785.43      2521488.45     13588611.37
      2522113.90     13588185.32      2522732.86     13586818.83
      2523672.76     13585769.07      2523474.64     13584149.80
      2523774.00     13583664.71      2523817.44     13581725.00
      2523374.50     13580952.25      2523935.48     13579815.20
      2524672.70     13579130.83      2526223.36     13578771.85
      2526972.57     13578080.52      2527485.10     13578013.89
      2527922.71     13577280.12      2528871.66     13576882.60
      2529227.74     13576969.66      2529930.67     13576176.98
      2530277.68     13576130.29      2531174.70     13576867.80
      2531543.21     13576525.09      2532159.91     13576875.77
      2533069.07     13576822.76      2533895.20     13576375.06
      2534823.84     13576571.88      2534677.06     13575880.85
      2535074.52     13575485.47      2534575.00     13575325.00

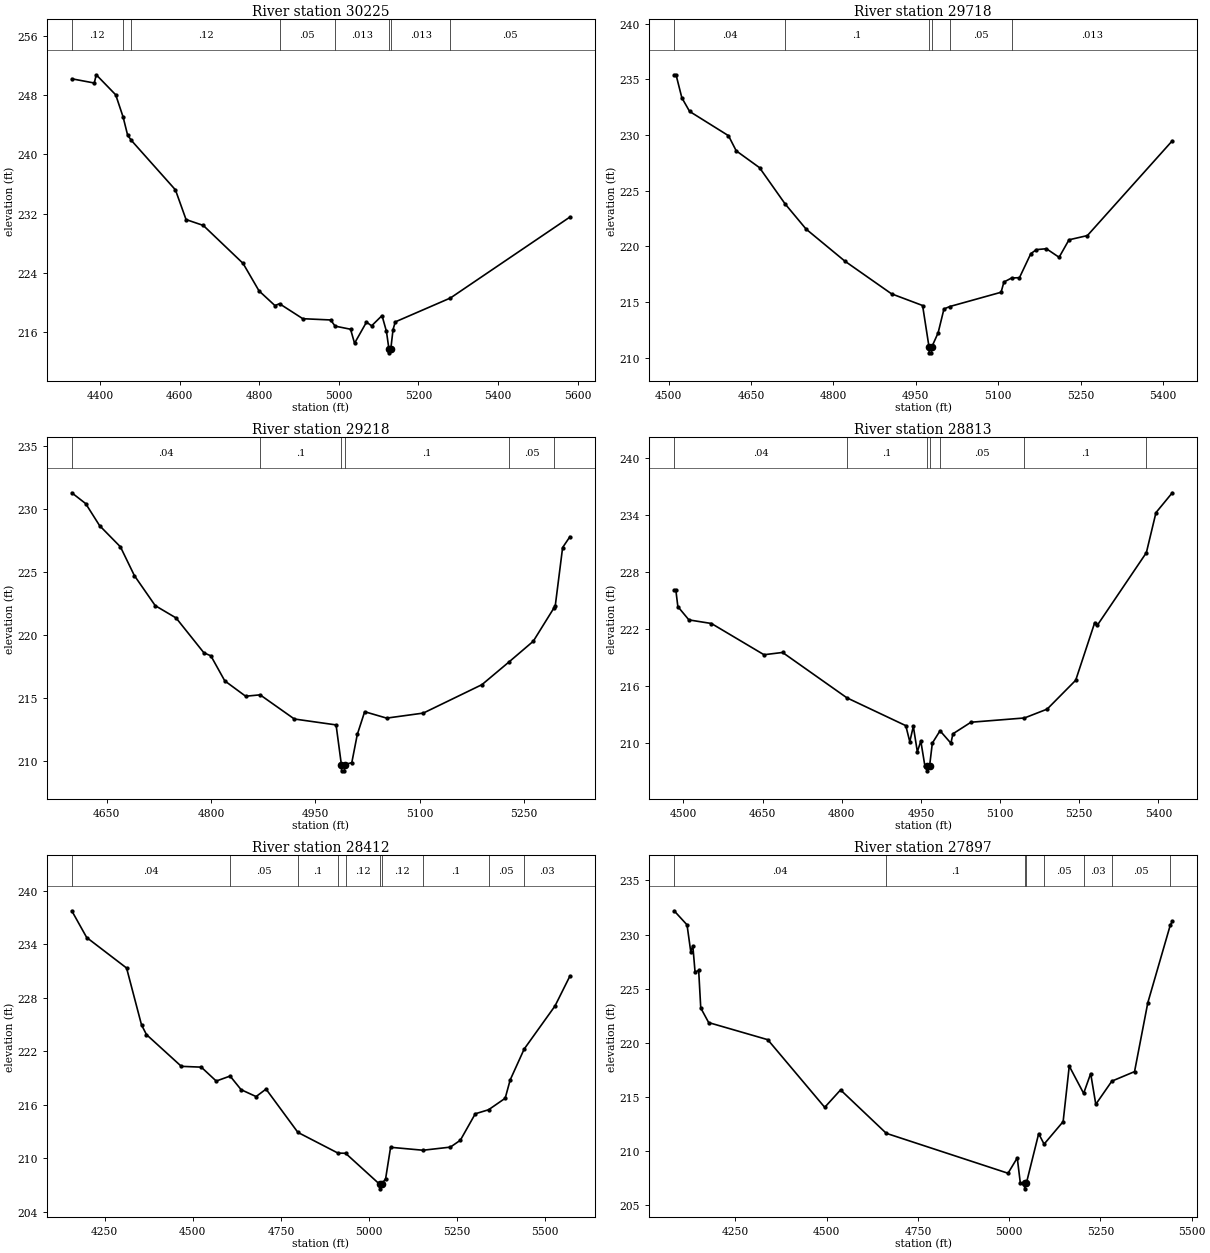
Type RM Length L Ch R = 1,30225,507,507,507
BEGIN DESCRIPTION:
OAXLEY BRANCH 52.0
END DESCRIPTION:
XS GIS Cut Line= 4
      2522045.42     13591242.50      2521290.17     13591209.83
      2521275.00     13591225.00      2520852.09     13591441.92
#Sta/Elev= 30
  4328.2  250.17  4384.8  249.60  4389.8  250.71  4438.7  248.01  4457.3  245.02
  4468.7  242.57  4478.2  241.86  4588.9  235.20  4615.6  231.20  4658.9  230.41
  4759.0  225.29  4799.1  221.59  4839.1  219.61  4850.6  219.86  4909.2  217.84
  4979.2  217.67  4990.4  216.84  5029.3  216.42  5039.3  214.53  5069.3  217.38
  5082.2  216.88  5108.4  218.26  5119.5  216.13  5125.8  213.74  5126.1  213.24
  5130.4  213.74  5136.1  216.37  5141.7  217.41  5280.4  220.63  5580.9  231.54
#Mann=8,-1,0
  4328.2    0.12       0  4457.3    0.05       0  4478.2    0.12       0
  4850.6    0.05       0  4990.4   0.013       0  5125.8    0.03       0
  5130.4   0.013       0  5280.4    0.05       0
Bank Sta=5125.8,5130.4
Exp/Cntr=0.3,0.1

Type RM Length L Ch R = 1,29718,500,500,500
BEGIN DESCRIPTION:
OAXLEY BRANCH 51.0
END DESCRIPTION:
XS GIS Cut Line= 3
      2521424.97     13590475.03      2521075.00     13590825.00
      2520675.04     13590924.99
#Sta/Elev= 30
  4509.9  235.40  4513.4  235.40  4524.0  233.33  4538.1  232.11  4608.9  229.93
  4623.0  228.57  4665.4  227.06  4712.1  223.80  4750.3  221.54  4821.0  218.66
  4905.8  215.73  4962.4  214.68  4974.2  210.93  4974.5  210.43  4978.6  210.43
  4978.9  210.93  4990.7  212.23  5001.3  214.37  5012.0  214.59  5105.3  215.87
  5110.5  216.79  5124.5  217.15  5138.8  217.18  5159.5  219.34  5169.8  219.70
  5187.8  219.78  5211.0  219.01  5229.0  220.58  5262.5  220.96  5417.1  229.47
#Mann=6,-1,0
  4509.9    0.04       0  4712.1     0.1       0  4974.2    0.05       0
  4978.9     0.1       0  5012.0    0.05       0  5124.5   0.013       0
Bank Sta=4974.2,4978.9
Exp/Cntr=0.3,0.1

Type RM Length L Ch R = 1,29218,405,405,405
BEGIN DESCRIPTION:
OAXLEY BRANCH 50.0
END DESCRIPTION:
XS GIS Cut Line= 3
      2521274.98     13590425.00      2520875.00     13590425.00
      2520575.00     13590525.00
#Sta/Elev= 30
  4600.0  231.32  4620.0  230.46  4640.0  228.71  4670.0  227.02  4690.0  224.74
  4720.0  222.35  4750.0  221.37  4790.0  218.60  4800.0  218.36  4820.0  216.37
  4850.0  215.15  4870.8  215.26  4920.0  213.34  4980.0  212.87  4987.6  209.72
  4987.9  209.22  4992.0  209.22  4992.4  209.72  5002.6  209.87  5010.5  212.11
  5021.1  213.92  5052.7  213.41  5105.4  213.81  5189.7  216.07  5228.1  217.85
  5263.5  219.52  5293.5  222.19  5295.1  222.33  5305.7  226.97  5316.2  227.83
#Mann=6,-1,0
  4600.0    0.04       0  4870.8     0.1       0  4987.6    0.05       0
  4992.4     0.1       0  5228.1    0.05       0  5293.5   0.013       0
Bank Sta=4987.6,4992.4
Exp/Cntr=0.3,0.1

Type RM Length L Ch R = 1,28813,401,401,401
BEGIN DESCRIPTION:
OAXLEY BRANCH 49.0
END DESCRIPTION:
XS GIS Cut Line= 3
      2521224.98     13590374.98      2520825.00     13590025.00
      2520424.99     13590125.00
#Sta/Elev= 30
  4482.5  226.04  4485.8  226.04  4489.6  224.32  4510.5  222.92  4553.2  222.54
  4652.8  219.25  4688.0  219.49  4809.9  214.71  4921.4  211.78  4929.0  210.09
  4935.7  211.71  4943.3  209.03  4949.9  210.15  4957.5  207.57  4961.7  207.52
  4962.1  207.02  4966.5  207.52  4971.7  209.94  4986.3  211.24  5006.9  209.93
  5010.7  210.92  5044.9  212.14  5146.3  212.59  5189.2  213.52  5243.3  216.56
  5279.4  222.64  5284.6  222.38  5377.2  230.00  5395.4  234.22  5426.3  236.31
#Mann=7,-1,0
  4482.5    0.04       0  4809.9     0.1       0  4961.7    0.05       0
  4966.5     0.1       0  4986.3    0.05       0  5146.3     0.1       0
  5377.2    0.05       0
Bank Sta=4961.7,4966.5
Exp/Cntr=0.3,0.1

Type RM Length L Ch R = 1,28412,515,515,515
BEGIN DESCRIPTION:
OAXLEY BRANCH 48.0
END DESCRIPTION:
XS GIS Cut Line= 3
      2521525.00     13590275.00      2520925.00     13589675.00
      2520525.01     13589275.01
#Sta/Elev= 30
  4156.3  237.76  4198.7  234.76  4311.9  231.34  4354.3  224.96  4368.4  223.87
  4467.4  220.31  4524.0  220.22  4566.4  218.66  4605.8  219.22  4637.1  217.69
  4679.6  216.92  4707.8  217.76  4798.3  212.90  4912.0  210.58  4933.6  210.56
  5030.7  207.07  5031.0  206.57  5035.6  207.07  5047.3  207.71  5061.4  211.23
  5153.5  210.90  5231.1  211.25  5259.4  212.02  5301.8  214.99  5339.5  215.44
  5386.7  216.73  5400.8  218.78  5440.6  222.25  5528.1  227.08  5570.5  230.44
#Mann=10,-1,0
  4156.3    0.04       0  4605.8    0.05       0  4798.3     0.1       0
  4912.0    0.05       0  4933.6    0.12       0  5030.7    0.05       0
  5035.6    0.12       0  5153.5     0.1       0  5339.5    0.05       0
  5440.6    0.03       0
Bank Sta=5030.7,5035.6
Exp/Cntr=0.3,0.1

Type RM Length L Ch R = 1,27897,490,490,490
BEGIN DESCRIPTION:
OAXLEY BRANCH 47.0
END DESCRIPTION:
XS GIS Cut Line= 3
      2521525.01     13590075.01      2521075.00     13589275.00
      2520675.01     13589075.00
#Sta/Elev= 30
  4081.8  232.20  4117.2  230.90  4127.4  228.42  4133.1  228.96  4139.2  226.53
  4149.1  226.69  4154.8  223.22  4176.5  221.87  4338.4  220.29  4494.5  214.04
  4537.9  215.65  4663.2  211.64  4996.8  207.95  5022.1  209.37  5030.4  207.07
  5042.0  207.01  5042.3  206.51  5046.9  207.01  5080.8  211.61  5095.6  210.64
  5147.8  212.72  5164.6  217.85  5204.0  215.33  5223.3  217.16  5237.3  214.32
  5281.3  216.46  5343.5  217.34  5379.8  223.70  5441.2  230.85  5446.9  231.23
#Mann=8,-1,0
  4081.8    0.04       0  4663.2     0.1       0  5042.0    0.05       0
  5046.9     0.1       0  5095.6    0.05       0  5204.0    0.03       0
  5281.3    0.05       0  5441.2    0.03       0
Bank Sta=5042,5046.9
Exp/Cntr=0.3,0.1

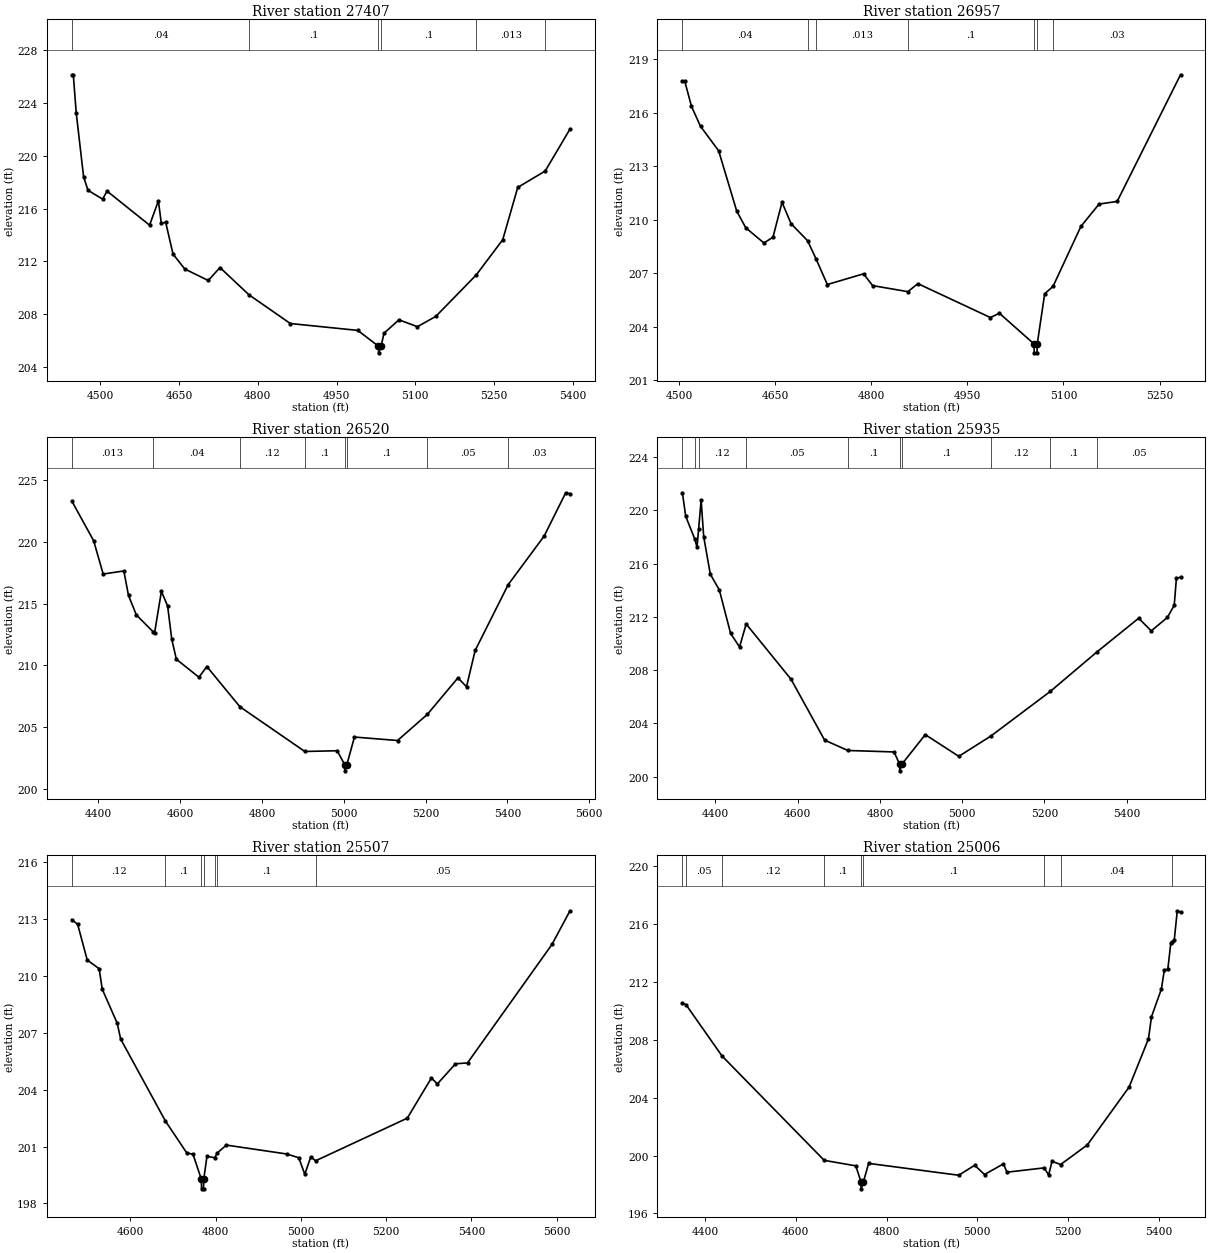
Type RM Length L Ch R = 1,27407,450,450,450
BEGIN DESCRIPTION:
OAXLEY BRANCH 46.0
END DESCRIPTION:
XS GIS Cut Line= 3
      2521874.96     13589174.98      2521375.00     13588925.00
      2521124.99     13588624.99
#Sta/Elev= 30
  4445.6  226.13  4448.3  226.13  4453.9  223.24  4467.9  218.41  4476.3  217.38
  4504.2  216.71  4512.6  217.32  4593.7  214.74  4610.5  216.58  4616.1  214.87
  4624.4  214.96  4638.4  212.55  4660.8  211.42  4705.5  210.55  4727.9  211.53
  4783.0  209.47  4862.0  207.29  4990.6  206.77  5030.0  205.57  5030.4  205.07
  5035.1  205.57  5040.4  206.55  5069.0  207.57  5104.2  207.05  5139.3  207.83
  5216.4  210.97  5266.9  213.64  5295.5  217.60  5347.8  218.84  5395.1  222.02
#Mann=6,-1,0
  4445.6    0.04       0  4783.0     0.1       0  5030.0    0.05       0
  5035.1     0.1       0  5216.4   0.013       0  5347.8    0.05       0
Bank Sta=5030,5035.1
Exp/Cntr=0.3,0.1

Type RM Length L Ch R = 1,26957,437,437,437
BEGIN DESCRIPTION:
OAXLEY BRANCH 45.0
END DESCRIPTION:
XS GIS Cut Line= 3
      2521925.02     13588925.02      2521675.00     13588675.00
      2521375.03     13588375.03
#Sta/Elev= 30
  4505.0  217.78  4508.6  217.78  4519.2  216.36  4533.3  215.24  4561.6  213.87
  4589.9  210.48  4604.0  209.55  4632.3  208.70  4646.4  209.02  4660.6  210.98
  4674.7  209.78  4700.4  208.83  4713.7  207.81  4731.3  206.37  4787.9  206.97
  4802.0  206.31  4857.1  205.97  4872.7  206.42  4985.9  204.52  5000.0  204.76
  5054.0  203.04  5054.4  202.54  5058.7  202.54  5059.1  203.04  5070.7  205.85
  5083.8  206.27  5127.3  209.63  5155.6  210.88  5183.9  211.03  5282.8  218.13
#Mann=7,-1,0
  4505.0    0.04       0  4700.4     0.1       0  4713.7   0.013       0
  4857.1     0.1       0  5054.0    0.05       0  5059.1     0.1       0
  5083.8    0.03       0
Bank Sta=5054,5059.1
Exp/Cntr=0.3,0.1

Type RM Length L Ch R = 1,26520,585,585,585
BEGIN DESCRIPTION:
OAXLEY BRANCH 44.0
END DESCRIPTION:
XS GIS Cut Line= 3
      2522175.01     13588875.02      2521975.00     13588325.00
      2521375.01     13588125.00
#Sta/Elev= 30
  4335.3  223.31  4388.5  220.10  4411.8  217.40  4462.3  217.65  4473.7  215.66
  4492.9  214.08  4534.1  212.71  4537.5  212.64  4554.1  215.99  4569.4  214.80
  4579.4  212.12  4590.7  210.49  4645.9  209.03  4665.2  209.90  4746.0  206.64
  4904.7  203.01  4983.8  203.07  5002.3  201.94  5002.7  201.44  5007.5  201.94
  5026.0  204.18  5131.4  203.90  5204.3  206.02  5279.0  208.98  5300.0  208.26
  5321.1  211.20  5401.9  216.54  5489.8  220.48  5542.5  223.99  5553.0  223.91
#Mann=8,-1,0
  4335.3   0.013       0  4534.1    0.04       0  4746.0    0.12       0
  4904.7     0.1       0  5002.3    0.05       0  5007.5     0.1       0
  5204.3    0.05       0  5401.9    0.03       0
Bank Sta=5002.3,5007.5
Exp/Cntr=0.3,0.1

Type RM Length L Ch R = 1,25935,428,428,428
BEGIN DESCRIPTION:
OAXLEY BRANCH 43.0
END DESCRIPTION:
XS GIS Cut Line= 3
      2522725.04     13588225.02      2522175.00     13587925.00
      2521624.98     13587724.99
#Sta/Elev= 30
  4319.5  221.33  4327.6  219.56  4349.9  217.83  4355.1  217.22  4359.1  218.64
  4365.1  220.78  4371.3  218.04  4387.4  215.21  4409.3  214.03  4436.8  210.76
  4458.6  209.74  4474.6  211.47  4583.9  207.31  4665.5  202.74  4721.9  201.96
  4834.5  201.85  4847.9  200.93  4848.3  200.43  4853.4  200.93  4910.4  203.15
  4991.9  201.52  5070.2  203.05  5214.6  206.40  5328.1  209.37  5429.5  211.90
  5460.1  210.95  5499.4  211.96  5516.0  212.87  5521.3  214.89  5531.3  214.99
#Mann=10,-1,0
  4319.5    0.12       0  4349.9    0.05       0  4359.1    0.12       0
  4474.6    0.05       0  4721.9     0.1       0  4847.9    0.05       0
  4853.4     0.1       0  5070.2    0.12       0  5214.6     0.1       0
  5328.1    0.05       0
Bank Sta=4847.9,4853.4
Exp/Cntr=0.3,0.1

Type RM Length L Ch R = 1,25507,501,501,501
BEGIN DESCRIPTION:
OAXLEY BRANCH 42.0
END DESCRIPTION:
XS GIS Cut Line= 3
      2522774.97     13587924.98      2522525.00     13587725.00
      2521925.03     13587125.03
#Sta/Elev= 30
  4462.7  212.98  4476.3  212.73  4498.7  210.85  4526.7  210.39  4533.9  209.31
  4569.1  207.51  4577.1  206.68  4682.1  202.35  4732.4  200.66  4746.8  200.60
  4766.5  199.27  4766.9  198.77  4771.5  198.77  4772.0  199.27  4779.6  200.49
  4798.0  200.41  4803.5  200.66  4825.2  201.08  4966.7  200.61  4995.0  200.41
  5009.1  199.54  5023.2  200.46  5034.4  200.25  5249.5  202.50  5306.1  204.62
  5320.2  204.31  5362.6  205.37  5390.9  205.42  5588.9  211.67  5631.3  213.45
#Mann=7,-1,0
  4462.7    0.12       0  4682.1     0.1       0  4766.5    0.05       0
  4772.0     0.1       0  4798.0    0.12       0  4803.5     0.1       0
  5034.4    0.05       0
Bank Sta=4766.5,4772
Exp/Cntr=0.3,0.1

Type RM Length L Ch R = 1,25006,451,451,451
BEGIN DESCRIPTION:
OAXLEY BRANCH 41.0
END DESCRIPTION:
XS GIS Cut Line= 3
      2522974.98     13587624.98      2522675.00     13587325.00
      2522225.01     13586825.02
#Sta/Elev= 30
  4350.5  210.52  4358.4  210.44  4437.7  206.89  4662.8  199.67  4732.3  199.29
  4743.7  198.20  4744.1  197.70  4749.3  198.20  4760.6  199.46  4959.0  198.64
  4994.1  199.33  5015.8  198.69  5057.6  199.43  5065.1  198.85  5147.1  199.15
  5157.0  198.66  5164.5  199.61  5183.3  199.38  5242.3  200.74  5334.2  204.74
  5376.8  208.07  5383.5  209.60  5405.2  211.51  5411.9  212.85  5419.4  212.87
  5426.1  214.72  5429.6  214.80  5433.6  214.90  5440.3  216.93  5447.4  216.83
#Mann=9,-1,0
  4350.5    0.12       0  4358.4    0.05       0  4437.7    0.12       0
  4662.8     0.1       0  4743.7    0.05       0  4749.3     0.1       0
  5147.1    0.05       0  5183.3    0.04       0  5429.6    0.05       0
Bank Sta=4743.7,4749.3
Exp/Cntr=0.3,0.1

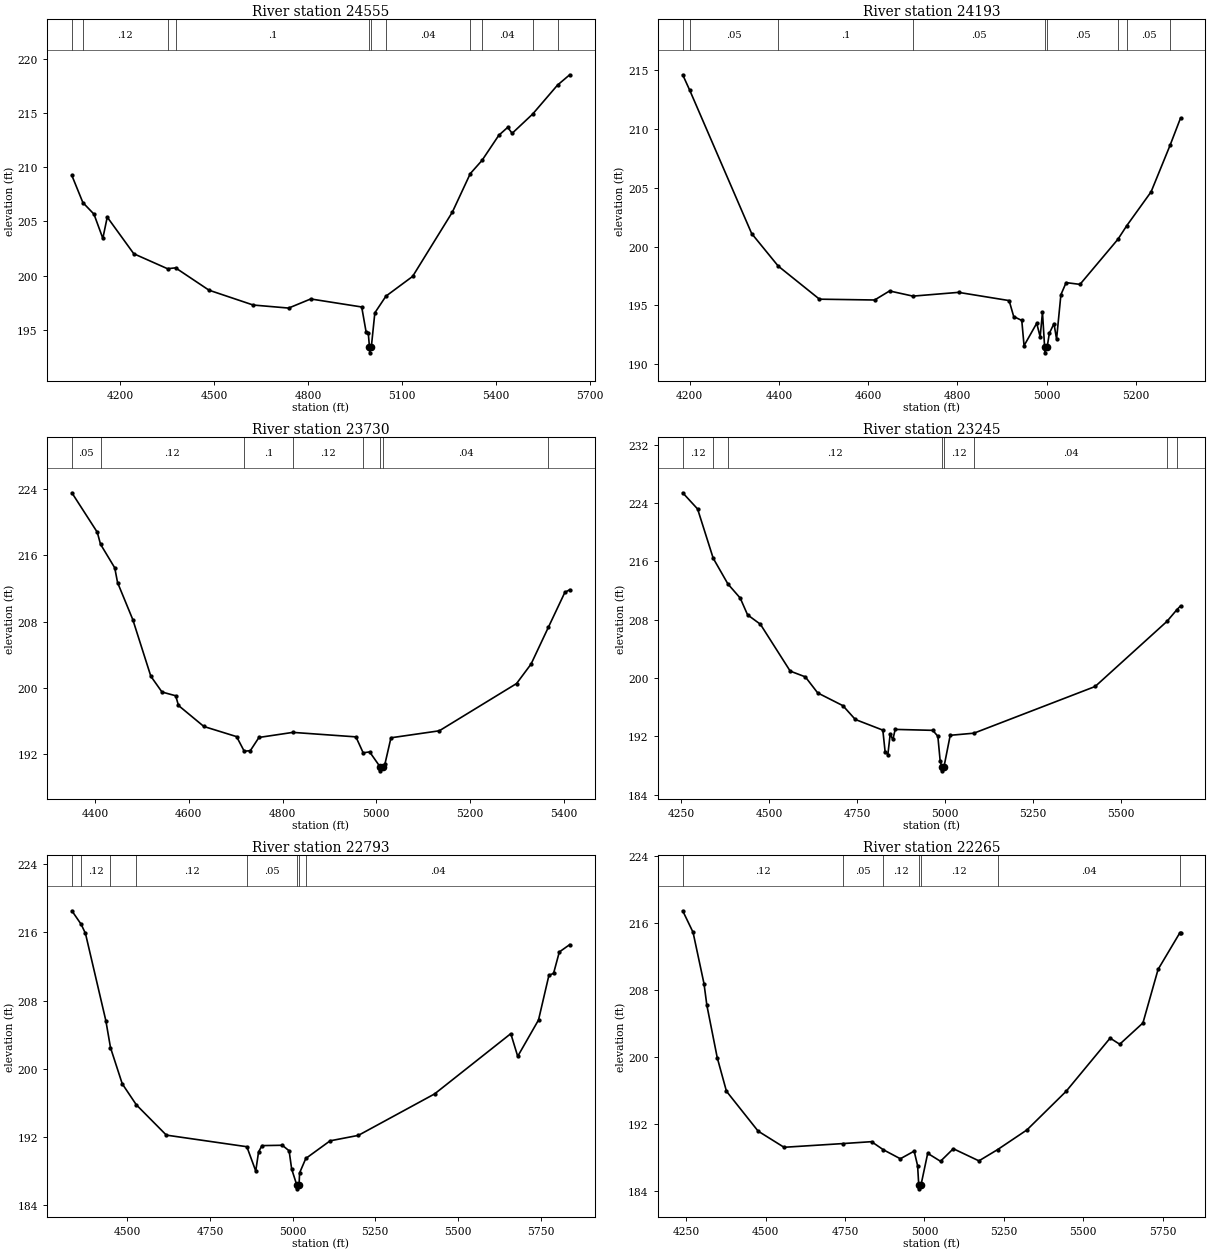
Type RM Length L Ch R = 1,24555,362,362,362
BEGIN DESCRIPTION:
OAXLEY BRANCH 40.0
END DESCRIPTION:
XS GIS Cut Line= 3
      2523424.99     13587474.99      2522875.00     13586925.00
      2522325.03     13586325.04
#Sta/Elev= 30
  4044.8  209.24  4080.0  206.74  4115.5  205.67  4143.8  203.44  4157.9  205.40
  4242.8  202.02  4350.6  200.64  4376.3  200.72  4483.2  198.66  4624.6  197.29
  4737.8  197.01  4808.5  197.85  4971.5  197.11  4985.4  194.83  4992.5  194.70
  4996.4  193.38  4996.9  192.88  5002.1  193.38  5013.5  196.57  5049.0  198.11
  5134.3  199.93  5261.3  205.86  5318.6  209.41  5356.1  210.63  5409.9  212.95
  5438.3  213.68  5452.5  213.13  5518.2  214.91  5597.6  217.58  5636.5  218.53
#Mann=11,-1,0
  4044.8    0.05       0  4080.0    0.12       0  4350.6    0.04       0
  4376.3     0.1       0  4996.4    0.05       0  5002.1     0.1       0
  5049.0    0.04       0  5318.6    0.05       0  5356.1    0.04       0
  5518.2    0.05       0  5597.6   0.013       0
Bank Sta=4996.4,5002.1
Exp/Cntr=0.3,0.1

Type RM Length L Ch R = 1,24193,463,463,463
BEGIN DESCRIPTION:
OAXLEY BRANCH 39.0
END DESCRIPTION:
XS GIS Cut Line= 3
      2523824.98     13586774.99      2523025.00     13586575.00
      2522875.02     13586325.04
#Sta/Elev= 30
  4184.3  214.63  4200.1  213.31  4338.9  201.11  4398.4  198.34  4490.9  195.52
  4614.6  195.45  4648.1  196.22  4700.5  195.78  4802.7  196.10  4916.1  195.40
  4926.4  194.04  4944.5  193.71  4949.6  191.56  4978.0  193.47  4985.7  192.31
  4990.9  194.40  4995.7  191.45  4996.2  190.95  5001.4  191.45  5006.3  192.61
  5016.7  193.44  5022.5  192.12  5032.2  195.90  5043.9  196.93  5075.0  196.78
  5160.0  200.62  5179.9  201.78  5234.4  204.66  5276.9  208.62  5300.4  210.94
#Mann=9,-1,0
  4184.3    0.04       0  4200.1    0.05       0  4398.4     0.1       0
  4700.5    0.05       0  4995.7    0.05       0  5001.4    0.05       0
  5160.0    0.12       0  5179.9    0.05       0  5276.9    0.12       0
Bank Sta=4995.7,5001.4
Exp/Cntr=0.3,0.1

Type RM Length L Ch R = 1,23730,485,485,485
BEGIN DESCRIPTION:
OAXLEY BRANCH 38.0
END DESCRIPTION:
XS GIS Cut Line= 3
      2523975.00     13586525.00      2523375.00     13586275.00
      2522975.01     13586175.00
#Sta/Elev= 30
  4350.4  223.51  4404.6  218.76  4411.5  217.32  4441.9  214.47  4447.9  212.70
  4480.4  208.24  4518.9  201.42  4542.7  199.52  4571.9  199.07  4577.9  197.90
  4632.1  195.37  4701.9  194.15  4718.2  192.39  4731.2  192.46  4749.6  194.05
  4822.0  194.66  4956.5  194.12  4972.0  192.20  4985.8  192.31  5007.9  190.53
  5008.3  190.03  5013.6  190.53  5018.4  190.84  5031.3  194.01  5134.4  194.85
  5299.3  200.54  5330.2  202.88  5367.4  207.34  5402.4  211.52  5412.7  211.84
#Mann=8,-1,0
  4350.4    0.05       0  4411.5    0.12       0  4718.2     0.1       0
  4822.0    0.12       0  4972.0    0.04       0  5007.9    0.04       0
  5013.6    0.04       0  5367.4    0.12       0
Bank Sta=5007.9,5013.6
Exp/Cntr=0.3,0.1

Type RM Length L Ch R = 1,23245,452,452,452
BEGIN DESCRIPTION:
OAXLEY BRANCH 37.0
END DESCRIPTION:
XS GIS Cut Line= 3
      2524074.98     13586474.97      2523575.00     13585875.00
      2522975.04     13586074.99
#Sta/Elev= 30
  4254.6  225.40  4296.9  223.18  4341.2  216.43  4383.0  212.90  4417.9  210.97
  4438.8  208.67  4475.2  207.38  4559.8  200.96  4602.8  200.17  4637.9  197.97
  4709.5  196.22  4744.7  194.33  4822.8  192.87  4829.3  189.90  4837.1  189.52
  4843.6  192.28  4851.4  191.60  4857.9  192.97  4964.6  192.84  4979.0  192.03
  4985.5  188.70  4990.4  187.79  4990.9  187.29  4996.2  187.79  5014.1  192.16
  5081.3  192.45  5425.6  198.85  5629.6  207.78  5657.0  209.34  5668.0  209.89
#Mann=8,-1,0
  4254.6    0.12       0  4341.2    0.05       0  4383.0    0.12       0
  4990.4    0.05       0  4996.2    0.12       0  5081.3    0.04       0
  5629.6    0.12       0  5657.0    0.04       0
Bank Sta=4990.4,4996.2
Exp/Cntr=0.3,0.1

Type RM Length L Ch R = 1,22793,528,528,528
BEGIN DESCRIPTION:
OAXLEY BRANCH 36.0
END DESCRIPTION:
XS GIS Cut Line= 3
      2524325.05     13585625.01      2523675.00     13585475.00
      2522874.99     13585225.00
#Sta/Elev= 30
  4332.5  218.53  4360.8  216.93  4373.6  215.87  4435.2  205.65  4449.3  202.48
  4484.8  198.24  4527.5  195.77  4618.2  192.22  4861.6  190.86  4888.5  188.01
  4897.0  190.24  4907.3  190.99  4968.8  191.03  4989.4  190.38  4997.1  188.24
  5012.2  186.42  5012.7  185.92  5019.5  186.42  5021.1  187.79  5039.8  189.48
  5113.3  191.55  5198.7  192.19  5429.2  197.05  5659.7  204.12  5680.6  201.46
  5743.5  205.72  5774.9  210.95  5789.1  211.20  5806.4  213.70  5837.8  214.56
#Mann=8,-1,0
  4332.5    0.05       0  4360.8    0.12       0  4449.3    0.05       0
  4527.5    0.12       0  4861.6    0.05       0  5012.2    0.05       0
  5019.5    0.05       0  5039.8    0.04       0
Bank Sta=5012.2,5019.5
Exp/Cntr=0.3,0.1

Type RM Length L Ch R = 1,22265,564,564,564
BEGIN DESCRIPTION:
OAXLEY BRANCH 35.0
END DESCRIPTION:
XS GIS Cut Line= 3
      2524374.97     13585274.99      2523675.00     13584975.00
      2522874.97     13585075.00
#Sta/Elev= 30
  4238.5  217.46  4271.1  214.89  4305.6  208.76  4314.6  206.18  4347.3  199.92
  4376.3  195.92  4476.0  191.16  4557.6  189.23  4741.9  189.67  4833.2  189.90
  4870.2  188.94  4923.9  187.86  4967.4  188.77  4978.3  187.03  4981.8  184.77
  4982.3  184.27  4989.2  184.77  5010.1  188.51  5050.4  187.56  5090.7  189.06
  5171.4  187.61  5230.1  188.95  5322.5  191.30  5446.0  195.91  5584.6  202.26
  5614.8  201.53  5687.9  204.07  5735.7  210.47  5804.5  214.85  5806.3  214.85
#Mann=7,-1,0
  4238.5    0.12       0  4741.9    0.05       0  4870.2    0.12       0
  4981.8    0.05       0  4989.2    0.12       0  5230.1    0.04       0
  5804.5   0.013       0
Bank Sta=4981.8,4989.2
Exp/Cntr=0.3,0.1

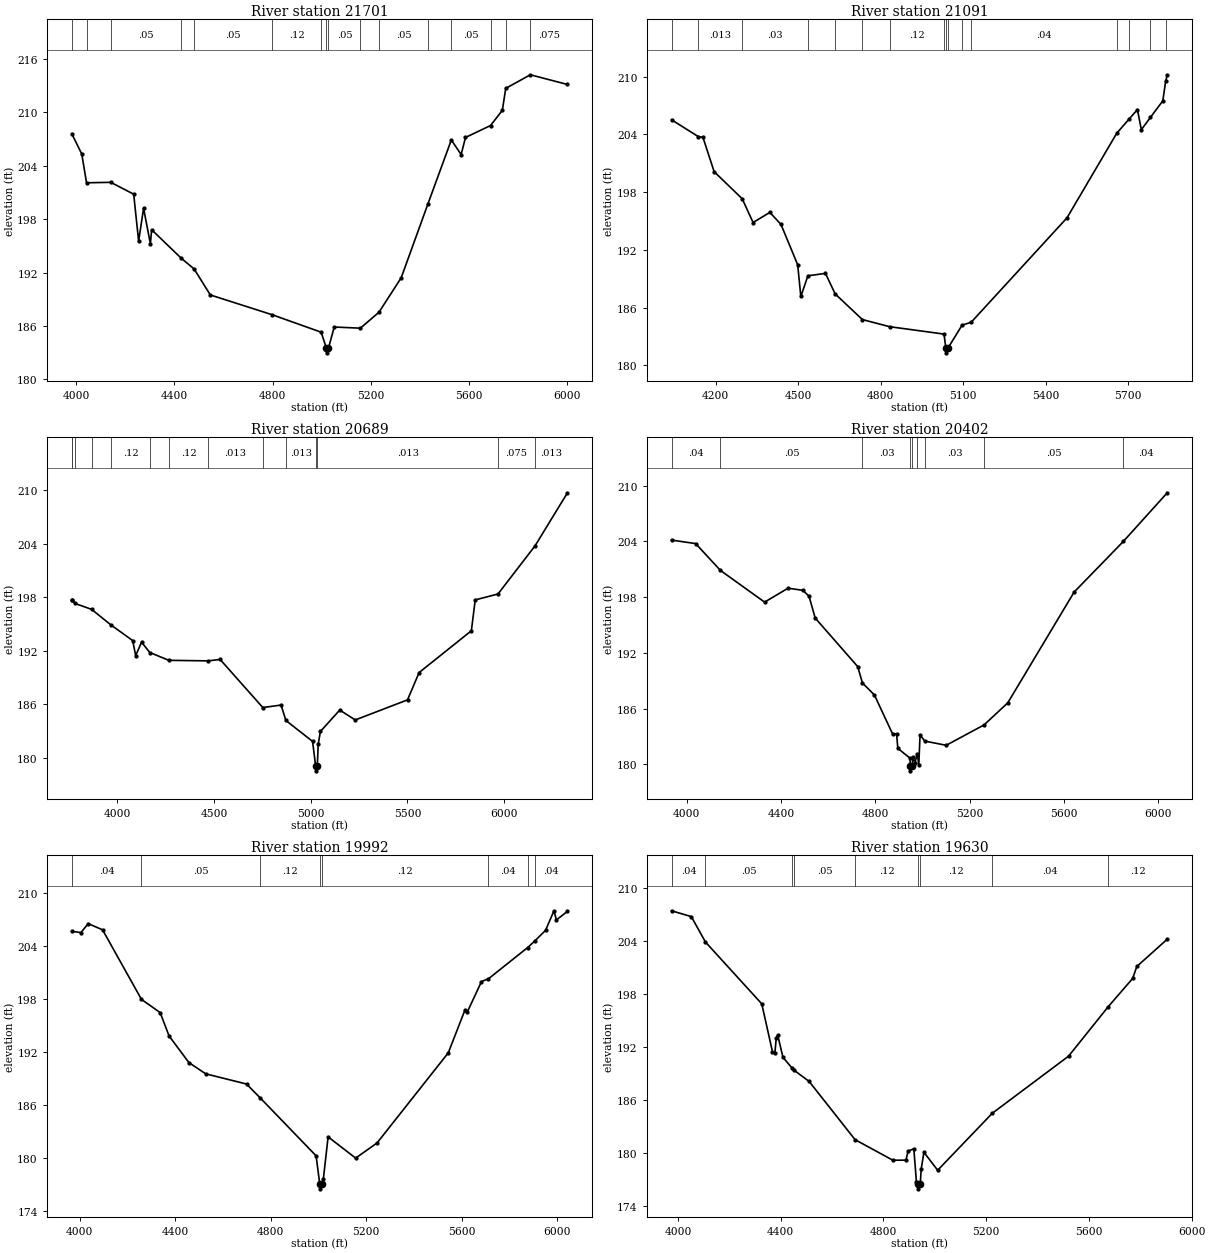
Type RM Length L Ch R = 1,21701,610,610,610
BEGIN DESCRIPTION:
Mapping XS 201a29b1
END DESCRIPTION:
XS GIS Cut Line= 4
      2524625.49     13584477.73      2524035.19     13584408.28
      2523075.99     13584542.83      2522659.70     13584729.29
#Sta/Elev= 30
  3981.9  207.60  4022.7  205.32  4042.0  202.09  4140.7  202.14  4234.1  200.81
  4254.3  195.54  4274.4  199.23  4302.2  195.23  4307.2  196.82  4426.5  193.65
  4480.5  192.40  4546.3  189.49  4797.0  187.28  4997.6  185.31  5019.3  183.49
  5019.8  182.99  5027.1  183.49  5051.1  185.89  5157.5  185.76  5233.1  187.55
  5323.7  191.42  5432.6  199.72  5527.9  206.90  5567.9  205.26  5585.6  207.18
  5687.7  208.52  5735.7  210.23  5749.4  212.69  5849.7  214.22  6001.0  213.13
#Mann=16,-1,0
  3981.9    0.05       0  4042.0   0.013       0  4140.7    0.05       0
  4426.5    0.12       0  4480.5    0.05       0  4797.0    0.12       0
  4997.6    0.05       0  5019.3    0.05       0  5027.1    0.05       0
  5157.5    0.04       0  5233.1    0.05       0  5432.6    0.12       0
  5527.9    0.05       0  5687.7    0.04       0  5749.4    0.05       0
  5849.7   0.075       0
Bank Sta=5019.3,5027.1
Exp/Cntr=0.3,0.1

Type RM Length L Ch R = 1,21091,402,402,402
BEGIN DESCRIPTION:
Mapping XS 470aad3f
END DESCRIPTION:
XS GIS Cut Line= 4
      2524577.71     13584043.69      2524035.19     13583956.89
      2523240.92     13584021.99      2522893.67     13584317.16
#Sta/Elev= 30
  4039.5  205.52  4136.9  203.77  4153.6  203.70  4194.3  200.13  4296.3  197.31
  4335.9  194.84  4396.7  195.89  4437.2  194.65  4498.0  190.45  4509.5  187.15
  4535.2  189.30  4599.1  189.55  4634.2  187.42  4733.2  184.75  4832.1  184.01
  5029.9  183.24  5036.7  181.79  5037.2  181.29  5044.5  181.79  5095.7  184.17
  5128.8  184.47  5477.2  195.33  5658.1  204.13  5703.5  205.62  5733.1  206.58
  5747.4  204.49  5780.1  205.76  5825.4  207.49  5835.7  209.52  5841.6  210.20
#Mann=16,-1,0
  4039.5    0.04       0  4136.9   0.013       0  4296.3    0.03       0
  4535.2    0.05       0  4634.2    0.12       0  4733.2    0.05       0
  4832.1    0.12       0  5029.9    0.04       0  5036.7    0.05       0
  5044.5    0.04       0  5095.7    0.05       0  5128.8    0.04       0
  5658.1    0.12       0  5703.5    0.04       0  5780.1    0.05       0
  5835.7   0.013       0
Bank Sta=5036.7,5044.5
Exp/Cntr=0.3,0.1

Type RM Length L Ch R = 1,20689,287,287,287
BEGIN DESCRIPTION:
OAXLEY BRANCH 32.0
END DESCRIPTION:
XS GIS Cut Line= 3
      2524990.04     13583444.74      2523732.53     13583668.75
      2522448.28     13583657.43
#Sta/Elev= 30
  3765.3  197.68  3767.3  197.70  3782.1  197.31  3867.7  196.65  3968.1  194.90
  4080.3  193.15  4095.5  191.46  4125.9  192.97  4168.9  191.81  4267.3  190.94
  4470.1  190.88  4531.9  191.04  4752.5  185.65  4847.1  185.93  4871.8  184.20
  5009.6  181.86  5025.8  179.06  5026.3  178.56  5034.1  179.06  5038.8  181.54
  5050.1  182.97  5150.1  185.37  5230.1  184.26  5500.2  186.51  5560.2  189.57
  5830.2  194.25  5850.2  197.71  5967.8  198.37  6159.1  203.76  6326.9  209.71
#Mann=14,-1,0
  3765.3   0.013       0  3767.3    0.04       0  3782.1   0.013       0
  3867.7    0.04       0  3968.1    0.12       0  4168.9   0.013       0
  4267.3    0.12       0  4470.1   0.013       0  4752.5    0.12       0
  4871.8   0.013       0  5025.8    0.03       0  5034.1   0.013       0
  5967.8   0.075       0  6159.1   0.013       0
Bank Sta=5025.8,5034.1
Exp/Cntr=0.3,0.1

Type RM Length L Ch R = 1,20402,410,410,410
BEGIN DESCRIPTION:
OAXLEY BRANCH 31.0
END DESCRIPTION:
XS GIS Cut Line= 3
      2524781.72     13583032.41      2523775.00     13583375.00
      2522741.80     13583284.15
#Sta/Elev= 30
  3936.6  204.14  4038.8  203.76  4143.4  200.88  4330.9  197.46  4430.3  198.96
  4493.1  198.73  4519.1  198.10  4545.2  195.75  4725.4  190.52  4745.5  188.76
  4796.1  187.47  4873.3  183.27  4890.2  183.28  4895.5  181.72  4947.2  180.66
  4948.4  179.80  4948.9  179.30  4957.5  179.80  4958.2  180.80  4968.3  180.18
  4977.6  181.15  4984.3  179.95  4989.6  183.15  5010.0  182.50  5100.4  182.05
  5260.7  184.24  5361.4  186.62  5642.5  198.54  5851.7  204.01  6037.2  209.23
#Mann=9,-1,0
  3936.6    0.04       0  4143.4    0.05       0  4745.5    0.03       0
  4948.4    0.05       0  4957.5    0.03       0  4977.6    0.05       0
  5010.0    0.03       0  5260.7    0.05       0  5851.7    0.04       0
Bank Sta=4948.4,4957.5
Exp/Cntr=0.3,0.1

Type RM Length L Ch R = 1,19992,362,362,362
BEGIN DESCRIPTION:
Mapping XS a264b512
END DESCRIPTION:
XS GIS Cut Line= 3
      2524803.40     13582889.18      2523805.16     13582989.01
      2522738.76     13583110.39
#Sta/Elev= 30
  3967.0  205.63  4005.6  205.49  4035.7  206.50  4096.0  205.80  4259.0  197.94
  4337.2  196.45  4374.8  193.80  4457.8  190.80  4528.2  189.53  4699.0  188.38
  4756.4  186.81  4990.5  180.27  5006.0  177.04  5006.5  176.54  5015.2  177.04
  5020.7  177.61  5040.8  182.41  5156.2  180.01  5245.7  181.72  5544.1  191.90
  5614.5  196.77  5624.6  196.56  5683.2  199.95  5712.5  200.27  5876.9  203.80
  5906.1  204.53  5951.7  205.74  5986.9  207.95  5997.0  206.91  6043.5  207.89
#Mann=8,-1,0
  3967.0    0.04       0  4259.0    0.05       0  4756.4    0.12       0
  5006.0    0.05       0  5015.2    0.12       0  5712.5    0.04       0
  5876.9    0.12       0  5906.1    0.04       0
Bank Sta=5006,5015.2
Exp/Cntr=0.3,0.1

Type RM Length L Ch R = 1,19630,539,539,539
BEGIN DESCRIPTION:
Mapping XS 5ea14b0f
END DESCRIPTION:
XS GIS Cut Line= 3
      2524690.57     13582481.20      2523722.69     13582672.17
      2522815.57     13582932.59
#Sta/Elev= 30
  3974.7  207.38  4051.7  206.72  4106.5  203.86  4326.0  196.87  4367.7  191.46
  4377.3  191.35  4382.4  193.02  4388.1  193.34  4408.5  190.83  4443.4  189.64
  4452.1  189.37  4510.4  188.11  4689.4  181.53  4836.6  179.21  4887.5  179.22
  4895.5  180.23  4918.1  180.51  4928.3  176.73  4933.9  176.48  4934.4  175.98
  4943.2  176.48  4946.8  178.22  4957.5  180.11  5010.9  178.08  5223.8  184.52
  5520.6  190.96  5674.5  196.53  5770.3  199.74  5786.4  201.09  5905.0  204.17
#Mann=9,-1,0
  3974.7    0.04       0  4106.5    0.05       0  4443.4    0.04       0
  4452.1    0.05       0  4689.4    0.12       0  4933.9    0.05       0
  4943.2    0.12       0  5223.8    0.04       0  5674.5    0.12       0
Bank Sta=4933.9,4943.2
Exp/Cntr=0.3,0.1

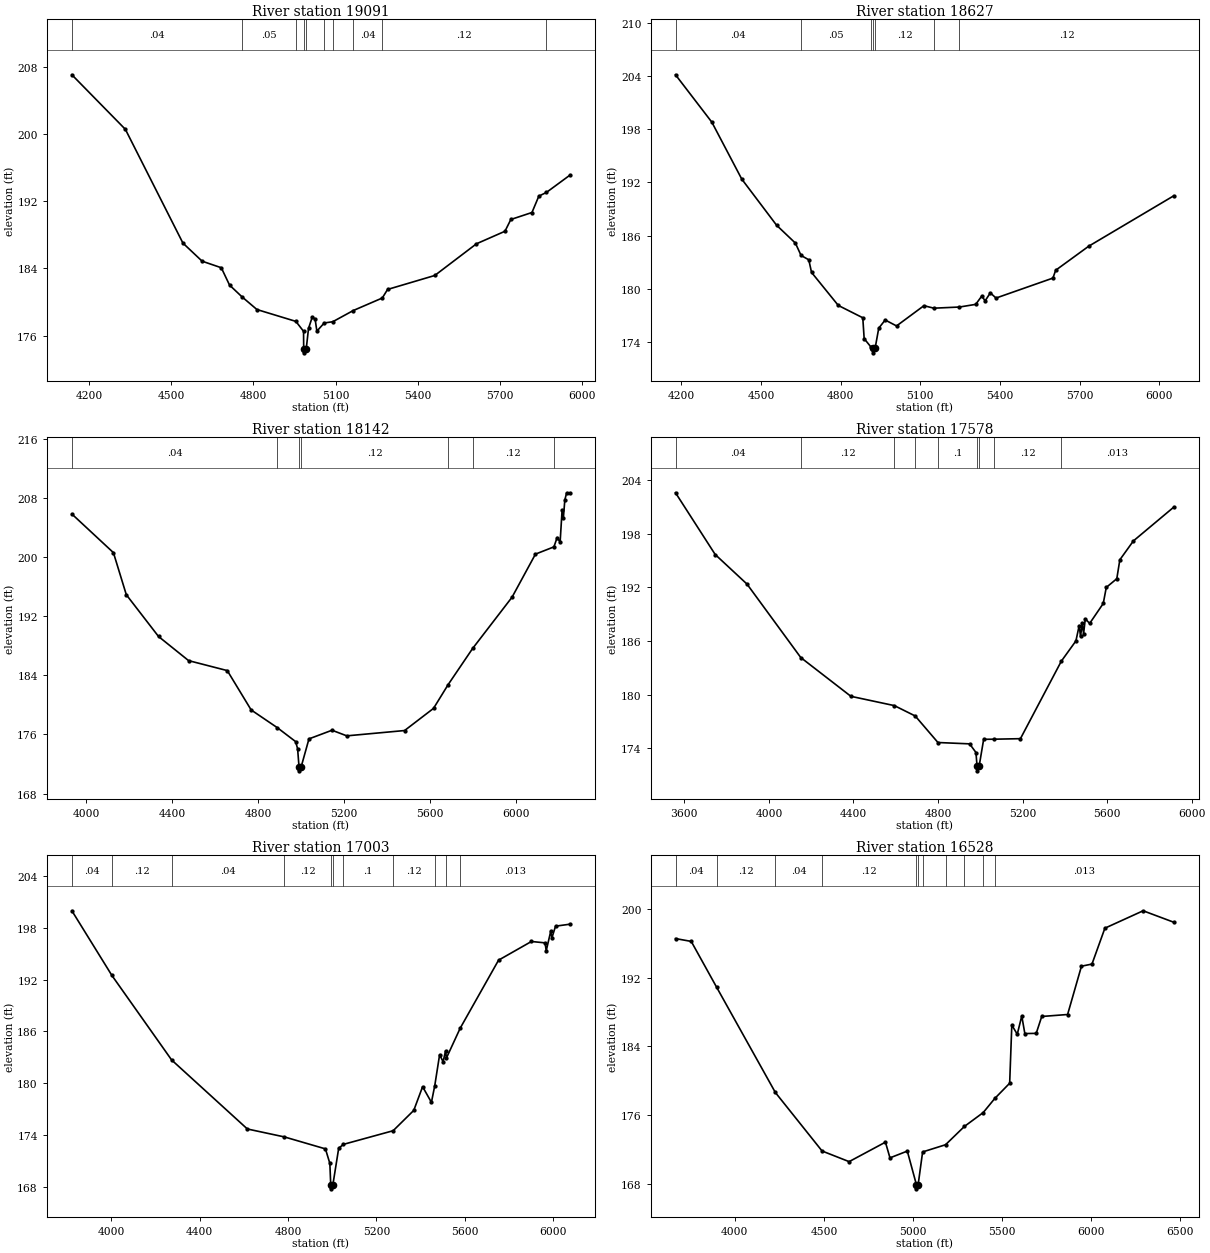
Type RM Length L Ch R = 1,19091,464,464,464
BEGIN DESCRIPTION:
Mapping XS 48578272
END DESCRIPTION:
XS GIS Cut Line= 3
      2524660.16     13582207.76      2523809.50     13582194.74
      2522902.37     13582528.94
#Sta/Elev= 30
  4137.6  207.02  4332.8  200.53  4542.8  187.00  4612.8  184.85  4682.8  184.07
  4712.8  182.01  4758.3  180.61  4812.8  179.10  4954.9  177.69  4982.9  176.51
  4983.4  174.45  4983.9  173.95  4992.8  174.45  5001.0  176.85  5014.5  178.19
  5025.1  177.96  5031.5  176.53  5058.3  177.50  5089.5  177.65  5164.2  178.98
  5270.1  180.47  5289.5  181.49  5461.6  183.15  5613.8  186.92  5717.8  188.41
  5739.2  189.81  5816.3  190.64  5841.4  192.59  5868.7  193.02  5955.1  195.09
#Mann=10,-1,0
  4137.6    0.04       0  4758.3    0.05       0  4954.9    0.12       0
  4983.4    0.05       0  4992.8    0.12       0  5058.3    0.05       0
  5089.5    0.12       0  5164.2    0.04       0  5270.1    0.12       0
  5868.7    0.05       0
Bank Sta=4983.4,4992.8
Exp/Cntr=0.3,0.1

Type RM Length L Ch R = 1,18627,485,485,485
BEGIN DESCRIPTION:
Mapping XS ad834d34
END DESCRIPTION:
XS GIS Cut Line= 3
      2524582.05     13581660.89      2523887.62     13581756.37
      2522789.76     13582172.95
#Sta/Elev= 30
  4178.3  204.12  4315.1  198.78  4427.7  192.37  4558.9  187.17  4629.6  185.16
  4651.0  183.77  4680.0  183.28  4690.4  181.86  4791.1  178.14  4883.3  176.75
  4888.5  174.40  4914.2  173.45  4920.2  173.30  4920.7  172.80  4929.6  173.30
  4943.4  175.58  4967.6  176.50  5010.4  175.83  5113.5  178.11  5150.9  177.83
  5247.3  177.96  5308.4  178.26  5331.3  179.20  5343.9  178.65  5363.4  179.56
  5384.8  178.97  5599.1  181.22  5609.4  182.10  5733.8  184.81  6053.5  190.48
#Mann=7,-1,0
  4178.3    0.04       0  4651.0    0.05       0  4914.2    0.12       0
  4920.2    0.05       0  4929.6    0.12       0  5150.9    0.05       0
  5247.3    0.12       0
Bank Sta=4920.2,4929.6
Exp/Cntr=0.3,0.1

Type RM Length L Ch R = 1,18142,564,564,564
BEGIN DESCRIPTION:
Mapping XS b0b3f7cd
END DESCRIPTION:
XS GIS Cut Line= 4
      2524738.28     13581300.64      2523935.37     13581304.98
      2522880.68     13581587.10      2522524.75     13581817.15
#Sta/Elev= 30
  3932.0  205.86  4125.3  200.63  4185.3  194.93  4335.3  189.27  4475.3  186.00
  4655.3  184.65  4766.4  179.32  4889.0  176.90  4973.4  175.03  4982.6  174.07
  4989.3  171.57  4989.8  171.07  4998.8  171.57  5035.5  175.40  5142.8  176.57
  5211.5  175.81  5480.6  176.53  5615.2  179.53  5683.3  182.75  5797.3  187.65
  5980.9  194.60  6089.7  200.43  6175.6  201.41  6190.7  202.68  6204.5  202.05
  6213.7  206.39  6219.7  205.35  6226.4  207.76  6234.8  208.74  6250.5  208.68
#Mann=7,-1,0
  3932.0    0.04       0  4889.0    0.12       0  4989.3    0.05       0
  4998.8    0.12       0  5683.3    0.05       0  5797.3    0.12       0
  6175.6   0.013       0
Bank Sta=4989.3,4998.8
Exp/Cntr=0.3,0.1

Type RM Length L Ch R = 1,17578,575,575,575
BEGIN DESCRIPTION:
Mapping XS 4915404b
END DESCRIPTION:
XS GIS Cut Line= 4
      2524812.08     13581001.16      2523848.56     13580918.70
      2522963.14     13580975.12      2522569.11     13581286.88
#Sta/Elev= 30
  3558.1  202.58  3745.9  195.67  3896.4  192.36  4150.7  184.14  4387.9  179.80
  4593.5  178.76  4692.2  177.60  4799.7  174.63  4949.6  174.48  4979.6  173.51
  4984.8  171.96  4985.3  171.46  4994.5  171.96  5016.0  174.99  5063.4  175.00
  5190.0  175.06  5383.4  183.73  5452.5  186.00  5468.0  187.72  5474.3  186.50
  5482.4  187.99  5488.8  186.80  5496.8  188.47  5517.6  187.96  5581.8  190.19
  5596.2  191.99  5645.9  192.96  5660.3  195.08  5724.4  197.19  5914.8  200.96
#Mann=9,-1,0
  3558.1    0.04       0  4150.7    0.12       0  4593.5    0.04       0
  4692.2    0.12       0  4799.7     0.1       0  4984.8    0.05       0
  4994.5     0.1       0  5063.4    0.12       0  5383.4   0.013       0
Bank Sta=4984.8,4994.5
Exp/Cntr=0.3,0.1

Type RM Length L Ch R = 1,17003,475,475,475
BEGIN DESCRIPTION:
Mapping XS 3a946c74
END DESCRIPTION:
XS GIS Cut Line= 4
      2524803.42     13580779.81      2524056.89     13580502.03
      2523219.22     13580519.39      2522633.25     13580727.74
#Sta/Elev= 30
  3820.7  199.95  4002.0  192.47  4272.5  182.70  4615.6  174.72  4783.7  173.80
  4969.2  172.42  4989.2  170.74  4993.1  168.30  4993.6  167.80  5003.1  168.30
  5029.2  172.49  5050.4  172.94  5275.9  174.52  5369.3  176.87  5409.3  179.61
  5449.3  177.80  5464.4  179.73  5486.4  183.31  5502.0  182.50  5513.5  183.75
  5517.3  182.93  5579.5  186.37  5753.4  194.24  5902.3  196.40  5964.0  196.24
  5969.3  195.33  5989.6  197.57  5994.9  196.81  6011.5  198.17  6077.0  198.40
#Mann=11,-1,0
  3820.7    0.04       0  4002.0    0.12       0  4272.5    0.04       0
  4783.7    0.12       0  4993.1    0.05       0  5003.1    0.12       0
  5050.4     0.1       0  5275.9    0.12       0  5464.4   0.013       0
  5513.5    0.12       0  5579.5   0.013       0
Bank Sta=4993.1,5003.1
Exp/Cntr=0.3,0.1

Type RM Length L Ch R = 1,16528,364,364,364
BEGIN DESCRIPTION:
Mapping XS cc13a0bb
END DESCRIPTION:
XS GIS Cut Line= 4
      2525050.78     13580458.60      2524234.85     13579972.52
      2523119.39     13580376.16      2522508.69     13580623.04
#Sta/Elev= 30
  3667.6  196.56  3755.8  196.23  3897.7  190.91  4227.8  178.62  4489.9  171.80
  4641.6  170.56  4845.4  172.83  4870.8  171.00  4968.1  171.79  5019.0  167.89
  5019.5  167.39  5029.0  167.89  5054.0  171.69  5182.6  172.53  5288.3  174.66
  5394.0  176.28  5458.7  177.92  5542.4  179.70  5554.4  186.48  5585.0  185.41
  5610.3  187.54  5627.5  185.49  5691.3  185.51  5722.3  187.48  5867.4  187.71
  5945.2  193.34  6004.2  193.59  6076.6  197.77  6291.2  199.80  6462.3  198.47
#Mann=11,-1,0
  3667.6    0.04       0  3897.7    0.12       0  4227.8    0.04       0
  4489.9    0.12       0  5019.0    0.05       0  5029.0    0.12       0
  5054.0    0.05       0  5182.6    0.12       0  5288.3   0.013       0
  5394.0    0.05       0  5458.7   0.013       0
Bank Sta=5019,5029
Exp/Cntr=0.3,0.1