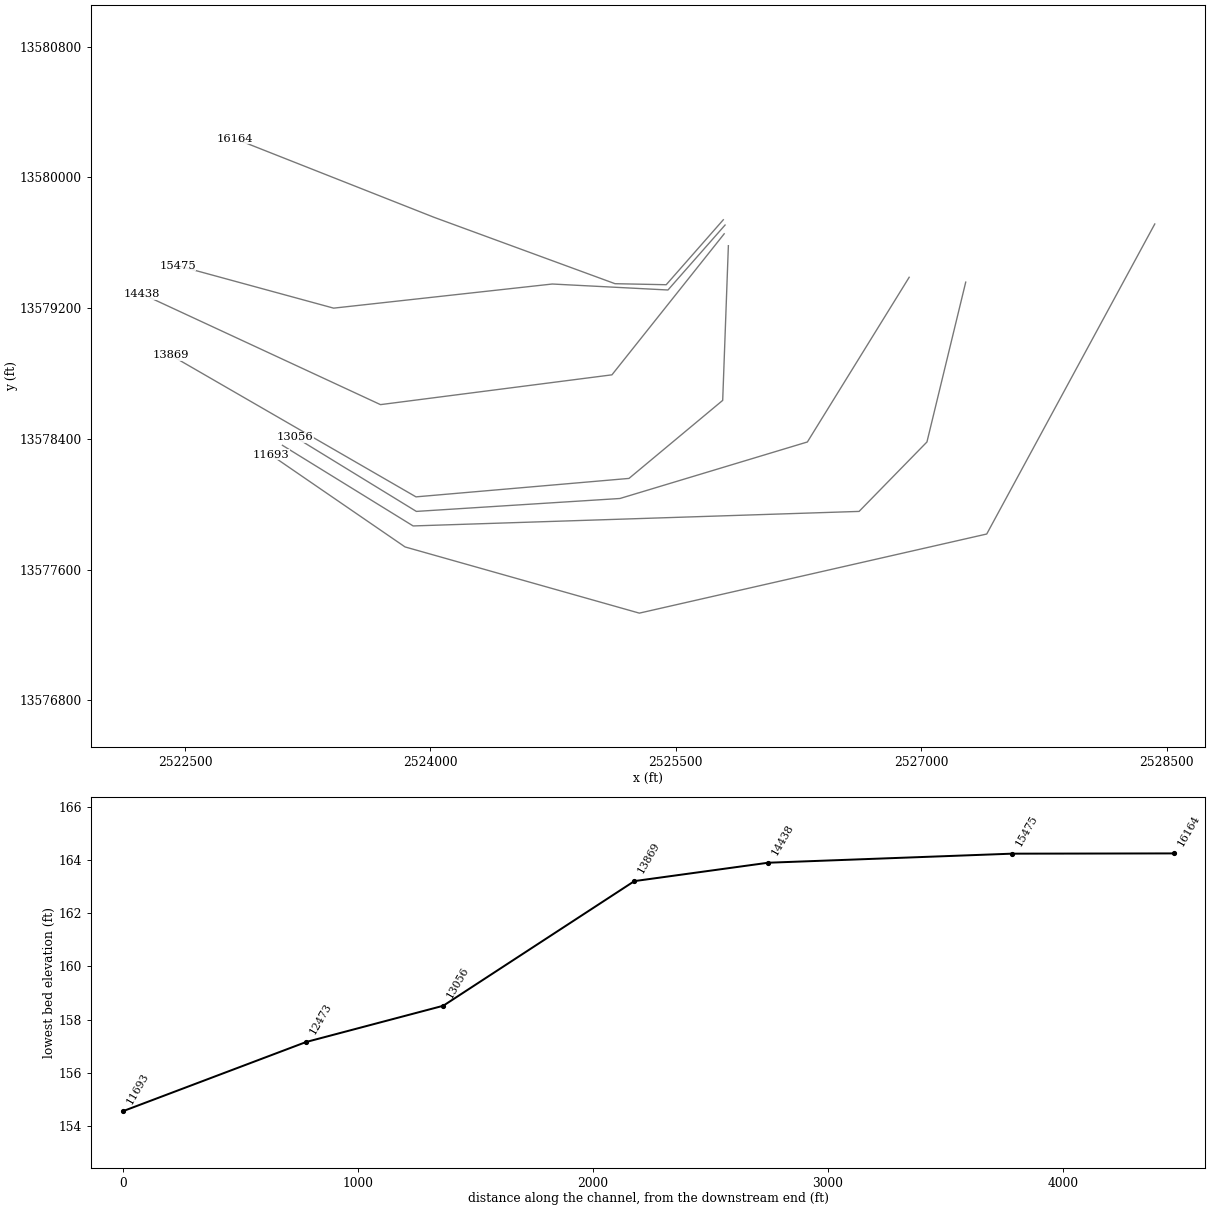
HEC-RAS study OAXLEY BRANCH.prj: OAXLEY BRANCH Base Level Engineering

--- OAXLEY BRANCH.g01 (geometry) --- (continued)

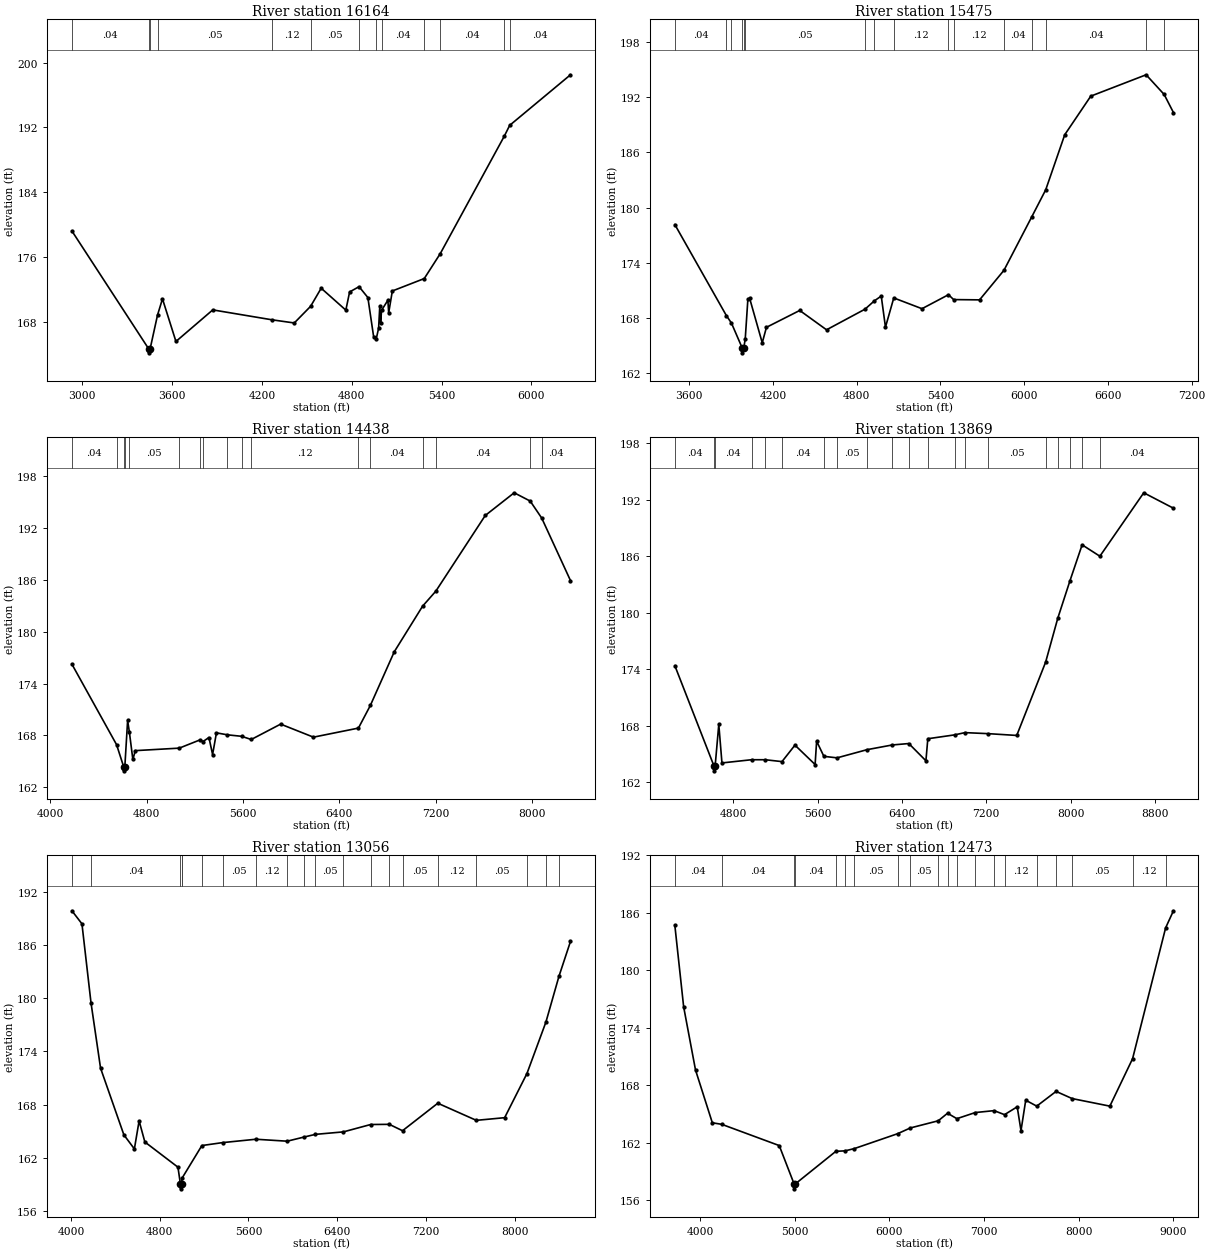
Type RM Length L Ch R = 1,16164,689,689,689
BEGIN DESCRIPTION:
Mapping XS e508e132
END DESCRIPTION:
XS GIS Cut Line= 5
      2525790.21     13579740.54      2525441.19     13579343.20
      2525128.17     13579349.55      2524022.17     13579755.50
      2522802.57     13580237.26
#Sta/Elev= 30
  2930.1  179.25  3442.7  164.74  3443.2  164.24  3452.8  164.74  3502.0  168.88
  3535.2  170.89  3625.2  165.64  3871.3  169.53  4269.9  168.30  4415.9  167.92
  4525.0  169.97  4595.7  172.20  4760.4  169.50  4785.6  171.74  4848.8  172.39
  4907.6  171.05  4946.0  166.24  4963.5  165.95  4979.4  167.28  4987.2  169.96
  4992.6  167.90  4999.1  169.48  5041.3  170.72  5046.7  169.17  5071.1  171.86
  5284.4  173.39  5391.3  176.46  5819.2  190.93  5855.2  192.26  6261.5  198.49
#Mann=13,-1,0
  2930.1    0.04       0  3442.7    0.04       0  3452.8    0.04       0
  3502.0    0.05       0  4269.9    0.12       0  4525.0    0.05       0
  4848.8    0.04       0  4963.5    0.05       0  4999.1    0.04       0
  5284.4   0.013       0  5391.3    0.04       0  5819.2    0.05       0
  5855.2    0.04       0
Bank Sta=3442.7,3452.8
Exp/Cntr=0.3,0.1

Type RM Length L Ch R = 1,15475,1037,1037,1037
BEGIN DESCRIPTION:
Mapping XS 8640117f
END DESCRIPTION:
XS GIS Cut Line= 5
      2525800.95     13579708.33      2525451.93     13579310.98
      2524744.83     13579347.52      2523408.02     13579199.95
      2522453.81     13579460.19
#Sta/Elev= 30
  3498.2  178.15  3867.7  168.26  3903.2  167.47  3981.4  164.73  3981.9  164.23
  3991.5  164.73  4002.3  165.74  4021.1  170.03  4034.0  170.14  4124.1  165.32
  4154.2  167.00  4392.6  168.83  4584.6  166.73  4860.2  168.97  4927.6  169.88
  4976.4  170.39  5006.6  167.02  5066.1  170.19  5268.2  169.02  5457.9  170.54
  5494.9  170.01  5680.6  169.98  5855.3  173.19  6052.6  178.94  6154.2  181.92
  6290.5  187.90  6477.0  192.09  6873.4  194.41  7002.8  192.27  7069.1  190.31
#Mann=16,-1,0
  3498.2    0.04       0  3867.7   0.013       0  3903.2    0.04       0
  3981.4    0.05       0  3991.5    0.04       0  4002.3    0.05       0
  4860.2    0.12       0  4927.6     0.1       0  5066.1    0.12       0
  5457.9    0.05       0  5494.9    0.12       0  5855.3    0.04       0
  6052.6   0.013       0  6154.2    0.04       0  6873.4   0.013       0
  7002.8    0.04       0
Bank Sta=3981.4,3991.5
Exp/Cntr=0.3,0.1

Type RM Length L Ch R = 1,14438,569,569,569
BEGIN DESCRIPTION:
Mapping XS ea0ca9bf
END DESCRIPTION:
XS GIS Cut Line= 4
      2525795.58     13579654.64      2525109.41     13578791.96
      2523694.48     13578609.67      2522236.12     13579286.76
#Sta/Elev= 30
  4181.0  176.24  4551.6  166.92  4609.8  164.39  4610.3  163.89  4620.2  164.39
  4643.3  169.73  4658.1  168.35  4686.6  165.21  4707.4  166.23  5071.9  166.52
  5246.7  167.49  5268.5  167.28  5318.0  167.75  5348.2  165.78  5380.2  168.29
  5471.4  168.06  5588.6  167.89  5669.0  167.52  5912.9  169.30  6185.1  167.79
  6558.3  168.84  6657.1  171.46  6855.7  177.68  7090.7  182.96  7200.6  184.70
  7610.5  193.46  7850.5  196.09  7983.4  195.13  8079.0  193.16  8317.8  185.92
#Mann=17,-1,0
  4181.0    0.04       0  4551.6   0.013       0  4609.8    0.05       0
  4620.2   0.013       0  4658.1    0.05       0  5071.9     0.1       0
  5246.7    0.12       0  5268.5    0.05       0  5471.4    0.12       0
  5588.6    0.05       0  5669.0    0.12       0  6558.3    0.05       0
  6657.1    0.04       0  7090.7   0.013       0  7200.6    0.04       0
  7983.4   0.013       0  8079.0    0.04       0
Bank Sta=4609.8,4620.2
Exp/Cntr=0.3,0.1

Type RM Length L Ch R = 1,13869,813,813,813
BEGIN DESCRIPTION:
Mapping XS b69aebd5
END DESCRIPTION:
XS GIS Cut Line= 5
      2525821.22     13579581.93      2525786.49     13578635.71
      2525213.58     13578158.28      2523911.49     13578045.43
      2522409.90     13578913.41
#Sta/Elev= 30
  4243.2  174.37  4615.2  163.70  4615.7  163.20  4625.6  163.70  4660.4  168.13
  4690.4  164.04  4971.0  164.38  5101.0  164.38  5260.5  164.18  5383.6  165.93
  5574.9  163.87  5589.3  166.35  5658.2  164.74  5783.3  164.58  6068.6  165.45
  6308.2  165.95  6464.6  166.10  6627.0  164.27  6645.1  166.61  6899.1  167.02
  6997.6  167.26  7219.2  167.15  7489.4  166.96  7763.7  174.75  7879.2  179.42
  7994.6  183.39  8110.1  187.21  8278.7  186.00  8695.3  192.74  8977.2  191.10
#Mann=20,-1,0
  4243.2    0.04       0  4615.2    0.04       0  4625.6    0.04       0
  4971.0    0.04       0  5101.0    0.05       0  5260.5    0.04       0
  5658.2   0.013       0  5783.3    0.05       0  6068.6    0.04       0
  6308.2    0.12       0  6464.6    0.12       0  6645.1    0.05       0
  6899.1    0.05       0  6997.6    0.12       0  7219.2    0.05       0
  7763.7    0.05       0  7879.2    0.12       0  7994.6    0.05       0
  8110.1    0.05       0  8278.7    0.04       0
Bank Sta=4615.2,4625.6
Exp/Cntr=0.3,0.1

Type RM Length L Ch R = 1,13056,583,583,583
BEGIN DESCRIPTION:
LGII4459
END DESCRIPTION:
XS GIS Cut Line= 5
      2526926.48     13579388.74      2526304.18     13578381.20
      2525158.35     13578035.48      2523913.75     13577956.45
      2523173.56     13578410.43
#Sta/Elev= 30
  4007.8  189.86  4098.3  188.39  4180.0  179.49  4266.2  172.12  4476.7  164.60
  4571.2  163.02  4613.8  166.18  4665.8  163.80  4964.2  160.96  4986.8  159.02
  4987.3  158.52  4997.4  159.02  5001.0  159.72  5180.0  163.40  5366.6  163.73
  5666.8  164.11  5949.1  163.89  6102.1  164.36  6203.9  164.66  6456.2  164.94
  6702.2  165.77  6870.2  165.79  6989.4  165.07  7307.5  168.17  7655.0  166.24
  7910.4  166.54  8111.3  171.51  8282.7  177.32  8400.1  182.47  8504.3  186.41
#Mann=20,-1,0
  4007.8   0.013       0  4180.0    0.04       0  4986.8    0.04       0
  4997.4    0.04       0  5001.0   0.013       0  5180.0    0.04       0
  5366.6    0.05       0  5666.8    0.12       0  5949.1    0.04       0
  6102.1   0.013       0  6203.9    0.05       0  6456.2    0.04       0
  6702.2    0.12       0  6870.2    0.12       0  6989.4    0.05       0
  7307.5    0.12       0  7655.0    0.05       0  8111.3    0.12       0
  8282.7    0.12       0  8400.1    0.05       0
Bank Sta=4986.8,4997.4
Exp/Cntr=0.3,0.1

Type RM Length L Ch R = 1,12473,780,780,780
BEGIN DESCRIPTION:
LGII4460
END DESCRIPTION:
XS GIS Cut Line= 5
      2527272.20     13579359.09      2527035.13     13578381.20
      2526620.27     13577956.45      2523893.99     13577867.55
      2523095.03     13578360.74
#Sta/Elev= 30
  3735.1  184.68  3828.1  176.17  3953.5  169.57  4131.0  164.06  4230.6  163.90
  4837.7  161.68  4995.1  157.66  4995.6  157.16  5005.7  157.66  5435.9  161.08
  5534.2  161.13  5632.5  161.37  6088.0  162.92  6222.4  163.52  6517.4  164.27
  6615.7  165.06  6714.0  164.49  6908.4  165.13  7107.3  165.33  7217.4  164.91
  7351.4  165.73  7391.4  163.24  7441.4  166.42  7557.7  165.80  7762.0  167.34
  7931.7  166.59  8330.0  165.80  8569.9  170.75  8919.3  184.43  9001.7  186.21
#Mann=20,-1,0
  3735.1    0.04       0  4230.6    0.04       0  4995.1    0.04       0
  5005.7    0.04       0  5435.9   0.013       0  5534.2    0.04       0
  5632.5    0.05       0  6088.0    0.12       0  6222.4    0.05       0
  6517.4    0.04       0  6615.7   0.013       0  6714.0    0.05       0
  6908.4    0.04       0  7107.3    0.05       0  7217.4    0.12       0
  7557.7    0.05       0  7762.0    0.12       0  7931.7    0.05       0
  8569.9    0.12       0  8919.3   0.013       0
Bank Sta=4995.1,5005.7
Exp/Cntr=0.3,0.1

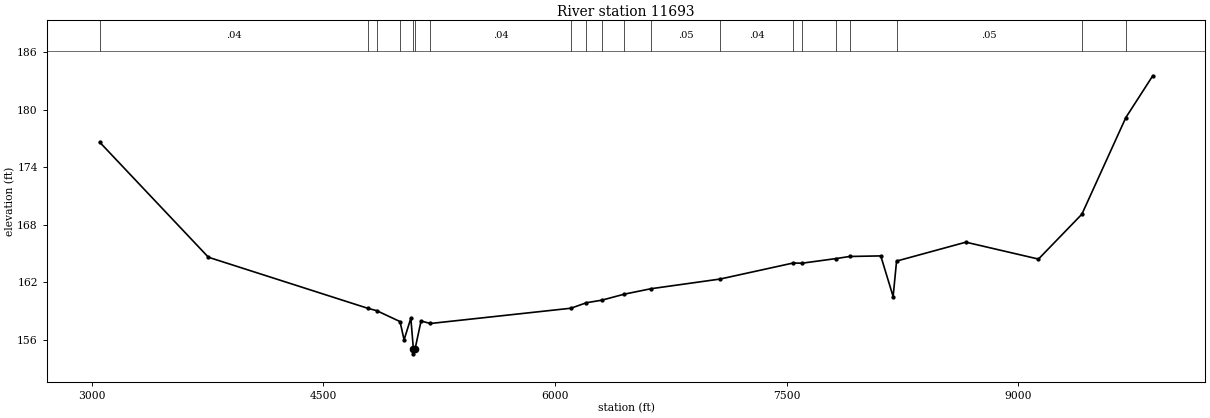
Type RM Length L Ch R = 1,11693,0,0,0
BEGIN DESCRIPTION:
LGII4461
END DESCRIPTION:
XS GIS Cut Line= 5
      2528427.92     13579714.72      2527400.61     13577818.17
      2525276.88     13577334.15      2523844.60     13577739.14
      2523024.75     13578302.17
#Sta/Elev= 30
  3051.3  176.61  3755.6  164.62  4787.9  159.30  4844.6  159.06  4996.1  157.92
  5022.4  156.02  5066.1  158.27  5082.6  155.06  5083.1  154.56  5093.3  155.06
  5132.2  157.98  5192.5  157.72  6102.3  159.31  6202.5  159.88  6302.8  160.15
  6446.8  160.77  6619.9  161.34  7068.3  162.35  7541.5  164.02  7598.6  164.00
  7818.0  164.48  7906.5  164.70  8108.4  164.76  8188.5  160.53  8210.8  164.22
  8659.4  166.19  9129.4  164.43  9410.4  169.10  9695.2  179.17  9869.4  183.52
#Mann=20,-1,0
  3051.3    0.04       0  4787.9   0.013       0  4844.6    0.04       0
  4996.1   0.013       0  5082.6    0.03       0  5093.3   0.013       0
  5192.5    0.04       0  6102.3   0.013       0  6202.5    0.04       0
  6302.8    0.12       0  6446.8    0.12       0  6619.9    0.05       0
  7068.3    0.04       0  7541.5   0.013       0  7598.6    0.04       0
  7818.0    0.05       0  7906.5    0.12       0  8210.8    0.05       0
  9410.4    0.12       0  9695.2   0.013       0
Bank Sta=5082.6,5093.3
Exp/Cntr=0.3,0.1

Chan Stop Cuts=-1