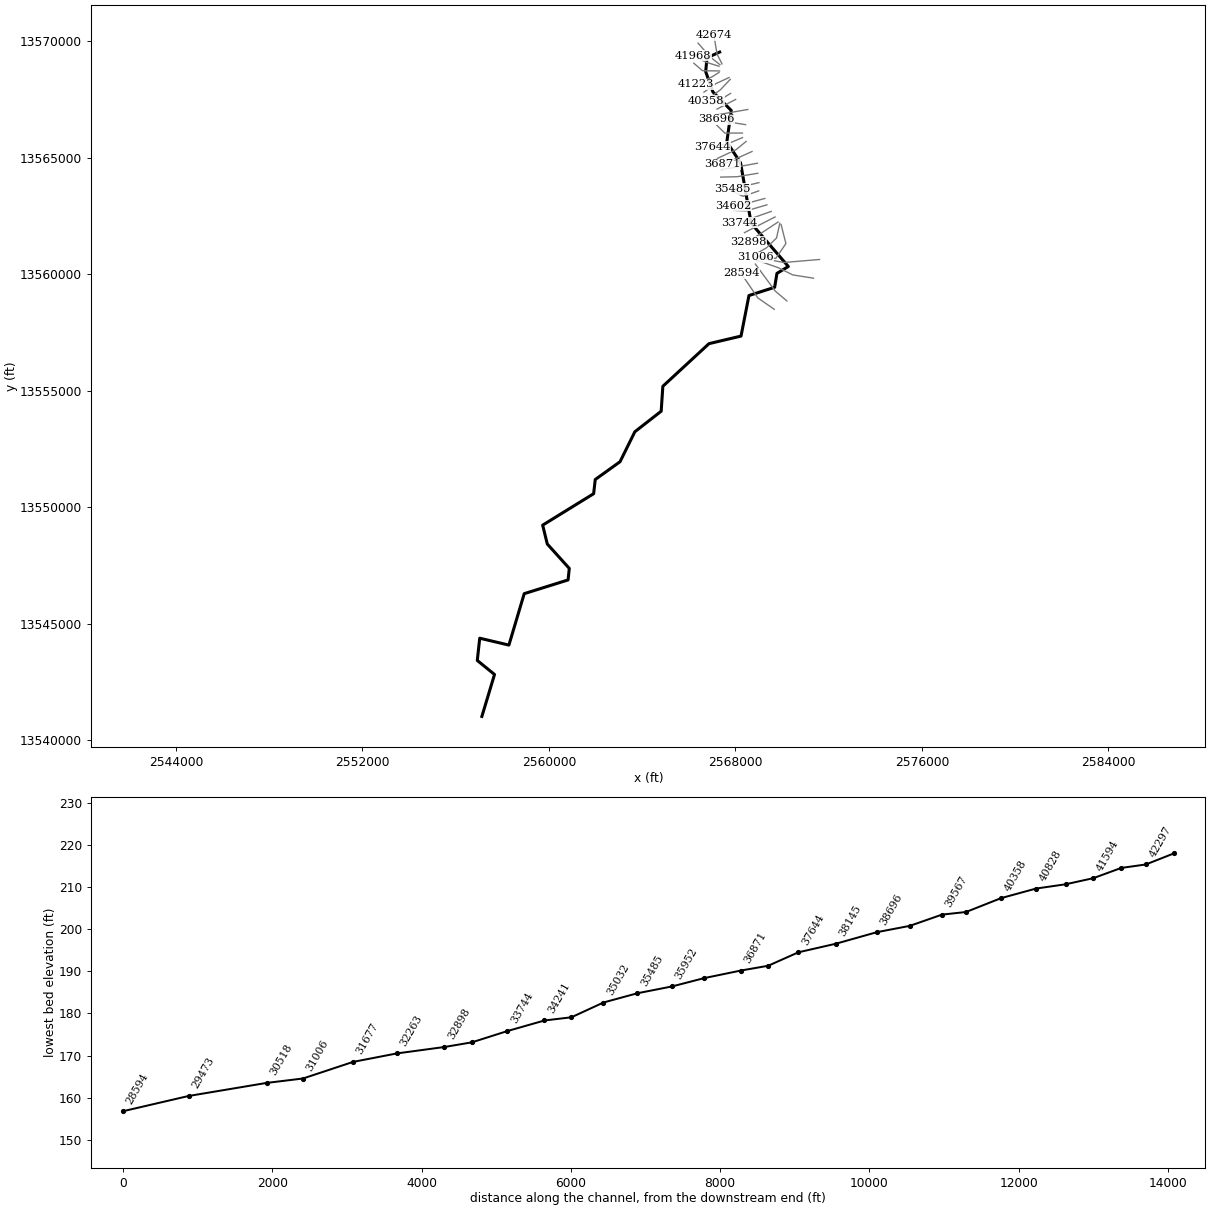
--- PRICE CREEK.prj (project) ---

Proj Title=PRICE CREEK Base Level Engineering
Current Plan=p01
Default Exp/Contr=0.3,0.1
English Units
Geom File=g01
Flow File=f01
Plan File=p01
Y Axis Title=Elevation
X Axis Title(PF)=Main Channel Distance
X Axis Title(XS)=Station
BEGIN DESCRIPTION:
PRICE CREEK
END DESCRIPTION:
DSS Export Rating Curves= 0
DSS Export Rating Curve Sorted= 0
DSS Export Volume Flow Curves= 0
DXF OffsetX= 0
DXF OffsetY= 0
DXF ScaleX= 1
DXF ScaleY= 10

--- PRICE CREEK.p01 (plan) ---

Plan Title=Multiple Run
Short Identifier=Multiple
Geom File=g01
Flow File=f01
Subcritical Flow
K Sum by GR= 0
Std Step Tol= 0.01
Critical Tol= 0.01
Num of Std Step Trials= 20
Max Error Tol= 0.3
Flow Tol Ratio= 0.001
Split Flow NTrial= 30
Split Flow Tol= 0.02
Split Flow Ratio= 0.02
Log Output Level= 0
Friction Slope Method= 1
Unsteady Friction Slope Method= 2
Unsteady Bridges Friction Slope Method= 1
Parabolic Critical Depth
Global Vel Dist=  1 , 1 , 1
Global Log Level= 0
CheckData=True
Encroach Param= -1, 0, 0, 0
BEGIN DESCRIPTION:
Multiple Run
END DESCRIPTION:

--- PRICE CREEK.f01 (steady flow) ---

Flow Title=Multiple
Number of Profiles=7
Profile Names=10-year,25-year,50-year,1pct_min,100-year,1pct_plu,500-year
River Rch & RM= PRICE CREEK,Reach-1,42674
     502     786    1035     661    1319    2632    2119
River Rch & RM= PRICE CREEK,Reach-1,38696
     746    1194    1597    1034    2063    4116    3405
River Rch & RM= PRICE CREEK,Reach-1,34602
     816    1312    1760    1142    2278    4546    3778
River Rch & RM= PRICE CREEK,Reach-1,31006
    1487    2471    3385    2241    4471    8920    7719
River Rch & RM= PRICE CREEK,Reach-1,29473
    1851    3103    4278    2846    5679   11331    9912
River Rch & RM= PRICE CREEK,Reach-1,26190
    1961    3293    4545    3026    6038   12048   10557
River Rch & RM= PRICE CREEK,Reach-1,23867
    2040    3431    4740    3159    6304   12577   11041
River Rch & RM= PRICE CREEK,Reach-1,23194
    2132    3589    4961    3308    6600   13169   11568
River Rch & RM= PRICE CREEK,Reach-1,20883
    3253    5580    7812    5270   10515   20980   18869
River Rch & RM= PRICE CREEK,Reach-1,17700
    3719    6405    8990    6074   12119   24180   21788
River Rch & RM= PRICE CREEK,Reach-1,16390
    4239    7328   10310    6979   13925   27785   25134
River Rch & RM= PRICE CREEK,Reach-1,12879
    4338    7496   10544    7134   14235   28402   25670
River Rch & RM= PRICE CREEK,Reach-1,10624
    4481    7753   10917    7394   14753   29435   26655
River Rch & RM= PRICE CREEK,Reach-1,9486
    4526    7831   11024    7465   14895   29719   26903
River Rch & RM= PRICE CREEK,Reach-1,8394
    4818    8369   11810    8014   15990   31905   29012
River Rch & RM= PRICE CREEK,Reach-1,3098
    5340    9293   13135    8927   17812   35539   32403
Boundary for River Rch & Prof#=PRICE CREEK,Reach-1,1
Up Type=0
Dn Type=3
Dn Slope=0.005
Boundary for River Rch & Prof#=PRICE CREEK,Reach-1,2
Up Type=0
Dn Type=3
Dn Slope=0.005
Boundary for River Rch & Prof#=PRICE CREEK,Reach-1,3
Up Type=0
Dn Type=3
Dn Slope=0.005
Boundary for River Rch & Prof#=PRICE CREEK,Reach-1,4
Up Type=0
Dn Type=3
Dn Slope=0.005
Boundary for River Rch & Prof#=PRICE CREEK,Reach-1,5
Up Type=0
Dn Type=3
Dn Slope=0.005
Boundary for River Rch & Prof#=PRICE CREEK,Reach-1,6
Up Type=0
Dn Type=3
Dn Slope=0.005
Boundary for River Rch & Prof#=PRICE CREEK,Reach-1,7
Up Type=0
Dn Type=3
Dn Slope=0.005

--- PRICE CREEK.g01 (geometry) ---

Geom Title=Existing Conditions

River Reach=PRICE CREEK,Reach-1
Reach XY= 30
      2567325.00     13569525.00      2566782.86     13569281.17
      2566726.22     13568685.50      2567036.10     13567814.68
      2567822.76     13567019.07      2567633.08     13565671.70
      2568222.94     13564769.54      2568676.96     13562180.89
      2570271.47     13560326.45      2569783.02     13560031.34
      2569684.79     13559435.50      2568582.86     13559081.17
      2568242.06     13557341.08      2566868.79     13557017.20
      2564888.61     13555188.24      2564817.17     13554118.81
      2563688.63     13553238.27      2563052.00     13551951.49
      2561988.62     13551188.22      2561919.97     13550580.08
      2559732.80     13549231.21      2559930.52     13548422.57
      2560875.00     13547375.00      2560822.94     13546880.85
      2558941.64     13546291.68      2558285.05     13544086.11
      2557032.85     13544381.19      2556928.54     13543426.47
      2557667.47     13542825.01      2557125.00     13541025.00

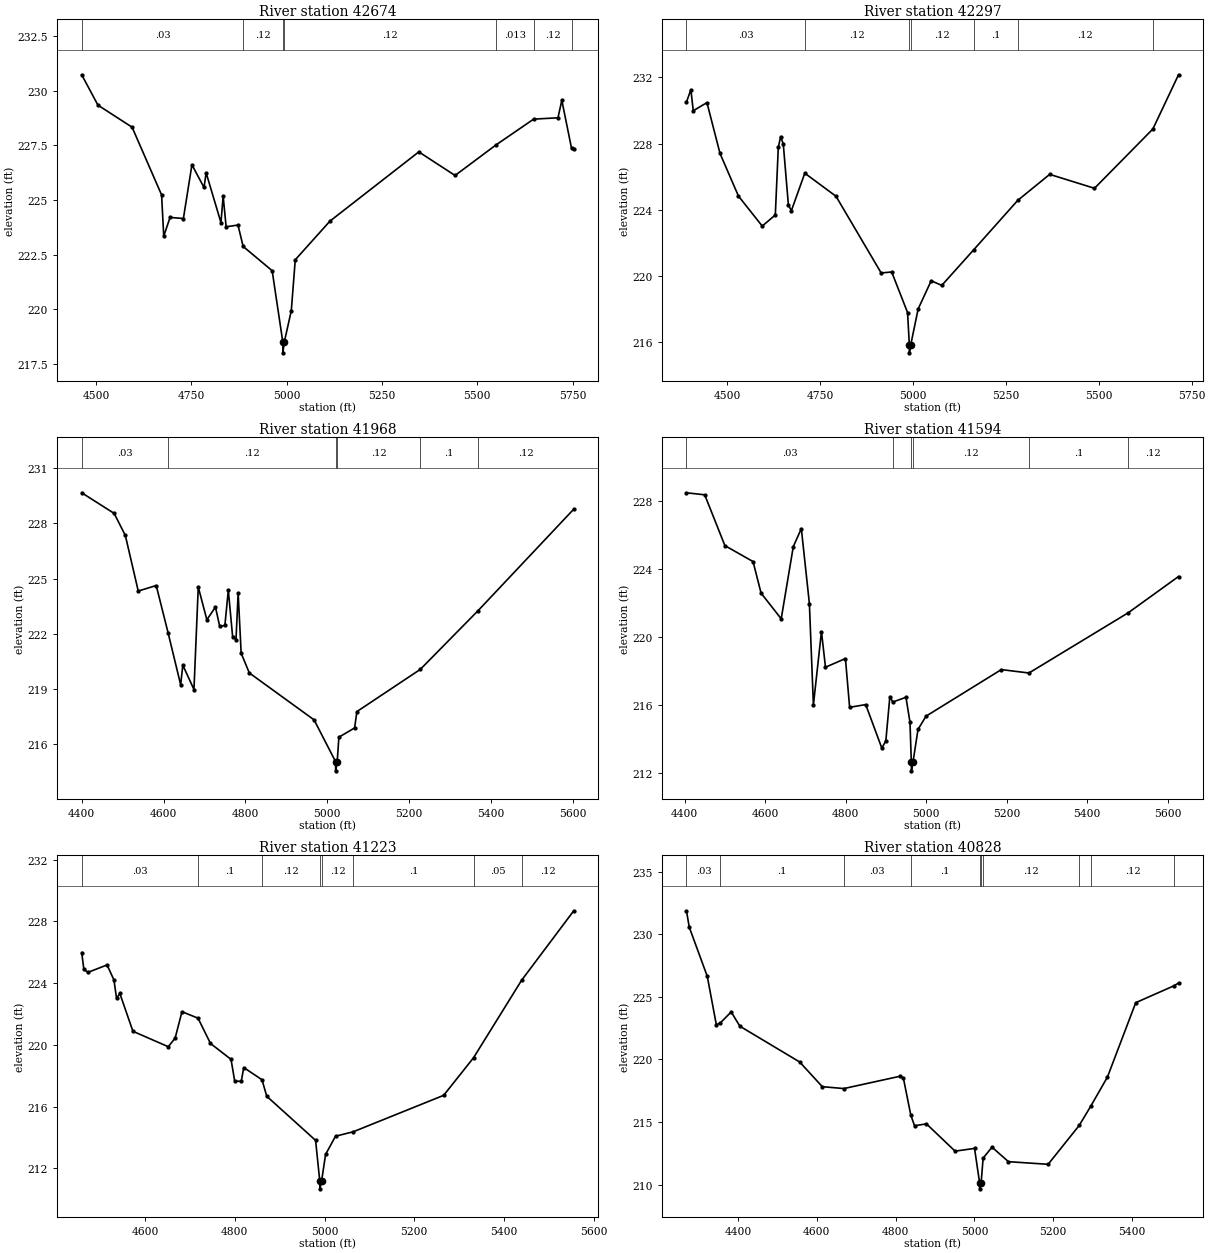
Type RM Length L Ch R = 1,42674,377,377,377
BEGIN DESCRIPTION:
LGII3008
END DESCRIPTION:
XS GIS Cut Line= 3
      2567426.79     13569017.07      2567214.12     13569436.52
      2567078.24     13570245.91
#Sta/Elev= 30
  4462.3  230.73  4504.9  229.34  4594.5  228.33  4671.9  225.23  4677.5  223.34
  4694.1  224.20  4729.1  224.15  4751.5  226.61  4783.2  225.57  4788.8  226.24
  4827.7  223.96  4833.4  225.18  4841.2  223.77  4872.3  223.85  4885.9  222.87
  4962.0  221.76  4989.9  218.50  4990.1  218.00  4993.9  218.50  5012.2  219.93
  5022.6  222.26  5113.6  224.03  5346.8  227.20  5441.9  226.12  5548.6  227.51
  5648.1  228.70  5711.8  228.76  5722.0  229.56  5747.5  227.36  5753.3  227.35
#Mann=7,-1,0
  4462.3    0.03       0  4885.9    0.12       0  4989.9    0.05       0
  4993.9    0.12       0  5548.6   0.013       0  5648.1    0.12       0
  5747.5    0.04       0
Bank Sta=4989.9,4993.9
Exp/Cntr=0.3,0.1

Type RM Length L Ch R = 1,42297,329,329,329
BEGIN DESCRIPTION:
LGII3007
END DESCRIPTION:
XS GIS Cut Line= 3
      2567338.15     13568981.65      2566918.74     13569318.37
      2566399.45     13569908.46
#Sta/Elev= 30
  4390.8  230.50  4402.7  231.25  4409.1  229.98  4445.9  230.47  4481.1  227.40
  4530.7  224.83  4594.7  223.02  4629.9  223.69  4637.9  227.77  4644.3  228.42
  4651.3  227.97  4665.1  224.28  4673.1  223.95  4709.2  226.21  4793.1  224.82
  4914.7  220.19  4943.0  220.25  4985.7  217.80  4990.4  215.87  4990.6  215.37
  4994.4  215.87  5014.2  218.02  5049.3  219.72  5077.7  219.44  5163.3  221.58
  5282.1  224.57  5368.1  226.14  5488.6  225.30  5645.8  228.88  5714.7  232.15
#Mann=7,-1,0
  4390.8    0.03       0  4709.2    0.12       0  4990.4    0.05       0
  4994.4    0.12       0  5163.3     0.1       0  5282.1    0.12       0
  5645.8    0.05       0
Bank Sta=4990.4,4994.4
Exp/Cntr=0.3,0.1

Type RM Length L Ch R = 1,41968,374,374,374
BEGIN DESCRIPTION:
LGII3006
END DESCRIPTION:
XS GIS Cut Line= 3
      2567296.79     13568916.66      2566729.69     13569093.88
      2566192.13     13569377.43
#Sta/Elev= 30
  4400.2  229.66  4479.5  228.54  4506.8  227.34  4538.3  224.32  4582.2  224.62
  4611.1  222.06  4641.9  219.23  4647.2  220.29  4674.4  218.97  4684.9  224.54
  4705.9  222.76  4726.9  223.45  4737.3  222.40  4749.9  222.45  4758.3  224.37
  4768.8  221.85  4777.1  221.68  4782.3  224.21  4789.7  220.94  4809.6  219.87
  4967.8  217.32  5020.3  215.05  5020.5  214.55  5024.3  215.05  5028.4  216.38
  5066.8  216.88  5072.4  217.77  5227.1  220.06  5368.2  223.25  5602.1  228.77
#Mann=6,-1,0
  4400.2    0.03       0  4611.1    0.12       0  5020.3    0.05       0
  5024.3    0.12       0  5227.1     0.1       0  5368.2    0.12       0
Bank Sta=5020.3,5024.3
Exp/Cntr=0.3,0.1

Type RM Length L Ch R = 1,41594,371,371,371
BEGIN DESCRIPTION:
LGII3005
END DESCRIPTION:
XS GIS Cut Line= 4
      2567320.45     13568715.79      2566759.23     13568721.70
      2566587.91     13568727.61      2566215.70     13569046.65
#Sta/Elev= 30
  4404.1  228.49  4449.5  228.37  4499.6  225.38  4569.6  224.44  4589.6  222.58
  4639.6  221.07  4669.6  225.32  4689.6  226.38  4709.6  221.97  4719.6  216.00
  4739.6  220.32  4749.6  218.22  4799.2  218.73  4809.6  215.86  4849.6  216.02
  4889.6  213.46  4899.6  213.88  4909.6  216.49  4916.9  216.17  4949.6  216.45
  4959.6  214.99  4963.0  212.62  4963.2  212.12  4967.0  212.62  4979.6  214.56
  4999.6  215.34  5186.6  218.08  5255.3  217.88  5501.7  221.42  5627.0  223.56
#Mann=6,-1,0
  4404.1    0.03       0  4916.9    0.12       0  4963.0    0.05       0
  4967.0    0.12       0  5255.3     0.1       0  5501.7    0.12       0
Bank Sta=4963,4967
Exp/Cntr=0.3,0.1

Type RM Length L Ch R = 1,41223,395,395,395
BEGIN DESCRIPTION:
LGII3004
END DESCRIPTION:
XS GIS Cut Line= 3
      2567296.84     13568650.82      2567007.35     13568467.67
      2566323.48     13568149.32
#Sta/Elev= 30
  4458.6  225.98  4463.4  224.89  4472.6  224.70  4515.1  225.18  4530.4  224.21
  4536.3  223.02  4543.6  223.33  4572.8  220.88  4651.6  219.88  4666.9  220.44
  4682.1  222.15  4717.9  221.73  4745.7  220.09  4791.5  219.06  4799.6  217.66
  4814.3  217.63  4819.8  218.53  4860.5  217.74  4871.1  216.67  4980.0  213.81
  4989.3  211.17  4989.5  210.67  4993.3  211.17  5002.3  212.90  5024.4  214.08
  5064.1  214.37  5265.5  216.73  5332.2  219.17  5439.3  224.19  5555.5  228.69
#Mann=8,-1,0
  4458.6    0.03       0  4717.9     0.1       0  4860.5    0.12       0
  4989.3    0.05       0  4993.3    0.12       0  5064.1     0.1       0
  5332.2    0.05       0  5439.3    0.12       0
Bank Sta=4989.3,4993.3
Exp/Cntr=0.3,0.1

Type RM Length L Ch R = 1,40828,470,470,470
BEGIN DESCRIPTION:
LGII3003
END DESCRIPTION:
XS GIS Cut Line= 3
      2567728.09     13568432.23      2567166.86     13568172.29
      2566652.92     13567806.04
#Sta/Elev= 30
  4268.8  231.87  4275.9  230.56  4321.7  226.63  4344.7  222.76  4355.0  222.92
  4382.4  223.79  4404.5  222.65  4556.4  219.79  4613.8  217.82  4668.6  217.67
  4812.2  218.66  4819.6  218.52  4838.6  215.54  4848.0  214.70  4878.3  214.85
  4951.0  212.67  5000.4  212.89  5013.2  210.16  5013.4  209.66  5017.2  210.16
  5022.2  212.11  5044.7  212.99  5086.5  211.83  5187.3  211.62  5266.1  214.72
  5295.5  216.26  5337.8  218.58  5409.8  224.53  5507.7  225.89  5518.4  226.10
#Mann=10,-1,0
  4268.8    0.03       0  4355.0     0.1       0  4668.6    0.03       0
  4838.6     0.1       0  5013.2    0.05       0  5017.2     0.1       0
  5022.2    0.12       0  5266.1     0.1       0  5295.5    0.12       0
  5507.7    0.05       0
Bank Sta=5013.2,5017.2
Exp/Cntr=0.3,0.1

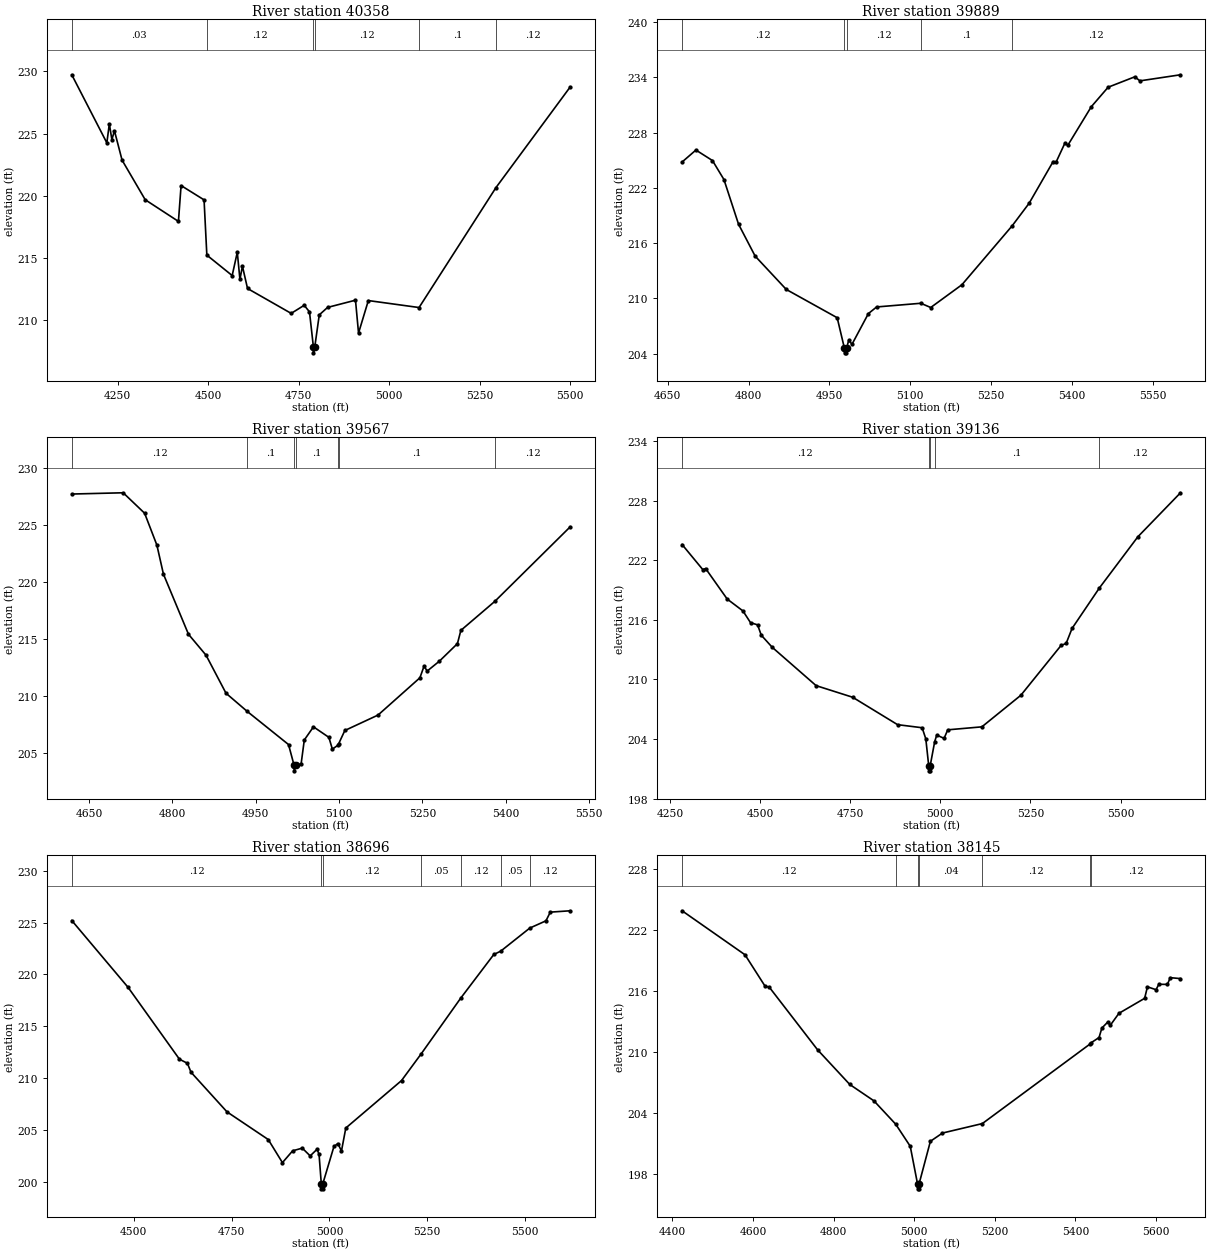
Type RM Length L Ch R = 1,40358,469,469,469
BEGIN DESCRIPTION:
LGII3002
END DESCRIPTION:
XS GIS Cut Line= 4
      2567781.26     13568355.44      2567355.90     13567906.45
      2567030.98     13567664.24      2566753.34     13567445.67
#Sta/Elev= 30
  4122.9  229.72  4219.8  224.25  4226.7  225.78  4233.7  224.51  4240.8  225.22
  4261.9  222.86  4325.8  219.68  4417.6  217.94  4424.9  220.82  4488.4  219.67
  4496.1  215.23  4566.1  213.59  4580.2  215.46  4587.5  213.28  4594.4  214.34
  4608.5  212.55  4729.1  210.55  4765.1  211.20  4779.7  210.67  4790.4  207.88
  4790.6  207.38  4794.4  207.88  4806.7  210.43  4829.7  211.03  4906.8  211.61
  4915.2  208.97  4942.3  211.58  5082.4  211.02  5295.0  220.66  5500.0  228.74
#Mann=6,-1,0
  4122.9    0.03       0  4496.1    0.12       0  4790.4    0.05       0
  4794.4    0.12       0  5082.4     0.1       0  5295.0    0.12       0
Bank Sta=4790.4,4794.4
Exp/Cntr=0.3,0.1

Type RM Length L Ch R = 1,39889,322,322,322
BEGIN DESCRIPTION:
LGII3001
END DESCRIPTION:
XS GIS Cut Line= 3
      2567793.02     13567752.83      2567279.10     13567433.84
      2567001.43     13567274.33
#Sta/Elev= 30
  4676.7  224.80  4702.4  226.10  4733.1  224.96  4754.4  222.90  4781.5  218.05
  4812.3  214.59  4870.1  210.97  4964.6  207.90  4978.0  204.59  4978.2  204.09
  4981.7  204.09  4982.0  204.59  4985.9  205.44  4992.2  205.03  5022.5  208.35
  5037.8  209.07  5119.8  209.47  5138.2  209.01  5196.1  211.48  5289.4  217.88
  5320.9  220.33  5365.4  224.85  5371.2  224.83  5387.0  226.82  5392.8  226.63
  5436.2  230.80  5467.5  232.92  5517.0  234.05  5526.5  233.61  5601.8  234.27
#Mann=5,-1,0
  4676.7    0.12       0  4978.0    0.05       0  4982.0    0.12       0
  5119.8     0.1       0  5289.4    0.12       0
Bank Sta=4978,4982
Exp/Cntr=0.3,0.1

Type RM Length L Ch R = 1,39567,431,431,431
BEGIN DESCRIPTION:
LGII3000
END DESCRIPTION:
XS GIS Cut Line= 2
      2568011.61     13567492.90      2567214.67     13567079.67
#Sta/Elev= 30
  4618.6  227.69  4711.2  227.80  4749.8  226.01  4771.9  223.22  4783.7  220.68
  4828.8  215.42  4860.4  213.59  4896.4  210.26  4934.6  208.67  5009.0  205.77
  5018.9  203.97  5019.2  203.47  5022.9  203.97  5031.6  204.05  5037.4  206.17
  5053.9  207.32  5081.7  206.40  5087.9  205.37  5097.4  205.69  5099.1  205.82
  5110.4  207.00  5170.2  208.35  5245.6  211.61  5253.1  212.63  5258.7  212.20
  5280.8  213.07  5313.2  214.60  5319.4  215.76  5380.6  218.30  5516.3  224.82
#Mann=7,-1,0
  4618.6    0.12       0  4934.6     0.1       0  5018.9    0.05       0
  5022.9     0.1       0  5097.4    0.12       0  5099.1     0.1       0
  5380.6    0.12       0
Bank Sta=5018.9,5022.9
Exp/Cntr=0.3,0.1

Type RM Length L Ch R = 1,39136,440,440,440
BEGIN DESCRIPTION:
LGII2999
END DESCRIPTION:
XS GIS Cut Line= 2
      2568531.56     13567061.67      2567168.44     13566825.63
#Sta/Elev= 30
  4283.1  223.59  4340.5  221.07  4348.5  221.17  4408.3  218.10  4452.1  216.90
  4473.1  215.72  4492.7  215.50  4502.9  214.46  4533.3  213.24  4655.1  209.38
  4756.6  208.21  4881.2  205.45  4949.4  205.14  4959.6  204.02  4967.7  201.30
  4968.0  200.80  4971.5  200.80  4971.7  201.30  4984.3  203.75  4990.0  204.40
  5010.3  204.07  5020.5  204.93  5115.2  205.23  5223.4  208.41  5335.1  213.43
  5349.1  213.63  5365.5  215.14  5441.3  219.21  5548.2  224.37  5666.5  228.80
#Mann=5,-1,0
  4283.1    0.12       0  4967.7    0.05       0  4971.7    0.12       0
  4984.3     0.1       0  5441.3    0.12       0
Bank Sta=4967.7,4971.7
Exp/Cntr=0.3,0.1

Type RM Length L Ch R = 1,38696,551,551,551
BEGIN DESCRIPTION:
LGII2998
END DESCRIPTION:
XS GIS Cut Line= 3
      2568436.96     13566411.83      2567651.28     13566535.89
      2567184.55     13566642.23
#Sta/Elev= 30
  4341.4  225.21  4485.1  218.77  4616.7  211.82  4637.0  211.43  4646.1  210.57
  4738.2  206.74  4843.6  204.07  4879.9  201.84  4906.0  202.98  4930.6  203.24
  4950.8  202.49  4968.4  203.13  4973.5  202.65  4979.2  199.81  4979.4  199.31
  4982.9  199.31  4983.2  199.81  5011.6  203.40  5021.7  203.68  5030.8  202.96
  5041.9  205.18  5184.3  209.76  5234.2  212.32  5335.7  217.72  5420.2  221.93
  5437.8  222.25  5512.2  224.48  5553.5  225.18  5564.7  226.02  5615.5  226.15
#Mann=7,-1,0
  4341.4    0.12       0  4979.2    0.05       0  4983.2    0.12       0
  5234.2    0.05       0  5335.7    0.12       0  5437.8    0.05       0
  5512.2    0.12       0
Bank Sta=4979.2,4983.2
Exp/Cntr=0.3,0.1

Type RM Length L Ch R = 1,38145,501,501,501
BEGIN DESCRIPTION:
LGII2997
END DESCRIPTION:
XS GIS Cut Line= 3
      2568301.11     13566051.46      2567544.94     13566051.46
      2567202.28     13566388.22
#Sta/Elev= 30
  4424.1  223.87  4580.2  219.55  4630.2  216.45  4640.2  216.38  4760.2  210.22
  4840.2  206.81  4900.2  205.20  4954.1  202.91  4990.2  200.74  5008.2  197.06
  5008.5  196.56  5012.0  196.56  5012.2  197.06  5040.2  201.23  5070.2  202.04
  5169.1  202.97  5435.8  210.77  5437.9  210.88  5458.6  211.42  5465.6  212.35
  5479.7  212.92  5486.8  212.64  5508.0  213.80  5571.7  215.27  5578.7  216.40
  5600.0  216.12  5607.0  216.65  5628.3  216.64  5635.3  217.30  5660.7  217.21
#Mann=7,-1,0
  4424.1    0.12       0  4954.1    0.04       0  5008.2    0.04       0
  5012.2    0.04       0  5169.1    0.12       0  5435.8    0.05       0
  5437.9    0.12       0
Bank Sta=5008.2,5012.2
Exp/Cntr=0.3,0.1

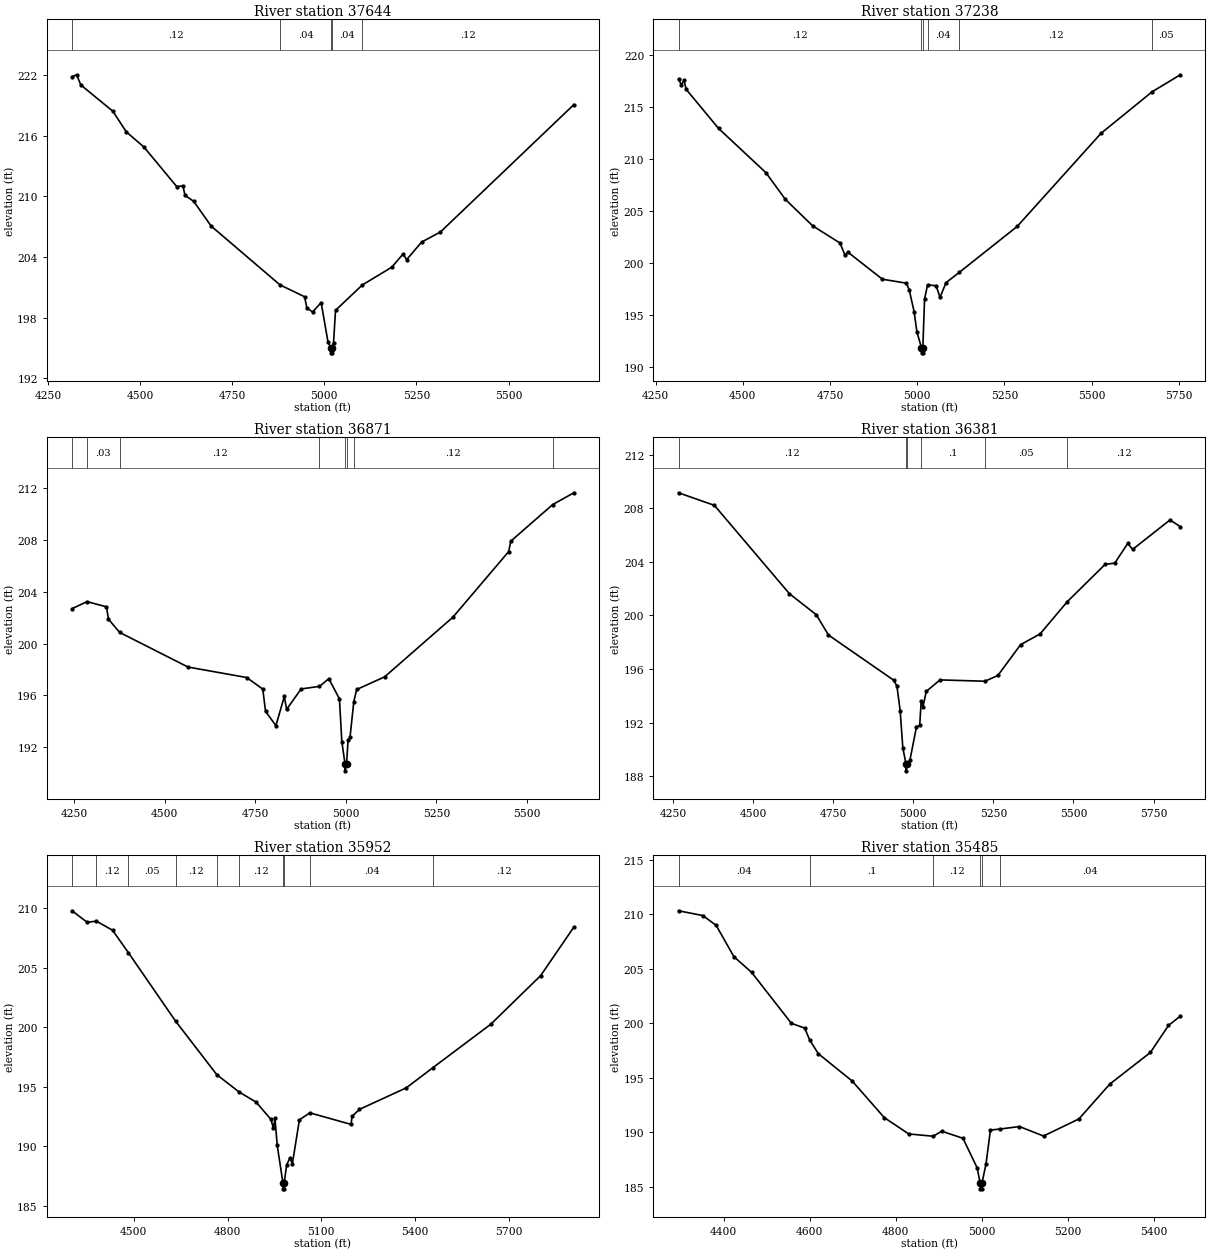
Type RM Length L Ch R = 1,37644,406,406,406
BEGIN DESCRIPTION:
LGII2996
END DESCRIPTION:
XS GIS Cut Line= 3
      2568307.04     13565856.52      2567686.73     13565596.58
      2567008.72     13565472.77
#Sta/Elev= 30
  4315.5  221.83  4327.8  222.01  4339.4  221.00  4426.1  218.41  4462.9  216.36
  4510.5  214.87  4599.6  210.96  4616.4  211.03  4621.9  210.10  4645.6  209.50
  4693.2  207.05  4879.6  201.25  4946.6  200.07  4952.7  198.96  4968.3  198.57
  4991.5  199.50  5010.2  195.57  5018.0  195.03  5018.2  194.53  5021.7  194.53
  5022.0  195.03  5025.1  195.52  5030.5  198.73  5102.9  201.23  5183.0  202.99
  5213.5  204.28  5223.6  203.75  5264.3  205.48  5315.1  206.47  5677.3  219.06
#Mann=5,-1,0
  4315.5    0.12       0  4879.6    0.04       0  5018.0    0.04       0
  5022.0    0.04       0  5102.9    0.12       0
Bank Sta=5018,5022
Exp/Cntr=0.3,0.1

Type RM Length L Ch R = 1,37238,367,367,367
BEGIN DESCRIPTION:
LGII2995
END DESCRIPTION:
XS GIS Cut Line= 3
      2568460.64     13565691.11      2568035.27     13565342.55
      2567231.83     13564964.46
#Sta/Elev= 30
  4316.0  217.65  4323.8  217.12  4331.6  217.52  4338.1  216.66  4430.7  212.91
  4566.3  208.66  4622.3  206.08  4700.5  203.54  4778.8  201.89  4793.1  200.70
  4801.0  201.02  4900.2  198.41  4968.6  198.03  4976.8  197.42  4991.3  195.25
  4998.9  193.36  5012.1  191.83  5012.4  191.33  5015.9  191.33  5016.1  191.83
  5021.0  196.51  5029.6  197.87  5054.1  197.78  5065.3  196.67  5082.5  198.08
  5120.2  199.06  5286.2  203.48  5526.7  212.44  5673.3  216.44  5753.9  218.07
#Mann=6,-1,0
  4316.0    0.12       0  5012.1    0.05       0  5016.1    0.12       0
  5029.6    0.04       0  5120.2    0.12       0  5673.3    0.05       0
Bank Sta=5012.1,5016.1
Exp/Cntr=0.3,0.1

Type RM Length L Ch R = 1,36871,490,490,490
BEGIN DESCRIPTION:
LGII2994
END DESCRIPTION:
XS GIS Cut Line= 3
      2568714.63     13565259.84      2568123.89     13564994.00
      2567444.50     13564710.43
#Sta/Elev= 30
  4244.9  202.69  4286.2  203.23  4339.8  202.83  4345.3  201.88  4376.0  200.86
  4564.6  198.19  4726.7  197.38  4770.9  196.49  4778.5  194.78  4807.1  193.67
  4830.3  195.92  4836.7  194.93  4876.6  196.50  4927.3  196.70  4953.1  197.29
  4982.3  195.74  4989.0  192.43  4997.9  190.69  4998.1  190.19  5001.9  190.69
  5006.1  192.55  5011.5  192.77  5022.0  195.53  5029.9  196.46  5106.8  197.43
  5295.2  202.03  5448.9  207.08  5455.0  207.89  5570.4  210.71  5628.9  211.62
#Mann=8,-1,0
  4244.9    0.05       0  4286.2    0.03       0  4376.0    0.12       0
  4927.3     0.1       0  4997.9    0.05       0  5001.9     0.1       0
  5022.0    0.12       0  5570.4    0.05       0
Bank Sta=4997.9,5001.9
Exp/Cntr=0.3,0.1

Type RM Length L Ch R = 1,36381,429,429,429
BEGIN DESCRIPTION:
LGII2993
END DESCRIPTION:
XS GIS Cut Line= 3
      2568945.03     13564757.70      2568017.55     13564586.38
      2567403.17     13564485.95
#Sta/Elev= 30
  4267.8  209.16  4379.7  208.22  4613.6  201.63  4697.8  200.05  4735.6  198.54
  4939.0  195.17  4949.2  194.73  4959.3  192.90  4967.6  190.12  4977.7  188.90
  4977.9  188.40  4981.7  188.90  4989.8  189.20  5010.2  191.68  5020.3  191.79
  5025.0  193.63  5030.7  193.19  5040.7  194.33  5083.7  195.19  5224.0  195.09
  5264.2  195.52  5335.1  197.82  5395.9  198.62  5480.4  201.02  5598.6  203.81
  5629.0  203.91  5669.5  205.38  5684.6  204.93  5801.2  207.13  5833.5  206.63
#Mann=6,-1,0
  4267.8    0.12       0  4977.7    0.05       0  4981.7    0.12       0
  5025.0     0.1       0  5224.0    0.05       0  5480.4    0.12       0
Bank Sta=4977.7,4981.7
Exp/Cntr=0.3,0.1

Type RM Length L Ch R = 1,35952,467,467,467
BEGIN DESCRIPTION:
LGII2992
END DESCRIPTION:
XS GIS Cut Line= 3
      2568962.79     13564326.45      2568076.63     13564178.75
      2567368.83     13564161.06
#Sta/Elev= 30
  4302.3  209.77  4350.7  208.80  4380.0  208.90  4431.8  208.14  4482.7  206.25
  4634.1  200.49  4765.7  196.01  4837.5  194.55  4891.0  193.72  4938.7  192.27
  4946.8  191.53  4951.9  192.34  4959.0  190.09  4977.3  186.93  4977.5  186.43
  4981.0  186.43  4981.3  186.93  4989.4  188.45  4999.6  189.01  5007.6  188.53
  5030.0  192.22  5063.4  192.81  5195.2  191.84  5199.0  192.52  5222.3  193.10
  5372.4  194.91  5457.9  196.61  5642.4  200.24  5802.5  204.33  5908.7  208.40
#Mann=10,-1,0
  4302.3    0.05       0  4380.0    0.12       0  4482.7    0.05       0
  4634.1    0.12       0  4765.7    0.05       0  4837.5    0.12       0
  4977.3    0.05       0  4981.3    0.12       0  5063.4    0.04       0
  5457.9    0.12       0
Bank Sta=4977.3,4981.3
Exp/Cntr=0.3,0.1

Type RM Length L Ch R = 1,35485,453,453,453
BEGIN DESCRIPTION:
LGII2991
END DESCRIPTION:
XS GIS Cut Line= 2
      2569010.06     13563924.74      2567875.76     13563652.98
#Sta/Elev= 30
  4295.1  210.33  4351.7  209.89  4382.6  208.99  4423.7  206.12  4464.8  204.68
  4557.4  200.00  4588.2  199.56  4600.1  198.46  4620.0  197.21  4699.0  194.69
  4773.3  191.34  4830.2  189.84  4887.1  189.63  4907.0  190.09  4956.3  189.44
  4989.3  186.72  4996.3  185.30  4996.5  184.80  5000.0  184.80  5000.3  185.30
  5009.8  187.08  5020.1  190.20  5042.4  190.29  5087.5  190.52  5143.5  189.65
  5225.8  191.22  5297.6  194.42  5391.9  197.32  5434.0  199.80  5461.5  200.66
#Mann=6,-1,0
  4295.1    0.04       0  4600.1     0.1       0  4887.1    0.12       0
  4996.3    0.05       0  5000.3    0.12       0  5042.4    0.04       0
Bank Sta=4996.3,5000.3
Exp/Cntr=0.3,0.1

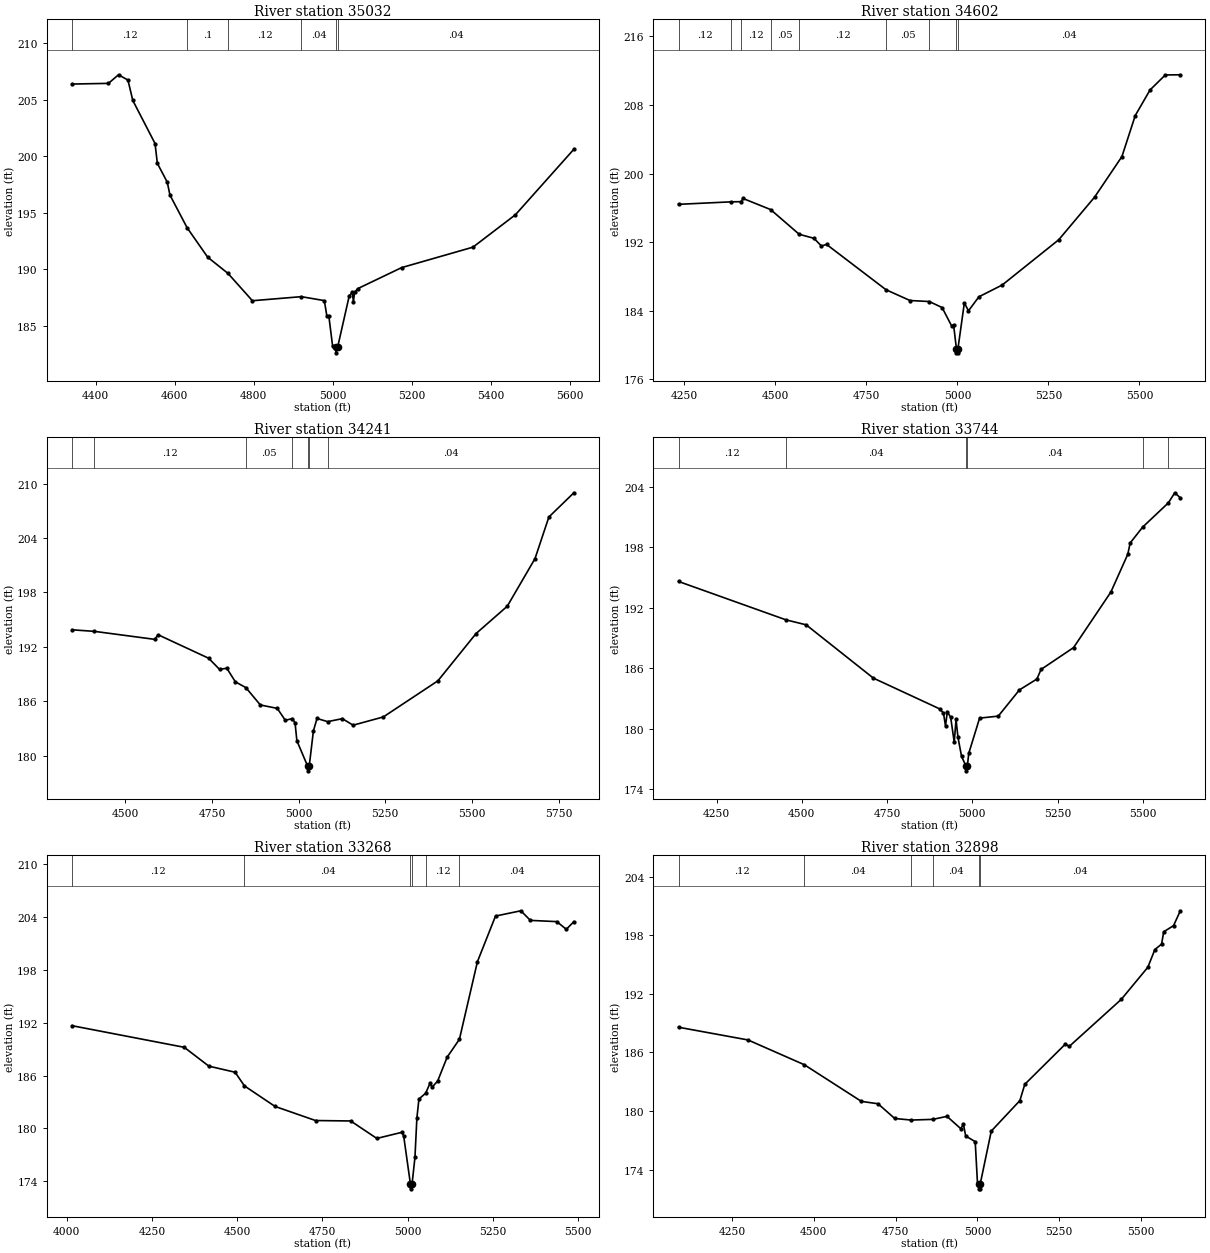
Type RM Length L Ch R = 1,35032,430,430,430
BEGIN DESCRIPTION:
LGII2990
END DESCRIPTION:
XS GIS Cut Line= 4
      2568998.23     13563570.28      2568566.96     13563416.67
      2568324.75     13563339.88      2567822.61     13563582.08
#Sta/Elev= 30
  4340.1  206.39  4432.0  206.45  4457.6  207.21  4481.5  206.74  4493.7  204.94
  4550.0  201.13  4555.8  199.38  4580.9  197.71  4587.7  196.57  4631.1  193.68
  4683.2  191.07  4734.5  189.64  4796.3  187.22  4920.1  187.58  4978.3  187.23
  4984.5  185.90  4989.7  185.85  4999.3  183.18  5007.6  183.11  5007.9  182.61
  5011.9  183.11  5041.2  187.64  5049.0  187.97  5051.8  187.12  5054.8  187.97
  5062.8  188.29  5173.8  190.15  5354.3  191.96  5461.8  194.83  5609.5  200.62
#Mann=6,-1,0
  4340.1    0.12       0  4631.1     0.1       0  4734.5    0.12       0
  4920.1    0.04       0  5007.6    0.04       0  5011.9    0.04       0
Bank Sta=5007.6,5011.9
Exp/Cntr=0.3,0.1

Type RM Length L Ch R = 1,34602,361,361,361
BEGIN DESCRIPTION:
LGII2989
END DESCRIPTION:
XS GIS Cut Line= 3
      2569264.05     13563245.35      2568431.08     13563020.86
      2567923.04     13562932.25
#Sta/Elev= 30
  4234.0  196.41  4378.2  196.70  4405.6  196.72  4411.3  197.09  4486.9  195.80
  4565.4  192.92  4605.9  192.45  4626.6  191.55  4640.5  191.74  4804.1  186.45
  4869.7  185.20  4922.7  185.08  4958.0  184.38  4984.3  182.23  4989.5  182.37
  4997.3  179.60  4997.5  179.10  5001.3  179.10  5001.6  179.60  5019.1  184.91
  5030.5  184.00  5059.0  185.63  5123.2  187.01  5278.4  192.28  5376.9  197.25
  5452.0  201.98  5488.6  206.76  5529.2  209.74  5571.1  211.49  5612.4  211.51
#Mann=9,-1,0
  4234.0    0.12       0  4378.2    0.05       0  4405.6    0.12       0
  4486.9    0.05       0  4565.4    0.12       0  4804.1    0.05       0
  4922.7    0.04       0  4997.3    0.04       0  5001.6    0.04       0
Bank Sta=4997.3,5001.6
Exp/Cntr=0.3,0.1

Type RM Length L Ch R = 1,34241,497,497,497
BEGIN DESCRIPTION:
LGII2988
END DESCRIPTION:
XS GIS Cut Line= 3
      2569353.58     13562972.04      2568463.82     13562711.62
      2567942.96     13562733.32
#Sta/Elev= 30
  4345.9  193.88  4410.2  193.71  4584.1  192.83  4594.5  193.33  4740.0  190.75
  4771.6  189.52  4792.5  189.65  4817.2  188.15  4847.6  187.51  4889.3  185.60
  4938.3  185.22  4961.4  183.91  4982.1  184.10  4989.6  183.61  4994.8  181.66
  5026.0  178.84  5026.3  178.34  5030.4  178.84  5042.5  182.74  5052.9  184.11
  5083.7  183.76  5125.9  184.09  5157.1  183.37  5244.4  184.28  5401.9  188.26
  5512.0  193.47  5602.1  196.48  5682.2  201.73  5722.2  206.31  5794.3  208.98
#Mann=7,-1,0
  4345.9    0.05       0  4410.2    0.12       0  4847.6    0.05       0
  4982.1     0.1       0  5026.0    0.05       0  5030.4     0.1       0
  5083.7    0.04       0
Bank Sta=5026,5030.4
Exp/Cntr=0.3,0.1

Type RM Length L Ch R = 1,33744,476,476,476
BEGIN DESCRIPTION:
LGII2987
END DESCRIPTION:
XS GIS Cut Line= 2
      2569537.99     13562689.90      2568149.59     13562201.79
#Sta/Elev= 30
  4138.5  194.62  4453.8  190.81  4512.7  190.32  4709.9  185.03  4904.9  181.97
  4915.5  181.56  4921.5  180.28  4926.8  181.70  4936.7  181.13  4947.1  178.67
  4952.4  180.94  4957.9  179.19  4968.5  177.27  4981.2  176.33  4981.5  175.83
  4985.7  176.33  4989.7  177.57  5021.5  181.06  5076.3  181.26  5138.3  183.86
  5189.6  184.94  5201.7  185.89  5297.1  188.06  5406.5  193.57  5456.1  197.32
  5463.1  198.44  5499.9  200.02  5575.1  202.42  5593.9  203.42  5610.2  202.92
#Mann=6,-1,0
  4138.5    0.12       0  4453.8    0.04       0  4981.2    0.04       0
  4985.7    0.04       0  5499.9    0.12       0  5575.1    0.04       0
Bank Sta=4981.2,4985.7
Exp/Cntr=0.3,0.1

Type RM Length L Ch R = 1,33268,370,370,370
BEGIN DESCRIPTION:
LGII2986
END DESCRIPTION:
XS GIS Cut Line= 2
      2569700.79     13562451.20      2568390.39     13561779.76
#Sta/Elev= 30
  4015.7  191.66  4344.8  189.21  4417.1  187.07  4494.1  186.38  4521.5  184.83
  4611.3  182.50  4730.1  180.90  4833.3  180.85  4909.9  178.87  4983.1  179.56
  4988.7  179.16  5008.7  173.65  5009.0  173.15  5013.2  173.65  5021.8  176.71
  5027.5  181.19  5033.5  183.34  5053.2  184.00  5066.2  185.15  5071.9  184.67
  5088.4  185.38  5116.3  188.09  5152.3  190.12  5205.1  198.92  5258.2  204.10
  5332.6  204.70  5360.5  203.61  5438.0  203.47  5465.9  202.60  5488.1  203.46
#Mann=6,-1,0
  4015.7    0.12       0  4521.5    0.04       0  5008.7    0.04       0
  5013.2    0.04       0  5053.2    0.12       0  5152.3    0.04       0
Bank Sta=5008.7,5013.2
Exp/Cntr=0.3,0.1

Type RM Length L Ch R = 1,32898,635,635,635
BEGIN DESCRIPTION:
LGII2985
END DESCRIPTION:
XS GIS Cut Line= 2
      2569831.04     13562234.21      2568552.26     13561388.92
#Sta/Elev= 30
  4086.9  188.58  4299.0  187.28  4471.3  184.74  4645.5  180.99  4696.2  180.75
  4747.4  179.24  4797.9  179.08  4863.9  179.15  4906.9  179.46  4949.0  178.20
  4957.2  178.66  4964.1  177.45  4993.2  176.87  5000.2  172.57  5003.9  172.54
  5004.3  172.04  5008.2  172.04  5008.5  172.54  5042.3  177.95  5129.6  181.07
  5144.7  182.74  5268.1  186.84  5280.9  186.63  5439.6  191.44  5520.6  194.72
  5542.0  196.53  5562.6  197.09  5569.0  198.35  5599.1  198.98  5619.8  200.50
#Mann=6,-1,0
  4086.9    0.12       0  4471.3    0.04       0  4797.9    0.12       0
  4863.9    0.04       0  5003.9    0.04       0  5008.5    0.04       0
Bank Sta=5003.9,5008.5
Exp/Cntr=0.3,0.1

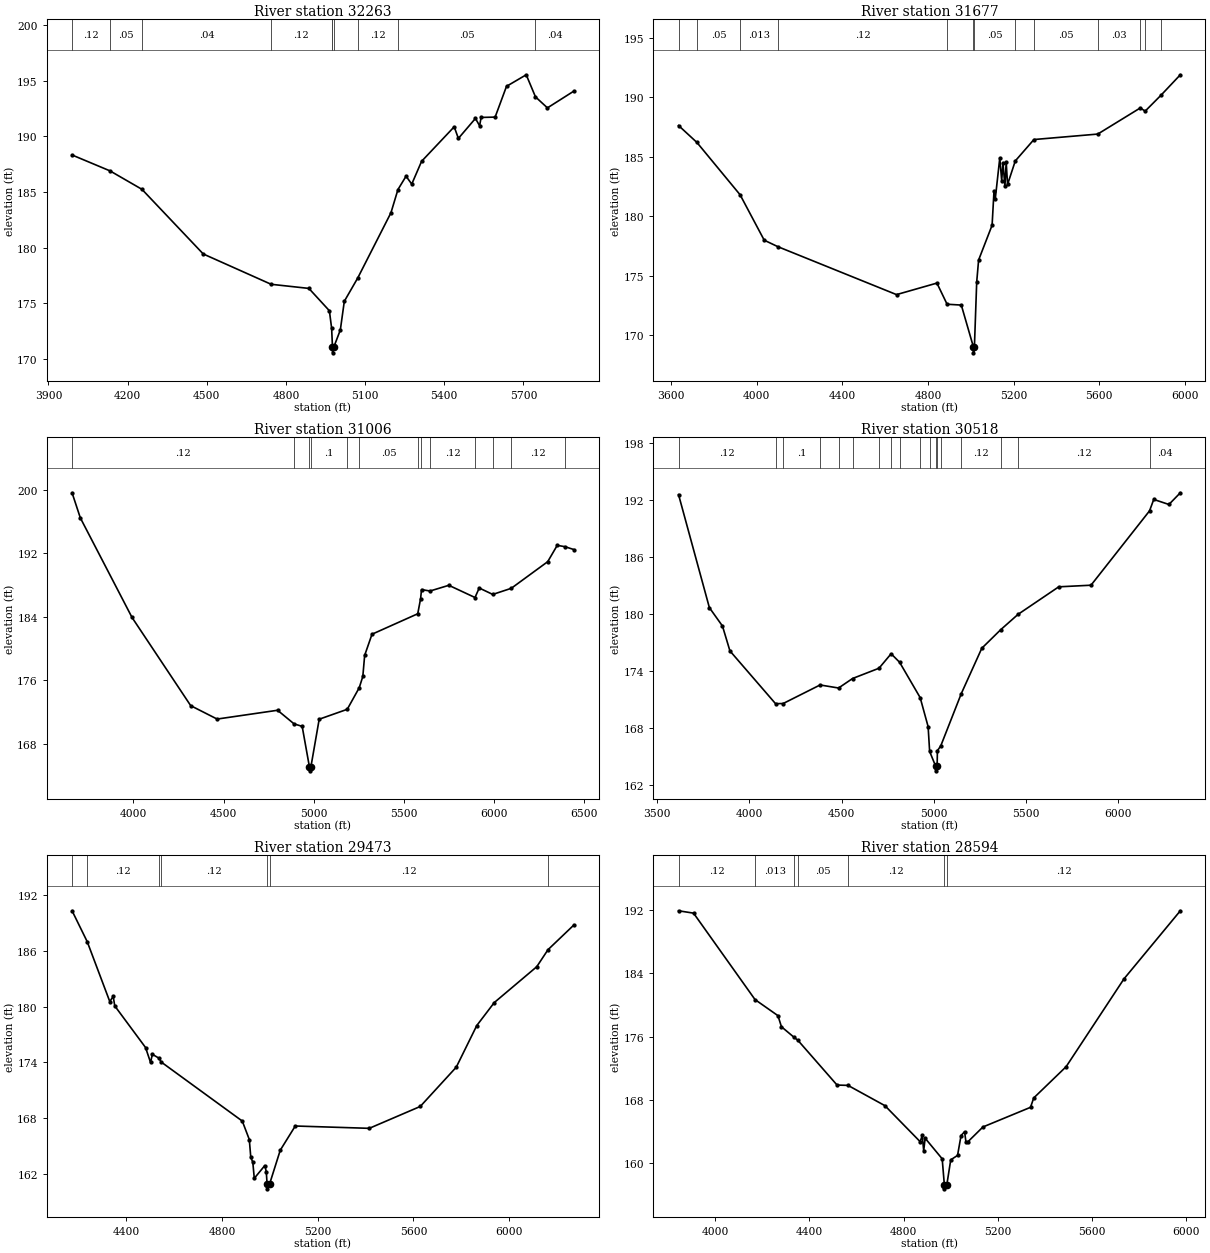
Type RM Length L Ch R = 1,32263,586,586,586
BEGIN DESCRIPTION:
LGII2984
END DESCRIPTION:
XS GIS Cut Line= 4
      2569906.97     13562179.96      2569765.90     13561550.60
      2569331.87     13561127.42      2568768.82     13560802.58
#Sta/Elev= 30
  3989.7  188.33  4133.4  186.90  4254.4  185.24  4486.7  179.42  4744.0  176.69
  4886.9  176.32  4964.6  174.31  4973.1  172.74  4976.4  171.02  4976.7  170.52
  4981.1  171.02  5006.1  172.58  5021.2  175.16  5072.1  177.26  5197.9  183.13
  5224.4  185.22  5255.1  186.42  5276.7  185.71  5314.0  187.76  5437.6  190.87
  5453.3  189.82  5518.0  191.62  5533.8  190.96  5539.5  191.71  5592.6  191.74
  5635.7  194.51  5710.4  195.55  5745.5  193.56  5790.8  192.57  5890.9  194.08
#Mann=10,-1,0
  3989.7    0.12       0  4133.4    0.05       0  4254.4    0.04       0
  4744.0    0.12       0  4973.1    0.05       0  4976.4    0.05       0
  4981.1    0.05       0  5072.1    0.12       0  5224.4    0.05       0
  5745.5    0.04       0
Bank Sta=4976.4,4981.1
Exp/Cntr=0.3,0.1

Type RM Length L Ch R = 1,31677,671,671,671
BEGIN DESCRIPTION:
LGII2983
END DESCRIPTION:
XS GIS Cut Line= 4
      2569961.22     13562125.67      2570167.38     13561311.88
      2569733.35     13560671.69      2569008.14     13560758.28
#Sta/Elev= 30
  3635.1  187.64  3720.7  186.22  3922.6  181.81  4035.2  177.99  4099.5  177.44
  4653.1  173.41  4841.7  174.38  4889.2  172.60  4955.6  172.53  5012.1  169.01
  5012.5  168.51  5016.8  169.01  5027.5  174.47  5036.4  176.32  5099.4  179.25
  5108.3  182.13  5114.3  181.48  5135.3  184.91  5144.2  183.01  5150.3  184.47
  5159.2  182.52  5165.2  184.56  5171.6  182.68  5207.7  184.66  5294.7  186.46
  5592.8  186.92  5791.6  189.12  5814.2  188.85  5888.7  190.20  5978.4  191.91
#Mann=13,-1,0
  3635.1    0.12       0  3720.7    0.05       0  3922.6   0.013       0
  4099.5    0.12       0  4889.2    0.05       0  5012.1    0.05       0
  5016.8    0.05       0  5207.7    0.03       0  5294.7    0.05       0
  5592.8    0.03       0  5791.6    0.12       0  5814.2    0.03       0
  5888.7    0.05       0
Bank Sta=5012.1,5016.8
Exp/Cntr=0.3,0.1

Type RM Length L Ch R = 1,31006,488,488,488
BEGIN DESCRIPTION:
LGII2982
END DESCRIPTION:
XS GIS Cut Line= 3
      2571610.50     13560628.28      2570080.57     13560498.08
      2568854.42     13560725.95
#Sta/Elev= 30
  3659.7  199.64  3705.4  196.48  3992.3  183.91  4317.6  172.79  4464.0  171.10
  4799.3  172.21  4891.0  170.49  4935.7  170.18  4975.9  165.07  4976.4  164.57
  4984.1  165.07  5030.1  171.08  5185.6  172.33  5252.1  175.05  5272.0  176.47
  5282.2  179.13  5322.9  181.80  5576.5  184.38  5592.4  186.28  5597.5  187.43
  5644.7  187.25  5749.0  187.97  5894.1  186.43  5917.5  187.63  5992.5  186.82
  6095.2  187.59  6297.3  190.95  6350.1  193.01  6393.2  192.84  6442.3  192.48
#Mann=13,-1,0
  3659.7    0.12       0  4891.0     0.1       0  4975.9    0.05       0
  4984.1     0.1       0  5185.6    0.12       0  5252.1    0.05       0
  5576.5    0.03       0  5592.4    0.05       0  5644.7    0.12       0
  5894.1    0.05       0  5992.5    0.03       0  6095.2    0.12       0
  6393.2    0.04       0
Bank Sta=4975.9,4984.1
Exp/Cntr=0.3,0.1

Type RM Length L Ch R = 1,30518,1045,1045,1045
BEGIN DESCRIPTION:
LGII2981
END DESCRIPTION:
XS GIS Cut Line= 4
      2571350.06     13559825.34      2570460.34     13559966.39
      2569852.71     13560270.21      2568779.20     13560649.73
#Sta/Elev= 30
  3616.7  192.57  3783.8  180.68  3854.7  178.75  3895.2  176.13  4142.4  170.58
  4183.7  170.60  4383.7  172.55  4483.7  172.23  4559.7  173.23  4702.9  174.31
  4768.5  175.83  4814.4  174.94  4925.9  171.22  4969.0  168.17  4977.2  165.56
  5009.5  164.02  5010.0  163.52  5017.9  164.02  5019.3  165.64  5037.4  166.14
  5148.9  171.65  5259.8  176.41  5362.2  178.36  5456.6  179.98  5676.7  182.87
  5851.5  183.04  6168.7  190.86  6191.5  192.06  6273.7  191.53  6335.5  192.76
#Mann=18,-1,0
  3616.7    0.12       0  4142.4    0.05       0  4183.7     0.1       0
  4383.7    0.05       0  4483.7    0.12       0  4559.7    0.05       0
  4702.9    0.12       0  4768.5     0.1       0  4814.4    0.12       0
  4925.9     0.1       0  4977.2    0.12       0  5009.5    0.05       0
  5017.9    0.12       0  5037.4     0.1       0  5148.9    0.12       0
  5362.2    0.05       0  5456.6    0.12       0  6168.7    0.04       0
Bank Sta=5009.5,5017.9
Exp/Cntr=0.3,0.1

Type RM Length L Ch R = 1,29473,879,879,879
BEGIN DESCRIPTION:
LGII2980
END DESCRIPTION:
XS GIS Cut Line= 3
      2570210.80     13558848.75      2569711.65     13559271.95
      2568855.57     13560431.45
#Sta/Elev= 30
  4174.3  190.29  4237.6  186.97  4331.8  180.54  4346.1  181.09  4352.6  180.07
  4481.2  175.60  4502.0  174.00  4509.7  174.87  4539.0  174.43  4545.1  174.07
  4885.2  167.70  4914.5  165.72  4920.7  163.80  4929.1  163.29  4935.3  161.55
  4979.2  162.92  4985.4  162.27  4988.8  160.92  4989.3  160.42  4999.0  160.92
  5043.8  164.57  5106.5  167.17  5415.6  166.92  5628.5  169.27  5778.9  173.49
  5864.5  177.96  5937.6  180.43  6115.0  184.28  6162.0  186.11  6270.0  188.76
#Mann=7,-1,0
  4174.3    0.05       0  4237.6    0.12       0  4539.0   0.013       0
  4545.1    0.12       0  4988.8    0.05       0  4999.0    0.12       0
  6162.0    0.04       0
Bank Sta=4988.8,4999
Exp/Cntr=0.3,0.1

Type RM Length L Ch R = 1,28594,776,776,776
BEGIN DESCRIPTION:
LGII2979
END DESCRIPTION:
XS GIS Cut Line= 3
      2569668.23     13558490.71      2568962.95     13558978.98
      2568247.34     13560030.71
#Sta/Elev= 30
  3844.3  191.90  3908.1  191.60  4169.0  180.69  4266.3  178.66  4281.1  177.26
  4335.4  175.91  4350.9  175.55  4517.2  169.90  4563.5  169.86  4720.3  167.30
  4870.0  162.75  4878.7  163.54  4884.9  161.61  4891.0  163.19  4963.4  160.59
  4972.6  157.30  4973.1  156.80  4983.0  157.30  4999.7  160.46  5028.6  161.02
  5043.5  163.53  5058.5  164.01  5064.5  162.66  5072.2  162.73  5136.4  164.61
  5338.3  167.09  5351.9  168.27  5489.5  172.22  5734.9  183.30  5974.2  191.90
#Mann=7,-1,0
  3844.3    0.12       0  4169.0   0.013       0  4335.4    0.12       0
  4350.9    0.05       0  4563.5    0.12       0  4972.6    0.05       0
  4983.0    0.12       0
Bank Sta=4972.6,4983
Exp/Cntr=0.3,0.1