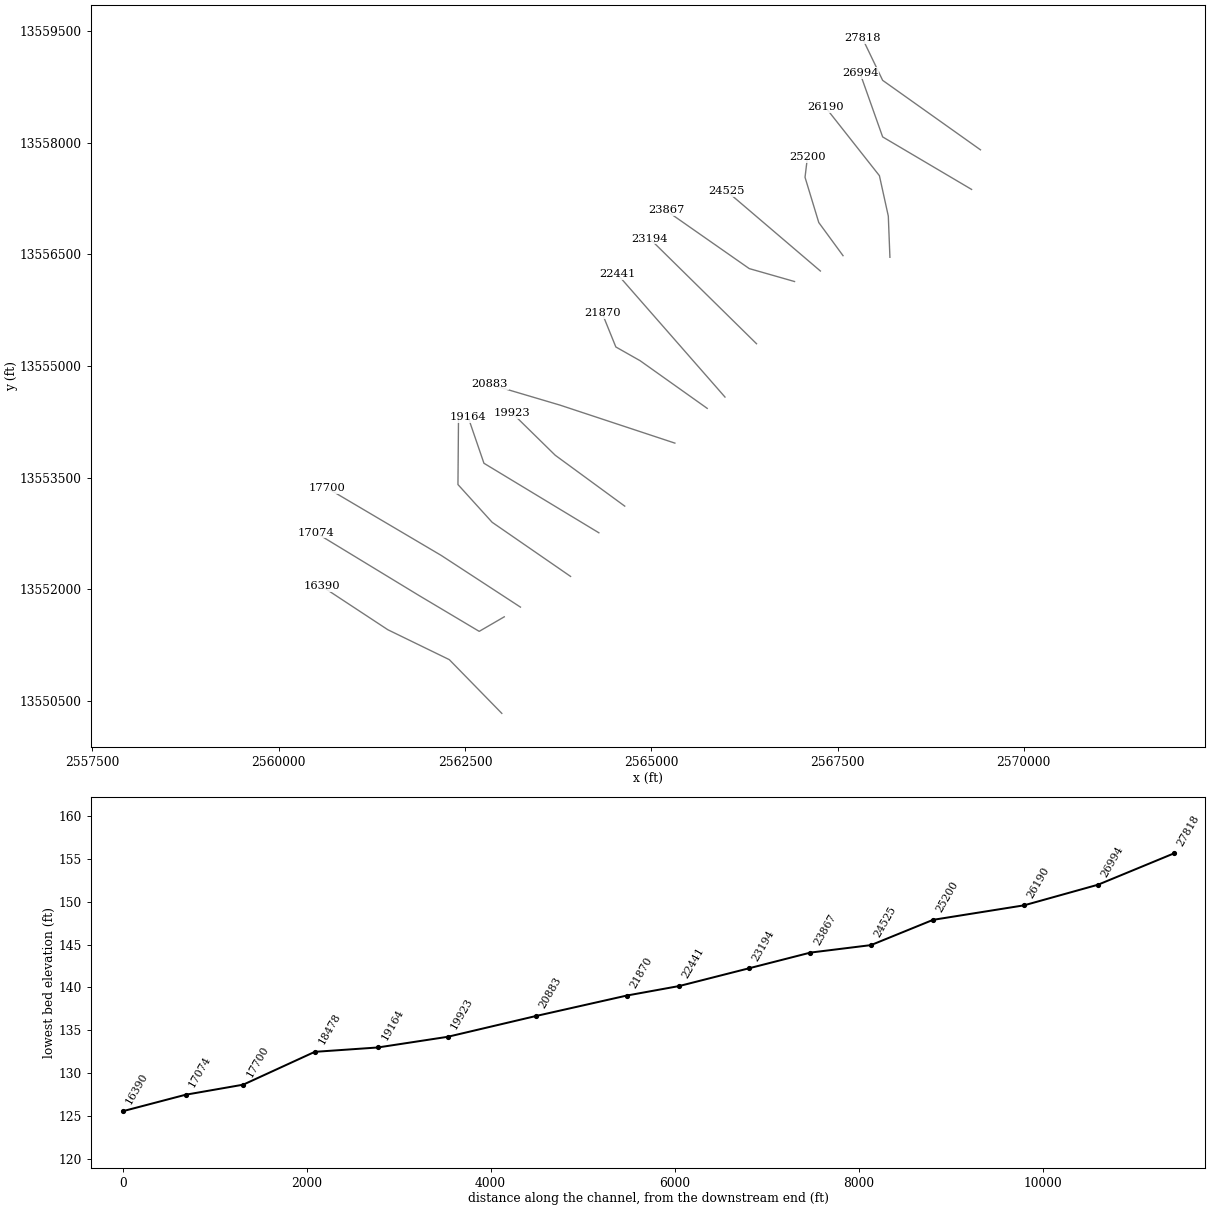
HEC-RAS study PRICE CREEK.prj: PRICE CREEK Base Level Engineering

--- PRICE CREEK.g01 (geometry) --- (continued)

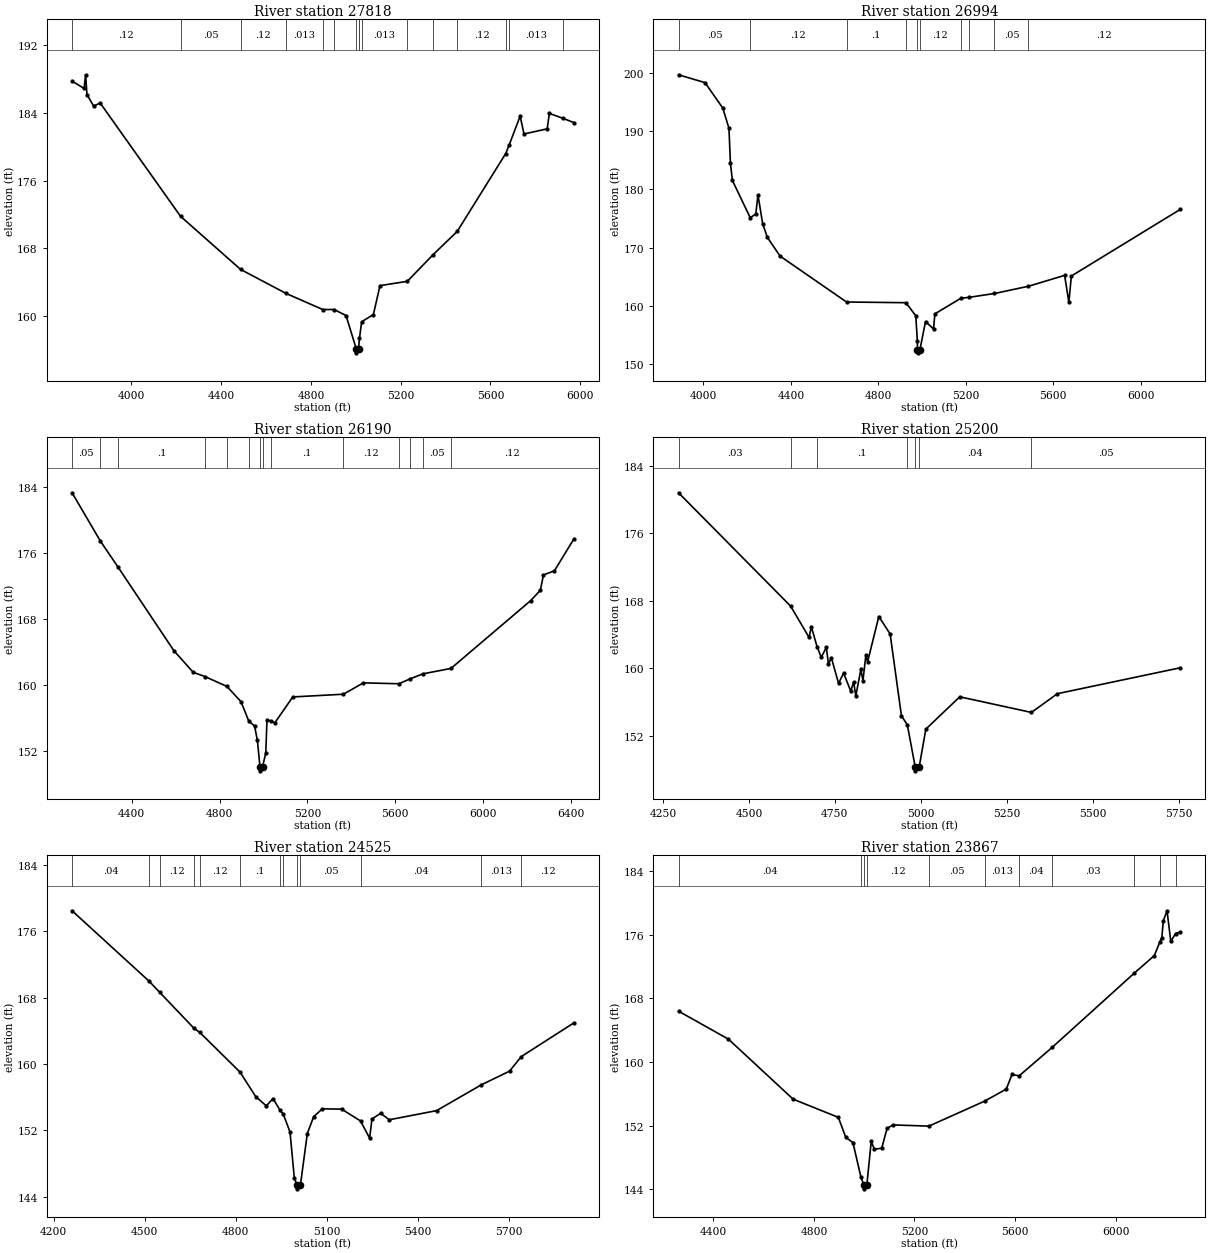
Type RM Length L Ch R = 1,27818,824,824,824
BEGIN DESCRIPTION:
LGII2978
END DESCRIPTION:
XS GIS Cut Line= 3
      2569418.69     13557904.75      2568105.74     13558837.92
      2567834.50     13559402.12
#Sta/Elev= 30
  3735.2  187.78  3788.8  186.91  3795.5  188.53  3801.6  186.19  3831.2  184.83
  3860.7  185.18  4218.7  171.77  4486.2  165.48  4688.8  162.64  4852.5  160.73
  4902.9  160.73  4956.5  160.02  5001.7  156.10  5002.2  155.60  5012.2  156.10
  5016.2  157.30  5026.0  159.28  5078.3  160.13  5107.8  163.56  5229.5  164.07
  5343.6  167.20  5452.3  169.99  5668.2  179.20  5683.3  180.20  5732.6  183.63
  5749.7  181.52  5853.1  182.13  5862.8  183.96  5924.3  183.36  5972.0  182.87
#Mann=16,-1,0
  3735.2    0.12       0  4218.7    0.05       0  4486.2    0.12       0
  4688.8   0.013       0  4852.5    0.12       0  4902.9   0.013       0
  5001.7    0.03       0  5012.2   0.013       0  5016.2    0.05       0
  5026.0   0.013       0  5229.5    0.12       0  5343.6   0.013       0
  5452.3    0.12       0  5668.2    0.05       0  5683.3   0.013       0
  5924.3    0.05       0
Bank Sta=5001.7,5012.2
Exp/Cntr=0.3,0.1

Type RM Length L Ch R = 1,26994,804,804,804
BEGIN DESCRIPTION:
LGII2977
END DESCRIPTION:
XS GIS Cut Line= 3
      2569299.35     13557373.06      2568105.74     13558078.37
      2567801.92     13558935.60
#Sta/Elev= 30
  3886.0  199.66  4007.2  198.31  4088.5  193.95  4116.7  190.48  4123.4  184.55
  4132.3  181.54  4214.1  175.13  4239.6  175.79  4249.4  179.08  4270.8  174.13
  4292.3  171.77  4350.8  168.55  4654.6  160.68  4926.4  160.56  4971.3  158.33
  4978.9  153.92  4979.2  152.46  4979.7  151.96  4990.3  152.46  5016.0  157.33
  5052.6  156.06  5058.9  158.65  5177.8  161.32  5215.5  161.48  5331.6  162.14
  5486.6  163.38  5652.5  165.25  5672.0  160.63  5683.3  165.14  6181.9  176.57
#Mann=10,-1,0
  3886.0    0.05       0  4214.1    0.12       0  4654.6     0.1       0
  4926.4    0.12       0  4979.2    0.05       0  4990.3    0.12       0
  5177.8    0.05       0  5215.5    0.12       0  5331.6    0.05       0
  5486.6    0.12       0
Bank Sta=4979.2,4990.3
Exp/Cntr=0.3,0.1

Type RM Length L Ch R = 1,26190,990,990,990
BEGIN DESCRIPTION:
LGII2976
END DESCRIPTION:
XS GIS Cut Line= 4
      2568203.40     13556461.61      2568181.70     13557015.01
      2568062.34     13557557.54      2567335.36     13558479.83
#Sta/Elev= 30
  4128.8  183.31  4258.1  177.43  4338.0  174.29  4592.6  164.13  4680.1  161.52
  4733.0  161.01  4833.3  159.81  4897.6  157.96  4933.6  155.56  4959.1  155.02
  4972.1  153.29  4983.9  150.06  4984.4  149.56  4995.7  150.06  5010.3  151.72
  5015.9  155.72  5033.9  155.62  5051.2  155.37  5133.1  158.53  5363.6  158.86
  5454.8  160.24  5616.5  160.13  5665.7  160.71  5724.9  161.33  5853.2  161.99
  6216.4  170.23  6259.8  171.47  6274.2  173.34  6323.9  173.84  6412.5  177.70
#Mann=14,-1,0
  4128.8    0.05       0  4258.1    0.12       0  4338.0     0.1       0
  4733.0    0.05       0  4833.3    0.12       0  4933.6    0.05       0
  4983.9    0.05       0  4995.7    0.05       0  5033.9     0.1       0
  5363.6    0.12       0  5616.5    0.05       0  5665.7    0.12       0
  5724.9    0.05       0  5853.2    0.12       0
Bank Sta=4983.9,4995.7
Exp/Cntr=0.3,0.1

Type RM Length L Ch R = 1,25200,675,675,675
BEGIN DESCRIPTION:
LGII2975
END DESCRIPTION:
XS GIS Cut Line= 4
      2567574.04     13556483.35      2567248.54     13556928.20
      2567064.08     13557535.84      2567096.63     13557807.15
#Sta/Elev= 30
  4295.3  180.81  4621.4  167.38  4675.0  163.67  4681.5  164.95  4698.1  162.59
  4710.5  161.31  4725.2  162.51  4731.4  160.49  4739.8  161.28  4760.7  158.23
  4775.4  159.45  4796.2  157.31  4804.7  158.40  4810.9  156.72  4825.5  159.88
  4831.7  158.57  4840.2  161.56  4845.3  160.80  4877.8  166.15  4910.7  164.09
  4943.6  154.40  4960.8  153.31  4983.5  148.37  4984.0  147.87  4995.4  148.37
  5014.6  152.81  5113.3  156.64  5321.7  154.79  5397.3  157.01  5754.8  160.08
#Mann=7,-1,0
  4295.3    0.03       0  4621.4    0.05       0  4698.1     0.1       0
  4960.8    0.04       0  4983.5    0.04       0  4995.4    0.04       0
  5321.7    0.05       0
Bank Sta=4983.5,4995.4
Exp/Cntr=0.3,0.1

Type RM Length L Ch R = 1,24525,658,658,658
BEGIN DESCRIPTION:
LGII2974
END DESCRIPTION:
XS GIS Cut Line= 2
      2567270.24     13556277.16      2566012.36     13557350.69
#Sta/Elev= 30
  4260.6  178.46  4515.1  169.95  4549.2  168.63  4662.1  164.30  4681.6  163.79
  4814.1  159.01  4865.7  156.06  4900.8  154.93  4922.8  155.82  4946.5  154.38
  4956.1  153.98  4978.8  151.80  4993.1  146.23  5001.4  145.43  5001.9  144.93
  5013.3  145.43  5035.9  151.60  5056.7  153.63  5085.3  154.58  5149.0  154.54
  5211.4  153.11  5241.2  151.04  5248.9  153.35  5277.4  154.04  5306.0  153.26
  5461.9  154.36  5608.7  157.46  5702.3  159.12  5741.1  160.88  5914.3  164.94
#Mann=13,-1,0
  4260.6    0.04       0  4515.1    0.03       0  4549.2    0.12       0
  4662.1    0.05       0  4681.6    0.12       0  4814.1     0.1       0
  4946.5    0.04       0  4956.1    0.05       0  5001.4    0.05       0
  5013.3    0.05       0  5211.4    0.04       0  5608.7   0.013       0
  5741.1    0.12       0
Bank Sta=5001.4,5013.3
Exp/Cntr=0.3,0.1

Type RM Length L Ch R = 1,23867,673,673,673
BEGIN DESCRIPTION:
LGII2973
END DESCRIPTION:
XS GIS Cut Line= 3
      2566923.05     13556136.09      2566315.38     13556309.71
      2565197.75     13557090.96
#Sta/Elev= 30
  4261.7  166.38  4460.2  162.86  4717.6  155.32  4897.2  153.04  4926.9  150.52
  4955.2  149.87  4986.9  145.56  4998.3  144.56  4998.8  144.06  5010.7  144.56
  5028.0  150.02  5040.6  149.03  5069.9  149.17  5090.8  151.64  5113.8  152.09
  5257.6  151.94  5479.1  155.08  5565.2  156.59  5587.9  158.43  5616.2  158.25
  5747.7  161.83  6073.2  171.13  6153.9  173.36  6176.0  175.09  6183.6  175.58
  6189.7  177.74  6204.5  178.99  6219.3  175.15  6238.6  176.13  6257.3  176.33
#Mann=11,-1,0
  4261.7    0.04       0  4986.9    0.12       0  4998.3    0.05       0
  5010.7    0.12       0  5257.6    0.05       0  5479.1   0.013       0
  5616.2    0.04       0  5747.7    0.03       0  6073.2    0.05       0
  6176.0   0.013       0  6238.6    0.05       0
Bank Sta=4998.3,5010.7
Exp/Cntr=0.3,0.1

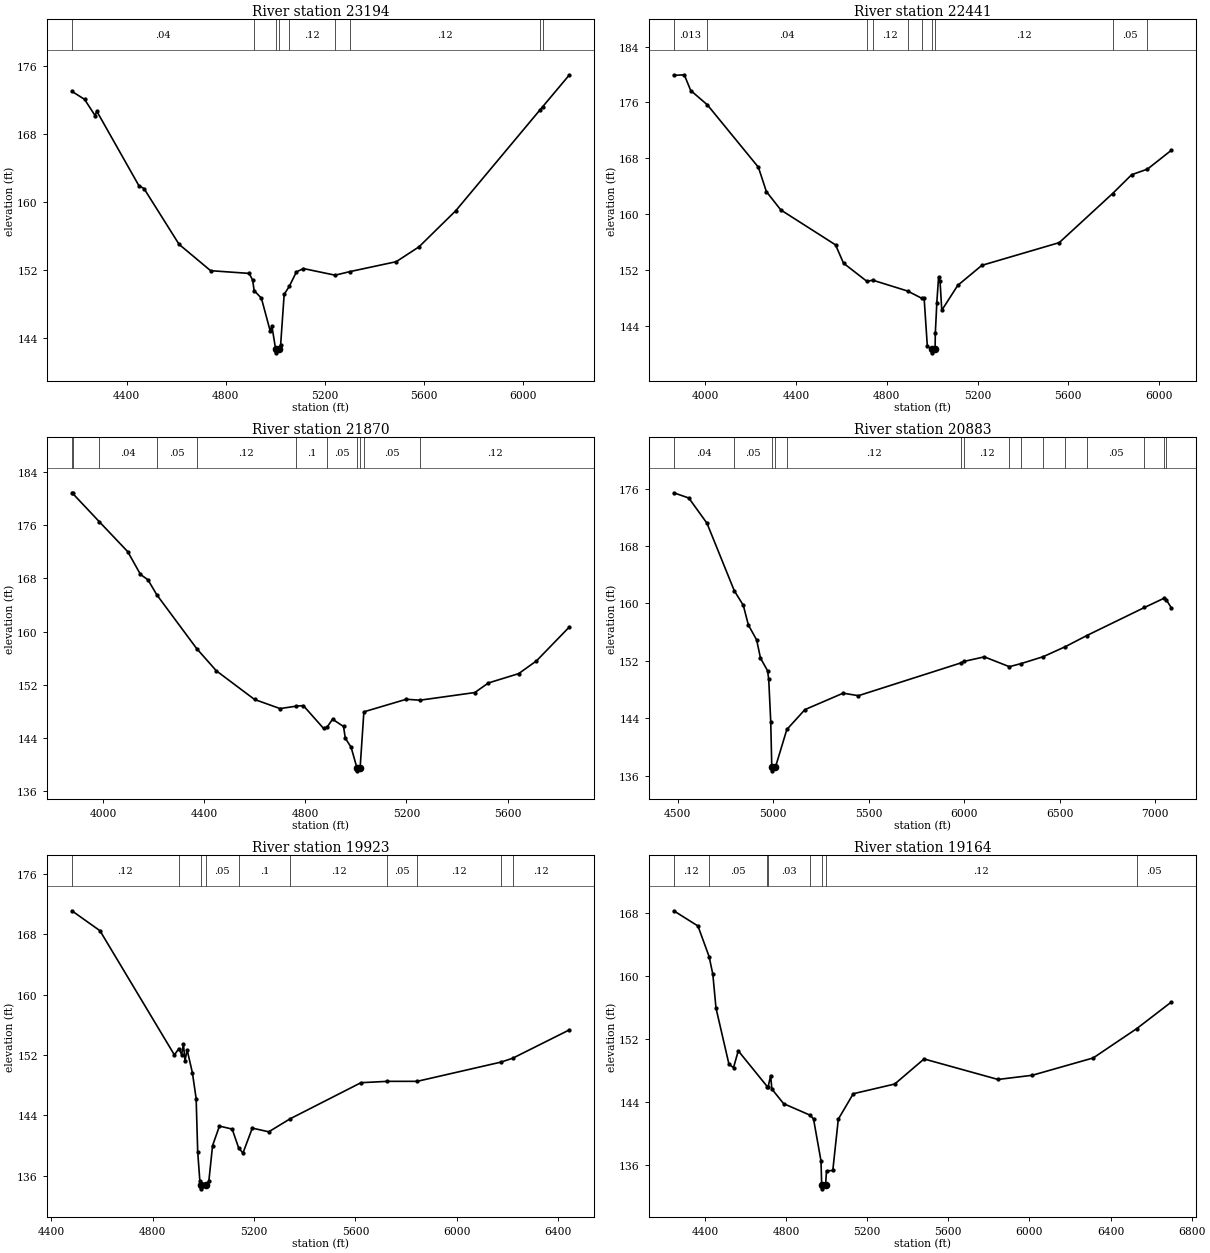
Type RM Length L Ch R = 1,23194,753,753,753
BEGIN DESCRIPTION:
LGII2972
END DESCRIPTION:
XS GIS Cut Line= 2
      2566413.01     13555300.62      2564981.34     13556710.60
#Sta/Elev= 30
  4178.3  173.00  4229.5  172.06  4272.0  170.15  4279.0  170.66  4448.7  161.91
  4470.0  161.54  4611.3  154.99  4738.6  151.89  4894.2  151.57  4908.3  150.79
  4914.3  149.55  4943.7  148.65  4979.0  144.81  4986.1  145.36  5000.8  142.72
  5001.3  142.22  5013.7  142.72  5021.4  143.17  5035.6  149.11  5056.2  150.04
  5085.1  151.75  5113.4  152.14  5241.4  151.36  5300.8  151.78  5488.2  152.95
  5580.1  154.70  5728.6  158.95  6068.5  170.81  6080.0  171.21  6187.7  174.95
#Mann=9,-1,0
  4178.3    0.04       0  4914.3   0.013       0  5000.8    0.03       0
  5013.7   0.013       0  5056.2    0.12       0  5241.4    0.05       0
  5300.8    0.12       0  6068.5    0.03       0  6080.0    0.12       0
Bank Sta=5000.8,5013.7
Exp/Cntr=0.3,0.1

Type RM Length L Ch R = 1,22441,571,571,571
BEGIN DESCRIPTION:
LGII2971
END DESCRIPTION:
XS GIS Cut Line= 2
      2565989.87     13554584.44      2564546.69     13556233.78
#Sta/Elev= 30
  3862.0  179.87  3908.3  179.96  3936.8  177.71  4010.0  175.66  4234.8  166.73
  4269.9  163.25  4333.5  160.62  4574.6  155.62  4609.7  153.00  4713.2  150.39
  4738.2  150.57  4892.4  149.01  4954.1  147.98  4964.7  148.03  4978.9  141.10
  4999.9  140.67  5000.4  140.17  5013.0  140.67  5014.0  142.94  5020.7  147.37
  5028.3  150.98  5034.9  150.39  5042.5  146.26  5112.7  149.82  5219.0  152.69
  5559.8  155.94  5794.9  162.97  5878.7  165.66  5948.4  166.46  6053.6  169.16
#Mann=10,-1,0
  3862.0   0.013       0  4010.0    0.04       0  4713.2    0.05       0
  4738.2    0.12       0  4892.4    0.05       0  4954.1    0.12       0
  4999.9    0.05       0  5013.0    0.12       0  5794.9    0.05       0
  5948.4    0.12       0
Bank Sta=4999.9,5013
Exp/Cntr=0.3,0.1

Type RM Length L Ch R = 1,21870,987,987,987
BEGIN DESCRIPTION:
LGII2970
END DESCRIPTION:
XS GIS Cut Line= 4
      2565751.16     13554432.53      2564850.54     13555072.73
      2564525.01     13555257.19      2564341.15     13555711.46
#Sta/Elev= 30
  3875.9  180.86  3878.6  180.78  3984.5  176.51  4097.0  172.01  4147.5  168.58
  4177.0  167.78  4212.1  165.52  4369.6  157.45  4447.8  154.09  4598.8  149.79
  4699.7  148.42  4763.4  148.78  4791.9  148.87  4871.9  145.44  4886.5  145.66
  4907.5  146.82  4950.9  145.73  4958.0  143.97  4980.9  142.61  5003.6  139.56
  5004.1  139.06  5016.7  139.56  5031.5  147.93  5199.2  149.82  5253.6  149.68
  5470.5  150.83  5524.1  152.27  5643.9  153.67  5714.5  155.59  5845.1  160.71
#Mann=11,-1,0
  3875.9    0.04       0  3878.6   0.013       0  3984.5    0.04       0
  4212.1    0.05       0  4369.6    0.12       0  4763.4     0.1       0
  4886.5    0.05       0  5003.6    0.05       0  5016.7    0.05       0
  5031.5    0.05       0  5253.6    0.12       0
Bank Sta=5003.6,5016.7
Exp/Cntr=0.3,0.1

Type RM Length L Ch R = 1,20883,960,960,960
BEGIN DESCRIPTION:
LGII2969
END DESCRIPTION:
XS GIS Cut Line= 3
      2565317.14     13553965.95      2563776.32     13554475.94
      2562834.14     13554755.13
#Sta/Elev= 30
  4479.0  175.42  4557.9  174.69  4653.0  171.18  4795.9  161.78  4843.3  159.74
  4869.8  157.00  4913.1  154.92  4933.2  152.39  4970.2  150.63  4976.3  149.46
  4986.9  143.55  4992.4  137.18  4992.9  136.68  5011.4  137.18  5071.2  142.44
  5165.9  145.21  5366.1  147.50  5445.9  147.15  5984.5  151.73  5997.8  151.92
  6105.3  152.56  6236.4  151.19  6299.0  151.63  6414.2  152.59  6530.3  153.99
  6642.0  155.53  6944.0  159.44  7047.4  160.74  7058.3  160.50  7084.7  159.38
#Mann=15,-1,0
  4479.0    0.04       0  4795.9    0.05       0  4992.4    0.05       0
  5011.4    0.05       0  5071.2    0.12       0  5984.5    0.05       0
  5997.8    0.12       0  6236.4    0.05       0  6299.0    0.12       0
  6414.2    0.05       0  6530.3    0.12       0  6642.0    0.05       0
  6944.0    0.12       0  7047.4    0.03       0  7058.3    0.12       0
Bank Sta=4992.4,5011.4
Exp/Cntr=0.3,0.1

Type RM Length L Ch R = 1,19923,759,759,759
BEGIN DESCRIPTION:
LGII2968
END DESCRIPTION:
XS GIS Cut Line= 3
      2564644.34     13553119.63      2563711.21     13553803.20
      2563136.11     13554367.45
#Sta/Elev= 30
  4481.7  171.12  4592.4  168.48  4886.1  152.01  4903.7  152.86  4914.7  152.05
  4921.6  153.48  4927.8  151.23  4936.3  152.67  4957.1  149.64  4971.8  146.23
  4978.0  139.16  4986.5  135.28  4991.6  134.76  4992.1  134.26  5010.7  134.76
  5022.0  135.31  5036.6  139.99  5063.7  142.58  5113.9  142.18  5139.7  139.66
  5156.5  139.01  5193.3  142.31  5258.2  141.82  5342.2  143.54  5621.8  148.33
  5726.2  148.51  5843.4  148.51  6173.9  151.06  6219.9  151.57  6444.1  155.34
#Mann=10,-1,0
  4481.7    0.12       0  4903.7    0.05       0  4991.6    0.05       0
  5010.7    0.05       0  5139.7     0.1       0  5342.2    0.12       0
  5726.2    0.05       0  5843.4    0.12       0  6173.9    0.05       0
  6219.9    0.12       0
Bank Sta=4991.6,5010.7
Exp/Cntr=0.3,0.1

Type RM Length L Ch R = 1,19164,686,686,686
BEGIN DESCRIPTION:
LGII2967
END DESCRIPTION:
XS GIS Cut Line= 3
      2564297.17     13552761.52      2562754.81     13553695.33
      2562543.91     13554310.88
#Sta/Elev= 30
  4246.2  168.28  4365.6  166.35  4420.7  162.46  4439.0  160.22  4454.5  155.95
  4518.5  148.82  4541.0  148.39  4564.4  150.52  4708.2  145.96  4711.6  145.95
  4724.1  147.39  4729.9  145.68  4788.1  143.82  4919.4  142.35  4935.5  141.88
  4972.3  136.56  4975.7  133.52  4976.2  133.02  4994.8  133.52  4999.5  135.29
  5030.5  135.35  5057.7  141.86  5131.4  145.08  5335.9  146.31  5480.5  149.49
  5845.1  146.89  6013.9  147.42  6314.7  149.62  6528.8  153.33  6699.9  156.71
#Mann=8,-1,0
  4246.2    0.12       0  4420.7    0.05       0  4708.2    0.12       0
  4711.6    0.03       0  4919.4    0.12       0  4975.7    0.05       0
  4994.8    0.12       0  6528.8    0.05       0
Bank Sta=4975.7,4994.8
Exp/Cntr=0.3,0.1

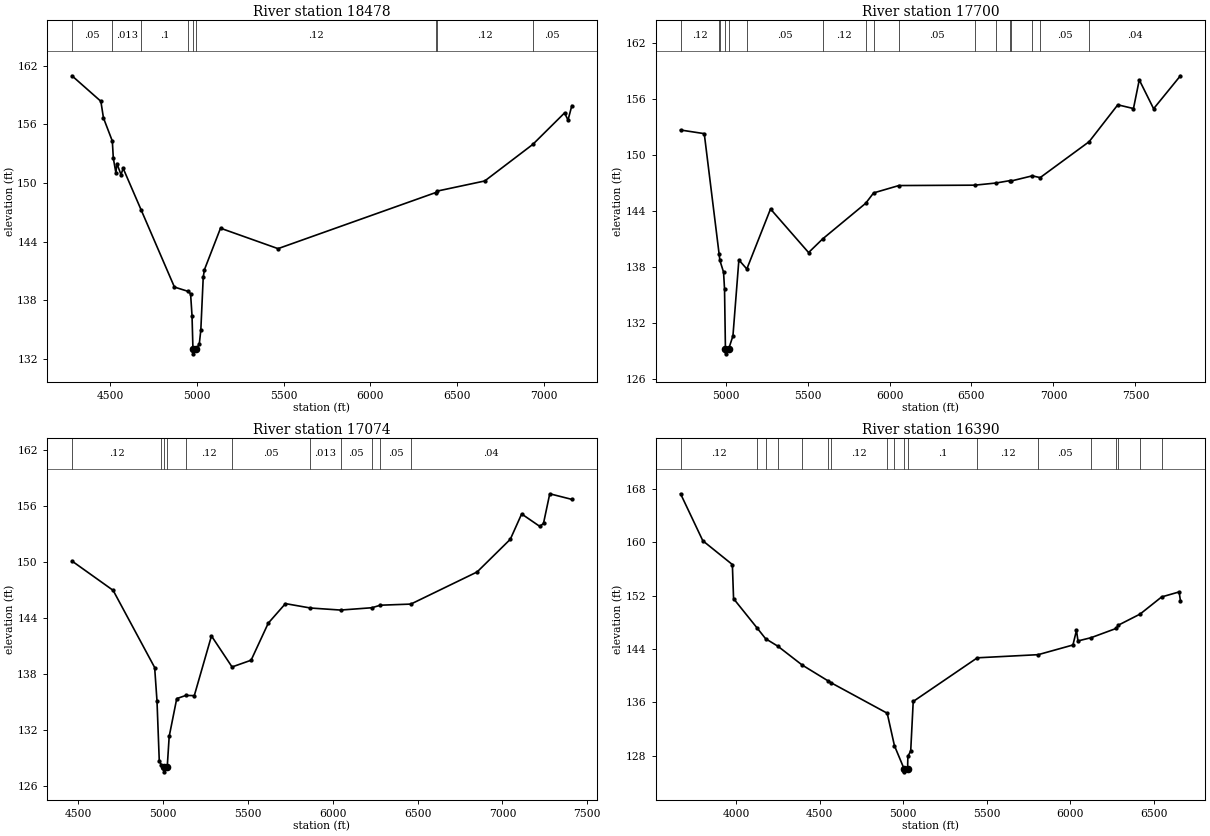
Type RM Length L Ch R = 1,18478,778,778,778
BEGIN DESCRIPTION:
LGII2966
END DESCRIPTION:
XS GIS Cut Line= 4
      2563917.37     13552175.60      2562864.86     13552902.59
      2562406.02     13553409.58      2562413.66     13554326.97
#Sta/Elev= 30
  4279.9  160.95  4446.4  158.34  4461.3  156.64  4512.5  154.27  4518.1  152.53
  4533.0  151.02  4539.0  151.97  4562.3  150.84  4574.9  151.48  4679.2  147.20
  4870.3  139.34  4950.7  138.89  4963.4  138.65  4971.7  136.40  4977.0  133.01
  4977.5  132.51  4996.1  133.01  5013.6  133.52  5022.4  134.95  5036.3  140.36
  5043.3  141.12  5135.9  145.36  5467.2  143.27  6376.5  149.01  6385.6  149.16
  6658.3  150.19  6935.3  153.93  7118.3  157.15  7138.3  156.42  7160.3  157.89
#Mann=9,-1,0
  4279.9    0.05       0  4512.5   0.013       0  4679.2     0.1       0
  4950.7    0.12       0  4977.0    0.05       0  4996.1    0.12       0
  6376.5   0.013       0  6385.6    0.12       0  6935.3    0.05       0
Bank Sta=4977,4996.1
Exp/Cntr=0.3,0.1

Type RM Length L Ch R = 1,17700,626,626,626
BEGIN DESCRIPTION:
LGII2965
END DESCRIPTION:
XS GIS Cut Line= 3
      2563244.60     13551763.29      2562181.26     13552457.71
      2560648.80     13553363.01
#Sta/Elev= 30
  4724.9  152.67  4869.5  152.28  4959.9  139.41  4964.8  138.70  4987.2  137.44
  4993.2  135.63  4998.7  129.19  4999.2  128.69  5017.9  129.19  5044.5  130.61
  5080.7  138.75  5129.2  137.78  5273.8  144.21  5506.0  139.54  5591.7  141.00
  5854.5  144.82  5902.7  145.93  6057.0  146.72  6519.7  146.76  6649.1  146.99
  6732.2  147.24  6742.6  147.21  6870.9  147.76  6919.0  147.57  7217.9  151.42
  7392.7  155.37  7488.3  154.97  7523.7  158.04  7611.2  154.95  7774.8  158.48
#Mann=17,-1,0
  4724.9    0.12       0  4959.9    0.05       0  4964.8     0.1       0
  4998.7    0.05       0  5017.9     0.1       0  5129.2    0.05       0
  5591.7    0.12       0  5854.5    0.05       0  5902.7    0.12       0
  6057.0    0.05       0  6519.7    0.12       0  6649.1    0.05       0
  6732.2    0.04       0  6742.6    0.05       0  6870.9    0.04       0
  6919.0    0.05       0  7217.9    0.04       0
Bank Sta=4998.7,5017.9
Exp/Cntr=0.3,0.1

Type RM Length L Ch R = 1,17074,684,684,684
BEGIN DESCRIPTION:
LGII2964
END DESCRIPTION:
XS GIS Cut Line= 4
      2563027.66     13551633.08      2562691.25     13551437.75
      2561888.95     13551915.83      2560502.33     13552759.76
#Sta/Elev= 30
  4462.6  150.09  4705.2  146.95  4949.9  138.69  4963.7  135.12  4977.2  128.67
  4989.3  128.27  5004.4  128.02  5004.9  127.52  5024.0  128.02  5035.6  131.31
  5080.1  135.36  5133.7  135.70  5183.6  135.68  5284.8  142.07  5406.1  138.75
  5518.4  139.47  5619.6  143.44  5720.8  145.53  5868.2  145.06  6045.8  144.84
  6230.7  145.09  6280.1  145.36  6460.0  145.48  6850.5  148.92  7046.2  152.42
  7113.0  155.13  7220.6  153.79  7241.9  154.13  7278.7  157.29  7408.8  156.69
#Mann=11,-1,0
  4462.6    0.12       0  4989.3     0.1       0  5004.4    0.05       0
  5024.0     0.1       0  5133.7    0.12       0  5406.1    0.05       0
  5868.2   0.013       0  6045.8    0.05       0  6230.7    0.12       0
  6280.1    0.05       0  6460.0    0.04       0
Bank Sta=5004.4,5024
Exp/Cntr=0.3,0.1

Type RM Length L Ch R = 1,16390,1030,1030,1030
BEGIN DESCRIPTION:
LGII2963
END DESCRIPTION:
XS GIS Cut Line= 4
      2562994.67     13550336.25      2562289.77     13551057.97
      2561465.12     13551459.45      2560575.35     13552045.39
#Sta/Elev= 30
  3667.8  167.25  3801.1  160.21  3977.8  156.65  3985.0  151.54  4126.4  147.13
  4176.8  145.54  4250.0  144.42  4394.9  141.61  4548.9  139.25  4571.0  138.91
  4904.5  134.38  4947.8  129.51  5004.7  126.10  5005.2  125.60  5026.5  126.10
  5028.1  127.91  5045.1  128.73  5060.1  136.14  5443.6  142.68  5807.8  143.15
  6016.0  144.60  6037.1  146.79  6046.2  145.21  6124.0  145.69  6275.7  147.09
  6287.6  147.57  6417.8  149.23  6546.9  151.80  6651.5  152.55  6659.2  151.24
#Mann=18,-1,0
  3667.8    0.12       0  4126.4    0.05       0  4176.8    0.12       0
  4250.0    0.05       0  4394.9    0.12       0  4548.9    0.05       0
  4571.0    0.12       0  4904.5    0.03       0  4947.8     0.1       0
  5004.7    0.05       0  5026.5     0.1       0  5443.6    0.12       0
  5807.8    0.05       0  6124.0   0.013       0  6275.7    0.04       0
  6287.6   0.013       0  6417.8    0.05       0  6546.9    0.04       0
Bank Sta=5004.7,5026.5
Exp/Cntr=0.3,0.1