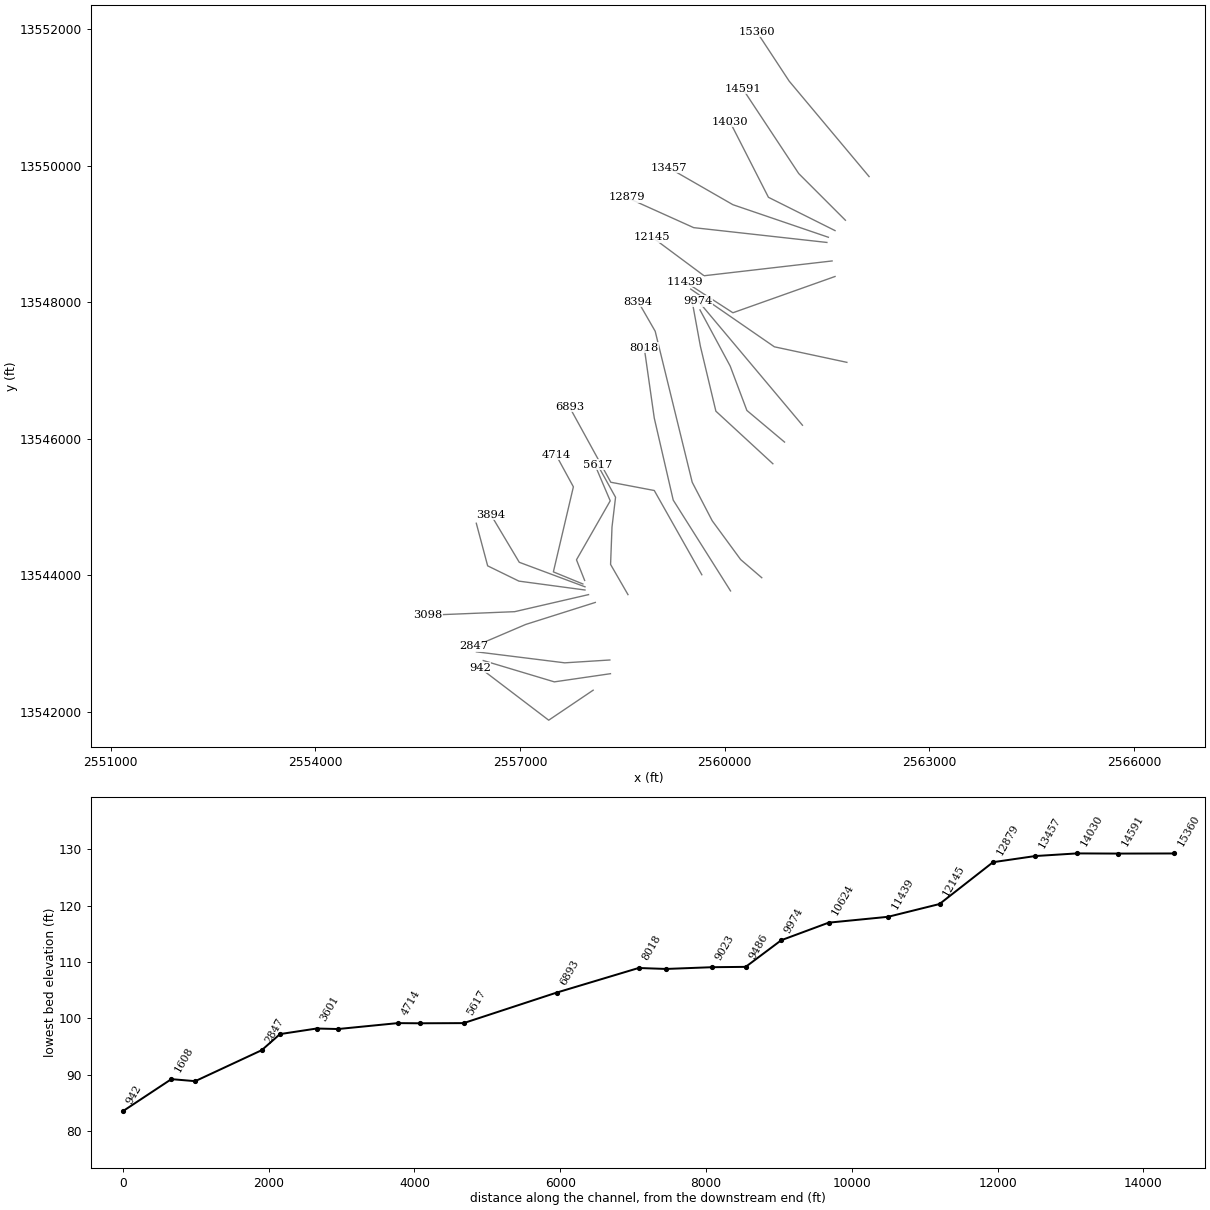
HEC-RAS study PRICE CREEK.prj: PRICE CREEK Base Level Engineering

--- PRICE CREEK.g01 (geometry) --- (continued)

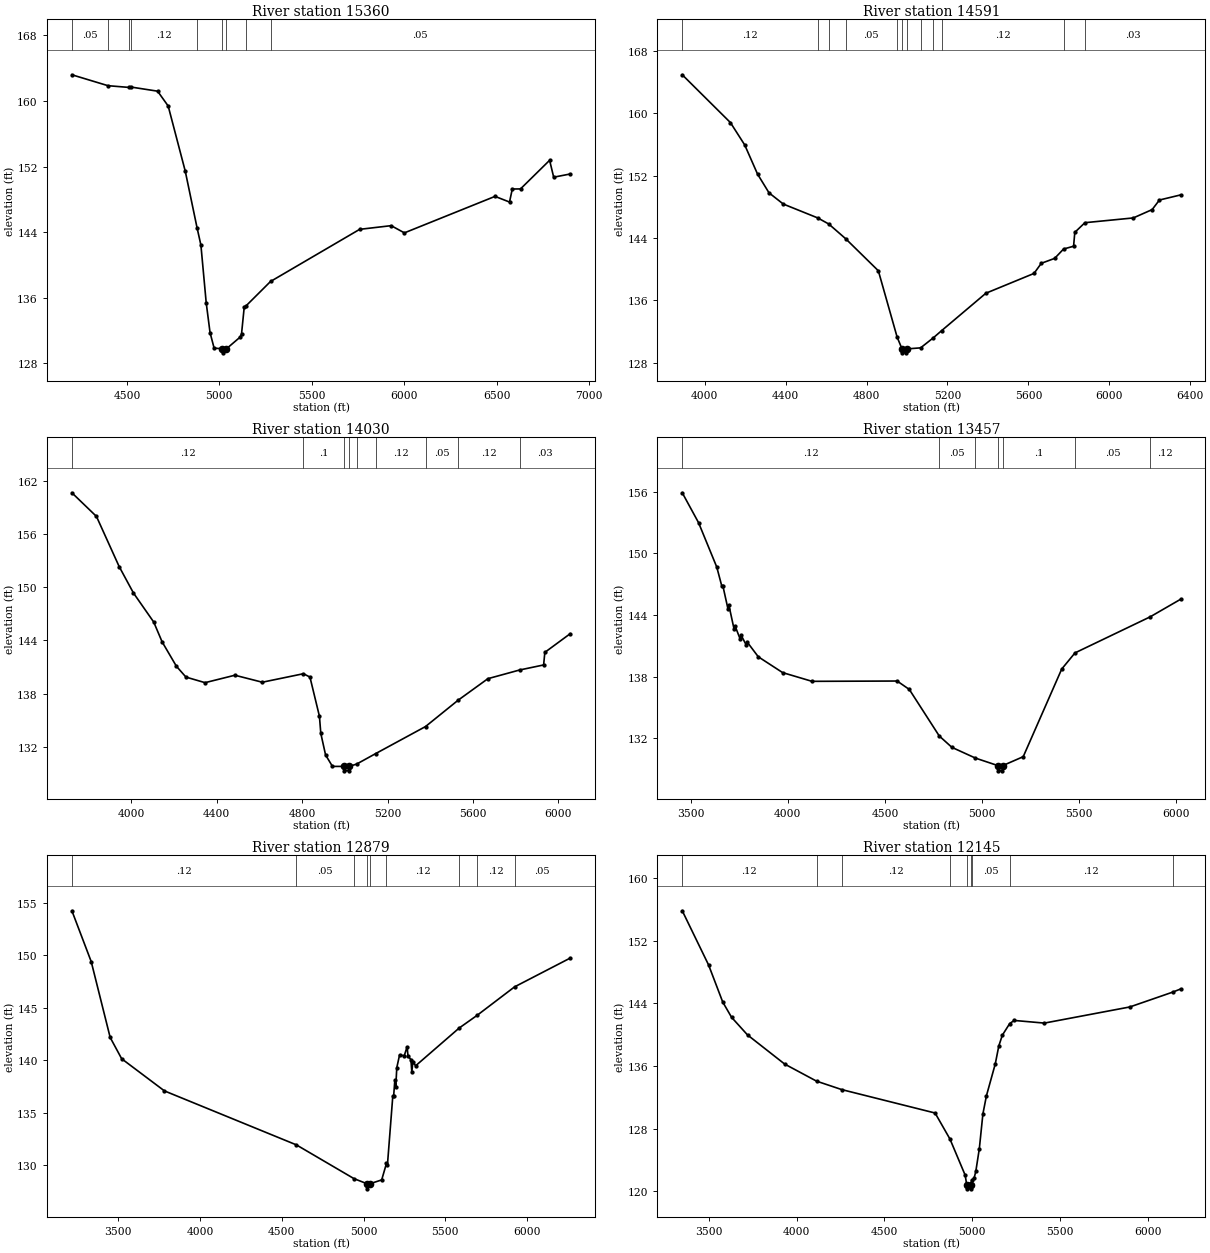
Type RM Length L Ch R = 1,15360,769,769,769
BEGIN DESCRIPTION:
LGII2962
END DESCRIPTION:
XS GIS Cut Line= 3
      2562116.14     13549842.72      2560944.29     13551242.44
      2560466.88     13551969.39
#Sta/Elev= 30
  4202.3  163.19  4397.4  161.86  4510.5  161.65  4523.1  161.69  4665.9  161.19
  4723.2  159.38  4815.6  151.43  4879.3  144.54  4900.2  142.42  4928.8  135.40
  4949.6  131.75  4971.7  129.85  5016.7  129.78  5017.2  129.28  5038.6  129.78
  5113.5  131.22  5120.1  131.62  5134.4  134.83  5144.4  135.01  5276.7  137.98
  5758.9  144.34  5929.4  144.79  6000.9  143.91  6491.2  148.36  6569.6  147.67
  6584.6  149.26  6629.0  149.27  6786.5  152.76  6808.5  150.70  6897.5  151.09
#Mann=9,-1,0
  4202.3    0.05       0  4397.4    0.12       0  4510.5    0.05       0
  4523.1    0.12       0  4879.3     0.1       0  5016.7    0.05       0
  5038.6     0.1       0  5144.4    0.12       0  5276.7    0.05       0
Bank Sta=5016.7,5038.6
Exp/Cntr=0.3,0.1

Type RM Length L Ch R = 1,14591,561,561,561
BEGIN DESCRIPTION:
LGII2961
END DESCRIPTION:
XS GIS Cut Line= 3
      2561768.92     13549202.52      2561085.34     13549886.10
      2560260.71     13551133.91
#Sta/Elev= 30
  3889.4  164.94  4127.3  158.81  4198.0  155.94  4261.6  152.19  4318.2  149.79
  4388.9  148.35  4559.2  146.57  4613.5  145.79  4696.3  143.92  4858.5  139.79
  4951.4  131.27  4975.6  129.76  4976.1  129.26  4997.2  129.26  4997.7  129.76
  5067.4  129.90  5130.8  131.20  5170.9  132.10  5390.0  136.91  5627.8  139.45
  5663.9  140.75  5729.8  141.38  5773.8  142.58  5823.4  142.94  5829.4  144.72
  5879.4  145.96  6118.3  146.57  6211.6  147.64  6247.7  148.87  6351.8  149.52
#Mann=12,-1,0
  3889.4    0.12       0  4559.2    0.05       0  4613.5    0.12       0
  4696.3    0.05       0  4951.4     0.1       0  4975.6    0.05       0
  4997.7     0.1       0  5067.4    0.12       0  5130.8    0.05       0
  5170.9    0.12       0  5773.8    0.05       0  5879.4    0.03       0
Bank Sta=4975.6,4997.7
Exp/Cntr=0.3,0.1

Type RM Length L Ch R = 1,14030,573,573,573
BEGIN DESCRIPTION:
LGII2959
END DESCRIPTION:
XS GIS Cut Line= 3
      2561617.07     13549050.57      2560640.47     13549538.88
      2560076.22     13550645.67
#Sta/Elev= 30
  3721.3  160.67  3836.4  158.00  3942.6  152.35  4009.7  149.36  4104.7  146.08
  4143.9  143.85  4211.0  141.09  4255.7  139.87  4345.1  139.24  4484.9  140.08
  4613.4  139.29  4806.1  140.25  4836.6  139.87  4881.0  135.45  4887.4  133.52
  4909.8  131.08  4942.1  129.79  4997.7  129.79  4998.2  129.29  5019.4  129.29
  5019.9  129.79  5055.1  130.05  5144.0  131.23  5378.1  134.29  5530.7  137.26
  5670.2  139.69  5818.7  140.67  5931.3  141.24  5937.0  142.66  6055.5  144.76
#Mann=9,-1,0
  3721.3    0.12       0  4806.1     0.1       0  4997.7    0.05       0
  5019.9     0.1       0  5055.1    0.05       0  5144.0    0.12       0
  5378.1    0.05       0  5530.7    0.12       0  5818.7    0.03       0
Bank Sta=4997.7,5019.9
Exp/Cntr=0.3,0.1

Type RM Length L Ch R = 1,13457,578,578,578
BEGIN DESCRIPTION:
LGII2960
END DESCRIPTION:
XS GIS Cut Line= 3
      2561519.38     13548952.94      2560119.63     13549430.37
      2559175.65     13549972.89
#Sta/Elev= 30
  3455.8  155.91  3539.7  153.00  3633.7  148.67  3659.7  146.81  3665.0  146.85
  3691.1  144.62  3696.3  144.94  3722.4  142.66  3727.7  142.95  3753.7  141.68
  3759.0  142.04  3785.1  141.09  3790.3  141.37  3847.7  139.93  3973.1  138.39
  4124.5  137.54  4563.2  137.57  4625.9  136.75  4780.1  132.22  4845.2  131.11
  4967.0  130.06  5084.1  129.32  5084.6  128.82  5105.8  128.82  5106.3  129.32
  5213.0  130.20  5411.4  138.74  5479.7  140.31  5866.9  143.82  6023.5  145.53
#Mann=7,-1,0
  3455.8    0.12       0  4780.1    0.05       0  4967.0     0.1       0
  5084.1    0.05       0  5106.3     0.1       0  5479.7    0.05       0
  5866.9    0.12       0
Bank Sta=5084.1,5106.3
Exp/Cntr=0.3,0.1

Type RM Length L Ch R = 1,12879,734,734,734
BEGIN DESCRIPTION:
LGII2958
END DESCRIPTION:
XS GIS Cut Line= 3
      2561497.67     13548876.98      2559544.55     13549094.00
      2558558.54     13549538.24
#Sta/Elev= 30
  3216.4  154.22  3334.5  149.38  3450.5  142.15  3520.9  140.12  3782.3  137.06
  4588.9  131.92  4941.6  128.70  5018.8  128.23  5019.3  127.73  5041.6  128.23
  5110.7  128.58  5140.1  130.16  5145.6  129.96  5178.8  136.60  5184.0  136.60
  5191.3  138.12  5196.8  137.42  5203.0  139.27  5220.0  140.48  5248.6  140.41
  5266.2  141.26  5271.7  140.37  5289.4  140.05  5294.9  138.87  5301.7  139.85
  5318.0  139.45  5584.6  143.05  5693.5  144.25  5923.1  146.97  6263.0  149.71
#Mann=9,-1,0
  3216.4    0.12       0  4588.9    0.05       0  4941.6     0.1       0
  5018.8    0.05       0  5041.6     0.1       0  5140.1    0.12       0
  5584.6    0.05       0  5693.5    0.12       0  5923.1    0.05       0
Bank Sta=5018.8,5041.6
Exp/Cntr=0.3,0.1

Type RM Length L Ch R = 1,12145,706,706,706
BEGIN DESCRIPTION:
LGII2957
END DESCRIPTION:
XS GIS Cut Line= 3
      2561573.64     13548605.72      2559696.46     13548388.70
      2558938.41     13548951.82
#Sta/Elev= 30
  3350.2  155.80  3499.8  148.89  3580.4  144.15  3630.7  142.20  3721.3  139.95
  3932.7  136.23  4113.9  134.05  4257.4  132.97  4788.3  129.98  4872.8  126.66
  4959.5  122.04  4968.2  120.80  4968.7  120.30  4990.6  120.30  4991.1  120.80
  4996.7  121.42  5009.8  121.63  5019.9  122.53  5040.0  125.44  5060.2  129.86
  5080.3  132.18  5130.6  136.25  5150.8  138.55  5170.9  139.92  5212.7  141.40
  5238.1  141.80  5409.8  141.46  5895.9  143.52  6139.2  145.41  6184.2  145.81
#Mann=9,-1,0
  3350.2    0.12       0  4113.9    0.05       0  4257.4    0.12       0
  4872.8     0.1       0  4968.2    0.05       0  4991.1     0.1       0
  4996.7    0.05       0  5212.7    0.12       0  6139.2    0.05       0
Bank Sta=4968.2,4991.1
Exp/Cntr=0.3,0.1

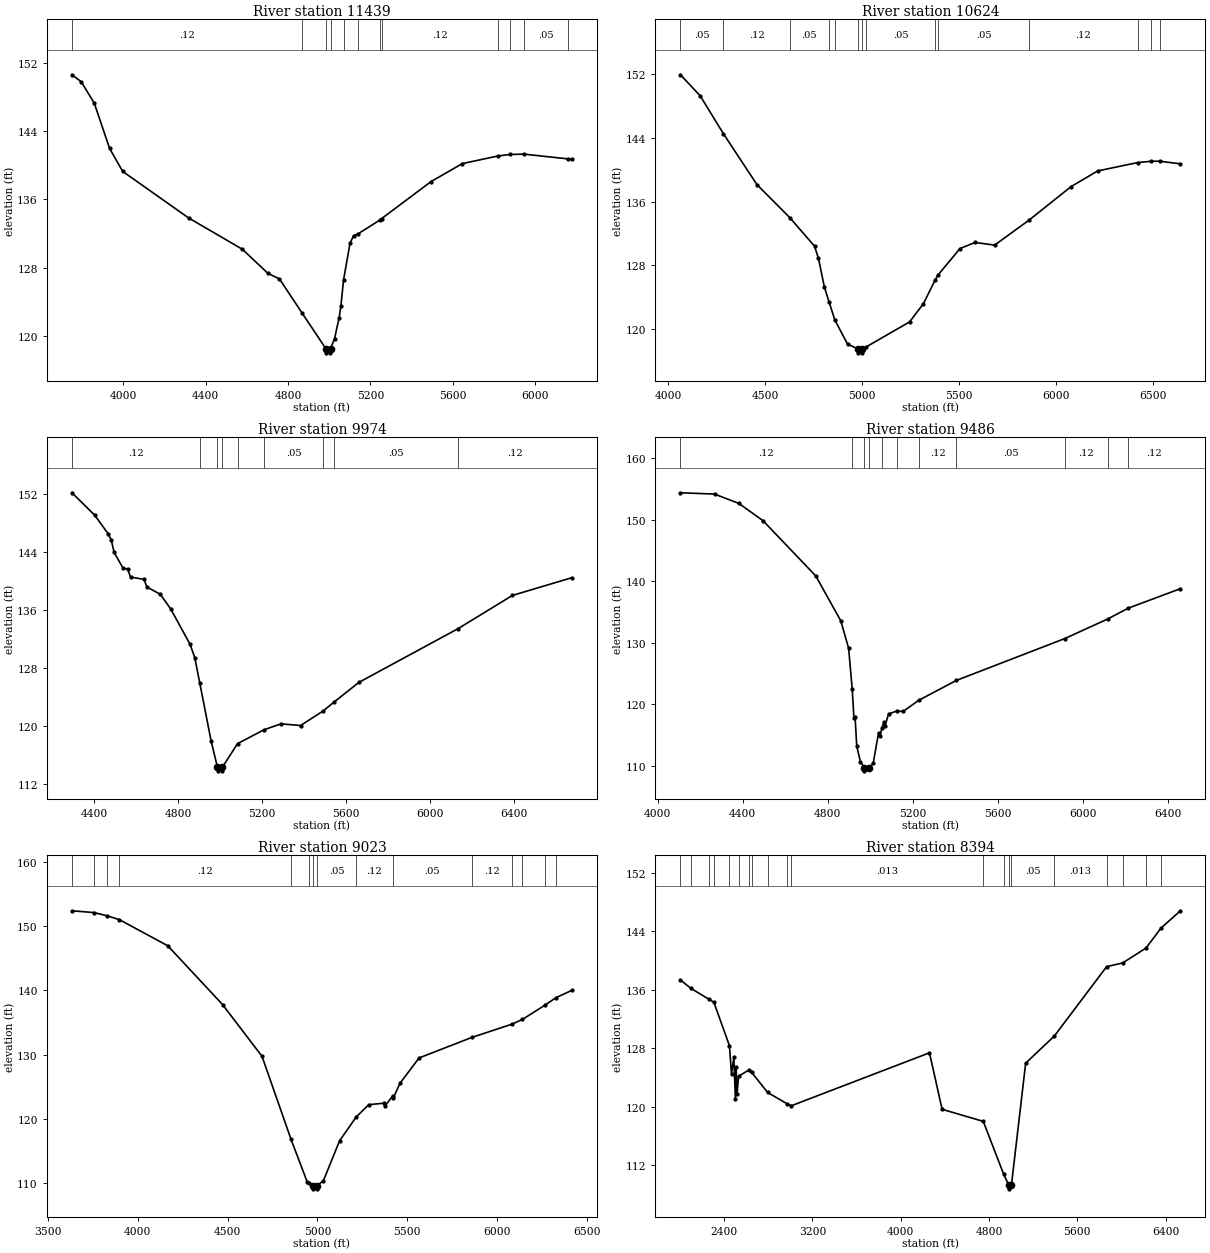
Type RM Length L Ch R = 1,11439,815,815,815
BEGIN DESCRIPTION:
LGII2956
END DESCRIPTION:
XS GIS Cut Line= 3
      2561617.03     13548377.85      2560119.63     13547846.17
      2559415.78     13548300.97
#Sta/Elev= 30
  3751.4  150.58  3796.0  149.77  3859.4  147.27  3934.0  141.96  3997.6  139.27
  4317.1  133.83  4578.9  130.15  4702.3  127.34  4758.7  126.68  4867.9  122.71
  4983.5  118.53  4984.0  118.03  5006.0  118.03  5006.5  118.53  5025.9  119.68
  5048.2  122.14  5056.7  123.47  5069.8  126.57  5101.2  130.86  5118.4  131.74
  5141.6  131.98  5246.4  133.58  5254.3  133.74  5494.8  138.08  5645.9  140.18
  5818.6  141.07  5876.9  141.25  5945.6  141.29  6157.1  140.74  6178.4  140.67
#Mann=12,-1,0
  3751.4    0.12       0  4867.9     0.1       0  4983.5    0.05       0
  5006.5     0.1       0  5069.8    0.05       0  5141.6    0.12       0
  5246.4    0.05       0  5254.3    0.12       0  5818.6    0.05       0
  5876.9    0.12       0  5945.6    0.05       0  6157.1    0.12       0
Bank Sta=4983.5,5006.5
Exp/Cntr=0.3,0.1

Type RM Length L Ch R = 1,10624,650,650,650
BEGIN DESCRIPTION:
LGII2955
END DESCRIPTION:
XS GIS Cut Line= 3
      2561790.63     13547119.17      2560727.27     13547347.04
      2559501.12     13548193.41
#Sta/Elev= 30
  4064.3  151.96  4165.5  149.33  4285.4  144.56  4458.7  138.14  4627.2  134.01
  4755.3  130.41  4775.7  128.88  4806.4  125.24  4830.1  123.42  4859.8  121.14
  4925.7  118.08  4978.8  117.49  4979.3  116.99  5001.7  116.99  5002.2  117.49
  5022.1  117.74  5245.4  120.88  5317.0  123.18  5376.0  126.10  5393.1  126.81
  5505.0  130.10  5582.7  130.87  5684.1  130.54  5860.3  133.66  6078.3  137.90
  6215.5  139.87  6421.3  140.92  6490.4  141.08  6534.5  141.09  6641.7  140.76
#Mann=14,-1,0
  4064.3    0.05       0  4285.4    0.12       0  4627.2    0.05       0
  4830.1    0.03       0  4859.8     0.1       0  4978.8    0.05       0
  5002.2     0.1       0  5022.1    0.05       0  5376.0    0.12       0
  5393.1    0.05       0  5860.3    0.12       0  6421.3    0.05       0
  6490.4    0.12       0  6534.5    0.05       0
Bank Sta=4978.8,5002.2
Exp/Cntr=0.3,0.1

Type RM Length L Ch R = 1,9974,488,488,488
BEGIN DESCRIPTION:
LGII2954
END DESCRIPTION:
XS GIS Cut Line= 2
      2561139.57     13546196.89      2559609.80     13548019.60
#Sta/Elev= 30
  4295.4  152.22  4403.8  149.12  4467.5  146.57  4481.8  145.76  4496.1  144.01
  4539.0  141.79  4559.9  141.72  4574.2  140.60  4637.9  140.28  4652.2  139.23
  4716.0  138.21  4765.4  136.20  4857.8  131.30  4879.9  129.47  4903.3  126.03
  4957.9  117.96  4987.8  114.37  4988.3  113.87  5010.9  113.87  5011.4  114.37
  5083.4  117.62  5208.9  119.53  5290.3  120.35  5383.3  120.12  5490.0  122.11
  5544.0  123.38  5660.4  126.06  6132.5  133.47  6391.5  138.06  6675.0  140.51
#Mann=9,-1,0
  4295.4    0.12       0  4903.3     0.1       0  4987.8    0.05       0
  5011.4     0.1       0  5083.4    0.12       0  5208.9    0.05       0
  5490.0    0.12       0  5544.0    0.05       0  6132.5    0.12       0
Bank Sta=4987.8,5011.4
Exp/Cntr=0.3,0.1

Type RM Length L Ch R = 1,9486,463,463,463
BEGIN DESCRIPTION:
Mapping XS b3d68512
END DESCRIPTION:
XS GIS Cut Line= 4
      2560876.47     13545950.34      2560324.39     13546413.88
      2560079.60     13547064.93      2559636.87     13547887.87
#Sta/Elev= 30
  4107.0  154.41  4267.1  154.20  4381.5  152.68  4494.7  149.88  4743.1  140.88
  4861.1  133.55  4897.8  129.07  4914.7  122.40  4922.7  117.72  4928.1  117.89
  4935.9  113.13  4953.0  110.66  4971.4  109.64  4971.9  109.14  4995.0  109.64
  5013.4  110.39  5038.3  115.31  5043.7  114.75  5054.9  116.13  5063.2  117.10
  5068.6  116.45  5085.5  118.40  5123.1  118.87  5153.9  118.81  5227.3  120.62
  5403.7  123.85  5913.0  130.66  6115.3  133.85  6211.6  135.61  6457.9  138.80
#Mann=11,-1,0
  4107.0    0.12       0  4914.7    0.05       0  4971.4    0.05       0
  4995.0    0.05       0  5054.9     0.1       0  5123.1    0.05       0
  5227.3    0.12       0  5403.7    0.05       0  5913.0    0.12       0
  6115.3    0.05       0  6211.6    0.12       0
Bank Sta=4971.4,4995
Exp/Cntr=0.3,0.1

Type RM Length L Ch R = 1,9023,629,629,629
BEGIN DESCRIPTION:
LGII2953
END DESCRIPTION:
XS GIS Cut Line= 4
      2560705.54     13545632.65      2559870.07     13546403.03
      2559642.20     13547357.89      2559522.84     13548008.93
#Sta/Elev= 30
  3635.0  152.39  3757.3  152.11  3828.1  151.63  3898.5  151.01  4167.6  146.94
  4472.1  137.79  4691.6  129.73  4853.4  116.77  4943.6  110.11  4954.1  110.00
  4973.8  109.58  4974.3  109.08  4997.0  109.08  4997.5  109.58  5032.9  110.34
  5123.0  116.56  5215.9  120.29  5285.5  122.19  5369.7  122.42  5374.9  121.95
  5417.7  123.54  5422.1  123.24  5459.1  125.53  5565.1  129.47  5859.0  132.67
  6080.7  134.72  6139.3  135.46  6265.8  137.70  6326.0  138.85  6415.0  140.00
#Mann=15,-1,0
  3635.0    0.05       0  3757.3   0.013       0  3828.1    0.05       0
  3898.5    0.12       0  4853.4     0.1       0  4954.1    0.05       0
  4973.8    0.05       0  4997.5    0.05       0  5215.9    0.12       0
  5417.7    0.05       0  5859.0    0.12       0  6080.7    0.05       0
  6139.3    0.12       0  6265.8    0.05       0  6326.0    0.12       0
Bank Sta=4973.8,4997.5
Exp/Cntr=0.3,0.1

Type RM Length L Ch R = 1,8394,376,376,376
BEGIN DESCRIPTION:
LGII2951
END DESCRIPTION:
XS GIS Cut Line= 6
      2560542.80     13543961.63      2560233.41     13544227.49
      2559815.81     13544797.12      2559522.84     13545361.36
      2558980.31     13547574.90      2558730.77     13548008.89
#Sta/Elev= 30
  2003.6  137.34  2099.4  136.18  2263.4  134.69  2306.1  134.30  2447.3  128.36
  2466.1  124.48  2487.0  126.74  2501.6  121.05  2507.8  125.42  2516.3  121.70
  2529.9  124.17  2620.2  125.00  2649.7  124.69  2793.1  121.96  2966.0  120.44
  3009.0  120.14  4260.5  127.38  4374.8  119.65  4748.0  118.00  4933.1  110.76
  4979.3  109.27  4979.8  108.77  5003.2  109.27  5132.1  125.96  5393.1  129.69
  5865.5  139.16  6011.8  139.68  6222.2  141.70  6359.3  144.45  6534.8  146.81
#Mann=20,-1,0
  2003.6    0.12       0  2099.4   0.013       0  2263.4    0.12       0
  2306.1   0.013       0  2447.3    0.05       0  2529.9   0.013       0
  2620.2    0.05       0  2649.7   0.013       0  2793.1   0.013       0
  2966.0    0.05       0  3009.0   0.013       0  4748.0   0.075       0
  4933.1    0.05       0  4979.3    0.05       0  5003.2    0.05       0
  5393.1   0.013       0  5865.5    0.05       0  6011.8   0.013       0
  6222.2    0.05       0  6359.3   0.013       0
Bank Sta=4979.3,5003.2
Exp/Cntr=0.3,0.1

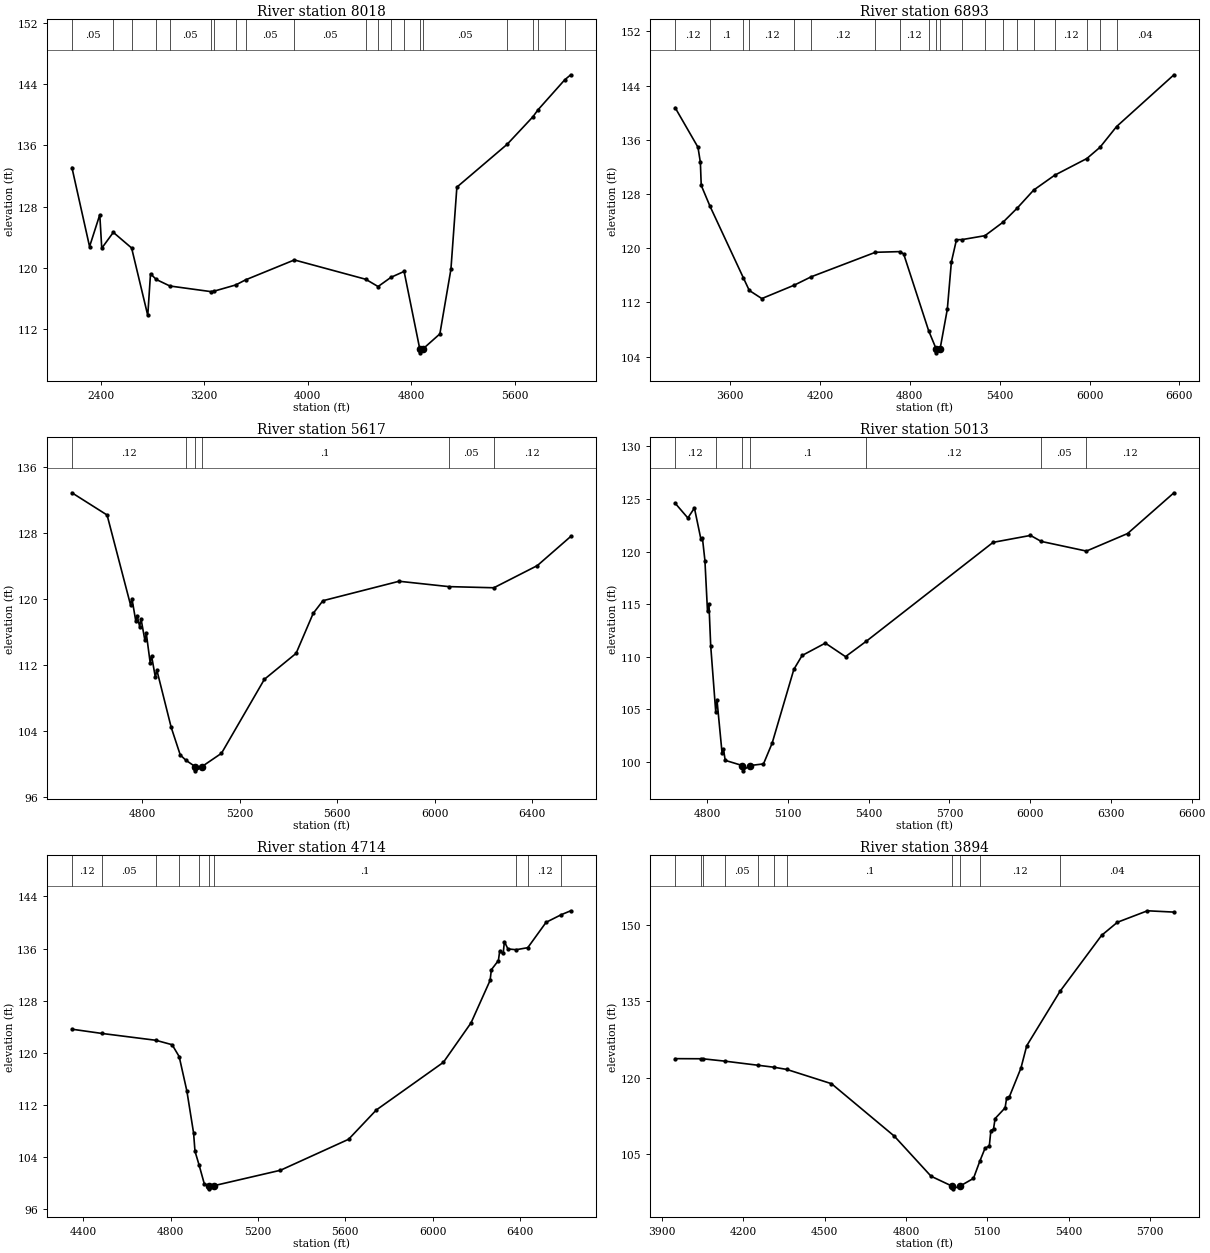
Type RM Length L Ch R = 1,8018,1125,1125,1125
BEGIN DESCRIPTION:
Mapping XS 95586f39
END DESCRIPTION:
XS GIS Cut Line= 4
      2560084.82     13543768.02      2559244.53     13545099.65
      2558966.75     13546301.90      2558819.19     13547335.71
#Sta/Elev= 30
  2178.0  133.12  2314.3  122.80  2393.2  126.96  2408.4  122.59  2497.7  124.66
  2639.1  122.62  2763.8  113.82  2785.0  119.26  2829.6  118.51  2934.8  117.66
  3250.9  116.93  3278.4  117.00  3443.7  117.80  3519.0  118.46  3896.0  121.06
  4447.1  118.54  4542.6  117.59  4643.1  118.80  4743.7  119.56  4864.8  109.44
  4865.3  108.94  4888.7  109.44  5019.9  111.41  5105.4  119.85  5151.3  130.56
  5540.3  136.16  5738.6  139.74  5777.5  140.64  5984.8  144.57  6030.8  145.22
#Mann=20,-1,0
  2178.0    0.05       0  2497.7    0.12       0  2639.1    0.05       0
  2829.6    0.12       0  2934.8    0.05       0  3250.9    0.12       0
  3278.4    0.05       0  3443.7    0.12       0  3519.0    0.05       0
  3896.0    0.05       0  4447.1    0.12       0  4542.6    0.05       0
  4643.1    0.12       0  4743.7    0.05       0  4864.8    0.05       0
  4888.7    0.05       0  5540.3   0.075       0  5738.6   0.013       0
  5777.5    0.04       0  5984.8    0.05       0
Bank Sta=4864.8,4888.7
Exp/Cntr=0.3,0.1

Type RM Length L Ch R = 1,6893,1276,1276,1276
BEGIN DESCRIPTION:
LGII2950
END DESCRIPTION:
XS GIS Cut Line= 4
      2559663.89     13544005.05      2558966.75     13545240.27
      2558329.27     13545361.36      2557721.61     13546468.17
#Sta/Elev= 30
  3233.5  140.76  3386.1  134.91  3402.1  132.68  3407.8  129.29  3465.7  126.24
  3688.6  115.66  3728.5  113.78  3812.2  112.58  4028.7  114.56  4142.6  115.80
  4570.4  119.41  4733.0  119.51  4759.1  119.17  4926.0  107.83  4977.6  105.07
  4978.1  104.57  5001.6  105.07  5050.6  111.01  5077.6  117.97  5111.7  121.27
  5148.1  121.28  5301.7  121.86  5422.9  123.86  5516.2  125.91  5626.9  128.59
  5766.8  130.78  5982.1  133.25  6069.9  134.91  6180.6  137.97  6563.4  145.61
#Mann=20,-1,0
  3233.5    0.12       0  3465.7     0.1       0  3688.6    0.05       0
  3728.5    0.12       0  4028.7     0.1       0  4142.6    0.12       0
  4570.4    0.05       0  4733.0    0.12       0  4926.0    0.05       0
  4977.6    0.05       0  5001.6    0.05       0  5148.1    0.05       0
  5301.7    0.12       0  5422.9    0.05       0  5516.2    0.12       0
  5626.9    0.05       0  5766.8    0.12       0  5982.1    0.12       0
  6069.9   0.013       0  6180.6    0.04       0
Bank Sta=4977.6,5001.6
Exp/Cntr=0.3,0.1

Type RM Length L Ch R = 1,5617,604,604,604
BEGIN DESCRIPTION:
Mapping XS 0dc34957
END DESCRIPTION:
XS GIS Cut Line= 5
      2558581.35     13543713.76      2558326.13     13544156.51
      2558346.96     13544703.38      2558399.04     13545140.88
      2558133.45     13545619.99
#Sta/Elev= 30
  4511.4  132.90  4655.7  130.20  4751.9  119.29  4757.7  120.05  4773.5  117.32
  4779.2  117.99  4789.3  116.64  4795.0  117.59  4810.8  114.99  4816.6  115.83
  4832.4  112.29  4838.1  113.12  4853.9  110.48  4859.7  111.40  4918.6  104.44
  4955.9  101.08  4979.2  100.43  5017.7   99.65  5018.2   99.15  5044.1   99.65
  5125.1  101.28  5301.1  110.26  5431.2  113.41  5501.3  118.26  5541.3  119.80
  5853.8  122.16  6057.9  121.51  6242.6  121.37  6420.9  124.06  6558.1  127.60
#Mann=6,-1,0
  4511.4    0.12       0  4979.2     0.1       0  5017.7    0.05       0
  5044.1     0.1       0  6057.9    0.05       0  6242.6    0.12       0
Bank Sta=5017.7,5044.1
Exp/Cntr=0.3,0.1

Type RM Length L Ch R = 1,5013,299,299,299
BEGIN DESCRIPTION:
Mapping XS 8a7c44e6
END DESCRIPTION:
XS GIS Cut Line= 4
      2557945.92     13543922.13      2557826.13     13544224.21
      2558320.92     13545088.80      2558112.58     13545578.39
#Sta/Elev= 30
  4681.0  124.60  4728.3  123.19  4752.7  124.14  4777.0  121.15  4782.4  121.30
  4791.7  119.14  4801.3  114.30  4806.7  114.98  4813.2  111.02  4831.8  104.76
  4836.4  105.90  4855.3  100.84  4860.7  101.20  4867.0  100.12  4931.2   99.62
  4931.7   99.12  4957.6   99.62  5009.3   99.78  5041.4  101.75  5122.1  108.78
  5152.8  110.10  5239.1  111.28  5314.0  109.99  5391.4  111.46  5862.3  120.87
  6001.2  121.53  6041.2  120.96  6209.0  120.04  6362.0  121.71  6534.2  125.59
#Mann=7,-1,0
  4681.0    0.12       0  4831.8     0.1       0  4931.2    0.05       0
  4957.6     0.1       0  5391.4    0.12       0  6041.2    0.05       0
  6209.0    0.12       0
Bank Sta=4931.2,4957.6
Exp/Cntr=0.3,0.1

Type RM Length L Ch R = 1,4714,820,820,820
BEGIN DESCRIPTION:
Mapping XS 8f0dff74
END DESCRIPTION:
XS GIS Cut Line= 4
      2557919.88     13543870.05      2557487.58     13544047.13
      2557780.90     13545294.26      2557524.07     13545765.84
#Sta/Elev= 30
  4347.5  123.63  4484.7  122.98  4732.2  121.93  4806.6  121.25  4838.9  119.43
  4874.1  114.16  4904.9  107.71  4911.3  104.92  4930.3  102.78  4953.7   99.95
  4973.9   99.65  4974.4   99.15  5000.4   99.65  5303.0  102.00  5615.1  106.75
  5742.3  111.25  6049.3  118.55  6176.0  124.60  6263.4  131.12  6269.1  132.75
  6301.4  134.16  6307.1  135.57  6323.2  135.24  6328.9  137.06  6345.0  135.94
  6382.7  135.82  6435.9  136.13  6519.8  140.02  6590.0  141.20  6632.8  141.79
#Mann=10,-1,0
  4347.5    0.12       0  4484.7    0.05       0  4732.2     0.1       0
  4838.9    0.05       0  4930.3     0.1       0  4973.9    0.05       0
  5000.4     0.1       0  6382.7    0.05       0  6435.9    0.12       0
  6590.0    0.05       0
Bank Sta=4973.9,5000.4
Exp/Cntr=0.3,0.1

Type RM Length L Ch R = 1,3894,293,293,293
BEGIN DESCRIPTION:
Mapping XS 5c376ad3
END DESCRIPTION:
XS GIS Cut Line= 3
      2557951.13     13543828.38      2556987.58     13544187.76
      2556570.92     13544885.66
#Sta/Elev= 30
  3947.8  123.72  4041.6  123.70  4050.3  123.69  4131.3  123.23  4253.7  122.42
  4312.6  122.03  4359.8  121.60  4525.0  118.79  4756.9  108.47  4892.5  100.58
  4971.3   98.60  4971.8   98.10  4998.0   98.60  5049.1  100.16  5072.3  103.52
  5091.9  106.11  5107.5  106.54  5113.3  109.57  5123.0  109.86  5128.9  111.93
  5165.8  114.04  5171.7  116.07  5181.4  116.20  5224.2  121.85  5245.6  126.26
  5368.1  136.94  5521.9  147.98  5580.3  150.56  5691.2  152.82  5789.0  152.56
#Mann=11,-1,0
  3947.8    0.12       0  4041.6    0.05       0  4050.3    0.12       0
  4131.3    0.05       0  4253.7    0.12       0  4312.6    0.05       0
  4359.8     0.1       0  4971.3    0.05       0  4998.0     0.1       0
  5072.3    0.12       0  5368.1    0.04       0
Bank Sta=4971.3,4998
Exp/Cntr=0.3,0.1

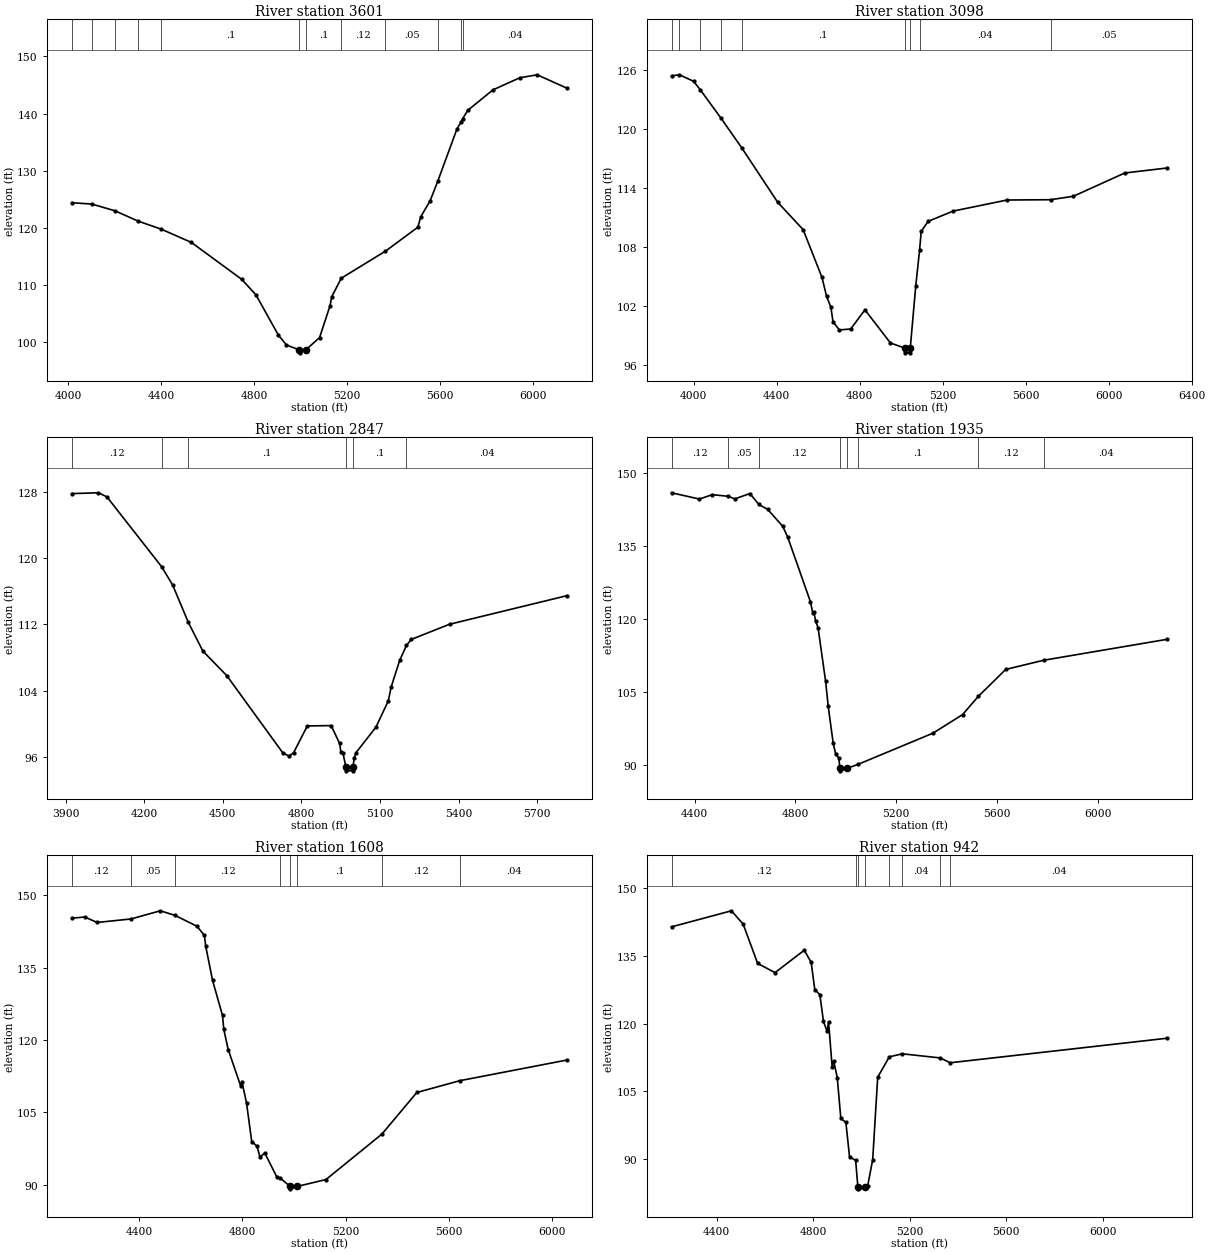
Type RM Length L Ch R = 1,3601,503,503,503
BEGIN DESCRIPTION:
Mapping XS 9c5525db
END DESCRIPTION:
XS GIS Cut Line= 4
      2557951.10     13543781.51      2556982.38     13543911.71
      2556524.04     13544135.67      2556357.45     13544760.38
#Sta/Elev= 30
  4014.4  124.43  4101.1  124.19  4200.7  123.01  4300.3  121.21  4399.9  119.80
  4529.3  117.49  4747.0  111.01  4807.6  108.31  4903.7  101.31  4938.7   99.56
  4994.8   98.69  4995.3   98.19  5021.5   98.69  5081.3  100.86  5126.3  106.42
  5133.6  107.99  5174.7  111.23  5364.9  115.96  5504.2  120.14  5517.2  121.99
  5557.3  124.77  5589.8  128.15  5672.5  137.29  5691.1  138.59  5697.7  139.11
  5718.6  140.55  5827.7  144.15  5942.8  146.26  6017.9  146.79  6148.5  144.41
#Mann=12,-1,0
  4014.4    0.12       0  4101.1    0.05       0  4200.7    0.12       0
  4300.3    0.05       0  4399.9     0.1       0  4994.8    0.05       0
  5021.5     0.1       0  5174.7    0.12       0  5364.9    0.05       0
  5589.8    0.12       0  5691.1    0.05       0  5697.7    0.04       0
Bank Sta=4994.8,5021.5
Exp/Cntr=0.3,0.1

Type RM Length L Ch R = 1,3098,251,251,251
BEGIN DESCRIPTION:
Mapping XS 9a63cc9c
END DESCRIPTION:
XS GIS Cut Line= 3
      2558003.22     13543713.80      2556919.88     13543463.80
      2555643.85     13543411.71
#Sta/Elev= 30
  3893.0  125.40  3931.3  125.51  3998.9  124.85  4031.5  123.99  4131.8  121.08
  4232.1  118.05  4404.3  112.54  4527.4  109.74  4618.1  104.88  4640.4  102.94
  4660.8  101.86  4671.1  100.38  4701.9   99.53  4756.6   99.63  4825.1  101.58
  4948.2   98.20  5015.8   97.70  5016.3   97.20  5043.2   97.20  5043.7   97.70
  5069.7  103.96  5088.3  107.62  5096.3  109.57  5129.8  110.59  5249.9  111.63
  5510.1  112.76  5719.7  112.79  5829.4  113.14  6077.2  115.51  6281.9  116.02
#Mann=9,-1,0
  3893.0    0.12       0  3931.3    0.05       0  4031.5    0.12       0
  4131.8    0.05       0  4232.1     0.1       0  5015.8    0.05       0
  5043.7     0.1       0  5088.3    0.04       0  5719.7    0.05       0
Bank Sta=5015.8,5043.7
Exp/Cntr=0.3,0.1

Type RM Length L Ch R = 1,2847,912,912,912
BEGIN DESCRIPTION:
Mapping XS 592eb537
END DESCRIPTION:
XS GIS Cut Line= 3
      2558102.12     13543599.20      2557081.33     13543276.30
      2556326.12     13542953.38
#Sta/Elev= 30
  3923.5  127.79  4025.5  127.89  4057.8  127.39  4266.5  118.97  4308.6  116.76
  4368.6  112.24  4423.9  108.79  4515.4  105.82  4728.1   96.55  4752.0   96.12
  4770.0   96.51  4822.5   99.76  4913.6   99.80  4945.9   97.64  4951.1   96.56
  4958.8   96.45  4969.5   94.84  4970.0   94.34  4996.9   94.34  4997.4   94.84
  5001.0   95.85  5008.3   96.53  5084.5   99.61  5131.5  102.77  5142.6  104.45
  5175.0  107.66  5201.1  109.47  5218.8  110.19  5365.8  112.03  5815.5  115.49
#Mann=6,-1,0
  3923.5    0.12       0  4266.5    0.05       0  4368.6     0.1       0
  4969.5    0.05       0  4997.4     0.1       0  5201.1    0.04       0
Bank Sta=4969.5,4997.4
Exp/Cntr=0.3,0.1

Type RM Length L Ch R = 1,1935,327,327,327
BEGIN DESCRIPTION:
Mapping XS 92d5fa92
END DESCRIPTION:
XS GIS Cut Line= 3
      2558315.73     13542755.46      2557654.25     13542713.80
      2556358.65     13542875.10
#Sta/Elev= 30
  4307.9  145.87  4418.9  144.58  4469.0  145.48  4532.9  145.15  4559.1  144.62
  4619.2  145.71  4654.5  143.48  4689.4  142.48  4749.5  139.01  4769.5  136.73
  4859.7  123.49  4868.4  121.28  4873.4  121.44  4879.8  119.61  4889.8  118.18
  4919.8  107.20  4929.9  102.16  4949.9   94.48  4959.9   92.25  4972.8   91.40
  4976.1   89.34  4976.6   88.84  5004.1   89.34  5048.7   90.17  5346.3   96.57
  5463.7  100.38  5526.2  104.12  5635.0  109.64  5785.3  111.52  6276.3  115.82
#Mann=8,-1,0
  4307.9    0.12       0  4532.9    0.05       0  4654.5    0.12       0
  4976.1    0.05       0  5004.1    0.12       0  5048.7     0.1       0
  5526.2    0.12       0  5785.3    0.04       0
Bank Sta=4976.1,5004.1
Exp/Cntr=0.3,0.1

Type RM Length L Ch R = 1,1608,666,666,666
BEGIN DESCRIPTION:
Mapping XS d86baefa
END DESCRIPTION:
XS GIS Cut Line= 3
      2558324.43     13542554.51      2557501.47     13542434.72
      2556459.86     13542747.20
#Sta/Elev= 30
  4139.9  145.20  4189.8  145.47  4238.0  144.33  4369.4  145.06  4482.9  146.75
  4540.4  145.78  4624.4  143.55  4653.4  141.67  4658.5  139.42  4685.0  132.34
  4723.5  125.09  4728.5  122.19  4745.6  118.02  4793.6  110.52  4798.6  111.39
  4816.4  107.02  4836.6   98.99  4856.8   98.04  4868.7   95.75  4887.1   96.62
  4933.7   91.66  4948.0   91.38  4985.2   89.70  4985.7   89.20  5013.2   89.70
  5124.2   91.13  5340.6  100.53  5475.7  109.14  5641.9  111.58  6059.0  115.88
#Mann=8,-1,0
  4139.9    0.12       0  4369.4    0.05       0  4540.4    0.12       0
  4948.0     0.1       0  4985.2    0.05       0  5013.2     0.1       0
  5340.6    0.12       0  5641.9    0.04       0
Bank Sta=4985.2,5013.2
Exp/Cntr=0.3,0.1

Type RM Length L Ch R = 1,942,0,0,0
BEGIN DESCRIPTION:
LGII2947
END DESCRIPTION:
XS GIS Cut Line= 3
      2558070.94     13542312.77      2557418.89     13541872.82
      2556410.34     13542640.21
#Sta/Elev= 30
  4213.4  141.35  4461.8  144.90  4510.3  141.94  4570.2  133.28  4642.1  131.24
  4763.4  136.19  4792.0  133.52  4807.0  127.50  4828.0  126.38  4843.0  120.47
  4858.0  118.26  4864.0  120.38  4879.0  110.45  4885.0  111.77  4900.0  108.08
  4914.9   99.04  4935.9   98.16  4950.9   90.58  4976.4   89.76  4985.3   84.00
  4985.8   83.50  5013.3   84.00  5026.1   84.17  5046.9   89.93  5067.7  108.15
  5115.7  112.64  5169.4  113.32  5326.4  112.41  5368.2  111.34  6267.3  116.76
#Mann=8,-1,0
  4213.4    0.12       0  4976.4     0.1       0  4985.3    0.05       0
  5013.3     0.1       0  5115.7    0.12       0  5169.4    0.04       0
  5326.4     0.1       0  5368.2    0.04       0
Bank Sta=4985.3,5013.3
Exp/Cntr=0.3,0.1

Chan Stop Cuts=-1