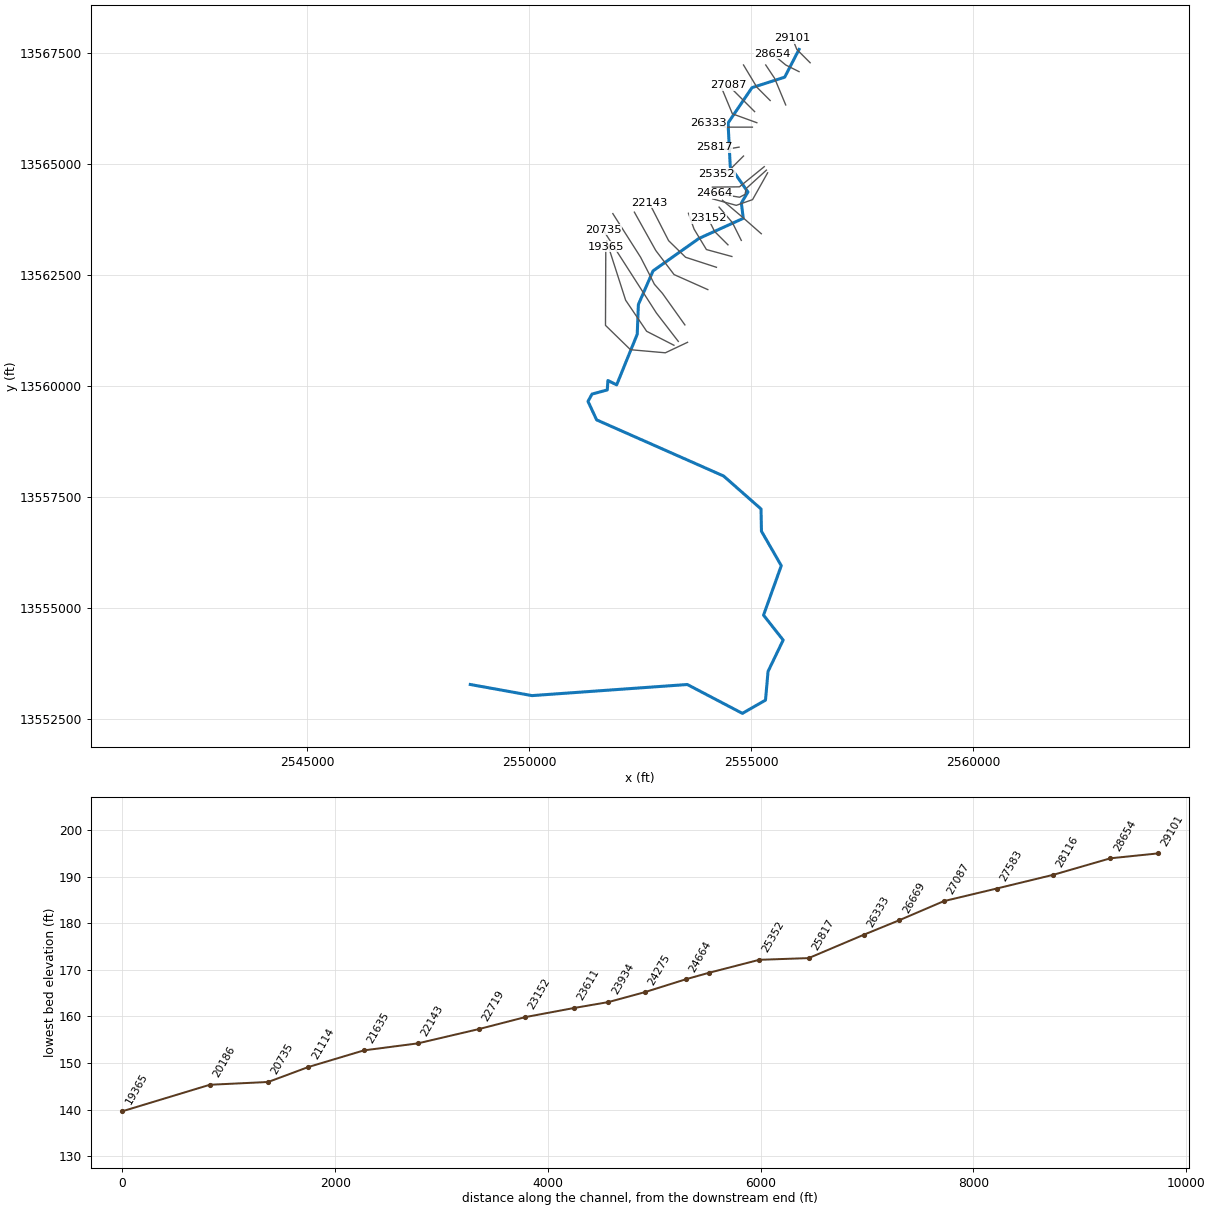
--- REEDS BRANCH.prj (project) ---

Proj Title=REEDS BRANCH Base Level Engineering
Current Plan=p01
Default Exp/Contr=0.3,0.1
English Units
Geom File=g01
Flow File=f01
Plan File=p01
Y Axis Title=Elevation
X Axis Title(PF)=Main Channel Distance
X Axis Title(XS)=Station
BEGIN DESCRIPTION:
REEDS BRANCH
END DESCRIPTION:
DSS Export Rating Curves= 0
DSS Export Rating Curve Sorted= 0
DSS Export Volume Flow Curves= 0
DXF OffsetX= 0
DXF OffsetY= 0
DXF ScaleX= 1
DXF ScaleY= 10

--- REEDS BRANCH.p01 (plan) ---

Plan Title=Multiple Run
Short Identifier=Multiple
Geom File=g01
Flow File=f01
Subcritical Flow
K Sum by GR= 0
Std Step Tol= 0.01
Critical Tol= 0.01
Num of Std Step Trials= 20
Max Error Tol= 0.3
Flow Tol Ratio= 0.001
Split Flow NTrial= 30
Split Flow Tol= 0.02
Split Flow Ratio= 0.02
Log Output Level= 0
Friction Slope Method= 1
Unsteady Friction Slope Method= 2
Unsteady Bridges Friction Slope Method= 1
Parabolic Critical Depth
Global Vel Dist=  1 , 1 , 1
Global Log Level= 0
CheckData=True
Encroach Param= -1, 0, 0, 0
BEGIN DESCRIPTION:
Multiple Run
END DESCRIPTION:

--- REEDS BRANCH.f01 (steady flow) ---

Flow Title=Multiple
Number of Profiles=7
Profile Names=10-year,25-year,50-year,1pct_min,100-year,1pct_plu,500-year
River Rch & RM= REEDS BRANCH,Reach-1,29101
     450     706     931     596    1189    2372    1915
River Rch & RM= REEDS BRANCH,Reach-1,27583
     573     911    1212     782    1560    3112    2555
River Rch & RM= REEDS BRANCH,Reach-1,23934
     835    1357    1832    1198    2390    4769    4025
River Rch & RM= REEDS BRANCH,Reach-1,21635
     924    1505    2036    1332    2659    5304    4487
Boundary for River Rch & Prof#=REEDS BRANCH,Reach-1,1
Up Type=0
Dn Type=3
Dn Slope=0.005
Boundary for River Rch & Prof#=REEDS BRANCH,Reach-1,2
Up Type=0
Dn Type=3
Dn Slope=0.005
Boundary for River Rch & Prof#=REEDS BRANCH,Reach-1,3
Up Type=0
Dn Type=3
Dn Slope=0.005
Boundary for River Rch & Prof#=REEDS BRANCH,Reach-1,4
Up Type=0
Dn Type=3
Dn Slope=0.005
Boundary for River Rch & Prof#=REEDS BRANCH,Reach-1,5
Up Type=0
Dn Type=3
Dn Slope=0.005
Boundary for River Rch & Prof#=REEDS BRANCH,Reach-1,6
Up Type=0
Dn Type=3
Dn Slope=0.005
Boundary for River Rch & Prof#=REEDS BRANCH,Reach-1,7
Up Type=0
Dn Type=3
Dn Slope=0.005

--- REEDS BRANCH.g01 (geometry) ---

Geom Title=Existing Conditions

River Reach=REEDS BRANCH,Reach-1
Reach XY= 30
      2556075.00     13567575.00      2555752.01     13566950.59
      2555015.32     13566714.25      2554477.06     13565919.14
      2554527.24     13564930.93      2554924.07     13564364.84
      2554776.05     13564114.57      2554819.70     13563771.65
      2553822.57     13563319.48      2552788.61     13562588.21
      2552458.65     13561832.18      2552432.61     13561161.61
      2551969.46     13560021.99      2551772.41     13560120.05
      2551758.78     13559908.32      2551414.62     13559814.04
      2551324.59     13559650.00      2551518.94     13559233.14
      2554377.29     13557969.15      2555219.19     13557227.29
      2555228.74     13556726.56      2555675.20     13555950.08
      2555275.55     13554835.64      2555717.47     13554274.99
      2555377.26     13553569.06      2555319.54     13552922.55
      2554799.96     13552624.51      2553559.78     13553274.51
      2550064.81     13553024.55      2548675.00     13553275.00

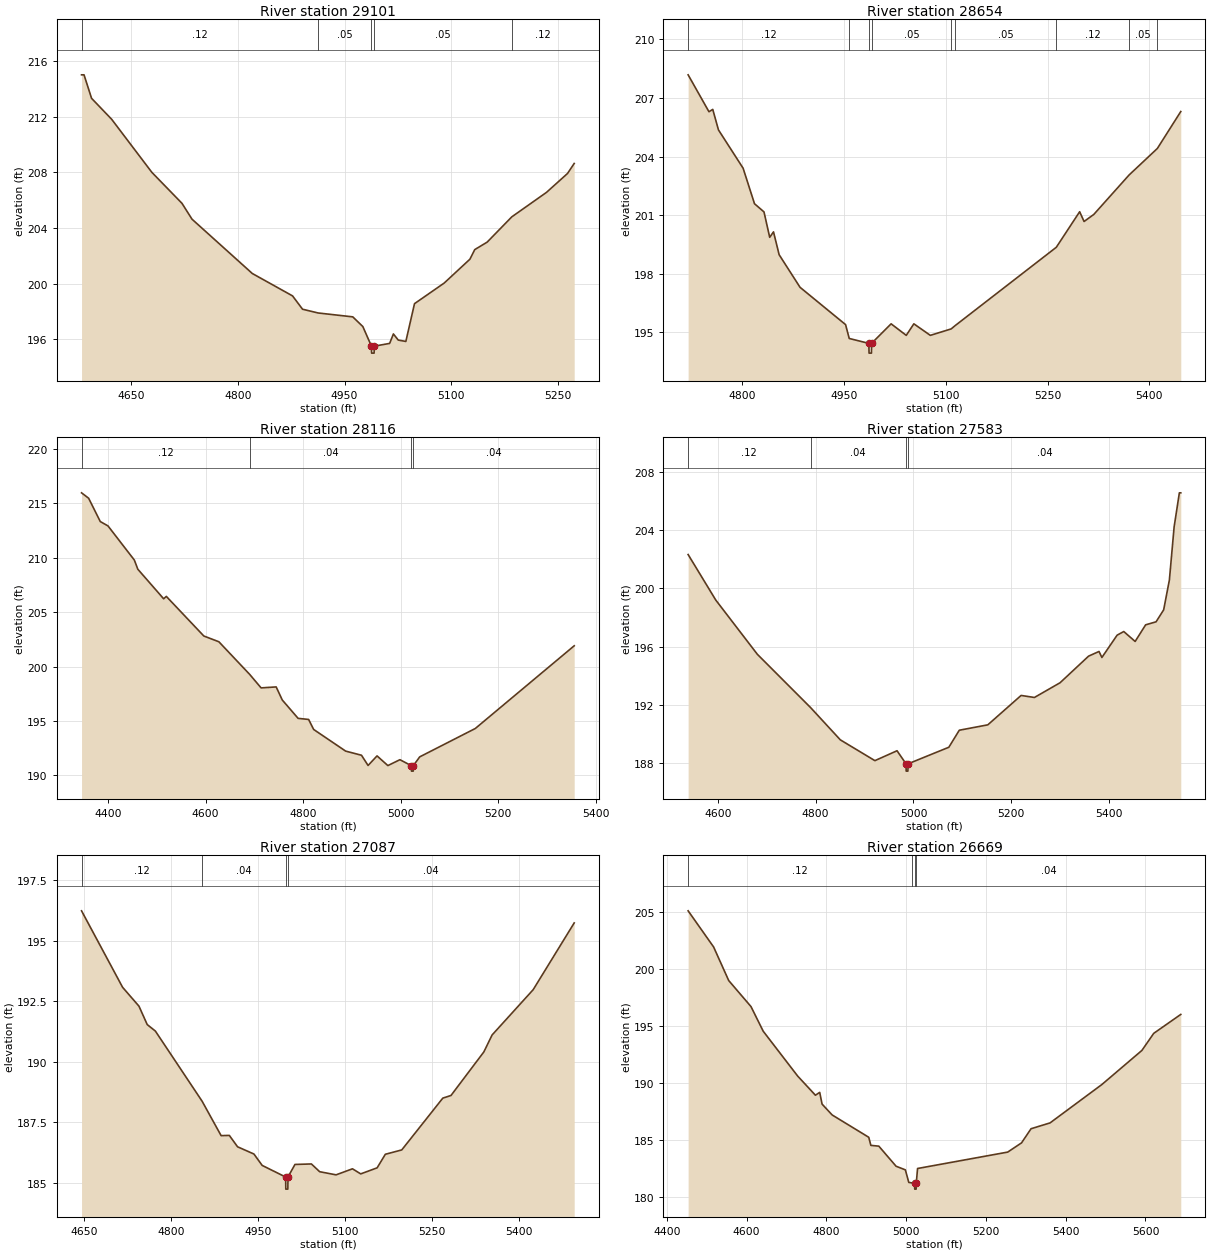
Type RM Length L Ch R = 1,29101,447,447,447
BEGIN DESCRIPTION:
REEDS BRANCH 46.0
END DESCRIPTION:
XS GIS Cut Line= 3
      2556324.98     13567275.02      2556025.00     13567575.00
      2555925.00     13567825.00
#Sta/Elev= 30
  4579.7  215.02  4583.2  215.02  4593.8  213.33  4622.1  211.82  4678.7  208.00
  4721.1  205.77  4735.2  204.63  4820.1  200.72  4876.7  199.11  4890.8  198.15
  4912.7  197.88  4961.5  197.60  4975.7  196.90  4987.8  195.49  4988.0  194.99
  4991.5  194.99  4991.8  195.49  5013.4  195.69  5018.7  196.37  5025.5  195.93
  5036.2  195.83  5048.4  198.55  5090.1  200.03  5126.4  201.75  5133.2  202.44
  5150.7  202.98  5185.4  204.80  5234.2  206.56  5263.8  207.92  5273.2  208.64
#Mann=5,-1,0
  4579.7    0.12       0  4912.7    0.05       0  4987.8    0.05       0
  4991.8    0.05       0  5185.4    0.12       0
Bank Sta=4987.8,4991.8
Exp/Cntr=0.3,0.1

Type RM Length L Ch R = 1,28654,538,538,538
BEGIN DESCRIPTION:
REEDS BRANCH 45.0
END DESCRIPTION:
XS GIS Cut Line= 3
      2556074.99     13567075.01      2555775.00     13567225.00
      2555475.01     13567475.00
#Sta/Elev= 30
  4720.3  208.19  4751.0  206.30  4756.6  206.42  4765.0  205.37  4801.3  203.41
  4818.1  201.59  4832.1  201.17  4840.5  199.87  4846.1  200.15  4854.4  198.98
  4885.2  197.31  4952.3  195.40  4957.7  194.69  4986.6  194.44  4986.9  193.94
  4990.4  193.94  4990.6  194.44  5019.4  195.44  5041.7  194.85  5052.9  195.44
  5077.2  194.85  5107.9  195.18  5113.8  195.35  5262.8  199.36  5297.2  201.18
  5303.7  200.68  5318.0  201.04  5370.0  203.06  5411.7  204.42  5446.2  206.31
#Mann=9,-1,0
  4720.3    0.12       0  4957.7    0.05       0  4986.6    0.05       0
  4990.6    0.05       0  5107.9    0.04       0  5113.8    0.05       0
  5262.8    0.12       0  5370.0    0.05       0  5411.7    0.12       0
Bank Sta=4986.6,4990.6
Exp/Cntr=0.3,0.1

Type RM Length L Ch R = 1,28116,533,533,533
BEGIN DESCRIPTION:
REEDS BRANCH 44.0
END DESCRIPTION:
XS GIS Cut Line= 3
      2555774.99     13566325.02      2555525.00     13566925.00
      2555325.02     13567224.97
#Sta/Elev= 30
  4345.7  215.97  4360.3  215.47  4384.1  213.33  4399.9  212.93  4454.0  209.79
  4461.1  208.95  4514.1  206.23  4519.6  206.45  4596.5  202.81  4627.4  202.28
  4690.6  199.28  4714.0  198.04  4744.9  198.13  4757.4  196.93  4789.9  195.24
  4811.5  195.14  4821.8  194.22  4887.4  192.23  4919.9  191.85  4933.4  190.91
  4951.8  191.79  4974.0  190.90  4998.7  191.44  5022.2  190.89  5022.5  190.39
  5026.0  190.39  5026.2  190.89  5039.3  191.70  5153.4  194.31  5356.2  201.91
#Mann=4,-1,0
  4345.7    0.12       0  4690.6    0.04       0  5022.2    0.04       0
  5026.2    0.04       0
Bank Sta=5022.2,5026.2
Exp/Cntr=0.3,0.1

Type RM Length L Ch R = 1,27583,496,496,496
BEGIN DESCRIPTION:
REEDS BRANCH 43.0
END DESCRIPTION:
XS GIS Cut Line= 3
      2555425.02     13566424.98      2555125.00     13566725.00
      2554825.00     13567225.01
#Sta/Elev= 30
  4539.2  202.32  4595.8  199.19  4680.7  195.47  4789.5  191.81  4850.4  189.59
  4921.1  188.16  4966.4  188.84  4984.8  187.94  4985.1  187.44  4988.6  187.44
  4988.8  187.94  5072.3  189.08  5093.7  190.25  5152.0  190.62  5220.1  192.64
  5247.3  192.50  5299.7  193.51  5358.1  195.34  5379.4  195.66  5385.3  195.25
  5416.4  196.78  5430.0  197.03  5453.3  196.35  5474.7  197.49  5496.1  197.70
  5511.6  198.52  5523.3  200.57  5533.0  204.22  5543.7  206.56  5546.6  206.56
#Mann=4,-1,0
  4539.2    0.12       0  4789.5    0.04       0  4984.8    0.04       0
  4988.8    0.04       0
Bank Sta=4984.8,4988.8
Exp/Cntr=0.3,0.1

Type RM Length L Ch R = 1,27087,418,418,418
BEGIN DESCRIPTION:
REEDS BRANCH 42.0
END DESCRIPTION:
XS GIS Cut Line= 3
      2555074.97     13566175.03      2554775.00     13566475.00
      2554474.99     13566775.01
#Sta/Elev= 30
  4646.3  196.24  4717.0  193.08  4745.2  192.30  4759.4  191.54  4773.5  191.27
  4854.0  188.37  4886.7  186.95  4900.8  186.96  4915.0  186.49  4943.2  186.19
  4957.4  185.72  4997.8  185.24  4998.1  184.74  5001.6  184.74  5001.8  185.24
  5013.9  185.76  5042.2  185.78  5056.4  185.46  5084.7  185.33  5112.9  185.58
  5127.1  185.37  5155.4  185.62  5169.5  186.18  5197.8  186.36  5268.5  188.50
  5282.6  188.61  5339.2  190.41  5353.4  191.11  5424.1  192.98  5494.8  195.74
#Mann=4,-1,0
  4646.3    0.12       0  4854.0    0.04       0  4997.8    0.04       0
  5001.8    0.04       0
Bank Sta=4997.8,5001.8
Exp/Cntr=0.3,0.1

Type RM Length L Ch R = 1,26669,336,336,336
BEGIN DESCRIPTION:
REEDS BRANCH 41.0
END DESCRIPTION:
XS GIS Cut Line= 3
      2555125.01     13565924.99      2554575.00     13566125.00
      2554324.98     13566725.05
#Sta/Elev= 30
  4453.3  205.07  4517.2  201.90  4555.1  198.95  4610.9  196.67  4641.5  194.51
  4728.0  190.57  4772.5  188.89  4783.2  189.14  4789.2  188.11  4814.4  187.16
  4906.2  185.20  4911.5  184.49  4931.5  184.42  4974.7  182.66  4998.0  182.34
  5006.6  181.24  5013.8  181.20  5021.3  181.15  5021.5  180.65  5025.0  180.65
  5025.3  181.15  5028.6  182.46  5254.7  183.90  5289.3  184.71  5313.2  185.95
  5360.8  186.46  5490.8  189.83  5591.1  192.82  5620.8  194.32  5688.6  195.98
#Mann=4,-1,0
  4453.3    0.12       0  5013.8    0.04       0  5021.3    0.05       0
  5025.3    0.04       0
Bank Sta=5021.3,5025.3
Exp/Cntr=0.3,0.1

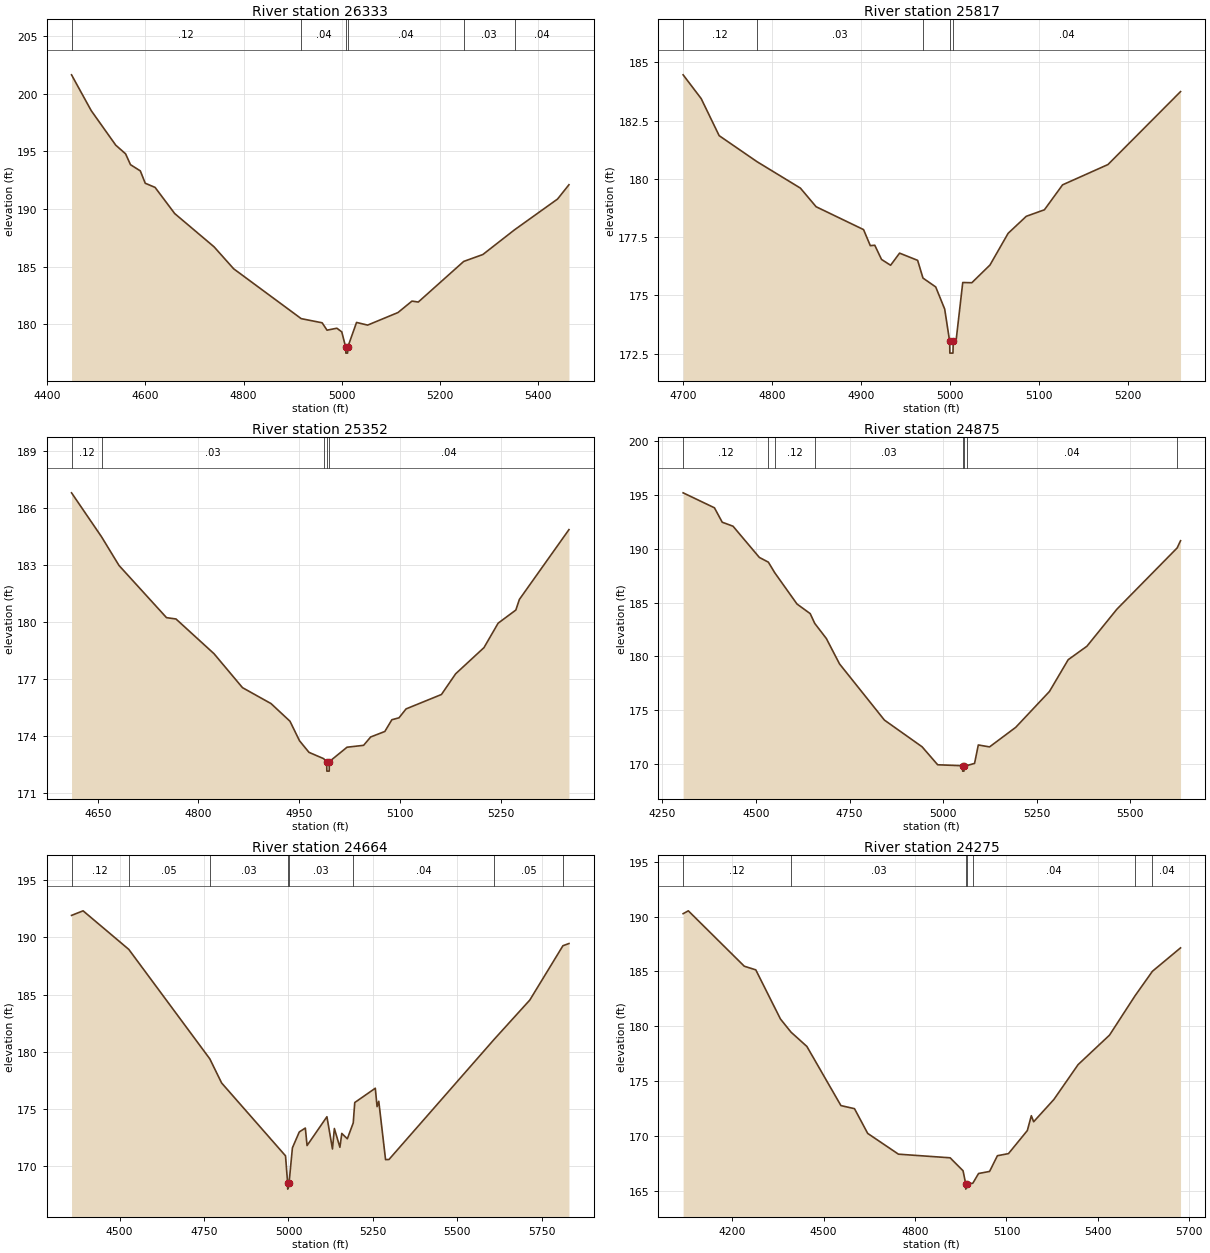
Type RM Length L Ch R = 1,26333,516,516,516
BEGIN DESCRIPTION:
REEDS BRANCH 40.0
END DESCRIPTION:
XS GIS Cut Line= 3
      2555025.01     13565825.00      2554425.00     13565825.00
      2554025.02     13565925.00
#Sta/Elev= 30
  4449.9  201.64  4489.9  198.54  4539.9  195.54  4559.9  194.79  4569.9  193.85
  4589.9  193.31  4599.9  192.24  4619.9  191.88  4659.9  189.61  4739.9  186.73
  4779.9  184.82  4917.3  180.50  4959.9  180.14  4969.9  179.50  4989.9  179.67
  4999.9  179.35  5007.9  178.01  5008.2  177.51  5011.7  177.51  5011.9  178.01
  5029.9  180.17  5052.5  179.94  5114.3  181.03  5142.7  182.02  5155.6  181.94
  5248.0  185.46  5287.0  186.06  5351.4  188.20  5439.0  190.87  5462.2  192.11
#Mann=6,-1,0
  4449.9    0.12       0  4917.3    0.04       0  5007.9    0.04       0
  5011.9    0.04       0  5248.0    0.03       0  5351.4    0.04       0
Bank Sta=5007.9,5011.9
Exp/Cntr=0.3,0.1

Type RM Length L Ch R = 1,25817,465,465,465
BEGIN DESCRIPTION:
REEDS BRANCH 39.0
END DESCRIPTION:
XS GIS Cut Line= 3
      2554724.99     13565375.00      2554425.00     13565325.00
      2554174.98     13565375.00
#Sta/Elev= 30
  4700.1  184.46  4720.4  183.44  4740.6  181.85  4783.3  180.73  4831.9  179.60
  4849.6  178.80  4902.9  177.82  4910.5  177.13  4915.5  177.15  4923.1  176.54
  4933.3  176.29  4943.4  176.81  4963.7  176.50  4969.7  175.74  4984.0  175.36
  4994.1  174.41  4999.7  173.02  4999.9  172.52  5003.4  172.52  5003.7  173.02
  5006.8  173.02  5014.4  175.55  5024.6  175.54  5045.0  176.30  5065.4  177.66
  5085.8  178.39  5106.2  178.67  5126.6  179.74  5177.6  180.61  5259.2  183.74
#Mann=5,-1,0
  4700.1    0.12       0  4783.3    0.03       0  4969.7    0.04       0
  4999.7    0.04       0  5003.7    0.04       0
Bank Sta=4999.7,5003.7
Exp/Cntr=0.3,0.1

Type RM Length L Ch R = 1,25352,477,477,477
BEGIN DESCRIPTION:
REEDS BRANCH 38.0
END DESCRIPTION:
XS GIS Cut Line= 3
      2554824.98     13565174.98      2554525.00     13564875.00
      2554224.96     13564774.99
#Sta/Elev= 30
  4611.0  186.82  4655.7  184.50  4681.7  182.99  4752.4  180.24  4766.5  180.17
  4823.1  178.34  4865.5  176.55  4908.0  175.71  4936.2  174.78  4950.4  173.75
  4964.5  173.14  4986.2  172.81  4990.8  172.65  4991.1  172.15  4994.6  172.15
  4994.8  172.65  5021.1  173.41  5045.8  173.51  5056.3  173.95  5077.4  174.24
  5087.9  174.86  5098.5  174.96  5109.0  175.43  5161.7  176.19  5182.8  177.28
  5225.0  178.66  5246.1  179.95  5272.4  180.64  5277.7  181.20  5351.5  184.88
#Mann=5,-1,0
  4611.0    0.12       0  4655.7    0.03       0  4986.2    0.04       0
  4990.8    0.04       0  4994.8    0.04       0
Bank Sta=4990.8,4994.8
Exp/Cntr=0.3,0.1

Type RM Length L Ch R = 1,24875,211,211,211
BEGIN DESCRIPTION:
REEDS BRANCH 37.0
END DESCRIPTION:
XS GIS Cut Line= 3
      2555291.94     13564935.12      2554733.61     13564481.18
      2554125.02     13564475.00
#Sta/Elev= 30
  4305.7  195.19  4389.3  193.80  4410.1  192.46  4438.9  192.09  4509.2  189.19
  4533.3  188.75  4550.3  187.77  4609.8  184.86  4645.0  183.97  4657.2  183.06
  4688.1  181.66  4723.3  179.30  4843.2  174.08  4943.8  171.60  4985.4  169.93
  5051.9  169.84  5052.1  169.34  5055.6  169.34  5055.9  169.84  5064.9  169.87
  5083.9  170.06  5093.9  171.77  5123.9  171.59  5193.9  173.41  5283.9  176.74
  5333.9  179.69  5383.9  180.94  5463.9  184.38  5624.8  190.07  5633.9  190.74
#Mann=8,-1,0
  4305.7    0.12       0  4533.3    0.05       0  4550.3    0.12       0
  4657.2    0.03       0  5051.9    0.03       0  5055.9    0.03       0
  5064.9    0.04       0  5624.8    0.05       0
Bank Sta=5051.9,5055.9
Exp/Cntr=0.3,0.1

Type RM Length L Ch R = 1,24664,389,389,389
BEGIN DESCRIPTION:
LGII3550
END DESCRIPTION:
XS GIS Cut Line= 5
      2555340.42     13564857.47      2554886.16     13564443.89
      2554859.04     13564311.68      2554737.00     13564247.26
      2554158.65     13564338.58
#Sta/Elev= 30
  4357.6  191.92  4391.8  192.32  4527.1  188.95  4767.0  179.38  4802.0  177.27
  4991.2  170.90  4997.5  168.49  4997.7  167.99  5001.5  168.49  5011.6  171.60
  5032.0  172.99  5049.9  173.33  5055.0  171.80  5113.8  174.32  5130.2  171.50
  5135.8  173.29  5152.2  171.65  5157.8  172.86  5174.2  172.39  5191.7  173.78
  5196.2  175.56  5257.0  176.81  5262.3  175.20  5267.3  175.67  5287.4  170.57
  5297.5  170.58  5608.2  181.06  5714.5  184.52  5812.6  189.27  5830.4  189.46
#Mann=8,-1,0
  4357.6    0.12       0  4527.1    0.05       0  4767.0    0.03       0
  4997.5    0.03       0  5001.5    0.03       0  5191.7    0.04       0
  5608.2    0.05       0  5812.6    0.04       0
Bank Sta=4997.5,5001.5
Exp/Cntr=0.3,0.1

Type RM Length L Ch R = 1,24275,341,341,341
BEGIN DESCRIPTION:
LGII3551
END DESCRIPTION:
XS GIS Cut Line= 4
      2555367.54     13564796.42      2555028.55     13564193.02
      2554662.41     13564064.20      2554130.15     13564209.98
#Sta/Elev= 30
  4039.0  190.26  4056.1  190.52  4239.7  185.48  4277.4  185.15  4358.3  180.68
  4393.1  179.48  4445.1  178.18  4556.8  172.80  4601.3  172.52  4644.6  170.27
  4745.5  168.38  4915.1  168.05  4957.5  166.87  4966.1  165.70  4966.3  165.20
  4970.1  165.70  4989.4  165.73  5008.3  166.62  5044.5  166.81  5070.2  168.24
  5106.5  168.43  5168.4  170.53  5181.5  171.88  5189.1  171.33  5255.6  173.36
  5335.0  176.53  5438.0  179.21  5521.8  182.79  5578.8  185.02  5671.1  187.15
#Mann=7,-1,0
  4039.0    0.12       0  4393.1    0.03       0  4966.1    0.04       0
  4970.1    0.03       0  4989.4    0.04       0  5521.8    0.05       0
  5578.8    0.04       0
Bank Sta=4966.1,4970.1
Exp/Cntr=0.3,0.1

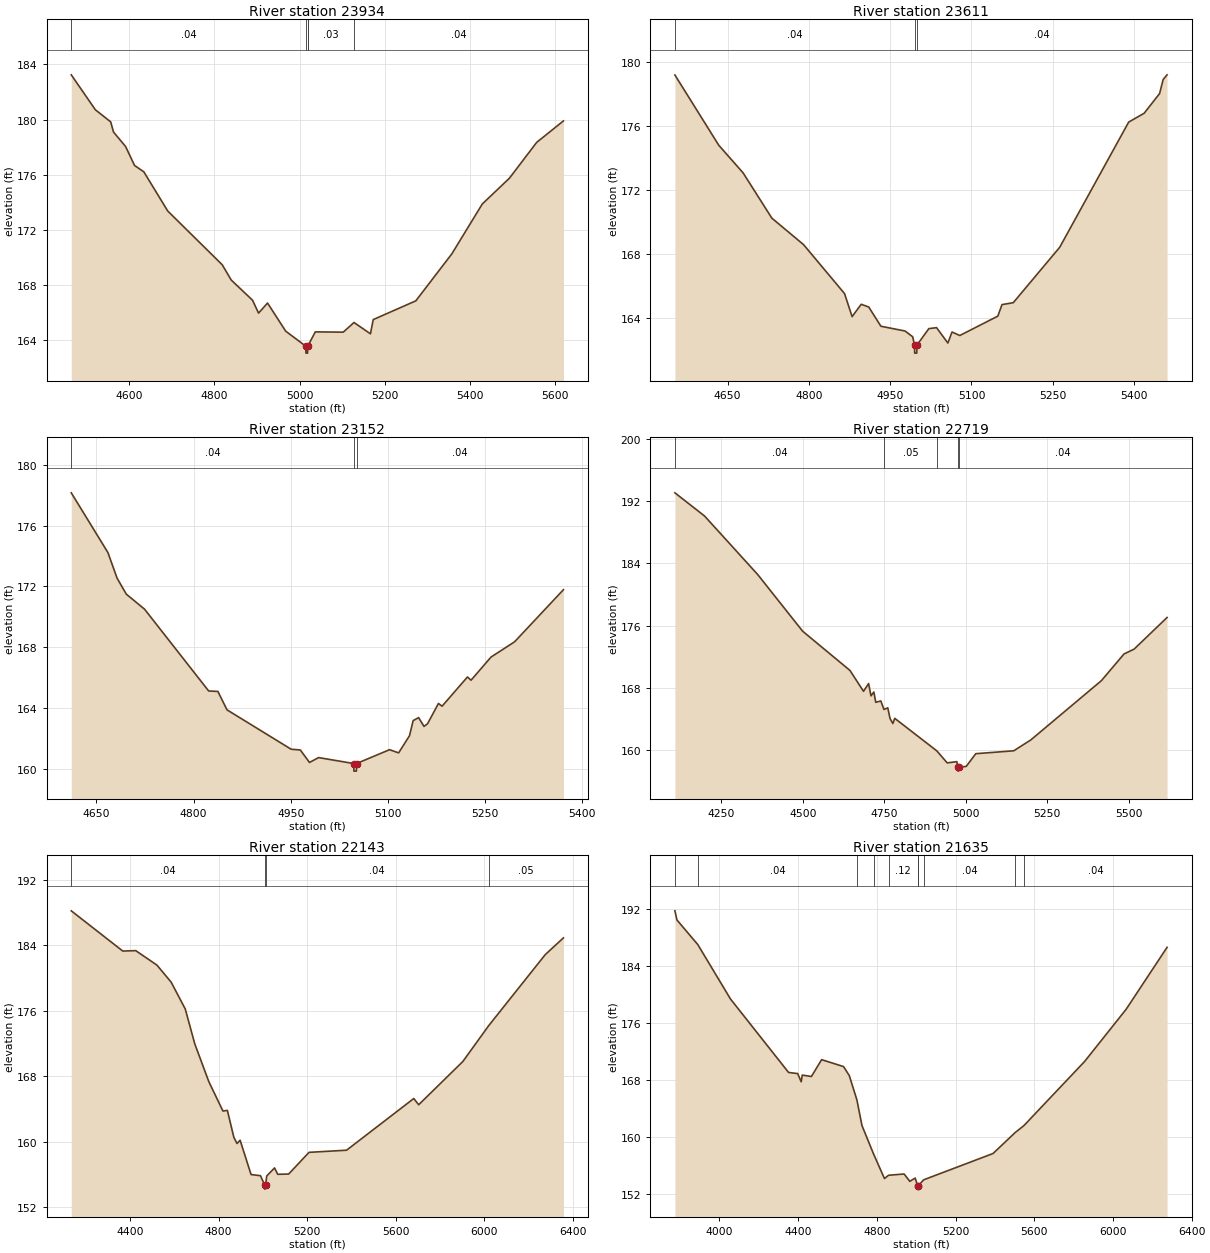
Type RM Length L Ch R = 1,23934,323,323,323
BEGIN DESCRIPTION:
REEDS BRANCH 36.0
END DESCRIPTION:
XS GIS Cut Line= 3
      2555225.00     13563425.00      2554791.24     13563806.55
      2554350.53     13564179.45
#Sta/Elev= 30
  4464.3  183.25  4520.8  180.72  4556.8  179.84  4563.5  179.10  4591.9  178.05
  4612.8  176.68  4634.6  176.22  4690.7  173.38  4818.7  169.48  4839.6  168.38
  4889.8  166.91  4903.8  165.98  4924.9  166.71  4967.6  164.67  5014.8  163.58
  5015.1  163.08  5018.8  163.08  5019.1  163.58  5019.5  163.60  5037.0  164.62
  5102.6  164.60  5127.8  165.30  5166.4  164.48  5172.9  165.51  5272.9  166.87
  5357.5  170.28  5428.9  173.89  5492.6  175.76  5556.4  178.35  5619.3  179.91
#Mann=5,-1,0
  4464.3    0.04       0  5014.8    0.04       0  5019.1    0.04       0
  5019.5    0.03       0  5127.8    0.04       0
Bank Sta=5014.8,5019.1
Exp/Cntr=0.3,0.1

Type RM Length L Ch R = 1,23611,459,459,459
BEGIN DESCRIPTION:
REEDS BRANCH 35.0
END DESCRIPTION:
XS GIS Cut Line= 3
      2554774.99     13563275.02      2554575.00     13563675.00
      2554274.98     13564025.03
#Sta/Elev= 30
  4552.8  179.18  4633.8  174.79  4678.6  173.07  4731.7  170.24  4790.4  168.58
  4865.8  165.53  4879.8  164.09  4896.6  164.86  4910.5  164.69  4932.9  163.49
  4977.6  163.19  4991.6  162.83  4995.0  162.31  4995.3  161.81  4999.1  161.81
  4999.4  162.31  5021.4  163.34  5035.7  163.40  5056.5  162.44  5064.2  163.13
  5078.5  162.91  5148.7  164.12  5156.4  164.84  5177.2  164.96  5262.9  168.42
  5390.2  176.24  5418.7  176.79  5447.2  178.02  5453.8  178.90  5461.0  179.19
#Mann=3,-1,0
  4552.8    0.04       0  4995.0    0.04       0  4999.4    0.04       0
Bank Sta=4995,4999.4
Exp/Cntr=0.3,0.1

Type RM Length L Ch R = 1,23152,433,433,433
BEGIN DESCRIPTION:
REEDS BRANCH 34.0
END DESCRIPTION:
XS GIS Cut Line= 3
      2554475.00     13563175.00      2554175.00     13563475.00
      2554024.99     13563775.02
#Sta/Elev= 30
  4611.1  178.15  4667.7  174.22  4681.8  172.54  4696.0  171.49  4724.2  170.50
  4823.2  165.12  4837.4  165.09  4851.5  163.88  4950.5  161.29  4964.7  161.24
  4978.8  160.42  4992.9  160.74  5047.1  160.35  5047.4  159.85  5051.2  159.85
  5051.5  160.35  5102.4  161.26  5116.4  161.05  5133.2  162.18  5138.8  163.17
  5147.2  163.37  5155.6  162.79  5161.1  162.97  5177.9  164.30  5183.5  164.12
  5222.6  166.04  5228.2  165.83  5259.0  167.35  5295.3  168.35  5370.8  171.78
#Mann=3,-1,0
  4611.1    0.04       0  5047.1    0.04       0  5051.5    0.04       0
Bank Sta=5047.1,5051.5
Exp/Cntr=0.3,0.1

Type RM Length L Ch R = 1,22719,576,576,576
BEGIN DESCRIPTION:
Mapping XS 00ccf6ac
END DESCRIPTION:
XS GIS Cut Line= 4
      2554562.78     13562912.56      2553989.86     13563068.81
      2553712.08     13563528.88      2553586.21     13563884.81
#Sta/Elev= 30
  4108.2  193.04  4199.2  190.06  4362.2  182.54  4499.8  175.27  4644.9  170.23
  4686.4  167.55  4702.0  168.55  4709.3  166.97  4718.1  167.46  4724.0  166.14
  4739.5  166.31  4749.1  165.22  4760.8  165.43  4767.7  164.06  4776.3  163.42
  4782.2  164.08  4911.2  159.90  4942.9  158.36  4972.4  158.52  4976.0  157.80
  4976.3  157.30  4980.4  157.80  5001.3  157.91  5030.6  159.54  5147.0  159.91
  5199.4  161.31  5415.7  168.92  5485.1  172.35  5516.0  172.97  5617.0  177.03
#Mann=5,-1,0
  4108.2    0.04       0  4749.1    0.05       0  4911.2    0.04       0
  4976.0    0.04       0  4980.4    0.04       0
Bank Sta=4976,4980.4
Exp/Cntr=0.3,0.1

Type RM Length L Ch R = 1,22143,508,508,508
BEGIN DESCRIPTION:
Mapping XS 9d701588
END DESCRIPTION:
XS GIS Cut Line= 4
      2554215.55     13562669.51      2553521.11     13562895.20
      2553139.17     13563268.46      2552701.71     13564121.72
#Sta/Elev= 30
  4134.2  188.19  4366.8  183.28  4425.5  183.33  4521.3  181.56  4585.2  179.49
  4649.1  176.21  4692.1  171.95  4755.5  167.34  4819.4  163.75  4839.3  163.83
  4868.6  160.54  4882.8  159.79  4896.9  160.19  4946.3  156.00  4988.8  155.86
  5007.8  154.72  5008.1  154.22  5012.3  154.72  5017.0  155.82  5052.5  156.81
  5066.6  156.03  5116.1  156.06  5208.1  158.71  5377.7  158.97  5681.3  165.28
  5703.5  164.52  5903.3  169.81  6019.6  174.17  6275.0  182.84  6357.3  184.89
#Mann=4,-1,0
  4134.2    0.04       0  5007.8    0.04       0  5012.3    0.04       0
  6019.6    0.05       0
Bank Sta=5007.8,5012.3
Exp/Cntr=0.3,0.1

Type RM Length L Ch R = 1,21635,521,521,521
BEGIN DESCRIPTION:
Mapping XS f81eff59
END DESCRIPTION:
XS GIS Cut Line= 4
      2554021.64     13562166.71      2553262.09     13562505.25
      2552849.77     13563047.79      2552368.39     13563910.79
#Sta/Elev= 30
  3773.8  191.68  3784.2  190.40  3890.0  186.96  4056.2  179.34  4351.4  169.05
  4397.8  168.89  4415.6  167.74  4421.0  168.68  4467.5  168.48  4519.4  170.84
  4630.9  169.87  4660.0  168.61  4698.9  165.19  4724.5  161.61  4783.5  157.63
  4838.8  154.19  4859.6  154.65  4938.6  154.83  4967.7  153.80  4994.8  154.26
  5007.0  153.21  5007.4  152.71  5011.7  153.21  5037.7  154.01  5390.7  157.70
  5502.9  160.63  5546.9  161.59  5855.8  170.58  6067.2  177.90  6275.0  186.57
#Mann=10,-1,0
  3773.8   0.013       0  3890.0    0.04       0  4698.9    0.05       0
  4783.5    0.04       0  4859.6    0.12       0  5007.0    0.05       0
  5011.7    0.12       0  5037.7    0.04       0  5502.9    0.03       0
  5546.9    0.04       0
Bank Sta=5007,5011.7
Exp/Cntr=0.3,0.1

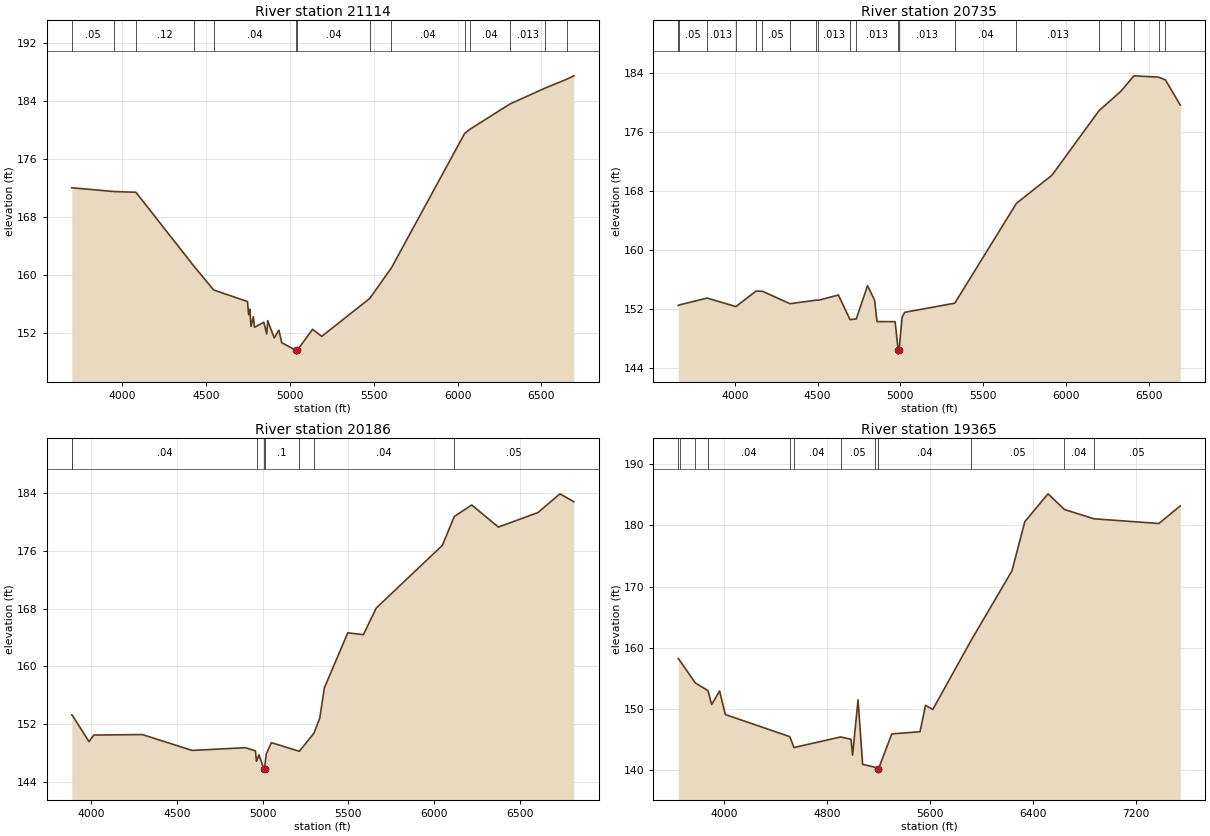
Type RM Length L Ch R = 1,21114,379,379,379
BEGIN DESCRIPTION:
Mapping XS f7a0cdc4
END DESCRIPTION:
XS GIS Cut Line= 6
      2553505.12     13561372.48      2553001.68     13562079.91
      2552818.58     13562287.86      2552720.73     13562482.24
      2552509.04     13562894.99      2551883.71     13563877.65
#Sta/Elev= 30
  3701.4  172.05  3953.9  171.53  4083.9  171.43  4428.3  161.29  4546.9  157.98
  4748.4  156.39  4755.1  154.57  4762.6  155.33  4769.3  152.97  4783.5  154.31
  4790.2  152.84  4845.7  153.54  4863.1  151.93  4868.7  153.76  4907.7  151.38
  4935.6  152.45  4952.4  150.73  5039.2  149.65  5039.5  149.15  5044.1  149.65
  5136.1  152.57  5191.1  151.60  5476.6  156.81  5606.2  161.03  6042.0  179.51
  6075.5  180.13  6311.9  183.58  6523.5  185.79  6653.6  187.02  6693.0  187.46
#Mann=14,-1,0
  3701.4    0.05       0  3953.9   0.013       0  4083.9    0.12       0
  4428.3   0.013       0  4546.9    0.04       0  5039.2    0.04       0
  5044.1    0.04       0  5476.6   0.013       0  5606.2    0.04       0
  6042.0   0.013       0  6075.5    0.04       0  6311.9   0.013       0
  6523.5    0.04       0  6653.6   0.013       0
Bank Sta=5039.2,5044.1
Exp/Cntr=0.3,0.1

Type RM Length L Ch R = 1,20735,549,549,549
BEGIN DESCRIPTION:
Mapping XS ed065a8f
END DESCRIPTION:
XS GIS Cut Line= 3
      2553357.03     13561000.88      2552863.94     13561639.80
      2551662.58     13563514.77
#Sta/Elev= 30
  3658.3  152.51  3665.7  152.59  3832.7  153.51  4006.5  152.36  4128.4  154.45
  4166.8  154.43  4333.8  152.75  4492.3  153.23  4505.8  153.22  4626.4  153.92
  4696.4  150.60  4733.7  150.68  4802.2  155.18  4844.5  153.25  4859.7  150.33
  4968.8  150.32  4987.5  146.43  4987.8  145.93  4992.4  146.43  5011.1  150.90
  5026.3  151.58  5329.4  152.82  5702.0  166.32  5916.5  170.12  6201.4  178.86
  6332.2  181.45  6411.9  183.56  6562.1  183.38  6602.5  183.00  6692.2  179.60
#Mann=20,-1,0
  3658.3   0.013       0  3665.7    0.05       0  3832.7   0.013       0
  4006.5    0.05       0  4128.4   0.013       0  4166.8    0.05       0
  4333.8   0.013       0  4492.3    0.05       0  4505.8   0.013       0
  4696.4    0.12       0  4733.7   0.013       0  4987.5    0.03       0
  4992.4   0.013       0  5329.4    0.04       0  5702.0   0.013       0
  6201.4    0.05       0  6332.2   0.013       0  6411.9    0.05       0
  6562.1   0.013       0  6602.5    0.05       0
Bank Sta=4987.5,4992.4
Exp/Cntr=0.3,0.1

Type RM Length L Ch R = 1,20186,821,821,821
BEGIN DESCRIPTION:
Mapping XS 28aef8e4
END DESCRIPTION:
XS GIS Cut Line= 4
      2553258.71     13560913.93      2552645.03     13561228.02
      2552171.45     13561928.72      2551746.66     13563251.36
#Sta/Elev= 30
  3888.8  153.26  3891.0  153.26  3989.2  149.56  4017.0  150.47  4300.1  150.54
  4589.9  148.34  4900.4  148.72  4958.5  148.28  4964.5  146.84  4969.3  147.11
  4979.5  147.73  5006.6  145.83  5007.0  145.33  5011.5  145.83  5021.5  147.85
  5051.4  149.42  5214.1  148.22  5299.1  150.72  5333.1  152.81  5360.1  157.03
  5496.4  164.65  5587.5  164.40  5662.2  168.09  6047.5  176.79  6116.8  180.79
  6218.5  182.38  6373.8  179.32  6603.8  181.33  6732.2  183.93  6813.1  182.83
#Mann=8,-1,0
  3888.8   0.013       0  3891.0    0.04       0  4969.3     0.1       0
  5006.6    0.05       0  5011.5     0.1       0  5214.1    0.05       0
  5299.1    0.04       0  6116.8    0.05       0
Bank Sta=5006.6,5011.5
Exp/Cntr=0.3,0.1

Type RM Length L Ch R = 1,19365,0,0,0
BEGIN DESCRIPTION:
Mapping XS 28fb3b3f
END DESCRIPTION:
XS GIS Cut Line= 5
      2553565.33     13560980.08      2553065.33     13560743.97
      2552280.61     13560813.41      2551718.11     13561362.02
      2551725.05     13563131.45
#Sta/Elev= 30
  3647.3  158.21  3664.1  157.77  3779.2  154.25  3878.8  152.97  3906.3  150.70
  3968.4  152.92  4012.6  149.07  4513.2  145.45  4545.2  143.67  4907.0  145.40
  4988.0  145.02  5000.2  142.44  5042.6  151.47  5078.0  140.93  5172.7  140.45
  5195.6  140.15  5196.0  139.65  5200.7  140.15  5304.2  145.90  5523.5  146.26
  5566.0  150.57  5622.6  149.90  5917.9  161.11  6236.7  172.56  6336.7  180.61
  6516.7  185.16  6644.1  182.60  6872.6  181.08  7376.7  180.31  7543.2  183.19
#Mann=13,-1,0
  3647.3    0.12       0  3664.1   0.013       0  3779.2    0.05       0
  3878.8    0.04       0  4513.2    0.12       0  4545.2    0.04       0
  4907.0    0.05       0  5172.7    0.04       0  5195.6    0.05       0
  5200.7    0.04       0  5917.9    0.05       0  6644.1    0.04       0
  6872.6    0.05       0
Bank Sta=5195.6,5200.7
Exp/Cntr=0.3,0.1

Chan Stop Cuts=-1