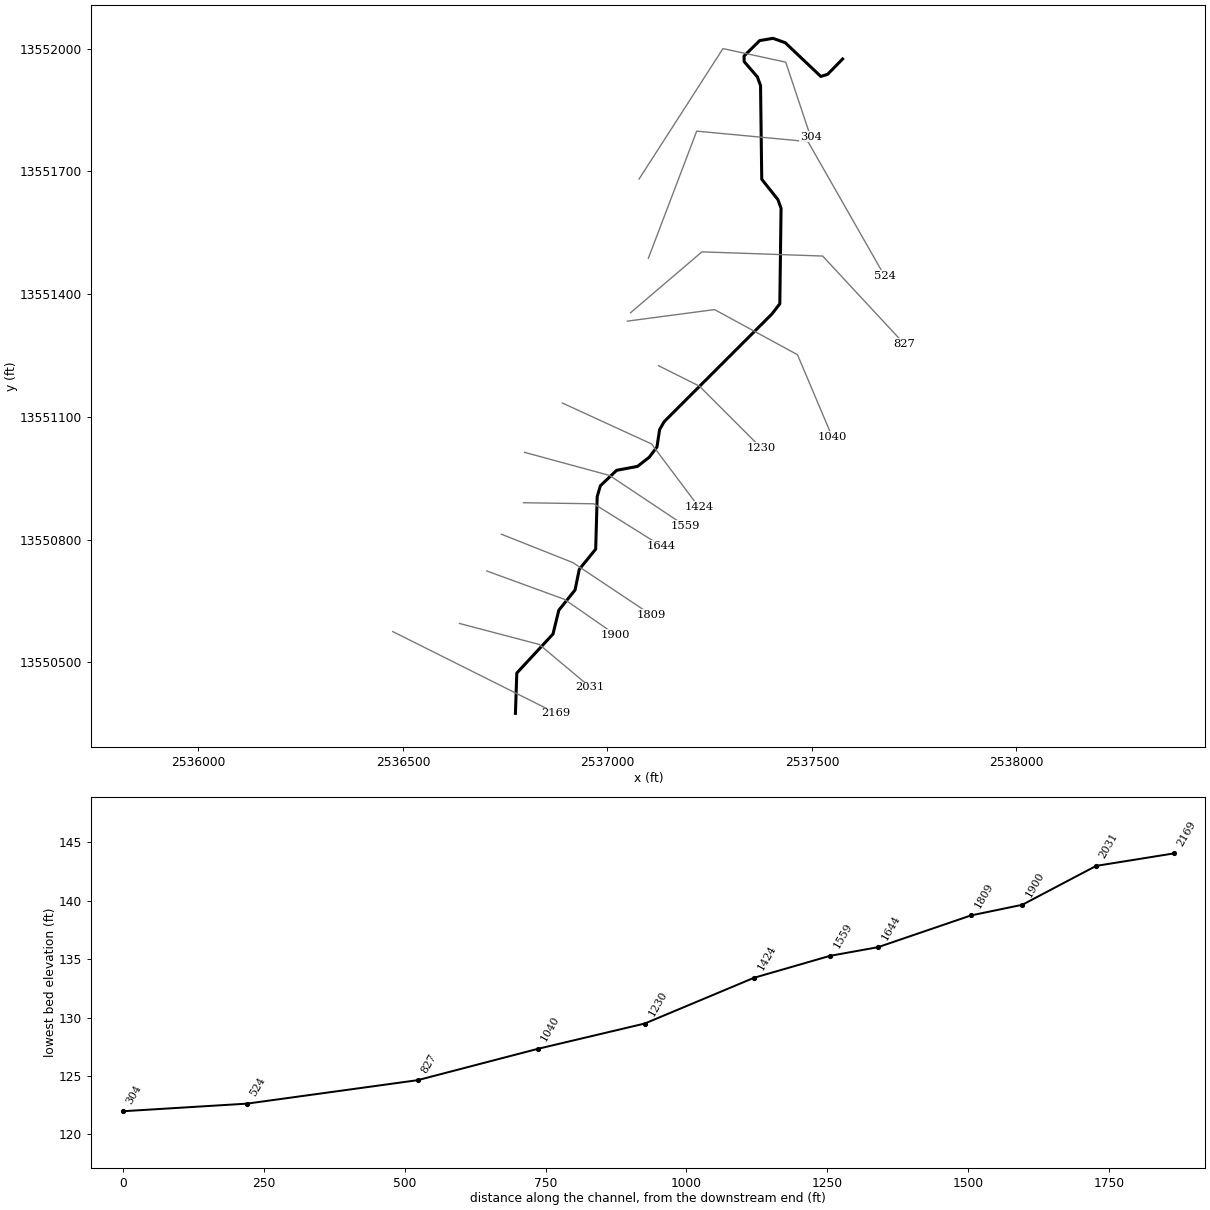
--- TRIB 1 TO CARLISLE CREEK.prj (project) ---

Proj Title=TRIB 1 TO CARLISLE CREEK Base Level Engineering
Current Plan=p01
Default Exp/Contr=0.3,0.1
English Units
Geom File=g01
Flow File=f01
Plan File=p01
BEGIN DESCRIPTION:
TRIB 1 TO CARLISLE CREEK
END DESCRIPTION:

--- TRIB 1 TO CARLISLE CREEK.p01 (plan) ---

Plan Title=Multiple Run
Short Identifier=Multiple
Geom File=g01
Flow File=f01
Subcritical Flow
K Sum by GR= 0
Std Step Tol= 0.01
Critical Tol= 0.01
Num of Std Step Trials= 20
Max Error Tol= 0.3
Flow Tol Ratio= 0.001
Split Flow NTrial= 30
Split Flow Tol= 0.02
Split Flow Ratio= 0.02
Log Output Level= 0
Friction Slope Method= 1
Unsteady Friction Slope Method= 2
Unsteady Bridges Friction Slope Method= 1
Parabolic Critical Depth
Global Vel Dist=  1 , 1 , 1
Global Log Level= 0
CheckData=True
Encroach Param= -1, 0, 0, 0
BEGIN DESCRIPTION:
Multiple Run
END DESCRIPTION:

--- TRIB 1 TO CARLISLE CREEK.f01 (steady flow) ---

Flow Title=Multiple
Number of Profiles=7
Profile Names=10-year,25-year,50-year,1pct_min,100-year,1pct_plu,500-year
River Rch & RM= TRIB 1 TO CARLIS,Reach-1,2169
     418     655     863     553    1103    2202    1778
Boundary for River Rch & Prof#=TRIB 1 TO CARLIS,Reach-1,1
Up Type=0
Dn Type=3
Dn Slope=0.005
Boundary for River Rch & Prof#=TRIB 1 TO CARLIS,Reach-1,2
Up Type=0
Dn Type=3
Dn Slope=0.005
Boundary for River Rch & Prof#=TRIB 1 TO CARLIS,Reach-1,3
Up Type=0
Dn Type=3
Dn Slope=0.005
Boundary for River Rch & Prof#=TRIB 1 TO CARLIS,Reach-1,4
Up Type=0
Dn Type=3
Dn Slope=0.005
Boundary for River Rch & Prof#=TRIB 1 TO CARLIS,Reach-1,5
Up Type=0
Dn Type=3
Dn Slope=0.005
Boundary for River Rch & Prof#=TRIB 1 TO CARLIS,Reach-1,6
Up Type=0
Dn Type=3
Dn Slope=0.005
Boundary for River Rch & Prof#=TRIB 1 TO CARLIS,Reach-1,7
Up Type=0
Dn Type=3
Dn Slope=0.005

--- TRIB 1 TO CARLISLE CREEK.g01 (geometry) ---

Geom Title=Existing Conditions

River Reach=TRIB 1 TO CARLIS,Reach-1
Reach XY= 30
      2536775.00     13550375.00      2536778.39     13550473.59
      2536866.84     13550568.95      2536881.10     13550627.19
      2536920.84     13550676.72      2536931.12     13550727.18
      2536971.24     13550776.56      2536974.94     13550905.11
      2536982.70     13550931.47      2537022.45     13550969.25
      2537073.53     13550978.90      2537102.13     13551001.17
      2537121.11     13551026.43      2537127.55     13551068.91
      2537138.64     13551088.20      2537402.14     13551351.47
      2537421.46     13551376.46      2537424.48     13551609.78
      2537416.86     13551631.06      2537377.26     13551680.94
      2537374.33     13551909.85      2537366.52     13551931.21
      2537334.22     13551968.67      2537334.01     13551982.12
      2537372.15     13552019.94      2537404.69     13552025.47
      2537434.65     13552014.80      2537521.67     13551932.27
      2537538.34     13551937.51      2537575.00     13551975.00

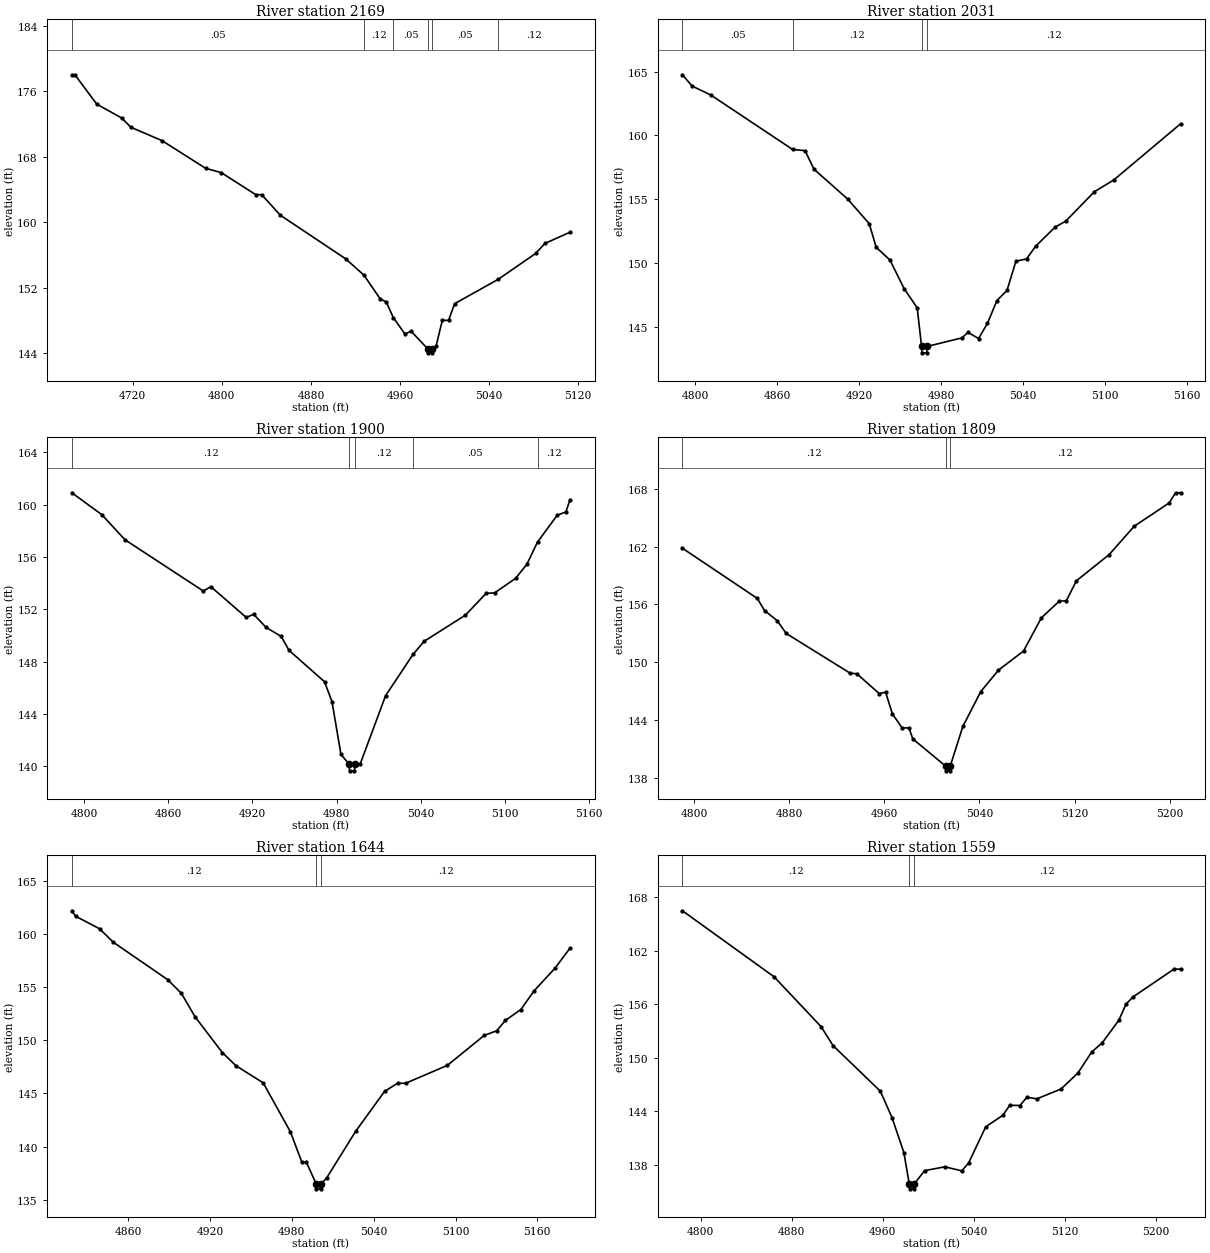
Type RM Length L Ch R = 1,2169,138,138,138
BEGIN DESCRIPTION:
TRIB 1 TO CARLISLE CREEK 4.0
END DESCRIPTION:
XS GIS Cut Line= 3
      2536475.04     13550574.98      2536775.00     13550425.00
      2536875.03     13550374.98
#Sta/Elev= 30
  4665.4  178.03  4668.1  178.03  4687.7  174.45  4710.1  172.75  4718.5  171.61
  4746.4  169.98  4785.5  166.60  4799.5  166.08  4830.3  163.40  4835.9  163.37
  4852.6  160.87  4911.3  155.54  4927.7  153.54  4942.1  150.68  4947.7  150.27
  4954.0  148.37  4964.4  146.37  4970.0  146.70  4984.8  144.56  4985.0  144.06
  4988.5  144.06  4988.8  144.56  4992.4  144.87  4998.0  148.03  5003.6  148.03
  5009.1  150.07  5048.3  153.05  5081.8  156.20  5090.2  157.43  5112.6  158.79
#Mann=6,-1,0
  4665.4    0.05       0  4927.7    0.12       0  4954.0    0.05       0
  4984.8    0.05       0  4988.8    0.05       0  5048.3    0.12       0
Bank Sta=4984.8,4988.8
Exp/Cntr=0.3,0.1

Type RM Length L Ch R = 1,2031,131,131,131
BEGIN DESCRIPTION:
Mapping XS 325287b2
END DESCRIPTION:
XS GIS Cut Line= 3
      2536638.21     13550594.82      2536833.23     13550543.50
      2536957.96     13550439.13
#Sta/Elev= 30
  4790.8  164.75  4797.8  163.87  4811.5  163.17  4871.3  158.91  4880.5  158.81
  4887.0  157.36  4911.6  155.03  4927.4  153.10  4932.5  151.25  4942.6  150.25
  4952.9  148.02  4962.5  146.51  4965.7  143.49  4965.9  142.99  4969.4  142.99
  4969.7  143.49  4995.2  144.16  4999.6  144.59  5007.4  144.11  5013.9  145.30
  5020.8  147.08  5028.2  147.88  5034.7  150.16  5042.5  150.34  5049.1  151.33
  5063.4  152.83  5071.2  153.30  5092.0  155.59  5106.3  156.52  5155.1  160.91
#Mann=4,-1,0
  4790.8    0.05       0  4871.3    0.12       0  4965.7    0.05       0
  4969.7    0.12       0
Bank Sta=4965.7,4969.7
Exp/Cntr=0.3,0.1

Type RM Length L Ch R = 1,1900,91,91,91
BEGIN DESCRIPTION:
Mapping XS eafd55e2
END DESCRIPTION:
XS GIS Cut Line= 3
      2536704.94     13550723.15      2536894.83     13550653.87
      2537020.26     13550566.83
#Sta/Elev= 30
  4791.4  160.92  4812.8  159.24  4829.2  157.33  4885.0  153.41  4890.4  153.74
  4915.6  151.39  4920.9  151.63  4929.8  150.62  4940.5  149.94  4946.1  148.87
  4971.4  146.47  4976.7  144.95  4983.1  140.91  4989.0  140.16  4989.2  139.66
  4992.7  139.66  4993.0  140.16  4996.7  140.16  5014.9  145.41  5034.4  148.56
  5042.4  149.57  5071.7  151.56  5086.5  153.23  5092.6  153.27  5107.5  154.38
  5115.5  155.45  5123.1  157.15  5137.2  159.21  5143.3  159.45  5146.2  160.38
#Mann=5,-1,0
  4791.4    0.12       0  4989.0    0.05       0  4993.0    0.12       0
  5034.4    0.05       0  5123.1    0.12       0
Bank Sta=4989,4993
Exp/Cntr=0.3,0.1

Type RM Length L Ch R = 1,1809,165,165,165
BEGIN DESCRIPTION:
Mapping XS 06b6a18c
END DESCRIPTION:
XS GIS Cut Line= 3
      2536740.81     13550813.01      2536915.36     13550743.70
      2537107.89     13550615.35
#Sta/Elev= 30
  4790.0  161.82  4853.0  156.62  4859.1  155.36  4869.8  154.31  4877.3  152.99
  4931.3  148.86  4936.7  148.82  4955.6  146.76  4961.0  146.90  4966.7  144.65
  4974.9  143.20  4980.6  143.20  4983.9  142.06  5011.4  139.25  5011.7  138.75
  5015.2  138.75  5015.4  139.25  5026.0  143.35  5041.0  146.95  5056.0  149.19
  5077.1  151.17  5092.1  154.61  5107.1  156.33  5113.1  156.38  5121.6  158.45
  5149.2  161.17  5170.2  164.10  5199.7  166.52  5205.0  167.57  5209.2  167.57
#Mann=3,-1,0
  4790.0    0.12       0  5011.4    0.05       0  5015.4    0.12       0
Bank Sta=5011.4,5015.4
Exp/Cntr=0.3,0.1

Type RM Length L Ch R = 1,1644,85,85,85
BEGIN DESCRIPTION:
Mapping XS dfa118c1
END DESCRIPTION:
XS GIS Cut Line= 3
      2536794.70     13550890.00      2536966.70     13550887.43
      2537130.51     13550785.05
#Sta/Elev= 30
  4818.7  162.16  4821.4  161.65  4839.0  160.47  4849.0  159.21  4889.0  155.68
  4899.0  154.40  4909.0  152.20  4929.0  148.84  4939.0  147.60  4959.0  145.99
  4979.0  141.37  4987.4  138.51  4990.7  138.51  4997.7  136.53  4997.9  136.03
  5001.4  136.03  5001.7  136.53  5005.6  137.07  5026.8  141.44  5048.0  145.19
  5057.5  145.95  5063.4  145.95  5094.0  147.63  5121.1  150.45  5130.2  150.88
  5136.5  151.85  5147.9  152.88  5157.7  154.65  5173.0  156.77  5183.9  158.64
#Mann=3,-1,0
  4818.7    0.12       0  4997.7    0.05       0  5001.7    0.12       0
Bank Sta=4997.7,5001.7
Exp/Cntr=0.3,0.1

Type RM Length L Ch R = 1,1559,135,135,135
BEGIN DESCRIPTION:
Mapping XS 84f46b55
END DESCRIPTION:
XS GIS Cut Line= 3
      2536797.31     13551013.20      2537005.20     13550956.73
      2537189.98     13550833.55
#Sta/Elev= 30
  4784.1  166.49  4864.6  159.08  4905.8  153.50  4916.4  151.36  4957.9  146.25
  4968.2  143.28  4978.6  139.36  4983.4  135.79  4983.7  135.29  4987.2  135.29
  4987.4  135.79  4996.8  137.33  5014.5  137.76  5029.5  137.31  5035.5  138.20
  5050.5  142.25  5065.6  143.55  5071.6  144.67  5080.6  144.64  5086.6  145.57
  5095.4  145.39  5116.6  146.49  5131.5  148.29  5143.7  150.67  5152.7  151.65
  5167.5  154.22  5173.7  156.01  5179.7  156.81  5215.8  159.94  5221.6  159.94
#Mann=3,-1,0
  4784.1    0.12       0  4983.4    0.05       0  4987.4    0.12       0
Bank Sta=4983.4,4987.4
Exp/Cntr=0.3,0.1

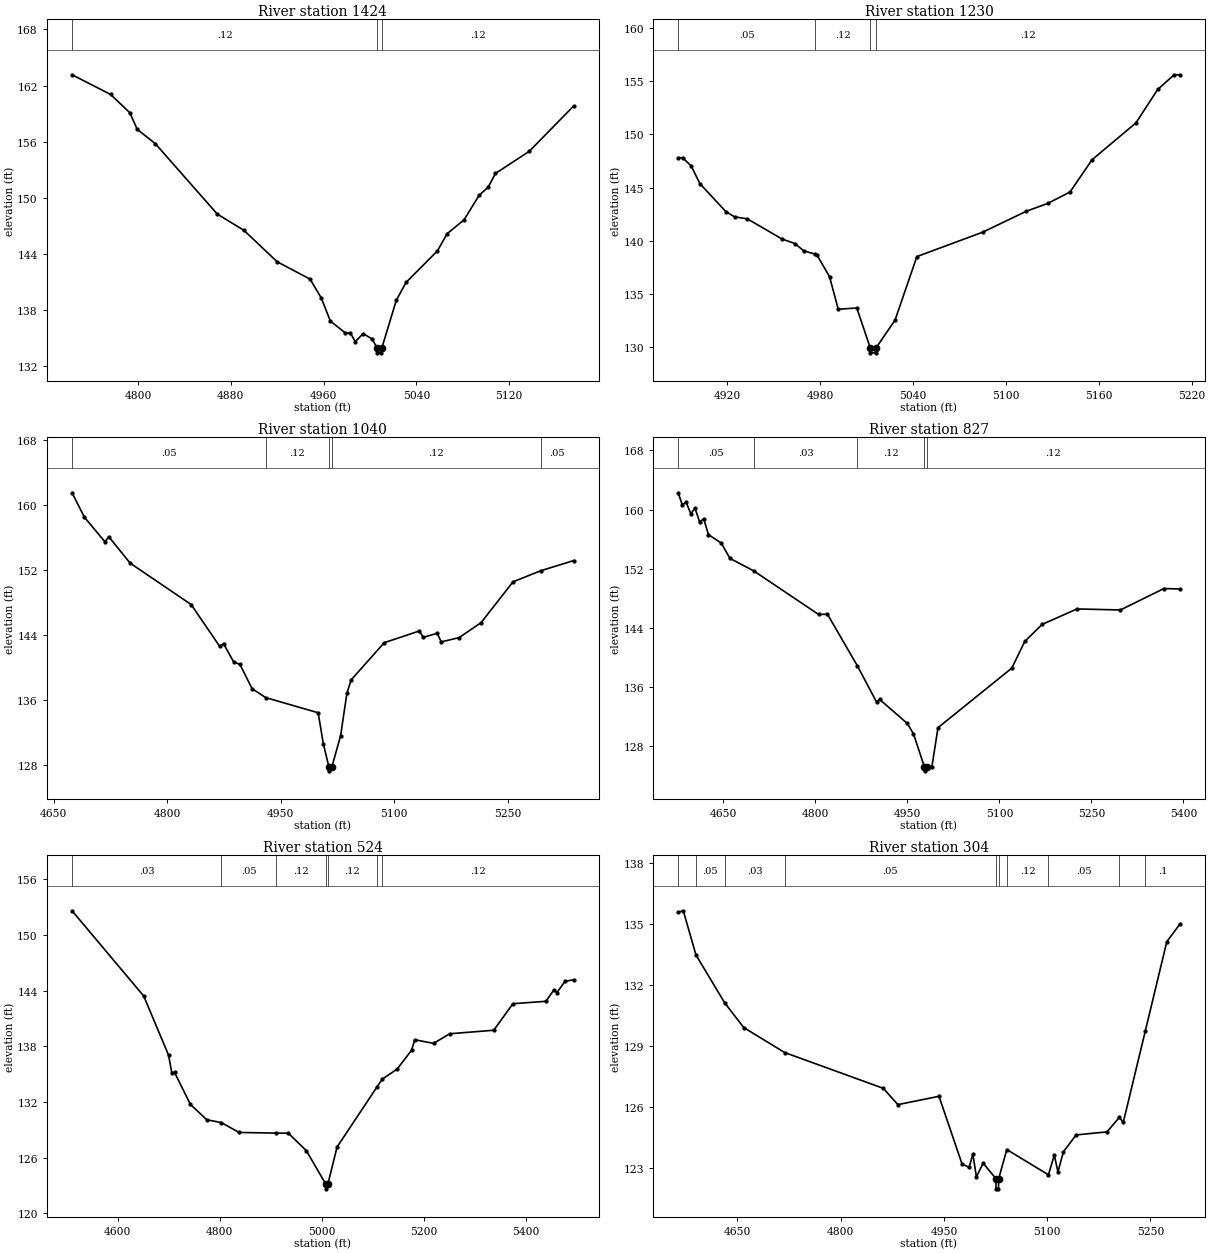
Type RM Length L Ch R = 1,1424,194,194,194
BEGIN DESCRIPTION:
Mapping XS f3aa9562
END DESCRIPTION:
XS GIS Cut Line= 3
      2536889.72     13551133.82      2537107.86     13551033.73
      2537223.24     13550879.90
#Sta/Elev= 30
  4743.2  163.15  4776.4  161.05  4793.0  159.09  4799.4  157.31  4815.0  155.78
  4868.4  148.25  4891.4  146.51  4919.9  143.16  4948.4  141.29  4958.1  139.26
  4965.9  136.80  4978.9  135.53  4983.2  135.53  4987.3  134.60  4994.1  135.46
  5001.9  134.90  5006.2  133.91  5006.4  133.41  5009.9  133.41  5010.2  133.91
  5022.7  139.03  5031.1  140.94  5058.2  144.32  5066.5  146.15  5081.1  147.63
  5094.1  150.26  5101.9  151.13  5108.2  152.60  5137.3  154.96  5175.5  159.80
#Mann=3,-1,0
  4743.2    0.12       0  5006.2    0.05       0  5010.2    0.12       0
Bank Sta=5006.2,5010.2
Exp/Cntr=0.3,0.1

Type RM Length L Ch R = 1,1230,190,190,190
BEGIN DESCRIPTION:
TRIB 1 TO CARLISLE CREEK 2.0
END DESCRIPTION:
XS GIS Cut Line= 3
      2537124.98     13551225.01      2537225.00     13551175.00
      2537375.03     13551024.97
#Sta/Elev= 30
  4888.2  147.80  4891.0  147.80  4896.6  147.03  4902.2  145.37  4919.0  142.74
  4924.6  142.25  4932.9  142.06  4955.3  140.17  4963.7  139.74  4969.3  139.06
  4976.7  138.75  4977.7  138.71  4986.0  136.63  4991.6  133.58  5003.6  133.70
  5012.2  129.99  5012.4  129.49  5015.9  129.49  5016.2  129.99  5028.3  132.56
  5042.4  138.52  5084.9  140.81  5113.2  142.78  5127.3  143.53  5141.4  144.59
  5155.6  147.61  5183.9  151.06  5198.0  154.20  5208.6  155.58  5212.2  155.58
#Mann=4,-1,0
  4888.2    0.05       0  4976.7    0.12       0  5012.2    0.05       0
  5016.2    0.12       0
Bank Sta=5012.2,5016.2
Exp/Cntr=0.3,0.1

Type RM Length L Ch R = 1,1040,213,213,213
BEGIN DESCRIPTION:
Mapping XS 9f319ed1
END DESCRIPTION:
XS GIS Cut Line= 4
      2537048.84     13551334.03      2537261.86     13551362.27
      2537464.63     13551251.90      2537549.32     13551051.72
#Sta/Elev= 30
  4674.1  161.50  4690.4  158.50  4717.6  155.47  4722.6  156.11  4750.9  152.85
  4831.6  147.76  4869.3  142.62  4874.4  142.95  4888.0  140.67  4896.0  140.42
  4912.1  137.42  4930.2  136.32  4999.5  134.46  5006.4  130.62  5013.7  127.82
  5013.9  127.32  5017.7  127.82  5029.2  131.64  5037.5  136.85  5043.2  138.51
  5086.9  143.07  5133.2  144.51  5138.6  143.73  5156.9  144.23  5162.3  143.17
  5186.0  143.70  5215.1  145.55  5257.1  150.55  5293.6  151.91  5337.2  153.16
#Mann=5,-1,0
  4674.1    0.05       0  4930.2    0.12       0  5013.7    0.05       0
  5017.7    0.12       0  5293.6    0.05       0
Bank Sta=5013.7,5017.7
Exp/Cntr=0.3,0.1

Type RM Length L Ch R = 1,827,303,303,303
BEGIN DESCRIPTION:
Mapping XS 6065f343
END DESCRIPTION:
XS GIS Cut Line= 4
      2537056.54     13551354.57      2537231.06     13551503.43
      2537526.23     13551493.17      2537725.31     13551278.77
#Sta/Elev= 30
  4576.5  162.27  4583.0  160.67  4589.5  160.96  4597.2  159.42  4603.8  160.19
  4611.5  158.32  4618.1  158.75  4625.8  156.61  4646.6  155.47  4660.9  153.39
  4699.6  151.70  4805.2  145.81  4819.8  145.83  4868.4  138.87  4899.8  133.95
  4904.8  134.31  4949.9  131.05  4959.9  129.66  4977.9  125.14  4978.2  124.64
  4981.9  125.14  4989.9  125.15  4999.9  130.48  5120.3  138.55  5141.3  142.15
  5169.7  144.46  5226.4  146.55  5297.2  146.41  5368.1  149.31  5393.8  149.25
#Mann=5,-1,0
  4576.5    0.05       0  4699.6    0.03       0  4868.4    0.12       0
  4977.9    0.05       0  4981.9    0.12       0
Bank Sta=4977.9,4981.9
Exp/Cntr=0.3,0.1

Type RM Length L Ch R = 1,524,220,220,220
BEGIN DESCRIPTION:
Mapping XS 2aceb55e
END DESCRIPTION:
XS GIS Cut Line= 4
      2537100.15     13551488.00      2537218.23     13551798.60
      2537490.30     13551772.93      2537677.68     13551444.37
#Sta/Elev= 30
  4510.3  152.61  4651.0  143.41  4699.7  137.03  4705.9  135.15  4711.3  135.19
  4742.4  131.74  4774.5  130.08  4803.4  129.77  4838.0  128.71  4910.1  128.64
  4934.5  128.63  4969.9  126.75  5008.1  123.13  5008.3  122.63  5012.1  123.13
  5030.2  127.14  5108.2  133.59  5119.2  134.47  5148.0  135.54  5176.3  137.57
  5182.6  138.71  5219.5  138.31  5251.2  139.35  5337.6  139.73  5375.1  142.59
  5439.9  142.85  5455.7  144.09  5461.5  143.79  5477.4  145.00  5494.1  145.17
#Mann=7,-1,0
  4510.3    0.03       0  4803.4    0.05       0  4910.1    0.12       0
  5008.1    0.05       0  5012.1    0.12       0  5108.2     0.1       0
  5119.2    0.12       0
Bank Sta=5008.1,5012.1
Exp/Cntr=0.3,0.1

Type RM Length L Ch R = 1,304,0,0,0
BEGIN DESCRIPTION:
Mapping XS 2aceb55eaa
END DESCRIPTION:
XS GIS Cut Line= 4
      2537077.42     13551681.55      2537282.46     13552000.36
      2537435.90     13551967.29      2537496.74     13551784.78
#Sta/Elev= 30
  4564.1  135.58  4571.5  135.65  4589.9  133.48  4631.7  131.12  4659.3  129.91
  4718.8  128.68  4862.1  126.92  4883.2  126.12  4942.9  126.53  4976.4  123.20
  4986.7  123.04  4992.1  123.69  4997.2  122.57  5007.1  123.24  5025.6  122.48
  5025.8  121.98  5029.3  121.98  5029.6  122.48  5041.4  123.91  5101.9  122.67
  5110.4  123.64  5115.7  122.81  5123.6  123.80  5142.1  124.63  5186.9  124.78
  5204.8  125.49  5210.6  125.25  5242.7  129.76  5273.8  134.13  5292.5  134.98
#Mann=10,-1,0
  4564.1    0.03       0  4589.9    0.05       0  4631.7    0.03       0
  4718.8    0.05       0  5025.6    0.05       0  5029.6    0.05       0
  5041.4    0.12       0  5101.9    0.05       0  5204.8    0.12       0
  5242.7     0.1       0
Bank Sta=5025.6,5029.6
Exp/Cntr=0.3,0.1

Chan Stop Cuts=-1