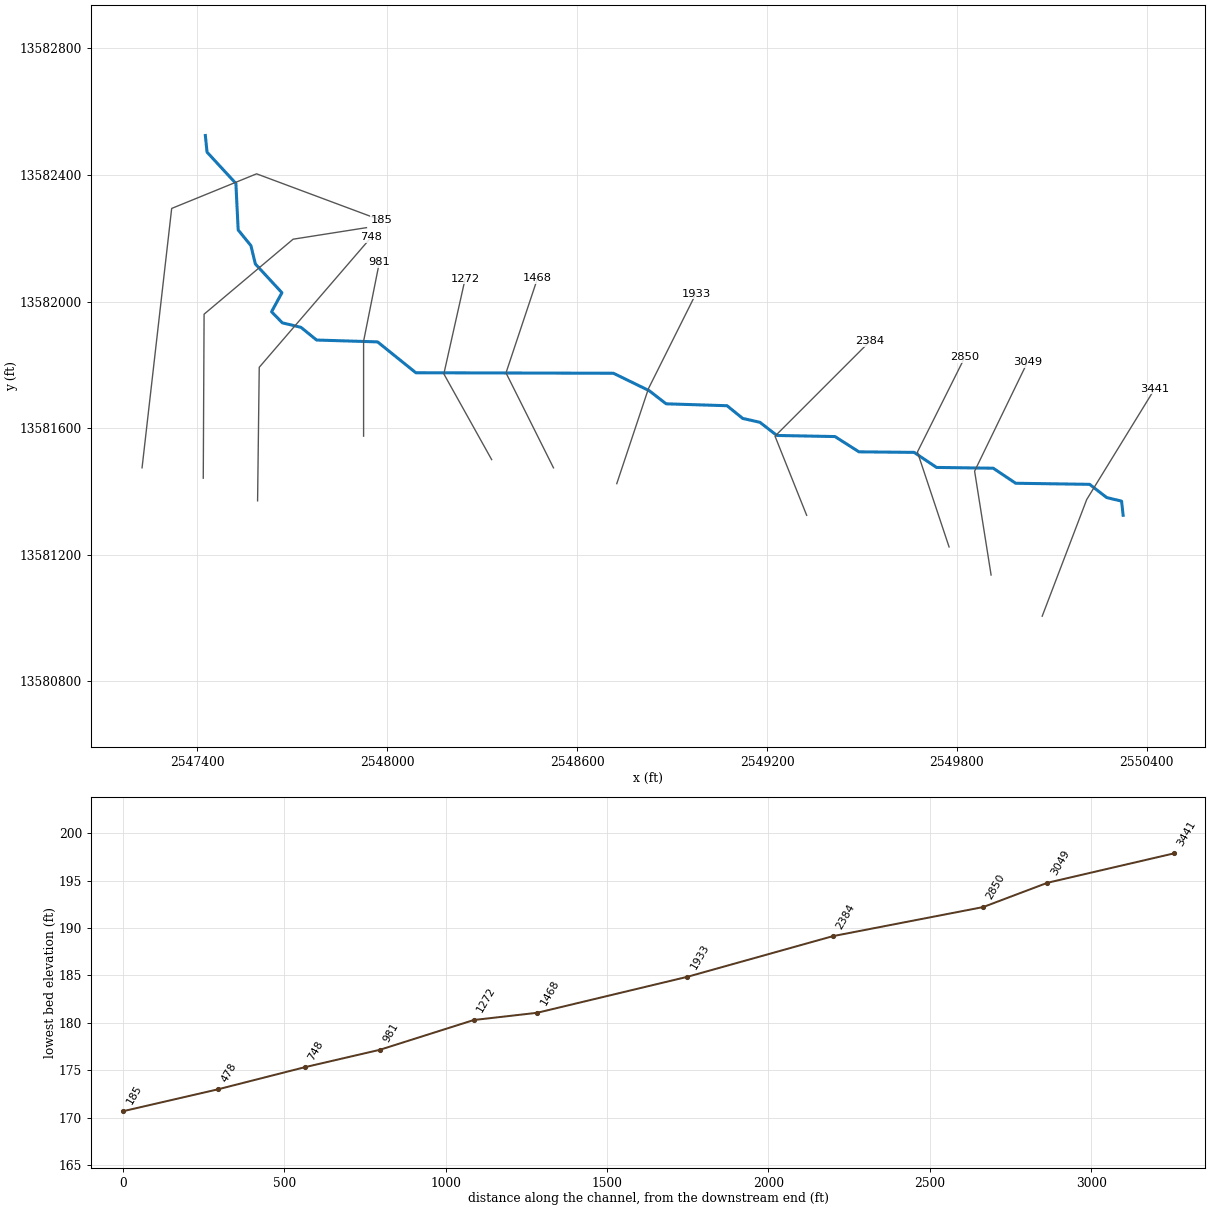
--- TRIB 1 TO CRITTENOON HOLLOW.prj (project) ---

Proj Title=TRIB 1 TO CRITTENOON HOLLOW Base Level Engineering
Current Plan=p01
Default Exp/Contr=0.3,0.1
English Units
Geom File=g01
Flow File=f01
Plan File=p01
Y Axis Title=Elevation
X Axis Title(PF)=Main Channel Distance
X Axis Title(XS)=Station
BEGIN DESCRIPTION:
TRIB 1 TO CRITTENOON HOLLOW
END DESCRIPTION:
DSS Export Rating Curves= 0
DSS Export Rating Curve Sorted= 0
DSS Export Volume Flow Curves= 0
DXF OffsetX= 0
DXF OffsetY= 0
DXF ScaleX= 1
DXF ScaleY= 10

--- TRIB 1 TO CRITTENOON HOLLOW.p01 (plan) ---

Plan Title=Multiple Run
Short Identifier=Multiple
Geom File=g01
Flow File=f01
Subcritical Flow
K Sum by GR= 0
Std Step Tol= 0.01
Critical Tol= 0.01
Num of Std Step Trials= 20
Max Error Tol= 0.3
Flow Tol Ratio= 0.001
Split Flow NTrial= 30
Split Flow Tol= 0.02
Split Flow Ratio= 0.02
Log Output Level= 0
Friction Slope Method= 1
Unsteady Friction Slope Method= 2
Unsteady Bridges Friction Slope Method= 1
Parabolic Critical Depth
Global Vel Dist=  1 , 1 , 1
Global Log Level= 0
CheckData=True
Encroach Param= -1, 0, 0, 0
BEGIN DESCRIPTION:
Multiple Run
END DESCRIPTION:

--- TRIB 1 TO CRITTENOON HOLLOW.f01 (steady flow) ---

Flow Title=Multiple
Number of Profiles=7
Profile Names=10-year,25-year,50-year,1pct_min,100-year,1pct_plu,500-year
River Rch & RM= TRIB 1 TO CRITTE,Reach-1,3441
     497     791    1055     683    1363    2720    2248
Boundary for River Rch & Prof#=TRIB 1 TO CRITTE,Reach-1,1
Up Type=0
Dn Type=3
Dn Slope=0.005
Boundary for River Rch & Prof#=TRIB 1 TO CRITTE,Reach-1,2
Up Type=0
Dn Type=3
Dn Slope=0.005
Boundary for River Rch & Prof#=TRIB 1 TO CRITTE,Reach-1,3
Up Type=0
Dn Type=3
Dn Slope=0.005
Boundary for River Rch & Prof#=TRIB 1 TO CRITTE,Reach-1,4
Up Type=0
Dn Type=3
Dn Slope=0.005
Boundary for River Rch & Prof#=TRIB 1 TO CRITTE,Reach-1,5
Up Type=0
Dn Type=3
Dn Slope=0.005
Boundary for River Rch & Prof#=TRIB 1 TO CRITTE,Reach-1,6
Up Type=0
Dn Type=3
Dn Slope=0.005
Boundary for River Rch & Prof#=TRIB 1 TO CRITTE,Reach-1,7
Up Type=0
Dn Type=3
Dn Slope=0.005

--- TRIB 1 TO CRITTENOON HOLLOW.g01 (geometry) ---

Geom Title=Existing Conditions

River Reach=TRIB 1 TO CRITTE,Reach-1
Reach XY= 30
      2550325.00     13581325.00      2550320.10     13581369.72
      2550273.00     13581381.04      2550219.10     13581422.79
      2549985.50     13581426.22      2549914.49     13581473.78
      2549735.51     13581476.22      2549664.49     13581523.78
      2549490.22     13581525.52      2549414.49     13581573.78
      2549230.93     13581577.24      2549177.18     13581618.88
      2549122.82     13581631.12      2549073.45     13581671.25
      2548880.93     13581677.24      2548827.18     13581718.88
      2548714.50     13581773.80      2548090.16     13581775.39
      2547969.14     13581872.93      2547776.55     13581878.75
      2547727.12     13581918.86      2547668.32     13581933.14
      2547634.19     13581968.05      2547666.98     13582028.32
      2547583.18     13582118.94      2547568.86     13582177.17
      2547528.76     13582226.56      2547521.46     13582373.53
      2547430.33     13582472.49      2547425.00     13582525.00

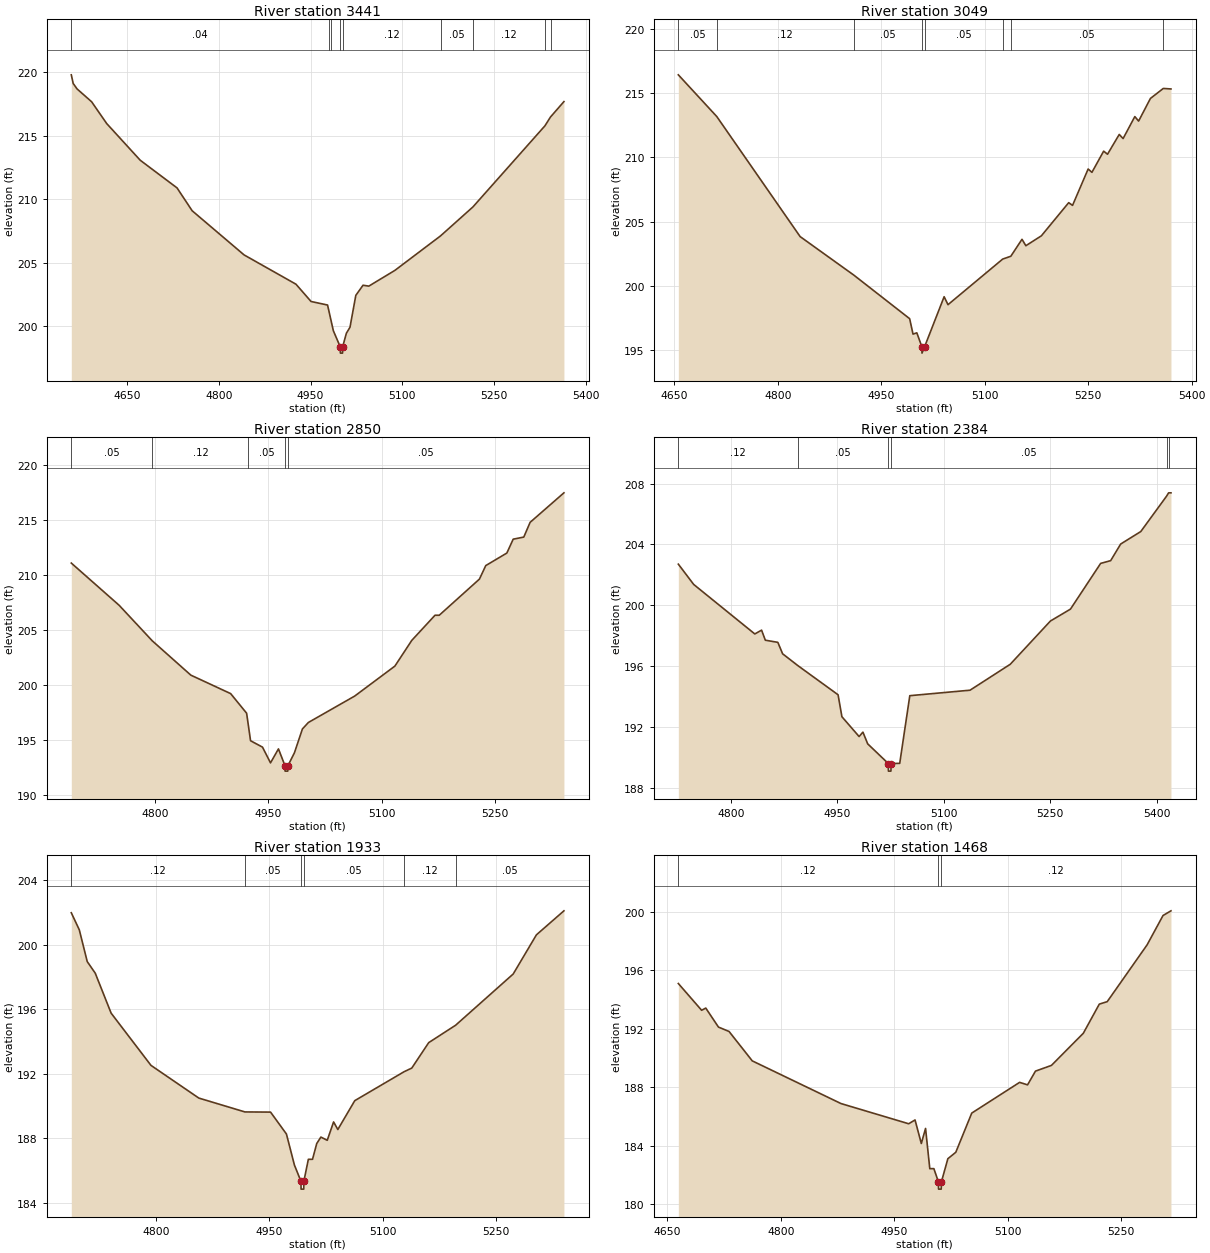
Type RM Length L Ch R = 1,3441,392,392,392
BEGIN DESCRIPTION:
TRIB 1 TO CRITTENOON HOLLOW 7.0
END DESCRIPTION:
XS GIS Cut Line= 3
      2550069.25     13581006.18      2550209.91     13581374.78
      2550424.99     13581724.98
#Sta/Elev= 30
  4558.8  219.79  4561.9  219.11  4568.2  218.68  4592.0  217.67  4616.7  215.95
  4671.5  213.06  4731.7  210.88  4756.4  209.08  4841.3  205.60  4926.2  203.29
  4950.8  201.93  4977.8  201.65  4980.2  201.14  4982.9  200.56  4987.3  199.62
  4998.5  198.36  4998.8  197.86  5002.3  197.86  5002.5  198.36  5008.6  199.43
  5014.5  199.90  5024.0  202.41  5035.8  203.21  5045.3  203.14  5087.9  204.38
  5162.6  207.10  5215.5  209.38  5333.2  215.77  5342.4  216.47  5364.3  217.68
#Mann=9,-1,0
  4558.8    0.04       0  4980.2    0.05       0  4982.9    0.12       0
  4998.5    0.05       0  5002.5    0.12       0  5162.6    0.05       0
  5215.5    0.12       0  5333.2    0.05       0  5342.4    0.12       0
Bank Sta=4998.5,5002.5
Exp/Cntr=0.3,0.1

Type RM Length L Ch R = 1,3049,199,199,199
BEGIN DESCRIPTION:
Mapping XS eeea00a5
END DESCRIPTION:
XS GIS Cut Line= 3
      2549907.78     13581136.30      2549855.69     13581464.47
      2550022.36     13581808.22
#Sta/Elev= 30
  4655.7  216.42  4711.5  213.17  4832.3  203.83  4910.2  200.83  4991.1  197.44
  4996.0  196.24  5001.5  196.34  5008.8  195.26  5009.0  194.76  5012.8  195.26
  5041.1  199.15  5046.7  198.53  5126.0  202.08  5137.8  202.30  5154.0  203.62
  5159.6  203.12  5182.1  203.89  5221.7  206.47  5227.3  206.26  5249.9  209.09
  5255.4  208.83  5272.4  210.48  5278.0  210.24  5295.0  211.78  5300.6  211.46
  5317.6  213.17  5323.1  212.82  5340.2  214.58  5358.9  215.36  5370.0  215.32
#Mann=8,-1,0
  4655.7    0.05       0  4711.5    0.12       0  4910.2    0.05       0
  5008.8    0.05       0  5012.8    0.05       0  5126.0    0.12       0
  5137.8    0.05       0  5358.9    0.12       0
Bank Sta=5008.8,5012.8
Exp/Cntr=0.3,0.1

Type RM Length L Ch R = 1,2850,466,466,466
BEGIN DESCRIPTION:
TRIB 1 TO CRITTENOON HOLLOW 6.0
END DESCRIPTION:
XS GIS Cut Line= 3
      2549774.99     13581225.03      2549675.00     13581525.00
      2549825.00     13581825.00
#Sta/Elev= 30
  4689.6  211.10  4752.8  207.27  4796.8  204.03  4847.7  200.92  4900.4  199.24
  4921.5  197.46  4923.9  196.31  4926.7  194.96  4942.5  194.38  4953.1  192.95
  4963.6  194.22  4972.2  192.70  4972.4  192.20  4975.9  192.20  4976.2  192.70
  4984.7  193.86  4995.3  196.03  5003.2  196.62  5064.5  199.02  5117.6  201.74
  5140.0  204.08  5170.7  206.36  5176.3  206.36  5229.4  209.64  5237.8  210.87
  5265.7  212.01  5274.1  213.27  5288.1  213.46  5296.5  214.80  5341.2  217.48
#Mann=5,-1,0
  4689.6    0.05       0  4796.8    0.12       0  4923.9    0.05       0
  4972.2    0.05       0  4976.2    0.05       0
Bank Sta=4972.2,4976.2
Exp/Cntr=0.3,0.1

Type RM Length L Ch R = 1,2384,451,451,451
BEGIN DESCRIPTION:
TRIB 1 TO CRITTENOON HOLLOW 5.0
END DESCRIPTION:
XS GIS Cut Line= 3
      2549325.01     13581324.97      2549225.00     13581575.00
      2549525.03     13581875.03
#Sta/Elev= 30
  4726.2  202.71  4747.8  201.38  4833.9  198.13  4843.4  198.38  4848.7  197.72
  4866.3  197.58  4873.0  196.83  4894.3  196.06  4951.1  194.14  4956.5  192.70
  4980.7  191.40  4986.1  191.69  4992.8  190.92  5021.8  189.63  5022.0  189.13
  5025.5  189.13  5025.8  189.63  5037.9  189.64  5052.1  194.08  5136.9  194.44
  5193.5  196.14  5250.1  198.98  5278.3  199.76  5320.8  202.76  5334.9  202.94
  5349.0  204.03  5377.3  204.85  5413.6  207.17  5416.5  207.39  5419.8  207.39
#Mann=6,-1,0
  4726.2    0.12       0  4894.3    0.05       0  5021.8    0.05       0
  5025.8    0.05       0  5413.6    0.04       0  5416.5    0.12       0
Bank Sta=5021.8,5025.8
Exp/Cntr=0.3,0.1

Type RM Length L Ch R = 1,1933,465,465,465
BEGIN DESCRIPTION:
TRIB 1 TO CRITTENOON HOLLOW 4.0
END DESCRIPTION:
XS GIS Cut Line= 3
      2548724.99     13581424.96      2548825.00     13581725.00
      2548975.01     13582025.02
#Sta/Elev= 30
  4688.3  201.99  4698.9  200.93  4709.4  198.96  4720.0  198.24  4741.0  195.76
  4793.7  192.52  4857.0  190.49  4918.0  189.63  4951.9  189.62  4972.9  188.26
  4983.5  186.33  4992.0  185.34  4992.3  184.84  4995.8  184.84  4996.0  185.34
  5001.9  186.69  5007.4  186.69  5013.0  187.67  5018.5  188.07  5026.9  187.87
  5035.3  189.01  5040.9  188.54  5063.3  190.33  5128.7  192.13  5138.7  192.35
  5161.1  193.93  5196.7  195.01  5272.9  198.19  5303.6  200.62  5340.0  202.11
#Mann=6,-1,0
  4688.3    0.12       0  4918.0    0.05       0  4992.0    0.05       0
  4996.0    0.05       0  5128.7    0.12       0  5196.7    0.05       0
Bank Sta=4992,4996
Exp/Cntr=0.3,0.1

Type RM Length L Ch R = 1,1468,196,196,196
BEGIN DESCRIPTION:
TRIB 1 TO CRITTENOON HOLLOW 3.0
END DESCRIPTION:
XS GIS Cut Line= 3
      2548525.00     13581475.00      2548375.00     13581775.00
      2548474.99     13582074.96
#Sta/Elev= 30
  4664.6  195.11  4695.4  193.28  4700.9  193.43  4717.7  192.13  4731.7  191.83
  4762.4  189.82  4879.8  186.90  4969.3  185.52  4977.7  185.78  4986.0  184.17
  4991.6  185.20  4997.2  182.45  5002.6  182.45  5008.6  181.55  5008.8  181.05
  5012.3  181.05  5012.6  181.55  5021.1  183.13  5031.6  183.57  5052.7  186.25
  5116.0  188.35  5126.5  188.18  5137.0  189.12  5158.1  189.51  5200.3  191.71
  5221.4  193.70  5231.9  193.87  5284.6  197.75  5305.7  199.76  5316.2  200.08
#Mann=3,-1,0
  4664.6    0.12       0  5008.6    0.05       0  5012.6    0.12       0
Bank Sta=5008.6,5012.6
Exp/Cntr=0.3,0.1

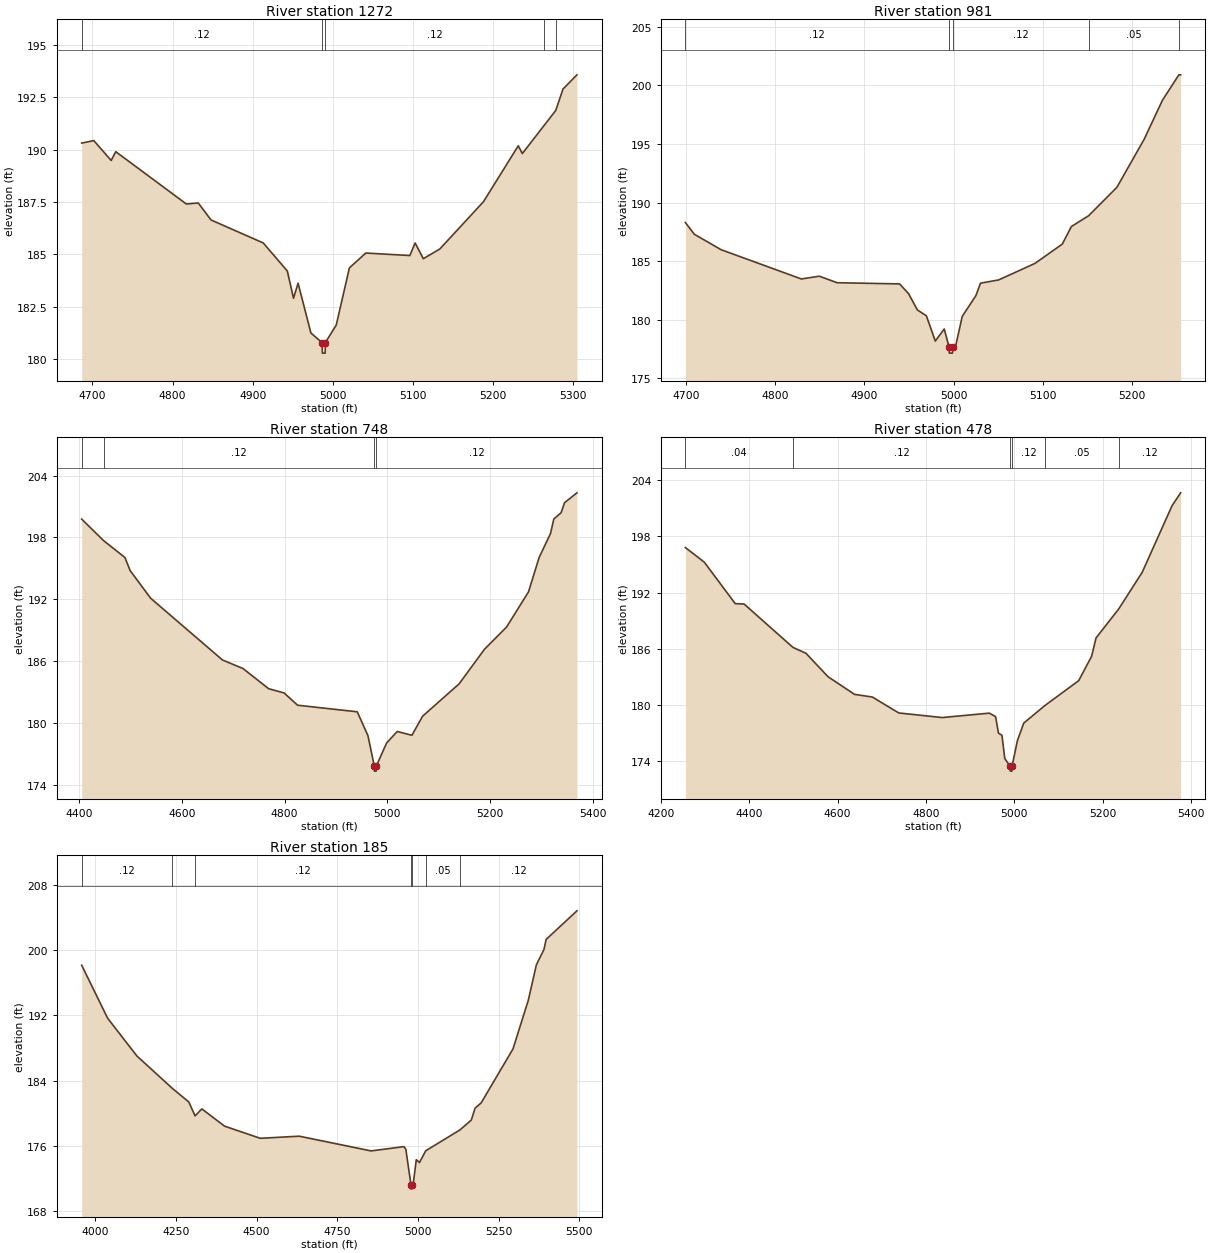
Type RM Length L Ch R = 1,1272,291,291,291
BEGIN DESCRIPTION:
Mapping XS 2f062867
END DESCRIPTION:
XS GIS Cut Line= 3
      2548329.63     13581500.97      2548178.61     13581771.76
      2548245.89     13582071.95
#Sta/Elev= 30
  4686.7  190.32  4701.8  190.44  4723.5  189.49  4729.2  189.91  4817.3  187.41
  4832.1  187.46  4848.0  186.65  4913.2  185.55  4943.2  184.21  4950.9  182.91
  4956.6  183.63  4972.6  181.25  4986.6  180.79  4986.9  180.29  4990.4  180.29
  4990.6  180.79  5004.2  181.63  5020.6  184.36  5041.1  185.07  5096.0  184.95
  5102.6  185.55  5112.8  184.80  5133.3  185.26  5187.8  187.52  5231.2  190.19
  5236.3  189.82  5263.2  191.15  5278.0  191.88  5287.0  192.90  5304.4  193.58
#Mann=5,-1,0
  4686.7    0.12       0  4986.6    0.05       0  4990.6    0.12       0
  5263.2    0.05       0  5278.0    0.12       0
Bank Sta=4986.6,4990.6
Exp/Cntr=0.3,0.1

Type RM Length L Ch R = 1,981,233,233,233
BEGIN DESCRIPTION:
TRIB 1 TO CRITTENOON HOLLOW 2.0
END DESCRIPTION:
XS GIS Cut Line= 3
      2547925.00     13581575.04      2547925.00     13581875.00
      2547975.00     13582124.99
#Sta/Elev= 30
  4699.6  188.30  4709.6  187.30  4739.6  185.98  4829.6  183.48  4849.6  183.72
  4869.6  183.16  4939.6  183.06  4949.6  182.23  4959.6  180.83  4969.6  180.34
  4979.6  178.18  4989.6  179.21  4995.1  177.65  4995.3  177.15  4998.8  177.15
  4999.1  177.65  5002.1  177.65  5009.8  180.29  5025.1  182.06  5030.2  183.12
  5050.6  183.40  5091.3  184.81  5121.9  186.46  5132.1  187.96  5151.4  188.88
  5183.1  191.31  5213.7  195.42  5234.1  198.74  5252.5  200.91  5254.5  200.91
#Mann=5,-1,0
  4699.6    0.12       0  4995.1    0.05       0  4999.1    0.12       0
  5151.4    0.05       0  5252.5    0.12       0
Bank Sta=4995.1,4999.1
Exp/Cntr=0.3,0.1

Type RM Length L Ch R = 1,748,270,270,270
BEGIN DESCRIPTION:
Mapping XS 4d9cee3b
END DESCRIPTION:
XS GIS Cut Line= 3
      2547590.07     13581370.73      2547595.28     13581792.60
      2547949.45     13582204.06
#Sta/Elev= 30
  4404.6  199.78  4447.3  197.69  4488.9  196.05  4498.9  194.79  4538.9  192.10
  4678.9  186.10  4718.9  185.27  4768.9  183.31  4798.9  182.90  4825.2  181.71
  4941.4  181.07  4962.3  178.75  4974.6  175.81  4974.8  175.31  4978.3  175.31
  4978.6  175.81  4998.5  178.03  5019.3  179.16  5047.9  178.79  5068.7  180.64
  5140.0  183.79  5189.4  187.15  5232.2  189.29  5275.0  192.71  5295.8  196.06
  5317.8  198.36  5324.4  199.79  5338.6  200.40  5345.2  201.37  5369.4  202.33
#Mann=4,-1,0
  4404.6    0.04       0  4447.3    0.12       0  4974.6    0.05       0
  4978.6    0.12       0
Bank Sta=4974.6,4978.6
Exp/Cntr=0.3,0.1

Type RM Length L Ch R = 1,478,293,293,293
BEGIN DESCRIPTION:
Mapping XS faaec516
END DESCRIPTION:
XS GIS Cut Line= 4
      2547418.42     13581442.23      2547421.02     13581960.41
      2547702.27     13582197.39      2547934.06     13582233.85
#Sta/Elev= 30
  4255.8  196.80  4298.6  195.24  4368.6  190.82  4388.6  190.78  4499.1  186.16
  4528.6  185.53  4578.6  183.03  4638.6  181.15  4678.6  180.87  4738.6  179.17
  4836.7  178.68  4943.4  179.15  4957.7  178.78  4964.2  177.02  4972.0  176.79
  4978.5  174.31  4990.8  173.47  4991.0  172.97  4994.5  172.97  4994.8  173.47
  5007.1  176.23  5021.4  178.09  5069.5  179.97  5145.7  182.61  5174.9  185.20
  5185.0  187.17  5235.8  190.22  5289.3  194.15  5357.1  201.27  5376.4  202.63
#Mann=6,-1,0
  4255.8    0.04       0  4499.1    0.12       0  4990.8    0.05       0
  4994.8    0.12       0  5069.5    0.05       0  5235.8    0.12       0
Bank Sta=4990.8,4994.8
Exp/Cntr=0.3,0.1

Type RM Length L Ch R = 1,185,0,0,0
BEGIN DESCRIPTION:
TRIB 1 TO CRITTENOON HOLLOW 1.0
END DESCRIPTION:
XS GIS Cut Line= 4
      2547225.00     13581475.01      2547318.61     13582294.59
      2547586.84     13582403.96      2547980.67     13582257.09
#Sta/Elev= 30
  3957.7  198.16  4038.2  191.65  4128.8  187.02  4238.7  183.04  4289.8  181.37
  4309.1  179.66  4330.1  180.52  4400.6  178.40  4511.3  176.91  4632.0  177.17
  4854.8  175.36  4956.4  175.89  4962.3  175.57  4978.4  171.17  4978.7  170.67
  4982.4  171.17  4985.8  171.50  4994.7  174.28  5004.5  173.93  5024.0  175.38
  5129.6  177.93  5165.2  179.15  5177.0  180.62  5195.6  181.25  5294.4  187.88
  5341.8  193.85  5366.8  198.20  5390.5  200.11  5397.1  201.33  5492.6  204.84
#Mann=7,-1,0
  3957.7    0.12       0  4238.7    0.04       0  4309.1    0.12       0
  4978.4    0.05       0  4982.4    0.12       0  5024.0    0.05       0
  5129.6    0.12       0
Bank Sta=4978.4,4982.4
Exp/Cntr=0.3,0.1

Chan Stop Cuts=-1