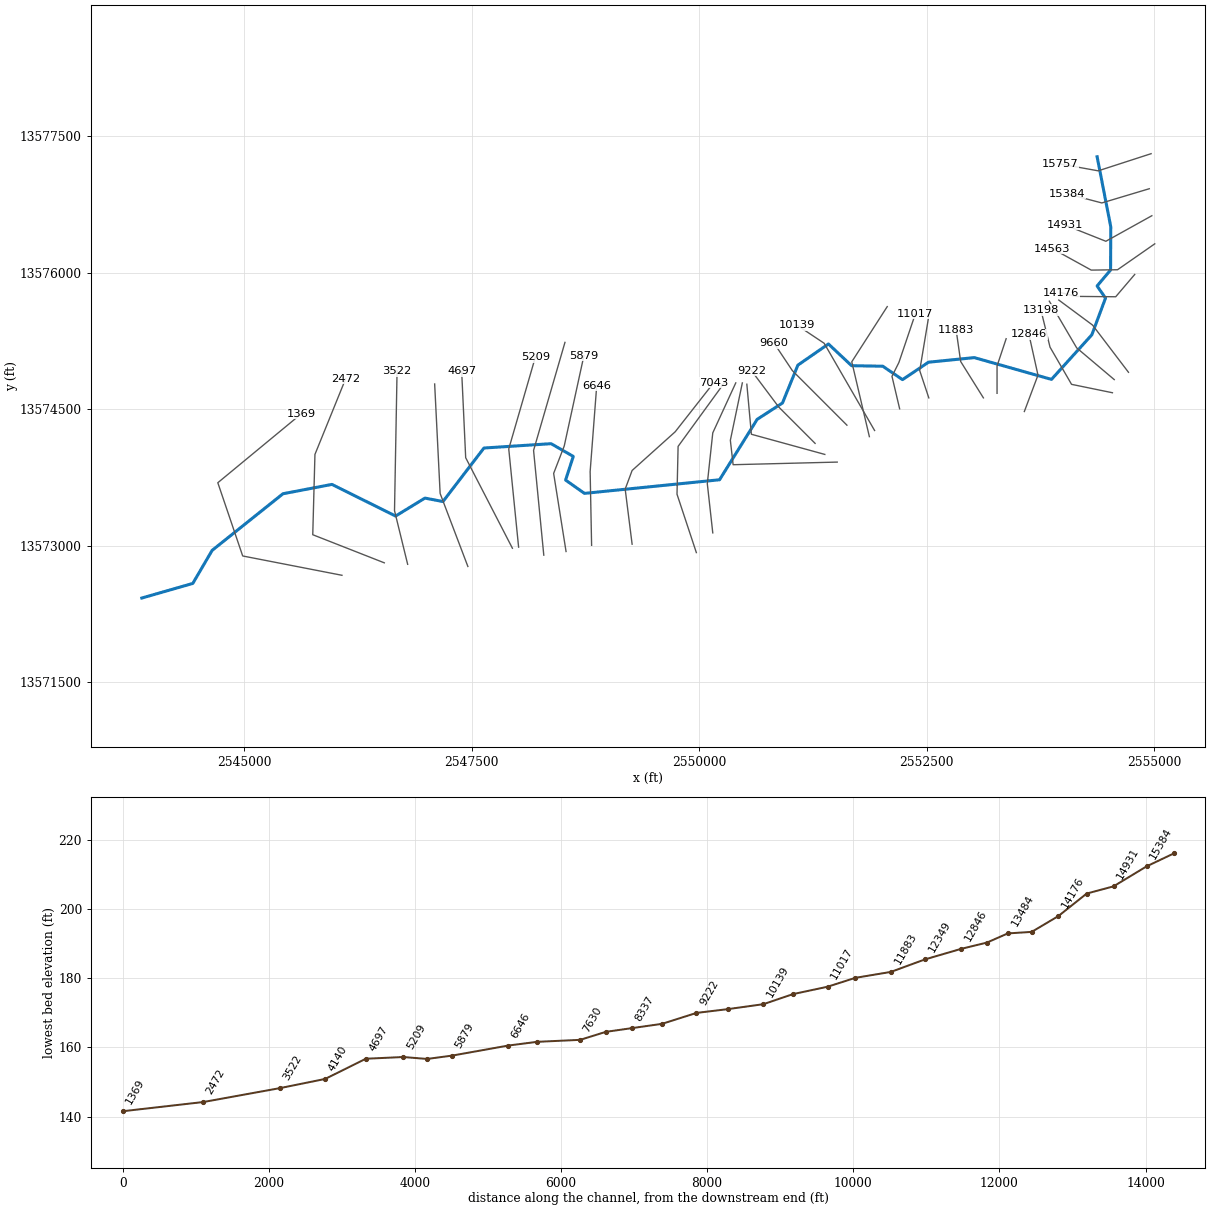
--- TRIB 1 TO IRISH CREEK.prj (project) ---

Proj Title=TRIB 1 TO IRISH CREEK Base Level Engineering
Current Plan=p01
Default Exp/Contr=0.3,0.1
English Units
Geom File=g01
Flow File=f01
Plan File=p01
BEGIN DESCRIPTION:
TRIB 1 TO IRISH CREEK
END DESCRIPTION:

--- TRIB 1 TO IRISH CREEK.p01 (plan) ---

Plan Title=Multiple Run
Short Identifier=Multiple
Geom File=g01
Flow File=f01
Subcritical Flow
K Sum by GR= 0
Std Step Tol= 0.01
Critical Tol= 0.01
Num of Std Step Trials= 20
Max Error Tol= 0.3
Flow Tol Ratio= 0.001
Split Flow NTrial= 30
Split Flow Tol= 0.02
Split Flow Ratio= 0.02
Log Output Level= 0
Friction Slope Method= 1
Unsteady Friction Slope Method= 2
Unsteady Bridges Friction Slope Method= 1
Parabolic Critical Depth
Global Vel Dist=  1 , 1 , 1
Global Log Level= 0
CheckData=True
Encroach Param= -1, 0, 0, 0
BEGIN DESCRIPTION:
Multiple Run
END DESCRIPTION:

--- TRIB 1 TO IRISH CREEK.f01 (steady flow) ---

Flow Title=Multiple
Number of Profiles=7
Profile Names=10-year,25-year,50-year,1pct_min,100-year,1pct_plu,500-year
River Rch & RM= TRIB 1 TO IRISH ,Reach-1,15757
     260     395     509     320     639    1275     991
River Rch & RM= TRIB 1 TO IRISH ,Reach-1,13484
     756    1227    1655    1082    2159    4308    3634
River Rch & RM= TRIB 1 TO IRISH ,Reach-1,12846
     835    1361    1842    1207    2408    4805    4075
River Rch & RM= TRIB 1 TO IRISH ,Reach-1,10139
    1254    2089    2868    1904    3800    7581    6603
River Rch & RM= TRIB 1 TO IRISH ,Reach-1,7982
    1654    2775    3827    2548    5084   10144    8889
River Rch & RM= TRIB 1 TO IRISH ,Reach-1,5879
    1825    3076    4255    2841    5669   11312    9969
River Rch & RM= TRIB 1 TO IRISH ,Reach-1,5535
    1930    3256    4507    3010    6006   11983   10568
Boundary for River Rch & Prof#=TRIB 1 TO IRISH ,Reach-1,1
Up Type=0
Dn Type=3
Dn Slope=0.005
Boundary for River Rch & Prof#=TRIB 1 TO IRISH ,Reach-1,2
Up Type=0
Dn Type=3
Dn Slope=0.005
Boundary for River Rch & Prof#=TRIB 1 TO IRISH ,Reach-1,3
Up Type=0
Dn Type=3
Dn Slope=0.005
Boundary for River Rch & Prof#=TRIB 1 TO IRISH ,Reach-1,4
Up Type=0
Dn Type=3
Dn Slope=0.005
Boundary for River Rch & Prof#=TRIB 1 TO IRISH ,Reach-1,5
Up Type=0
Dn Type=3
Dn Slope=0.005
Boundary for River Rch & Prof#=TRIB 1 TO IRISH ,Reach-1,6
Up Type=0
Dn Type=3
Dn Slope=0.005
Boundary for River Rch & Prof#=TRIB 1 TO IRISH ,Reach-1,7
Up Type=0
Dn Type=3
Dn Slope=0.005

--- TRIB 1 TO IRISH CREEK.g01 (geometry) ---

Geom Title=Existing Conditions

River Reach=TRIB 1 TO IRISH ,Reach-1
Reach XY= 30
      2554375.00     13577275.00      2554524.96     13576504.97
      2554522.94     13576030.85      2554374.53     13575854.84
      2554467.39     13575721.67      2554317.24     13575318.79
      2553873.38     13574828.12      2553025.01     13575067.47
      2552521.68     13575016.96      2552235.64     13574825.55
      2552019.07     13574972.76      2551676.46     13574978.54
      2551421.80     13575217.42      2551085.78     13574984.68
      2550916.86     13574568.94      2550638.20     13574388.73
      2550225.00     13573725.00      2548740.27     13573575.37
      2548532.75     13573721.58      2548617.42     13573981.59
      2548373.53     13574121.46      2547635.50     13574073.80
      2547184.79     13573485.43      2546987.13     13573523.53
      2546664.46     13573326.08      2545964.50     13573673.78
      2545426.58     13573571.17      2544648.07     13572948.85
      2544435.17     13572585.32      2543875.00     13572425.00

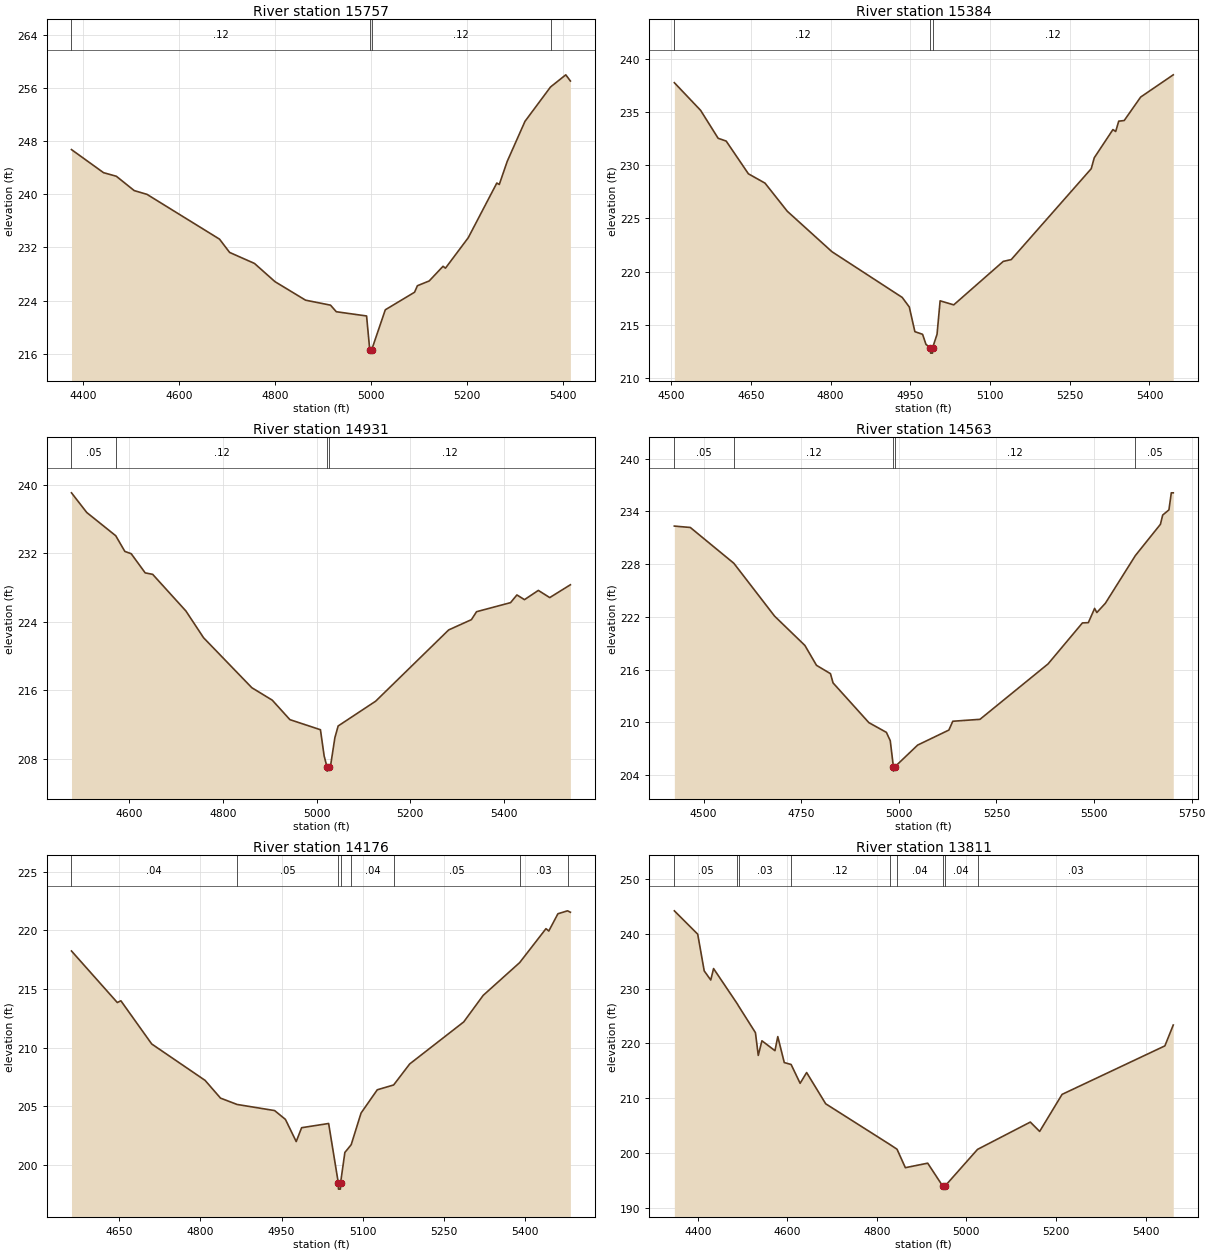
Type RM Length L Ch R = 1,15757,373,373,373
BEGIN DESCRIPTION:
Mapping XS a66b5021
END DESCRIPTION:
XS GIS Cut Line= 3
      2554968.47     13577308.97      2554386.75     13577120.42
      2553965.51     13577196.64
#Sta/Elev= 30
  4376.1  246.75  4442.9  243.27  4469.6  242.73  4506.8  240.57  4533.5  240.00
  4684.6  233.25  4705.6  231.25  4757.4  229.59  4800.2  226.84  4863.9  224.05
  4915.9  223.30  4927.9  222.31  4991.0  221.67  4997.6  216.57  4997.8  216.07
  5001.6  216.57  5030.0  222.60  5091.0  225.25  5096.9  226.23  5121.5  226.95
  5150.3  229.16  5155.4  228.88  5202.8  233.46  5262.4  241.71  5267.5  241.49
  5284.1  244.98  5321.0  251.00  5374.3  256.19  5406.1  258.02  5415.7  257.09
#Mann=4,-1,0
  4376.1    0.12       0  4997.6    0.05       0  5001.6    0.12       0
  5374.3    0.04       0
Bank Sta=4997.6,5001.6
Exp/Cntr=0.3,0.1

Type RM Length L Ch R = 1,15384,453,453,453
BEGIN DESCRIPTION:
Mapping XS 9fd068d3
END DESCRIPTION:
XS GIS Cut Line= 3
      2554948.40     13576923.86      2554426.86     13576767.40
      2554045.74     13576867.69
#Sta/Elev= 30
  4506.2  237.77  4555.6  235.17  4588.6  232.54  4603.7  232.28  4645.5  229.20
  4676.8  228.32  4718.6  225.68  4802.7  221.87  4934.9  217.57  4948.2  216.67
  4958.7  214.35  4973.2  214.10  4979.6  213.15  4988.0  212.83  4988.3  212.33
  4991.8  212.33  4992.0  212.83  5000.4  214.10  5006.2  217.25  5031.8  216.87
  5125.0  220.96  5140.0  221.13  5290.5  229.68  5296.2  230.71  5331.3  233.36
  5336.5  233.18  5342.2  234.15  5352.5  234.21  5383.5  236.42  5444.8  238.51
#Mann=3,-1,0
  4506.2    0.12       0  4988.0    0.05       0  4992.0    0.12       0
Bank Sta=4988,4992
Exp/Cntr=0.3,0.1

Type RM Length L Ch R = 1,14931,368,368,368
BEGIN DESCRIPTION:
Mapping XS b086e987
END DESCRIPTION:
XS GIS Cut Line= 3
      2554976.47     13576627.00      2554470.99     13576346.18
      2554018.87     13576526.23
#Sta/Elev= 30
  4476.9  239.09  4509.5  236.79  4571.4  234.07  4590.8  232.24  4604.4  231.97
  4634.2  229.73  4650.2  229.56  4721.2  225.27  4758.9  222.14  4861.9  216.30
  4905.4  214.85  4943.1  212.57  5008.3  211.39  5016.2  208.32  5022.3  207.05
  5022.6  206.55  5026.3  207.05  5030.0  207.22  5039.1  210.46  5046.1  211.83
  5126.2  214.73  5282.0  223.06  5330.5  224.26  5341.5  225.19  5414.1  226.25
  5427.6  227.15  5443.8  226.60  5473.4  227.68  5497.7  226.84  5541.8  228.34
#Mann=4,-1,0
  4476.9    0.05       0  4571.4    0.12       0  5022.3    0.05       0
  5026.3    0.12       0
Bank Sta=5022.3,5026.3
Exp/Cntr=0.3,0.1

Type RM Length L Ch R = 1,14563,387,387,387
BEGIN DESCRIPTION:
Mapping XS 45d876c0
END DESCRIPTION:
XS GIS Cut Line= 4
      2555008.56     13576318.12      2554599.36     13576033.28
      2554310.53     13576029.27      2553881.29     13576265.95
#Sta/Elev= 30
  4425.3  232.32  4466.2  232.16  4577.7  228.09  4682.0  222.08  4759.6  218.75
  4789.3  216.49  4825.1  215.54  4831.7  214.49  4923.5  209.97  4968.2  208.87
  4978.2  207.92  4986.2  204.96  4986.5  204.46  4990.2  204.96  5048.3  207.42
  5128.3  209.13  5138.3  210.13  5208.0  210.35  5382.3  216.65  5470.3  221.31
  5485.4  221.34  5501.5  222.96  5507.2  222.49  5529.0  223.54  5605.9  228.97
  5670.0  232.52  5675.8  233.57  5691.8  234.16  5697.9  236.10  5702.9  236.10
#Mann=5,-1,0
  4425.3    0.05       0  4577.7    0.12       0  4986.2    0.05       0
  4990.2    0.12       0  5605.9    0.05       0
Bank Sta=4986.2,4990.2
Exp/Cntr=0.3,0.1

Type RM Length L Ch R = 1,14176,365,365,365
BEGIN DESCRIPTION:
Mapping XS fb07b6e6
END DESCRIPTION:
XS GIS Cut Line= 4
      2554787.91     13575981.14      2554579.30     13575736.42
      2554138.03     13575740.44      2553982.61     13575780.29
#Sta/Elev= 30
  4561.3  218.24  4646.1  213.85  4652.7  214.00  4709.8  210.32  4808.6  207.22
  4837.1  205.71  4867.8  205.17  4937.2  204.65  4957.2  203.90  4977.2  202.01
  4987.2  203.19  5037.2  203.55  5055.2  198.46  5055.4  197.96  5058.9  197.96
  5059.2  198.46  5067.2  201.08  5078.9  201.74  5097.2  204.44  5127.2  206.42
  5157.5  206.83  5187.2  208.62  5287.2  212.20  5323.2  214.46  5390.7  217.25
  5439.4  220.14  5444.6  219.94  5461.5  221.41  5479.3  221.66  5484.6  221.54
#Mann=8,-1,0
  4561.3    0.04       0  4867.8    0.05       0  5055.2    0.05       0
  5059.2    0.05       0  5078.9    0.04       0  5157.5    0.05       0
  5390.7    0.03       0  5479.3    0.05       0
Bank Sta=5055.2,5059.2
Exp/Cntr=0.3,0.1

Type RM Length L Ch R = 1,13811,327,327,327
BEGIN DESCRIPTION:
TRIB 1 TO IRISH CREEK 24.0
END DESCRIPTION:
XS GIS Cut Line= 3
      2554719.73     13574906.01      2554325.00     13575425.00
      2553953.70     13575700.17
#Sta/Elev= 30
  4347.8  244.23  4400.0  239.96  4414.5  233.26  4429.1  231.59  4435.4  233.68
  4488.7  227.20  4491.1  226.86  4528.9  221.97  4535.2  217.82  4543.4  220.49
  4572.5  218.68  4578.8  221.25  4593.3  216.51  4608.6  216.16  4628.7  212.72
  4643.2  214.69  4685.8  208.98  4828.4  201.58  4845.1  200.68  4863.7  197.31
  4913.6  198.13  4947.6  193.89  4947.8  193.39  4951.6  193.89  5024.9  200.65
  5142.8  205.64  5163.6  203.93  5213.7  210.70  5443.3  219.56  5462.0  223.37
#Mann=9,-1,0
  4347.8    0.05       0  4488.7    0.12       0  4491.1    0.03       0
  4608.6    0.12       0  4828.4    0.03       0  4845.1    0.04       0
  4947.6    0.04       0  4951.6    0.04       0  5024.9    0.03       0
Bank Sta=4947.6,4951.6
Exp/Cntr=0.3,0.1

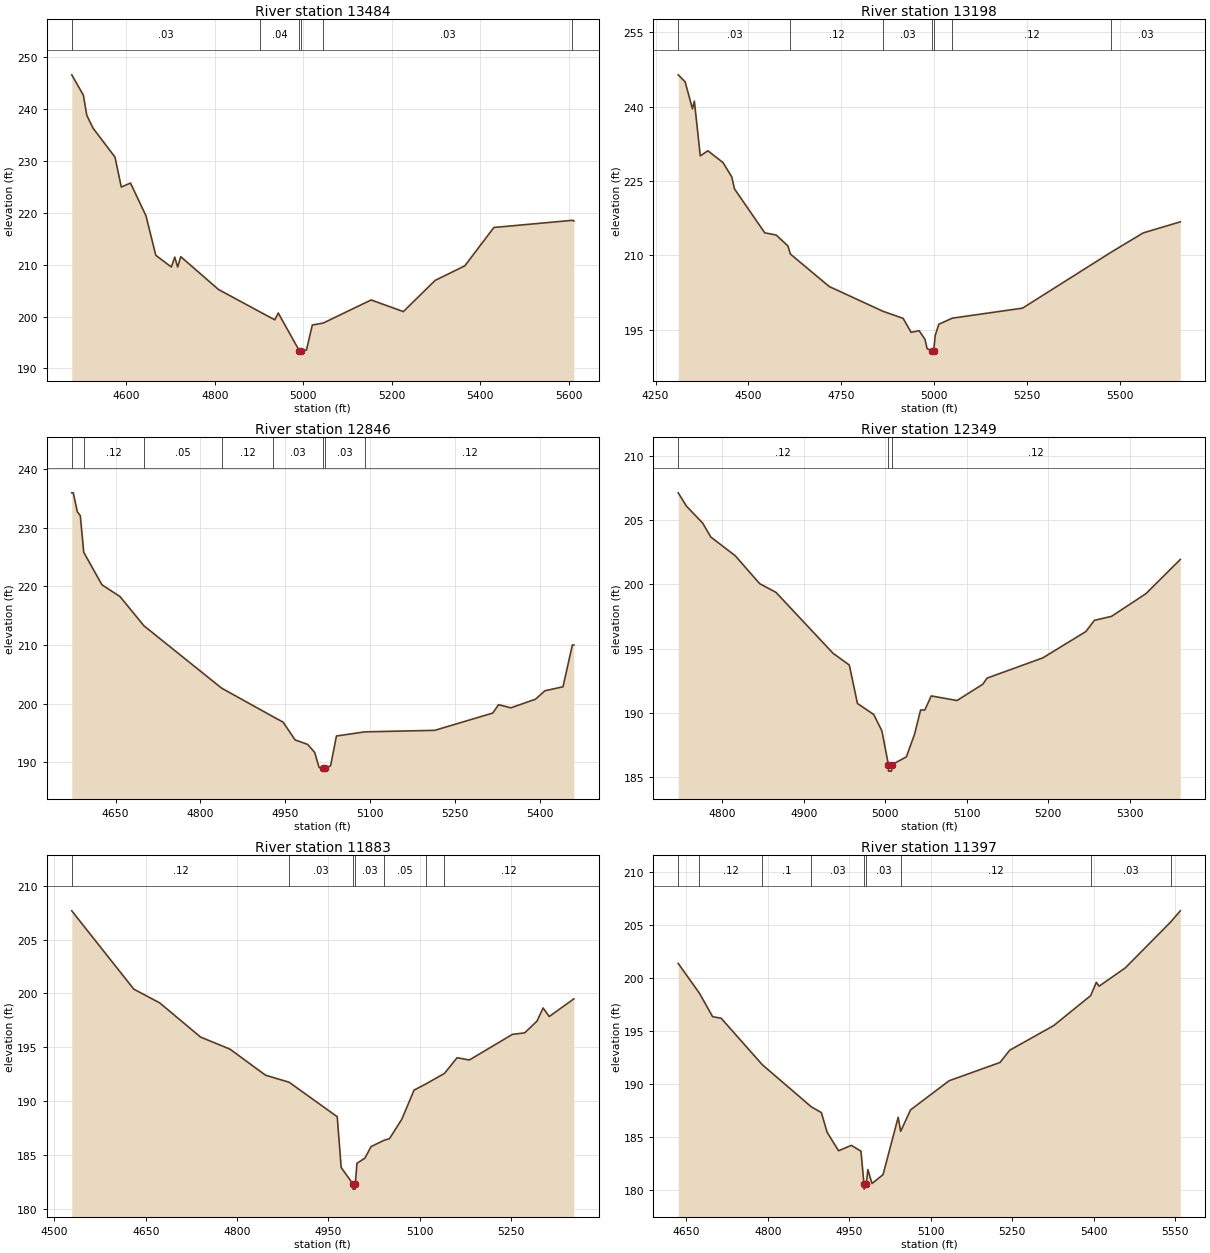
Type RM Length L Ch R = 1,13484,286,286,286
BEGIN DESCRIPTION:
Mapping XS 145281f3
END DESCRIPTION:
XS GIS Cut Line= 3
      2554563.24     13574825.81      2554150.07     13575174.80
      2553849.59     13575687.62
#Sta/Elev= 30
  4476.4  246.55  4502.6  242.64  4510.4  238.75  4524.6  236.27  4574.1  230.71
  4588.4  224.94  4609.2  225.70  4644.3  219.38  4666.4  211.79  4701.5  209.54
  4709.3  211.44  4715.8  209.53  4722.8  211.53  4808.1  205.21  4903.1  200.84
  4935.5  199.36  4943.3  200.67  4990.7  193.45  4991.0  192.95  4994.7  193.45
  5007.0  193.54  5020.3  198.37  5044.6  198.73  5153.3  203.19  5226.1  200.95
  5297.9  206.95  5365.2  209.77  5430.8  217.15  5608.5  218.53  5611.6  218.41
#Mann=6,-1,0
  4476.4    0.03       0  4903.1    0.04       0  4990.7    0.04       0
  4994.7    0.04       0  5044.6    0.03       0  5608.5    0.05       0
Bank Sta=4990.7,4994.7
Exp/Cntr=0.3,0.1

Type RM Length L Ch R = 1,13198,352,352,352
BEGIN DESCRIPTION:
Mapping XS cb327443
END DESCRIPTION:
XS GIS Cut Line= 4
      2554543.18     13574681.39      2554093.90     13574773.65
      2553857.22     13575182.83      2553757.18     13575591.00
#Sta/Elev= 30
  4311.2  246.41  4329.8  244.99  4349.5  239.56  4354.6  241.10  4370.6  230.07
  4391.0  231.10  4431.8  228.71  4455.4  225.82  4462.5  223.43  4544.1  214.56
  4574.8  214.11  4606.5  211.92  4613.2  210.27  4717.7  203.73  4862.6  198.73
  4916.6  197.31  4938.2  194.49  4959.7  194.82  4975.5  193.08  4981.2  191.19
  4995.0  190.80  4995.3  190.30  4999.0  190.80  5002.8  193.81  5012.8  196.13
  5049.1  197.35  5238.1  199.37  5476.0  210.62  5562.9  214.54  5662.8  216.77
#Mann=7,-1,0
  4311.2    0.03       0  4613.2    0.12       0  4862.6    0.03       0
  4995.0    0.03       0  4999.0    0.03       0  5049.1    0.12       0
  5476.0    0.03       0
Bank Sta=4995,4999
Exp/Cntr=0.3,0.1

Type RM Length L Ch R = 1,12846,497,497,497
BEGIN DESCRIPTION:
TRIB 1 TO IRISH CREEK 22.0
END DESCRIPTION:
XS GIS Cut Line= 3
      2553575.00     13574474.99      2553725.00     13574875.00
      2553625.00     13575325.01
#Sta/Elev= 30
  4572.4  235.97  4575.1  235.97  4582.2  232.76  4587.5  232.07  4593.6  225.82
  4625.8  220.28  4657.9  218.26  4700.0  213.29  4837.6  202.64  4928.7  197.77
  4946.2  196.85  4967.6  193.81  4989.8  193.05  5002.2  191.67  5009.9  189.12
  5016.8  188.99  5017.1  188.49  5020.8  188.99  5030.3  189.41  5040.6  194.48
  5091.0  195.19  5214.7  195.45  5317.2  198.40  5327.4  199.83  5349.2  199.29
  5392.7  200.76  5409.4  202.20  5441.4  202.88  5458.0  210.02  5460.6  210.02
#Mann=8,-1,0
  4572.4    0.03       0  4593.6    0.12       0  4700.0    0.05       0
  4837.6    0.12       0  4928.7    0.03       0  5016.8    0.03       0
  5020.8    0.03       0  5091.0    0.12       0
Bank Sta=5016.8,5020.8
Exp/Cntr=0.3,0.1

Type RM Length L Ch R = 1,12349,466,466,466
BEGIN DESCRIPTION:
TRIB 1 TO IRISH CREEK 21.0
END DESCRIPTION:
XS GIS Cut Line= 3
      2553275.00     13574674.97      2553275.00     13574975.00
      2553375.01     13575275.04
#Sta/Elev= 30
  4745.7  207.15  4755.7  206.12  4775.7  204.79  4785.7  203.70  4815.7  202.24
  4845.7  200.06  4865.7  199.38  4935.7  194.63  4955.7  193.71  4965.7  190.71
  4985.7  189.85  4995.7  188.57  5003.7  185.93  5003.9  185.43  5007.5  185.43
  5007.8  185.93  5025.7  186.54  5035.7  188.29  5043.2  190.20  5048.4  190.20
  5056.3  191.30  5087.9  190.94  5119.5  192.21  5124.8  192.69  5193.3  194.27
  5246.0  196.32  5256.6  197.20  5277.6  197.51  5319.8  199.28  5362.0  201.95
#Mann=3,-1,0
  4745.7    0.12       0  5003.7    0.05       0  5007.8    0.12       0
Bank Sta=5003.7,5007.8
Exp/Cntr=0.3,0.1

Type RM Length L Ch R = 1,11883,486,486,486
BEGIN DESCRIPTION:
TRIB 1 TO IRISH CREEK 20.0
END DESCRIPTION:
XS GIS Cut Line= 3
      2553124.99     13574625.01      2552875.00     13575025.00
      2552825.01     13575374.96
#Sta/Elev= 30
  4528.4  207.68  4630.4  200.40  4672.8  199.13  4740.1  195.95  4788.4  194.83
  4846.8  192.41  4885.7  191.75  4964.7  188.55  4971.2  183.83  4990.3  182.32
  4990.6  181.82  4994.2  181.82  4994.5  182.32  4997.1  184.22  5010.2  184.70
  5020.3  185.77  5041.7  186.36  5050.6  186.51  5070.8  188.31  5091.0  191.02
  5110.3  191.59  5140.9  192.57  5161.7  194.03  5181.9  193.82  5252.6  196.20
  5272.8  196.34  5293.0  197.43  5303.1  198.65  5313.2  197.86  5353.6  199.50
#Mann=7,-1,0
  4528.4    0.12       0  4885.7    0.03       0  4990.3    0.03       0
  4994.5    0.03       0  5041.7    0.05       0  5110.3    0.03       0
  5140.9    0.12       0
Bank Sta=4990.3,4994.5
Exp/Cntr=0.3,0.1

Type RM Length L Ch R = 1,11397,380,380,380
BEGIN DESCRIPTION:
TRIB 1 TO IRISH CREEK 19.0
END DESCRIPTION:
XS GIS Cut Line= 3
      2552525.01     13574624.96      2552425.00     13574925.00
      2552524.99     13575524.96
#Sta/Elev= 30
  4635.1  201.35  4674.2  198.54  4698.4  196.34  4714.2  196.19  4789.7  191.83
  4880.0  187.86  4898.7  187.31  4909.2  185.47  4930.3  183.72  4953.9  184.23
  4971.6  183.68  4977.1  180.61  4977.4  180.11  4981.4  180.61  4984.3  181.95
  4991.9  180.64  5012.2  181.47  5040.1  186.87  5044.7  185.55  5062.9  187.57
  5133.9  190.31  5227.6  192.03  5245.4  193.18  5326.5  195.50  5394.5  198.32
  5405.0  199.57  5410.1  199.21  5458.3  200.93  5541.7  205.24  5559.6  206.30
#Mann=9,-1,0
  4635.1     0.1       0  4674.2    0.12       0  4789.7     0.1       0
  4880.0    0.03       0  4977.1    0.03       0  4981.4    0.03       0
  5044.7    0.12       0  5394.5    0.03       0  5541.7    0.12       0
Bank Sta=4977.1,4981.4
Exp/Cntr=0.3,0.1

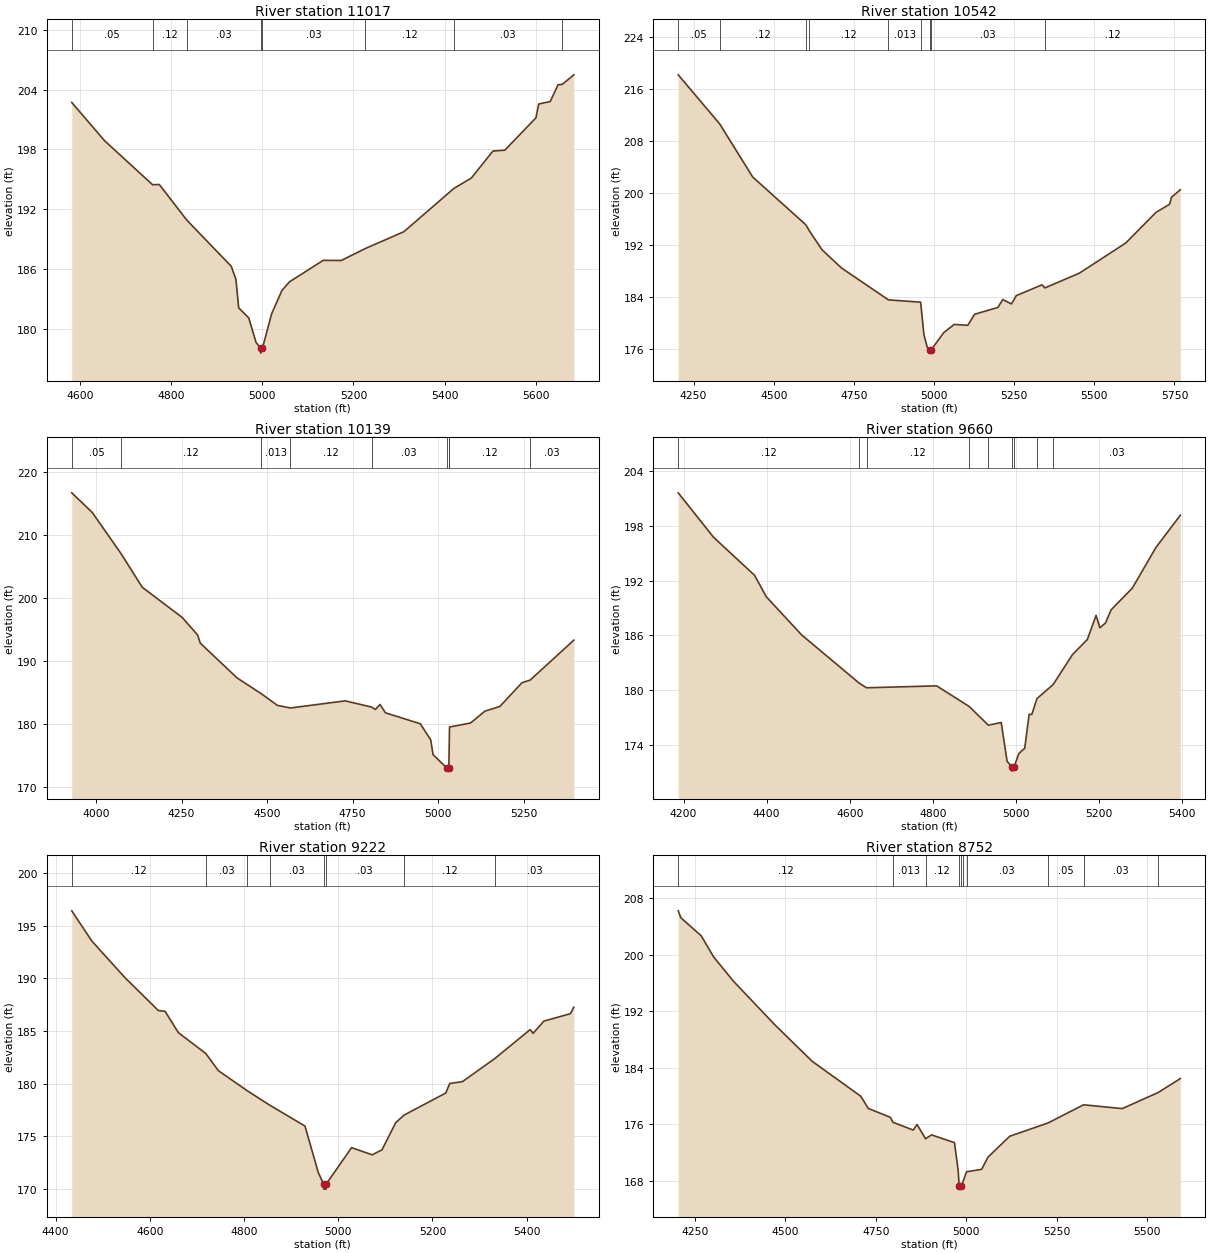
Type RM Length L Ch R = 1,11017,475,475,475
BEGIN DESCRIPTION:
Mapping XS b8659f24
END DESCRIPTION:
XS GIS Cut Line= 4
      2552204.46     13574504.85      2552120.21     13574861.90
      2552196.43     13575014.34      2552376.94     13575547.84
#Sta/Elev= 30
  4582.5  202.72  4654.6  198.87  4759.6  194.46  4774.4  194.48  4834.7  190.90
  4932.0  186.27  4942.3  184.96  4948.4  182.09  4970.4  181.08  4986.4  178.62
  4996.2  178.04  4996.5  177.54  5000.5  178.04  5020.7  181.51  5043.1  183.83
  5059.9  184.71  5133.6  186.86  5173.3  186.85  5226.0  188.05  5310.5  189.74
  5419.9  194.08  5458.3  195.13  5505.6  197.84  5531.7  197.93  5599.9  201.18
  5606.1  202.57  5631.3  202.82  5648.3  204.50  5657.5  204.54  5683.0  205.50
#Mann=8,-1,0
  4582.5    0.05       0  4759.6    0.12       0  4834.7    0.03       0
  4996.2    0.03       0  5000.5    0.03       0  5226.0    0.12       0
  5419.9    0.03       0  5657.5    0.12       0
Bank Sta=4996.2,5000.5
Exp/Cntr=0.3,0.1

Type RM Length L Ch R = 1,10542,403,403,403
BEGIN DESCRIPTION:
TRIB 1 TO IRISH CREEK 17.0
END DESCRIPTION:
XS GIS Cut Line= 3
      2551871.68     13574198.78      2551678.33     13575021.65
      2552068.07     13575628.13
#Sta/Elev= 30
  4202.1  218.23  4331.4  210.68  4434.5  202.50  4600.1  195.16  4611.5  194.19
  4651.0  191.29  4711.8  188.49  4857.7  183.60  4958.3  183.24  4968.6  178.23
  4978.9  176.30  4987.0  175.90  4987.3  175.40  4991.3  175.90  5030.3  178.56
  5063.1  179.82  5105.4  179.68  5126.6  181.38  5199.2  182.43  5214.4  183.64
  5241.6  182.97  5256.7  184.25  5336.7  185.91  5346.1  185.44  5453.5  187.71
  5598.2  192.35  5692.6  197.07  5734.9  198.31  5740.8  199.40  5768.3  200.54
#Mann=9,-1,0
  4202.1    0.05       0  4331.4    0.12       0  4600.1    0.05       0
  4611.5    0.12       0  4857.7   0.013       0  4958.3    0.03       0
  4987.0    0.03       0  4991.3    0.03       0  5346.1    0.12       0
Bank Sta=4987,4991.3
Exp/Cntr=0.3,0.1

Type RM Length L Ch R = 1,10139,479,479,479
BEGIN DESCRIPTION:
TRIB 1 TO IRISH CREEK 16.0
END DESCRIPTION:
XS GIS Cut Line= 3
      2551928.99     13574266.49      2551375.00     13575225.00
      2551075.04     13575424.97
#Sta/Elev= 30
  3929.1  216.74  3989.0  213.62  4072.7  207.11  4135.3  201.72  4251.7  196.94
  4297.0  194.14  4304.8  192.84  4412.5  187.31  4482.8  184.82  4530.2  182.95
  4568.3  182.54  4728.3  183.67  4805.3  182.69  4816.7  182.30  4830.2  183.10
  4846.0  181.77  4947.9  180.03  4978.4  177.47  4985.2  175.12  5025.4  173.00
  5025.9  172.50  5031.3  173.00  5032.2  175.93  5033.3  179.51  5094.8  180.15
  5136.8  182.04  5180.4  182.78  5245.0  186.55  5269.1  186.98  5396.7  193.32
#Mann=9,-1,0
  3929.1    0.05       0  4072.7    0.12       0  4482.8   0.013       0
  4568.3    0.12       0  4805.3    0.03       0  5025.4    0.03       0
  5031.3    0.03       0  5032.2    0.12       0  5269.1    0.03       0
Bank Sta=5025.4,5031.3
Exp/Cntr=0.3,0.1

Type RM Length L Ch R = 1,9660,438,438,438
BEGIN DESCRIPTION:
TRIB 1 TO IRISH CREEK 15.0
END DESCRIPTION:
XS GIS Cut Line= 3
      2551625.00     13574325.00      2551025.00     13574925.00
      2550824.99     13575225.01
#Sta/Elev= 30
  4187.1  201.64  4272.0  196.77  4370.9  192.59  4399.2  190.23  4484.1  186.05
  4623.1  180.74  4640.6  180.24  4809.4  180.45  4887.7  178.19  4934.0  176.13
  4964.9  176.43  4979.1  172.16  4990.2  171.59  4990.7  171.09  4996.2  171.59
  5007.3  173.02  5021.5  173.60  5032.1  177.32  5038.6  177.32  5050.9  179.05
  5089.9  180.59  5136.3  183.87  5172.3  185.54  5193.4  188.19  5202.4  186.83
  5215.9  187.34  5229.4  188.79  5280.5  191.17  5337.6  195.65  5396.2  199.18
#Mann=9,-1,0
  4187.1    0.12       0  4623.1   0.013       0  4640.6    0.12       0
  4887.7    0.05       0  4934.0    0.03       0  4990.2    0.03       0
  4996.2    0.03       0  5050.9    0.05       0  5089.9    0.03       0
Bank Sta=4990.2,4996.2
Exp/Cntr=0.3,0.1

Type RM Length L Ch R = 1,9222,470,470,470
BEGIN DESCRIPTION:
TRIB 1 TO IRISH CREEK 14.0
END DESCRIPTION:
XS GIS Cut Line= 3
      2551275.03     13574124.97      2550875.00     13574525.00
      2550575.02     13574924.97
#Sta/Elev= 30
  4434.5  196.40  4477.0  193.54  4547.7  190.04  4618.4  186.93  4632.5  186.86
  4660.8  184.83  4719.0  182.85  4745.7  181.22  4807.2  179.31  4854.5  177.95
  4929.5  175.96  4957.8  171.54  4968.9  170.47  4969.4  169.97  4974.4  169.97
  4974.9  170.47  5028.4  173.91  5072.1  173.23  5092.9  173.70  5122.1  176.28
  5139.8  177.00  5228.4  179.10  5236.7  180.00  5263.8  180.18  5332.4  182.37
  5407.5  185.12  5413.8  184.77  5436.7  185.93  5492.9  186.63  5500.2  187.25
#Mann=8,-1,0
  4434.5    0.12       0  4719.0    0.03       0  4807.2   0.013       0
  4854.5    0.03       0  4968.9    0.03       0  4974.9    0.03       0
  5139.8    0.12       0  5332.4    0.03       0
Bank Sta=4968.9,4974.9
Exp/Cntr=0.3,0.1

Type RM Length L Ch R = 1,8752,415,415,415
BEGIN DESCRIPTION:
TRIB 1 TO IRISH CREEK 13.0
END DESCRIPTION:
XS GIS Cut Line= 3
      2551382.09     13574003.43      2550575.00     13574225.00
      2550525.00     13574774.98
#Sta/Elev= 30
  4203.3  206.22  4210.7  205.23  4266.8  202.69  4301.2  199.70  4355.8  196.27
  4469.9  190.12  4573.6  184.93  4708.4  179.97  4729.2  178.24  4790.5  176.98
  4797.4  176.28  4853.6  175.18  4864.0  175.97  4887.6  173.95  4904.2  174.50
  4967.7  173.40  4978.0  169.42  4980.4  167.32  4980.9  166.82  4986.5  167.32
  4990.4  167.77  5001.1  169.28  5042.8  169.62  5060.3  171.35  5120.6  174.31
  5226.2  176.18  5324.9  178.76  5431.9  178.22  5531.3  180.50  5592.5  182.47
#Mann=10,-1,0
  4203.3    0.12       0  4797.4   0.013       0  4887.6    0.12       0
  4980.4    0.05       0  4986.5    0.12       0  4990.4    0.05       0
  5001.1    0.03       0  5226.2    0.05       0  5324.9    0.03       0
  5531.3    0.12       0
Bank Sta=4980.4,4986.5
Exp/Cntr=0.3,0.1

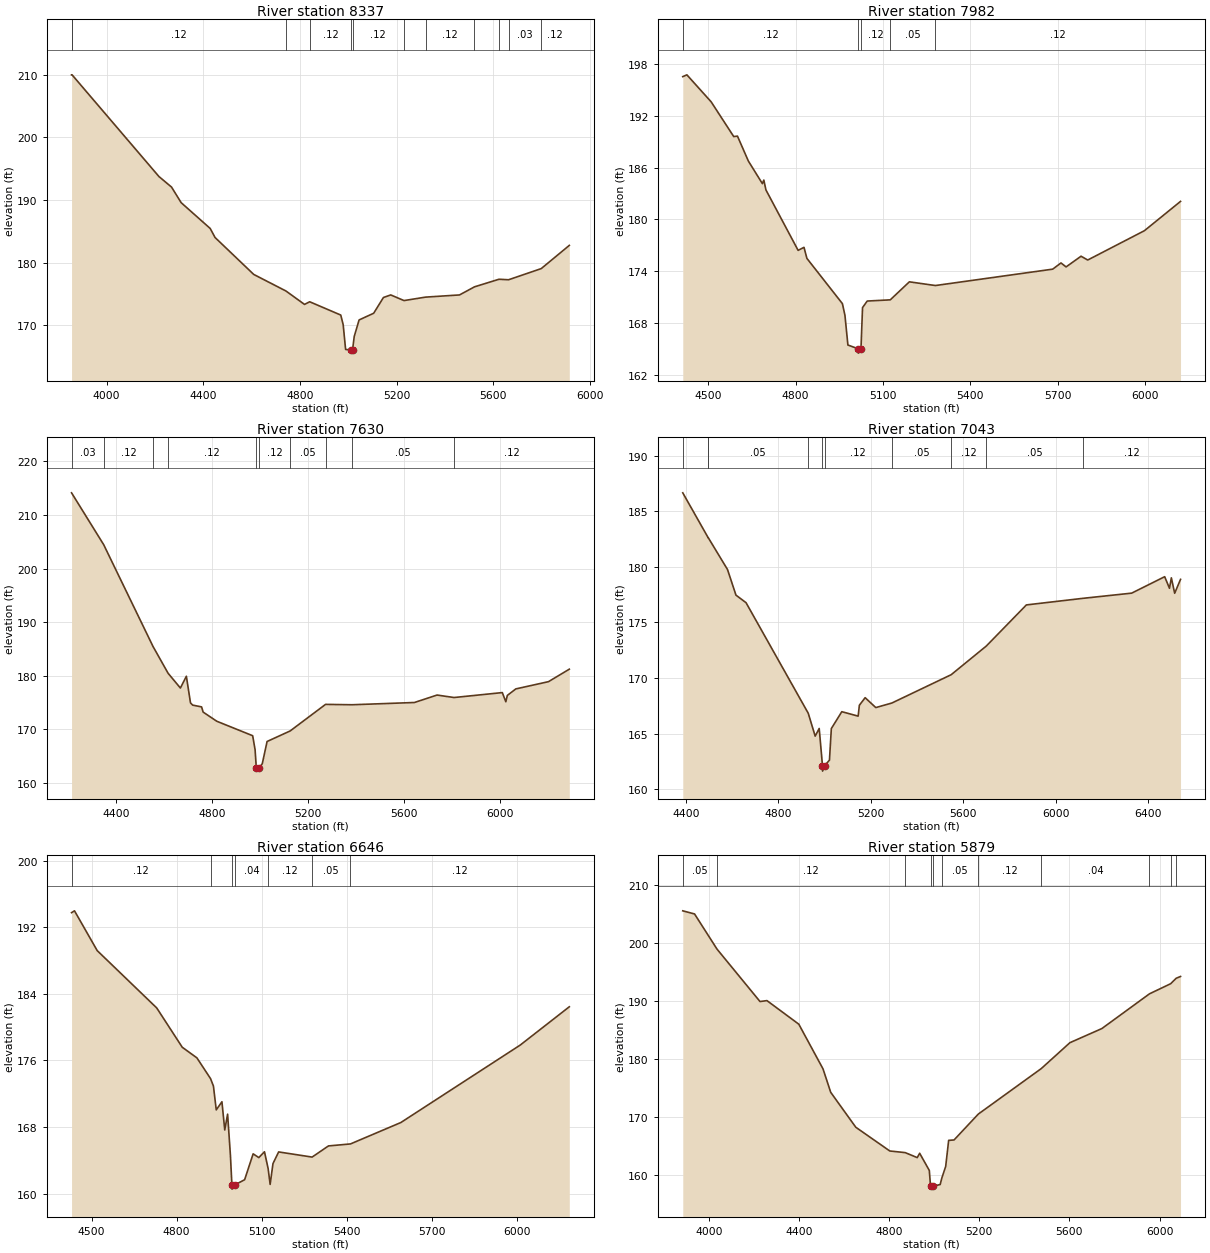
Type RM Length L Ch R = 1,8337,355,355,355
BEGIN DESCRIPTION:
Mapping XS de3c1833
END DESCRIPTION:
XS GIS Cut Line= 4
      2551518.47     13573919.18      2550374.13     13573890.36
      2550343.77     13574158.89      2550475.46     13574789.65
#Sta/Elev= 30
  3855.3  209.95  3857.4  209.95  4216.9  193.73  4268.9  192.05  4308.9  189.56
  4428.9  185.45  4449.0  184.01  4609.0  178.12  4742.2  175.48  4819.1  173.34
  4840.5  173.76  4969.1  171.64  4979.1  170.10  4989.1  166.16  5011.7  166.07
  5012.2  165.57  5017.8  166.07  5024.8  168.23  5044.9  170.86  5105.3  171.93
  5145.6  174.44  5175.8  174.85  5230.8  173.95  5319.8  174.50  5460.4  174.85
  5522.3  176.14  5623.6  177.35  5663.3  177.27  5798.5  179.05  5914.6  182.75
#Mann=12,-1,0
  3855.3    0.04       0  3857.4    0.12       0  4742.2   0.013       0
  4840.5    0.12       0  5011.7    0.05       0  5017.8    0.12       0
  5230.8    0.05       0  5319.8    0.12       0  5522.3    0.05       0
  5623.6    0.12       0  5663.3    0.03       0  5798.5    0.12       0
Bank Sta=5011.7,5017.8
Exp/Cntr=0.3,0.1

Type RM Length L Ch R = 1,7982,352,352,352
BEGIN DESCRIPTION:
Mapping XS 42eebdb2
END DESCRIPTION:
XS GIS Cut Line= 4
      2550150.53     13573140.98      2550090.36     13573682.50
      2550150.53     13574240.11      2550403.26     13574789.68
#Sta/Elev= 30
  4412.1  196.57  4426.2  196.78  4509.6  193.65  4587.2  189.62  4600.1  189.67
  4637.5  186.78  4685.7  184.16  4690.7  184.57  4697.9  183.43  4808.5  176.42
  4828.7  176.77  4838.7  175.49  4960.7  170.24  4969.5  168.87  4979.6  165.44
  5015.1  165.00  5015.6  164.50  5024.5  165.00  5029.9  169.78  5045.9  170.54
  5125.2  170.68  5190.8  172.77  5280.2  172.34  5683.4  174.24  5711.9  174.96
  5729.4  174.50  5780.8  175.74  5803.8  175.30  5998.6  178.70  6122.7  182.10
#Mann=5,-1,0
  4412.1    0.12       0  5015.1    0.05       0  5024.5    0.12       0
  5125.2    0.05       0  5280.2    0.12       0
Bank Sta=5015.1,5024.5
Exp/Cntr=0.3,0.1

Type RM Length L Ch R = 1,7630,587,587,587
BEGIN DESCRIPTION:
Mapping XS a0290acb
END DESCRIPTION:
XS GIS Cut Line= 4
      2549970.01     13572924.31      2549757.40     13573566.17
      2549769.43     13574091.68      2550282.90     13574797.70
#Sta/Elev= 30
  4215.0  214.14  4349.1  204.45  4554.7  185.45  4617.3  180.47  4668.7  177.70
  4693.6  179.90  4710.8  174.93  4720.0  174.51  4757.0  174.18  4763.5  173.21
  4820.4  171.50  4970.0  168.80  4980.0  166.20  4985.3  162.69  4985.8  162.19
  4994.8  162.69  5010.0  163.57  5030.0  167.72  5126.2  169.69  5273.8  174.65
  5384.3  174.58  5644.2  175.00  5738.5  176.39  5809.6  175.93  6010.5  176.85
  6025.2  175.14  6031.4  176.32  6067.0  177.54  6203.0  178.89  6289.8  181.22
#Mann=10,-1,0
  4215.0    0.03       0  4349.1    0.12       0  4554.7   0.013       0
  4617.3    0.12       0  4985.3    0.05       0  4994.8    0.12       0
  5126.2    0.05       0  5273.8    0.12       0  5384.3    0.05       0
  5809.6    0.12       0
Bank Sta=4985.3,4994.8
Exp/Cntr=0.3,0.1

Type RM Length L Ch R = 1,7043,397,397,397
BEGIN DESCRIPTION:
Mapping XS 18d884b0
END DESCRIPTION:
XS GIS Cut Line= 5
      2549263.97     13573016.60      2549187.76     13573622.33
      2549263.98     13573826.92      2549737.34     13574252.14
      2550162.57     13574793.71
#Sta/Elev= 30
  4386.7  186.67  4497.1  182.61  4497.3  182.62  4580.2  179.77  4616.9  177.46
  4660.5  176.78  4929.6  166.83  4959.6  164.77  4977.0  165.46  4991.2  162.12
  4991.7  161.62  5000.8  162.12  5021.4  162.61  5029.5  165.45  5074.8  166.97
  5145.5  166.57  5150.8  167.55  5175.8  168.23  5221.9  167.34  5291.5  167.75
  5548.1  170.30  5700.1  172.88  5873.4  176.58  6116.7  177.17  6329.0  177.64
  6471.8  179.12  6492.6  178.08  6500.7  179.02  6515.1  177.63  6540.4  178.88
#Mann=10,-1,0
  4386.7    0.05       0  4497.1    0.12       0  4497.3    0.05       0
  4929.6    0.12       0  4991.2    0.05       0  5000.8    0.12       0
  5291.5    0.05       0  5548.1    0.12       0  5700.1    0.05       0
  6116.7    0.12       0
Bank Sta=4991.2,5000.8
Exp/Cntr=0.3,0.1

Type RM Length L Ch R = 1,6646,767,767,767
BEGIN DESCRIPTION:
Mapping XS 0a32f680
END DESCRIPTION:
XS GIS Cut Line= 3
      2548818.69     13573004.56      2548802.65     13573814.88
      2548874.86     13574757.64
#Sta/Elev= 30
  4429.3  193.76  4439.7  193.98  4519.8  189.20  4729.8  182.31  4819.8  177.59
  4871.6  176.31  4919.6  173.82  4929.8  172.93  4939.8  170.06  4959.8  171.04
  4969.8  167.65  4979.8  169.55  4989.8  164.59  4995.0  161.04  4995.5  160.54
  5004.7  161.04  5039.9  161.67  5069.9  164.78  5089.9  164.33  5109.9  165.03
  5122.8  163.01  5129.9  161.11  5139.9  163.61  5159.9  165.01  5277.9  164.39
  5335.6  165.73  5413.3  165.97  5590.9  168.54  6012.2  177.85  6185.3  182.45
#Mann=7,-1,0
  4429.3    0.12       0  4919.6    0.04       0  4995.0    0.04       0
  5004.7    0.04       0  5122.8    0.12       0  5277.9    0.05       0
  5413.3    0.12       0
Bank Sta=4995,5004.7
Exp/Cntr=0.3,0.1

Type RM Length L Ch R = 1,5879,344,344,344
BEGIN DESCRIPTION:
Mapping XS b8517bda
END DESCRIPTION:
XS GIS Cut Line= 4
      2548537.89     13572936.31      2548401.49     13573794.83
      2548517.82     13574095.69      2548734.40     13575090.33
#Sta/Elev= 30
  3883.4  205.59  3935.7  205.05  4035.5  198.99  4226.3  189.96  4257.1  190.12
  4398.5  186.06  4506.0  178.36  4540.2  174.32  4651.6  168.30  4802.6  164.21
  4870.9  163.93  4924.4  163.07  4935.1  163.82  4978.0  160.85  4983.3  158.14
  4983.8  157.64  4994.2  158.14  5026.1  158.43  5033.8  159.59  5050.6  161.55
  5063.8  166.04  5087.7  166.11  5195.4  170.57  5475.0  178.41  5602.1  182.87
  5744.2  185.31  5955.4  191.29  6049.3  193.03  6073.9  193.97  6093.2  194.28
#Mann=11,-1,0
  3883.4    0.05       0  4035.5    0.12       0  4870.9    0.04       0
  4983.3    0.04       0  4994.2    0.04       0  5033.8    0.05       0
  5195.4    0.12       0  5475.0    0.04       0  5955.4    0.12       0
  6049.3    0.04       0  6073.9    0.05       0
Bank Sta=4983.3,4994.2
Exp/Cntr=0.3,0.1

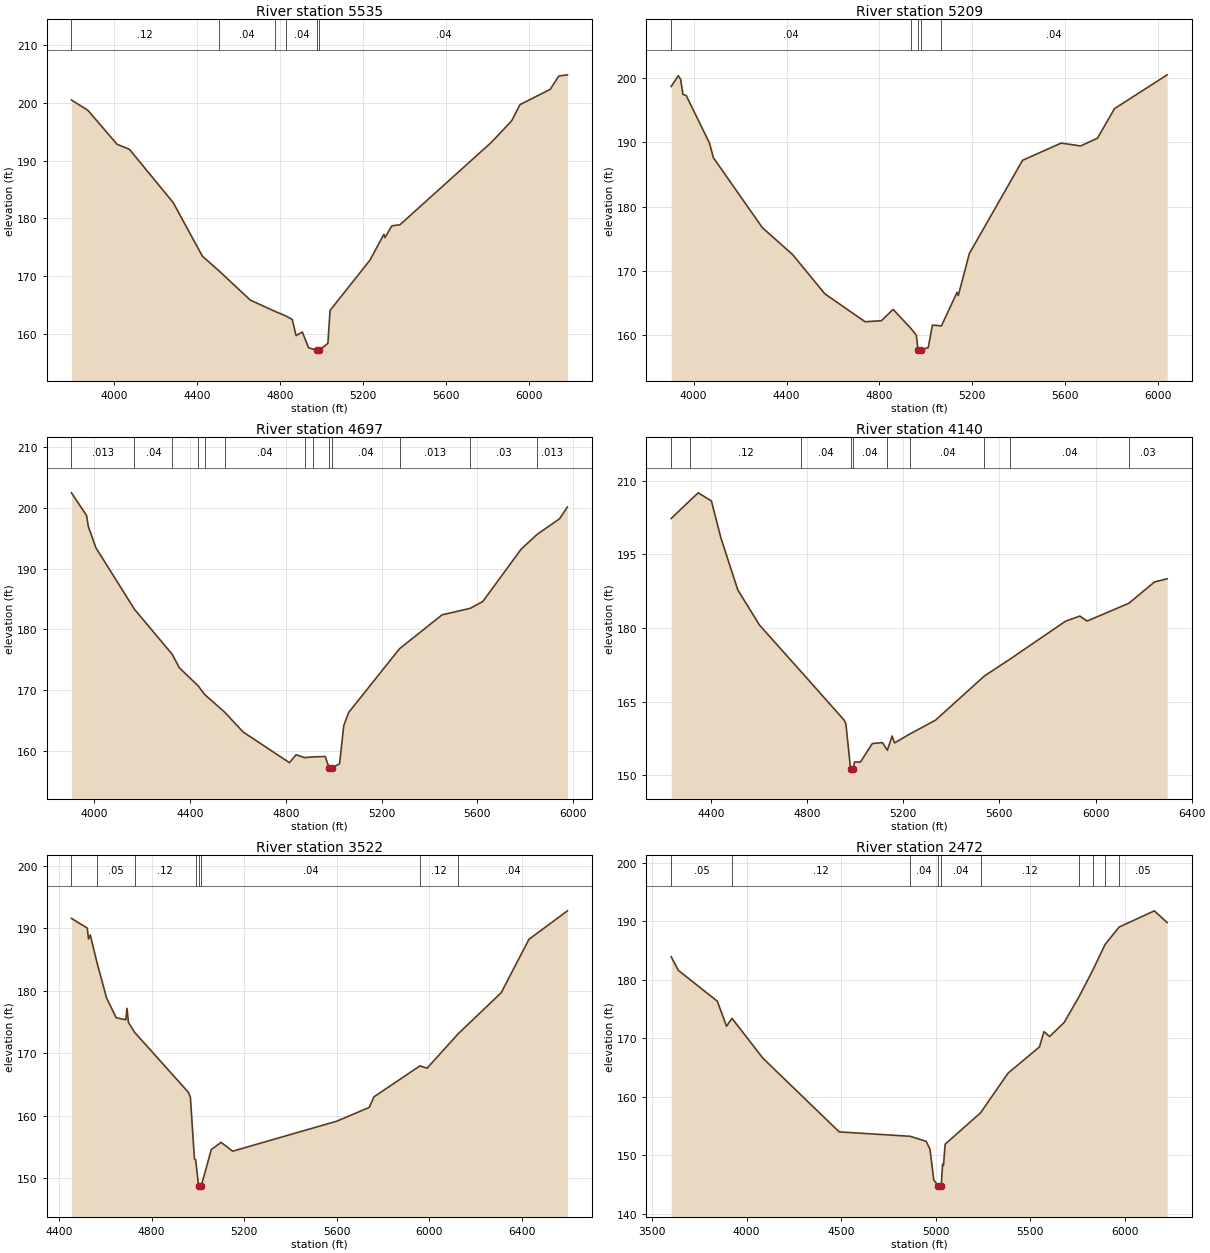
Type RM Length L Ch R = 1,5535,326,326,326
BEGIN DESCRIPTION:
Mapping XS 93c53d3a
END DESCRIPTION:
XS GIS Cut Line= 3
      2548293.18     13572896.22      2548180.85     13574047.55
      2548525.84     13575234.95
#Sta/Elev= 30
  3793.5  200.51  3872.7  198.73  4013.3  192.85  4073.6  191.96  4284.6  182.73
  4425.3  173.46  4503.2  170.99  4656.4  165.86  4774.1  163.93  4829.2  163.10
  4859.2  162.48  4877.4  159.70  4907.5  160.33  4937.7  157.60  4978.1  157.17
  4978.6  156.67  4989.1  157.17  5030.9  158.35  5041.4  164.06  5234.0  172.78
  5301.1  177.25  5306.3  176.69  5339.8  178.72  5378.6  178.90  5822.4  193.26
  5918.1  196.93  5957.8  199.71  6103.5  202.35  6145.2  204.66  6186.8  204.87
#Mann=6,-1,0
  3793.5    0.12       0  4503.2    0.04       0  4774.1    0.12       0
  4829.2    0.04       0  4978.1    0.04       0  4989.1    0.04       0
Bank Sta=4978.1,4989.1
Exp/Cntr=0.3,0.1

Type RM Length L Ch R = 1,5209,512,512,512
BEGIN DESCRIPTION:
Mapping XS 07fe20b5
END DESCRIPTION:
XS GIS Cut Line= 3
      2548016.38     13572984.51      2547908.07     13574063.60
      2548200.47     13575072.99
#Sta/Elev= 30
  3903.3  198.65  3933.9  200.33  3944.0  199.75  3954.0  197.42  3968.1  197.23
  4068.5  189.84  4084.7  187.60  4295.8  176.72  4426.4  172.53  4565.0  166.44
  4738.0  162.11  4808.3  162.26  4858.6  164.03  4934.7  161.10  4959.1  160.00
  4965.8  157.73  4966.3  157.23  4976.8  157.73  5010.1  158.10  5028.2  161.59
  5066.8  161.46  5134.2  166.67  5139.4  166.18  5187.1  172.70  5416.1  187.18
  5582.7  189.86  5666.0  189.41  5738.9  190.62  5811.8  195.20  6038.7  200.46
#Mann=5,-1,0
  3903.3    0.04       0  4934.7    0.05       0  4965.8    0.05       0
  4976.8    0.05       0  5066.8    0.04       0
Bank Sta=4965.8,4976.8
Exp/Cntr=0.3,0.1

Type RM Length L Ch R = 1,4697,557,557,557
BEGIN DESCRIPTION:
Mapping XS 88db6117
END DESCRIPTION:
XS GIS Cut Line= 3
      2547948.19     13572972.44      2547434.70     13573967.32
      2547390.58     13574918.02
#Sta/Elev= 30
  3904.5  202.43  3967.6  198.71  3974.9  196.91  4006.3  193.43  4167.6  183.31
  4325.1  175.92  4355.2  173.70  4434.4  170.70  4460.3  169.33  4543.7  166.44
  4621.0  163.17  4814.8  158.12  4842.6  159.42  4878.4  158.95  4913.7  159.07
  4964.2  159.13  4980.8  157.23  4981.3  156.73  4992.0  157.23  5024.1  157.94
  5041.8  164.21  5061.8  166.34  5274.7  176.83  5452.2  182.39  5570.3  183.47
  5622.4  184.58  5782.6  193.18  5849.4  195.61  5942.7  198.16  5975.8  200.11
#Mann=13,-1,0
  3904.5   0.013       0  4167.6    0.04       0  4325.1   0.013       0
  4434.4    0.04       0  4460.3   0.013       0  4543.7    0.04       0
  4878.4    0.05       0  4913.7    0.04       0  4980.8    0.05       0
  4992.0    0.04       0  5274.7   0.013       0  5570.3    0.03       0
  5849.4   0.013       0
Bank Sta=4980.8,4992
Exp/Cntr=0.3,0.1

Type RM Length L Ch R = 1,4140,618,618,618
BEGIN DESCRIPTION:
Mapping XS ce8f7043
END DESCRIPTION:
XS GIS Cut Line= 3
      2547458.75     13572771.92      2547153.89     13573574.19
      2547093.72     13574777.64
#Sta/Elev= 30
  4234.8  202.32  4312.3  205.96  4347.2  207.55  4402.1  205.89  4441.4  198.40
  4511.9  187.78  4602.2  180.62  4776.5  171.07  4954.8  161.25  4961.7  160.47
  4980.9  151.39  4981.4  150.89  4992.1  151.39  4997.6  152.76  5022.0  152.73
  5071.5  156.51  5113.9  156.69  5134.1  155.15  5153.9  158.04  5163.9  156.63
  5229.0  158.49  5334.2  161.26  5538.0  170.27  5644.0  173.68  5874.8  181.40
  5934.9  182.46  5964.9  181.44  6138.8  185.07  6245.3  189.40  6298.0  190.05
#Mann=10,-1,0
  4234.8    0.05       0  4312.3    0.12       0  4776.5    0.04       0
  4980.9    0.04       0  4992.1    0.04       0  5134.1    0.05       0
  5229.0    0.04       0  5538.0    0.03       0  5644.0    0.04       0
  6138.8    0.03       0
Bank Sta=4980.9,4992.1
Exp/Cntr=0.3,0.1

Type RM Length L Ch R = 1,3522,1050,1050,1050
BEGIN DESCRIPTION:
Mapping XS e4b5775b
END DESCRIPTION:
XS GIS Cut Line= 3
      2546796.86     13572795.93      2546652.44     13573385.65
      2546680.51     13574921.05
#Sta/Elev= 30
  4453.6  191.58  4522.0  190.03  4527.2  188.28  4535.0  188.93  4563.8  184.52
  4605.3  178.85  4646.9  175.67  4688.5  175.35  4693.6  177.18  4699.7  174.94
  4726.7  173.33  4957.1  163.81  4967.4  162.98  4984.9  153.08  4990.3  152.92
  5002.9  148.74  5003.4  148.24  5014.2  148.74  5057.8  154.57  5100.1  155.73
  5150.1  154.31  5600.2  159.12  5740.2  161.32  5760.2  163.00  5959.1  167.97
  5990.3  167.60  6123.5  173.07  6310.3  179.68  6430.3  188.23  6596.4  192.79
#Mann=8,-1,0
  4453.6    0.03       0  4563.8    0.05       0  4726.7    0.12       0
  4990.3    0.04       0  5002.9    0.04       0  5014.2    0.04       0
  5959.1    0.12       0  6123.5    0.04       0
Bank Sta=5002.9,5014.2
Exp/Cntr=0.3,0.1

Type RM Length L Ch R = 1,2472,1103,1103,1103
BEGIN DESCRIPTION:
Mapping XS ca1e4d39
END DESCRIPTION:
XS GIS Cut Line= 4
      2546540.12     13572811.99      2545753.85     13573120.88
      2545777.92     13574003.43      2546114.89     13574833.82
#Sta/Elev= 30
  3600.8  183.92  3638.5  181.60  3844.8  176.33  3893.6  172.05  3922.5  173.41
  4086.0  166.59  4489.7  154.00  4864.9  153.25  4949.9  152.38  4969.9  151.05
  4989.9  145.80  5014.1  144.72  5014.6  144.22  5025.6  144.72  5029.9  144.98
  5036.4  148.49  5041.4  148.26  5049.9  151.89  5237.7  157.26  5382.9  164.04
  5549.0  168.51  5573.1  171.14  5602.6  170.29  5680.3  172.72  5757.7  177.05
  5830.0  181.55  5896.5  186.03  5970.5  189.00  6157.1  191.77  6224.6  189.76
#Mann=10,-1,0
  3600.8    0.05       0  3922.5    0.12       0  4864.9    0.04       0
  5014.1    0.04       0  5025.6    0.04       0  5237.7    0.12       0
  5757.7    0.04       0  5830.0    0.12       0  5896.5    0.04       0
  5970.5    0.05       0
Bank Sta=5014.1,5025.6
Exp/Cntr=0.3,0.1

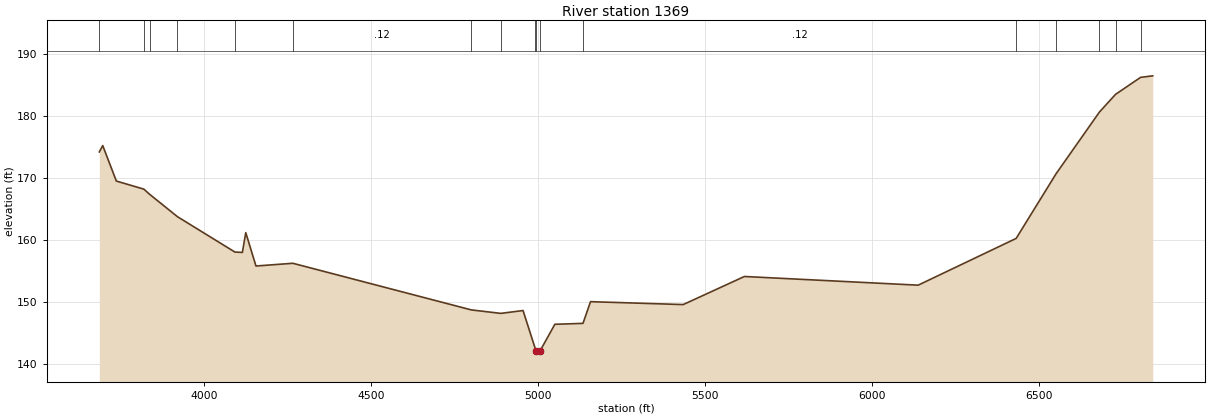
Type RM Length L Ch R = 1,1369,0,0,0
BEGIN DESCRIPTION:
TRIB 1 TO IRISH CREEK 1.0
END DESCRIPTION:
XS GIS Cut Line= 4
      2546074.99     13572675.00      2544983.80     13572887.34
      2544710.35     13573692.32      2545627.66     13574449.73
#Sta/Elev= 30
  3687.4  174.17  3697.6  175.19  3738.3  169.47  3820.5  168.17  3837.5  167.35
  3921.2  163.72  4093.0  158.02  4115.3  157.96  4125.5  161.15  4156.0  155.77
  4266.3  156.21  4800.3  148.69  4888.5  148.13  4955.0  148.59  4991.6  142.44
  4994.2  142.06  4994.7  141.56  5005.7  142.06  5050.1  146.37  5134.3  146.52
  5156.9  150.02  5434.1  149.55  5617.2  154.08  6137.0  152.68  6430.2  160.22
  6549.9  170.67  6679.5  180.61  6727.5  183.45  6802.4  186.19  6838.8  186.44
#Mann=17,-1,0
  3687.4    0.03       0  3820.5    0.12       0  3837.5    0.03       0
  3921.2    0.12       0  4093.0    0.05       0  4266.3    0.12       0
  4800.3     0.1       0  4888.5    0.12       0  4991.6    0.04       0
  4994.2    0.04       0  5005.7    0.04       0  5134.3    0.12       0
  6430.2    0.05       0  6549.9    0.12       0  6679.5    0.05       0
  6727.5    0.12       0  6802.4    0.05       0
Bank Sta=4994.2,5005.7
Exp/Cntr=0.3,0.1