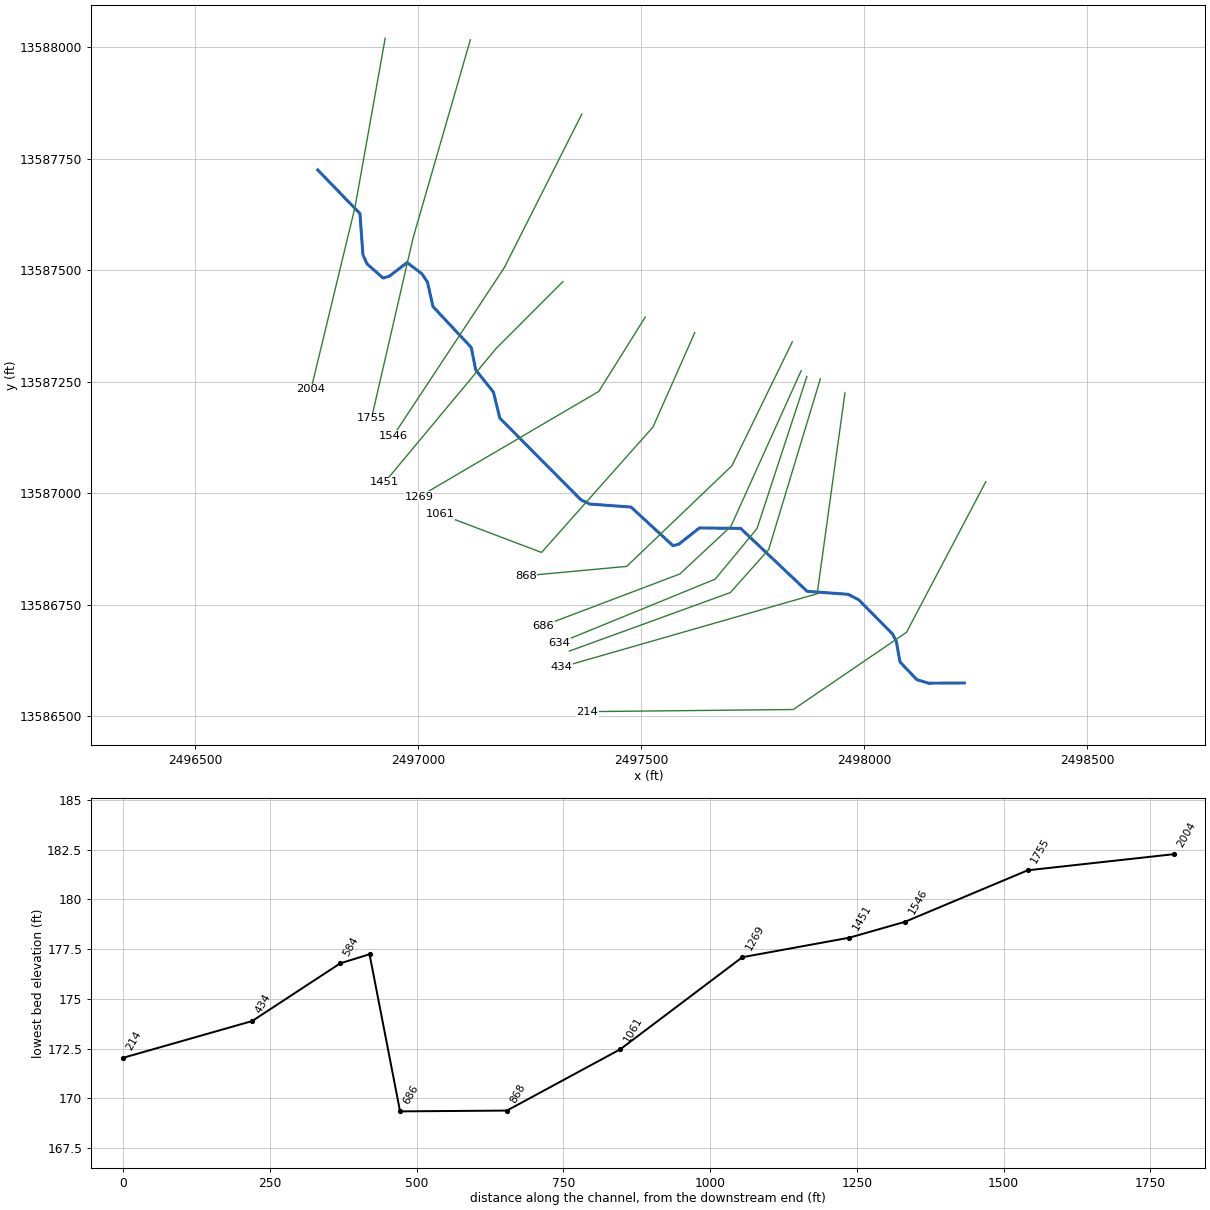
--- TRIB 1 TO LOST CREEK.prj (project) ---

Proj Title=TRIB 1 TO LOST CREEK Base Level Engineering
Current Plan=p01
Default Exp/Contr=0.3,0.1
English Units
Geom File=g01
Flow File=f01
Plan File=p01
Y Axis Title=Elevation
X Axis Title(PF)=Main Channel Distance
X Axis Title(XS)=Station
BEGIN DESCRIPTION:
TRIB 1 TO LOST CREEK
END DESCRIPTION:
DSS Export Rating Curves= 0
DSS Export Rating Curve Sorted= 0
DSS Export Volume Flow Curves= 0
DXF OffsetX= 0
DXF OffsetY= 0
DXF ScaleX= 1
DXF ScaleY= 10

--- TRIB 1 TO LOST CREEK.p01 (plan) ---

Plan Title=Multiple Run
Short Identifier=Multiple
Geom File=g01
Flow File=f01
Subcritical Flow
K Sum by GR= 0
Std Step Tol= 0.01
Critical Tol= 0.01
Num of Std Step Trials= 20
Max Error Tol= 0.3
Flow Tol Ratio= 0.001
Split Flow NTrial= 30
Split Flow Tol= 0.02
Split Flow Ratio= 0.02
Log Output Level= 0
Friction Slope Method= 1
Unsteady Friction Slope Method= 2
Unsteady Bridges Friction Slope Method= 1
Parabolic Critical Depth
Global Vel Dist=  1 , 1 , 1
Global Log Level= 0
CheckData=True
Encroach Param= -1, 0, 0, 0
BEGIN DESCRIPTION:
Multiple Run
END DESCRIPTION:

--- TRIB 1 TO LOST CREEK.f01 (steady flow) ---

Flow Title=Multiple
Number of Profiles=7
Profile Names=10-year,25-year,50-year,1pct_min,100-year,1pct_plu,500-year
River Rch & RM= TRIB 1 TO LOST C,Reach-1,2004
     419     659     871     559    1115    2225    1807
Boundary for River Rch & Prof#=TRIB 1 TO LOST C,Reach-1,1
Up Type=0
Dn Type=3
Dn Slope=0.005
Boundary for River Rch & Prof#=TRIB 1 TO LOST C,Reach-1,2
Up Type=0
Dn Type=3
Dn Slope=0.005
Boundary for River Rch & Prof#=TRIB 1 TO LOST C,Reach-1,3
Up Type=0
Dn Type=3
Dn Slope=0.005
Boundary for River Rch & Prof#=TRIB 1 TO LOST C,Reach-1,4
Up Type=0
Dn Type=3
Dn Slope=0.005
Boundary for River Rch & Prof#=TRIB 1 TO LOST C,Reach-1,5
Up Type=0
Dn Type=3
Dn Slope=0.005
Boundary for River Rch & Prof#=TRIB 1 TO LOST C,Reach-1,6
Up Type=0
Dn Type=3
Dn Slope=0.005
Boundary for River Rch & Prof#=TRIB 1 TO LOST C,Reach-1,7
Up Type=0
Dn Type=3
Dn Slope=0.005

--- TRIB 1 TO LOST CREEK.g01 (geometry) ---

Geom Title=Existing Conditions

River Reach=TRIB 1 TO LOST C,Reach-1
Reach XY= 30
      2496775.00     13587725.00      2496869.54     13587627.45
      2496876.16     13587535.15      2496885.52     13587514.51
      2496921.39     13587482.89      2496934.88     13587486.66
      2496975.20     13587517.52      2497008.35     13587492.53
      2497021.03     13587473.82      2497033.18     13587419.00
      2497119.15     13587327.29      2497129.19     13587276.73
      2497168.90     13587227.19      2497183.14     13587168.94
      2497365.21     13586985.52      2497385.48     13586976.17
      2497477.43     13586969.45      2497571.59     13586882.81
      2497584.85     13586886.34      2497630.89     13586922.63
      2497723.50     13586921.54      2497872.57     13586780.52
      2497964.52     13586773.84      2497988.33     13586761.61
      2498064.23     13586684.69      2498072.46     13586668.92
      2498080.73     13586622.43      2498118.45     13586582.60
      2498144.73     13586574.62      2498225.00     13586575.00

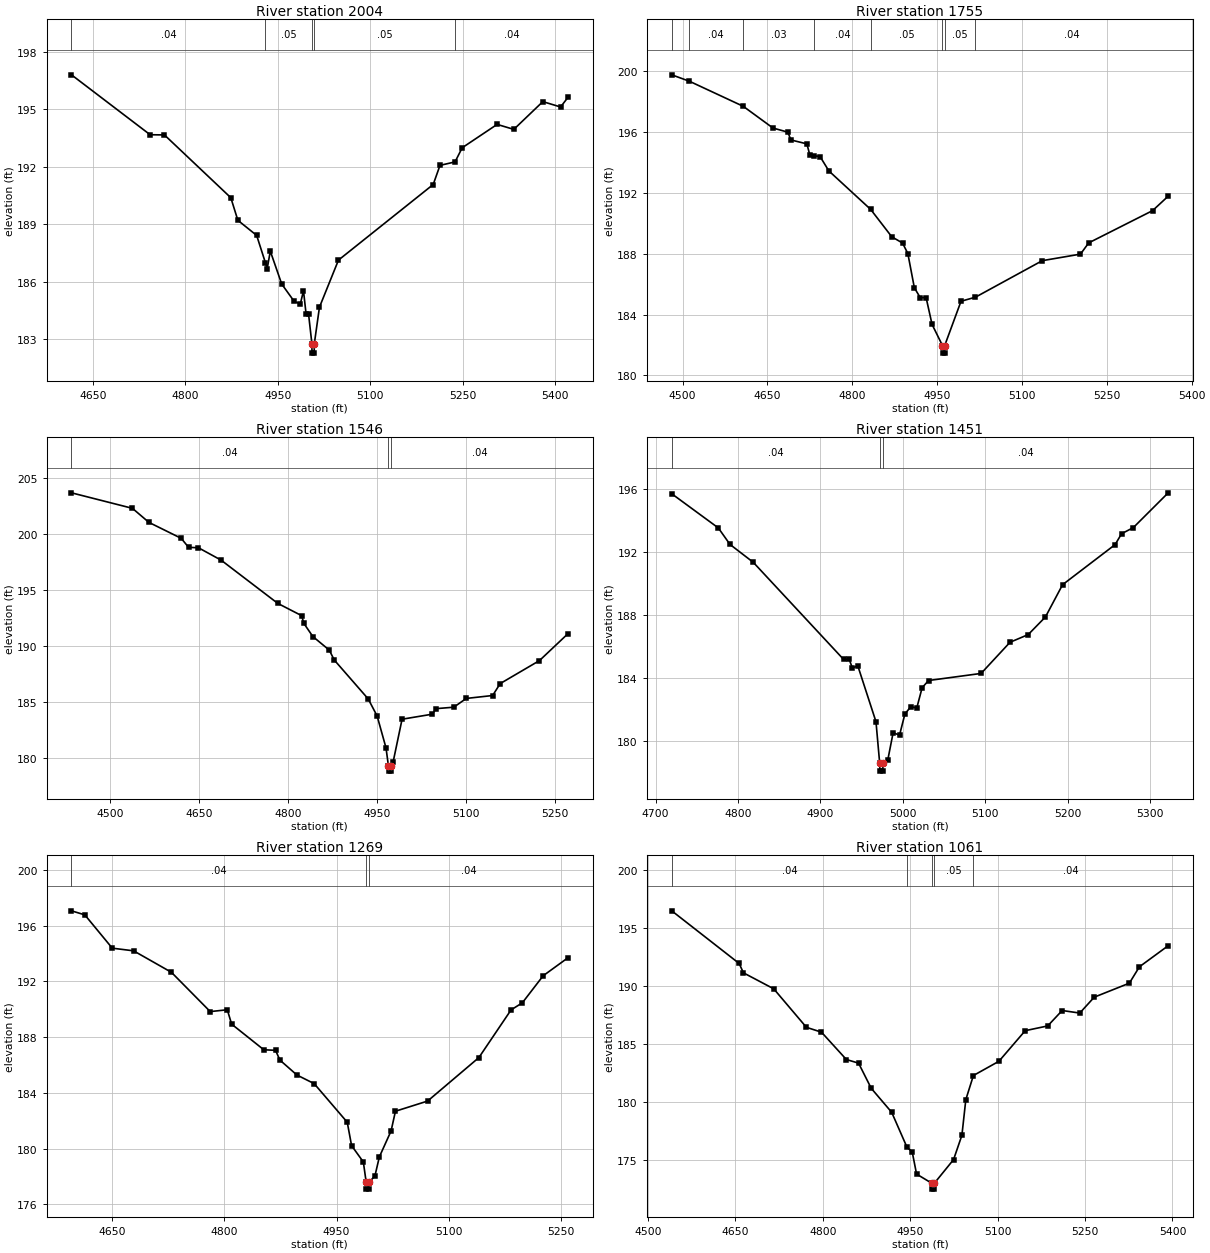
Type RM Length L Ch R = 1,2004,249,249,249
BEGIN DESCRIPTION:
TRIB 1 TO LOST CREEK 4.0
END DESCRIPTION:
XS GIS Cut Line= 3
      2496926.11     13588020.48      2496858.48     13587642.03
      2496759.73     13587233.44
#Sta/Elev= 30
  4615.5  196.81  4743.0  193.68  4766.2  193.67  4873.8  190.39  4885.2  189.21
  4915.7  188.42  4929.9  186.99  4932.7  186.67  4937.8  187.60  4956.3  185.88
  4976.6  184.97  4986.5  184.84  4991.6  185.53  4995.9  184.29  4999.9  184.29
  5005.2  182.77  5005.4  182.27  5008.9  182.27  5009.2  182.77  5017.5  184.67
  5048.3  187.13  5201.9  191.08  5212.9  192.08  5237.3  192.26  5248.9  193.00
  5305.5  194.22  5332.6  193.96  5379.6  195.41  5408.4  195.13  5420.3  195.63
#Mann=5,-1,0
  4615.5    0.04       0  4929.9    0.05       0  5005.2    0.05       0
  5009.2    0.05       0  5237.3    0.04       0
Bank Sta=5005.2,5009.2
Exp/Cntr=0.3,0.1

Type RM Length L Ch R = 1,1755,209,209,209
BEGIN DESCRIPTION:
Mapping XS e5d7f9d9
END DESCRIPTION:
XS GIS Cut Line= 3
      2497117.09     13588016.99      2496988.61     13587572.52
      2496895.28     13587168.11
#Sta/Elev= 30
  4480.8  199.76  4511.9  199.34  4607.2  197.69  4659.8  196.26  4686.1  195.99
  4691.3  195.48  4719.7  195.22  4724.9  194.49  4732.6  194.44  4743.1  194.38
  4758.6  193.44  4832.5  190.91  4869.8  189.11  4888.8  188.70  4898.2  188.01
  4909.7  185.76  4920.1  185.11  4930.5  185.11  4941.0  183.35  4959.4  181.96
  4959.7  181.46  4963.2  181.46  4963.4  181.96  4992.2  184.87  5017.8  185.14
  5135.9  187.54  5203.4  187.97  5218.0  188.71  5330.9  190.83  5358.5  191.78
#Mann=8,-1,0
  4480.8    0.03       0  4511.9    0.04       0  4607.2    0.03       0
  4732.6    0.04       0  4832.5    0.05       0  4959.4    0.05       0
  4963.4    0.05       0  5017.8    0.04       0
Bank Sta=4959.4,4963.4
Exp/Cntr=0.3,0.1

Type RM Length L Ch R = 1,1546,95,95,95
BEGIN DESCRIPTION:
Mapping XS 0bb1cff0
END DESCRIPTION:
XS GIS Cut Line= 3
      2497367.06     13587850.26      2497193.47     13587506.55
      2496944.10     13587129.03
#Sta/Elev= 30
  4434.8  203.64  4537.6  202.26  4565.4  201.01  4619.9  199.59  4632.3  198.79
  4649.0  198.75  4687.2  197.65  4782.8  193.80  4823.0  192.71  4826.9  192.01
  4842.0  190.85  4869.7  189.64  4878.1  188.76  4935.3  185.30  4950.4  183.78
  4965.4  180.94  4969.4  179.37  4969.7  178.87  4973.2  178.87  4973.4  179.37
  4977.5  179.71  4992.5  183.49  5043.7  183.94  5049.6  184.43  5079.8  184.56
  5100.8  185.34  5145.3  185.60  5158.0  186.66  5224.3  188.71  5272.3  191.10
#Mann=3,-1,0
  4434.8    0.04       0  4969.4    0.04       0  4973.4    0.04       0
Bank Sta=4969.4,4973.4
Exp/Cntr=0.3,0.1

Type RM Length L Ch R = 1,1451,182,182,182
BEGIN DESCRIPTION:
TRIB 1 TO LOST CREEK 3.0
END DESCRIPTION:
XS GIS Cut Line= 3
      2497324.98     13587474.98      2497175.00     13587325.00
      2496925.01     13587025.01
#Sta/Elev= 30
  4719.6  195.70  4776.1  193.53  4790.3  192.48  4818.6  191.34  4928.2  185.17
  4935.0  185.17  4938.9  184.62  4945.4  184.77  4967.5  181.21  4972.0  178.57
  4972.3  178.07  4975.8  178.07  4976.0  178.57  4981.8  178.77  4988.3  180.51
  4996.1  180.36  5002.6  181.70  5009.8  182.17  5017.0  182.08  5023.5  183.37
  5031.3  183.83  5095.1  184.28  5130.2  186.26  5152.3  186.75  5173.2  187.87
  5194.0  189.92  5257.8  192.47  5265.6  193.16  5279.9  193.55  5322.2  195.76
#Mann=3,-1,0
  4719.6    0.04       0  4972.0    0.04       0  4976.0    0.04       0
Bank Sta=4972,4976
Exp/Cntr=0.3,0.1

Type RM Length L Ch R = 1,1269,208,208,208
BEGIN DESCRIPTION:
Mapping XS eb28edce
END DESCRIPTION:
XS GIS Cut Line= 3
      2497509.43     13587395.42      2497405.27     13587228.77
      2497002.49     13586992.66
#Sta/Elev= 30
  4595.7  197.06  4613.5  196.77  4650.2  194.38  4678.7  194.19  4729.2  192.65
  4781.1  189.83  4803.9  189.96  4809.7  188.93  4852.7  187.09  4868.4  187.05
  4874.2  186.35  4896.9  185.28  4920.0  184.66  4964.2  181.89  4970.0  180.21
  4985.7  179.04  4989.5  177.59  4989.7  177.09  4993.2  177.09  4993.5  177.59
  5001.2  178.04  5007.1  179.40  5022.8  181.27  5028.6  182.68  5071.6  183.41
  5140.1  186.53  5183.1  189.95  5198.2  190.46  5226.0  192.40  5259.1  193.69
#Mann=3,-1,0
  4595.7    0.04       0  4989.5    0.04       0  4993.5    0.04       0
Bank Sta=4989.5,4993.5
Exp/Cntr=0.3,0.1

Type RM Length L Ch R = 1,1061,193,193,193
BEGIN DESCRIPTION:
Mapping XS c6e19146
END DESCRIPTION:
XS GIS Cut Line= 4
      2497620.56     13587360.73      2497526.80     13587148.91
      2497276.80     13586867.66      2497048.85     13586954.01
#Sta/Elev= 30
  4541.0  196.47  4656.6  191.93  4664.0  191.12  4716.0  189.74  4772.0  186.42
  4797.9  186.00  4840.6  183.64  4861.5  183.33  4883.2  181.16  4918.3  179.09
  4944.6  176.07  4953.5  175.68  4961.0  173.76  4987.4  172.96  4987.7  172.46
  4991.2  172.46  4991.4  172.96  5024.5  175.01  5038.8  177.11  5045.5  180.18
  5058.5  182.26  5102.3  183.49  5147.4  186.13  5186.0  186.54  5210.8  187.87
  5241.0  187.65  5265.8  189.02  5326.1  190.23  5343.3  191.64  5392.7  193.46
#Mann=5,-1,0
  4541.0    0.04       0  4944.6    0.05       0  4987.4    0.05       0
  4991.4    0.05       0  5058.5    0.04       0
Bank Sta=4987.4,4991.4
Exp/Cntr=0.3,0.1

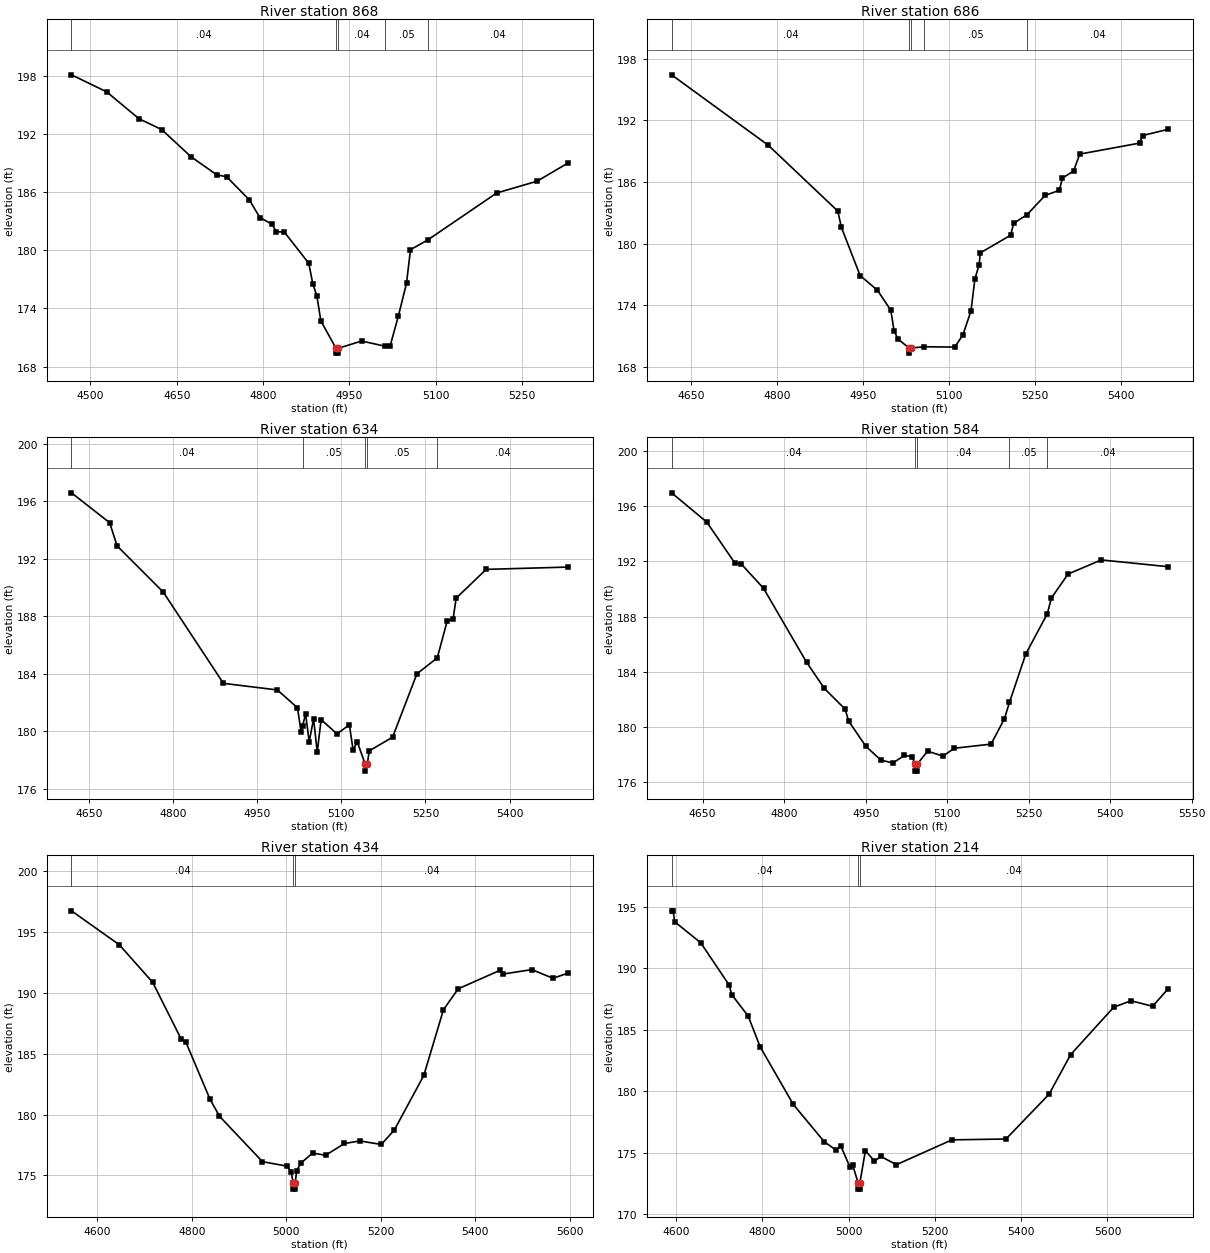
Type RM Length L Ch R = 1,868,182,182,182
BEGIN DESCRIPTION:
Mapping XS 5356b930
END DESCRIPTION:
XS GIS Cut Line= 4
      2497839.28     13587339.84      2497703.89     13587062.11
      2497467.77     13586836.41      2497242.05     13586815.57
#Sta/Elev= 30
  4467.0  198.09  4528.0  196.34  4584.3  193.56  4623.8  192.44  4674.5  189.65
  4719.5  187.77  4736.5  187.58  4776.0  185.19  4794.3  183.37  4815.7  182.67
  4822.7  181.91  4836.8  181.87  4879.3  178.65  4886.2  176.56  4893.4  175.27
  4900.3  172.70  4926.6  169.88  4926.9  169.38  4930.4  169.38  4930.6  169.88
  4971.1  170.63  5012.0  170.09  5020.8  170.15  5034.9  173.19  5049.1  176.58
  5056.0  180.05  5085.9  181.05  5205.8  185.90  5276.1  187.12  5329.3  188.98
#Mann=5,-1,0
  4467.0    0.04       0  4926.6    0.04       0  4930.6    0.04       0
  5012.0    0.05       0  5085.9    0.04       0
Bank Sta=4926.6,4930.6
Exp/Cntr=0.3,0.1

Type RM Length L Ch R = 1,686,52,52,52
BEGIN DESCRIPTION:
Mapping XS 3d45a008
END DESCRIPTION:
XS GIS Cut Line= 4
      2497859.17     13587275.17      2497701.61     13586926.20
      2497587.03     13586819.42      2497281.05     13586703.54
#Sta/Elev= 30
  4616.0  196.44  4785.2  189.57  4906.3  183.17  4912.4  181.61  4945.3  176.89
  4975.6  175.46  4998.9  173.51  5004.5  171.53  5011.4  170.70  5030.9  169.84
  5031.1  169.34  5034.9  169.84  5056.8  169.96  5110.6  169.93  5124.7  171.11
  5138.9  173.45  5145.7  176.57  5153.1  177.94  5155.1  179.10  5208.1  180.82
  5213.4  181.98  5236.9  182.83  5268.4  184.70  5293.2  185.19  5298.6  186.39
  5318.0  187.07  5328.8  188.72  5433.3  189.79  5438.6  190.53  5482.7  191.13
#Mann=5,-1,0
  4616.0    0.04       0  5030.9    0.04       0  5034.9    0.04       0
  5056.8    0.05       0  5236.9    0.04       0
Bank Sta=5030.9,5034.9
Exp/Cntr=0.3,0.1

Type RM Length L Ch R = 1,634,50,50,50
BEGIN DESCRIPTION:
Mapping XS 5356b930aa
END DESCRIPTION:
XS GIS Cut Line= 4
      2497872.06     13587262.27      2497760.09     13586921.14
      2497666.34     13586807.86      2497316.07     13586664.62
#Sta/Elev= 30
  4619.2  196.58  4687.3  194.50  4700.5  192.89  4782.8  189.68  4890.0  183.34
  4986.2  182.88  5022.0  181.64  5028.5  179.94  5031.4  180.41  5036.4  181.22
  5042.9  179.29  5050.7  180.87  5057.2  178.56  5064.1  180.82  5092.4  179.83
  5114.5  180.46  5121.0  178.73  5128.7  179.26  5142.5  177.74  5142.7  177.24
  5146.5  177.74  5149.9  178.65  5191.5  179.60  5234.8  184.00  5271.1  185.11
  5288.8  187.67  5299.4  187.84  5304.8  189.26  5358.2  191.26  5503.7  191.42
#Mann=5,-1,0
  4619.2    0.04       0  5031.4    0.05       0  5142.5    0.04       0
  5146.5    0.05       0  5271.1    0.04       0
Bank Sta=5142.5,5146.5
Exp/Cntr=0.3,0.1

Type RM Length L Ch R = 1,584,150,150,150
BEGIN DESCRIPTION:
Mapping XS e013fa1e
END DESCRIPTION:
XS GIS Cut Line= 4
      2497902.13     13587256.93      2497786.25     13586874.11
      2497700.31     13586777.76      2497339.18     13586646.56
#Sta/Elev= 30
  4592.9  196.98  4657.6  194.86  4709.8  191.86  4720.3  191.85  4762.1  190.05
  4841.2  184.69  4874.1  182.78  4912.2  181.28  4918.8  180.41  4950.4  178.58
  4978.1  177.58  5000.3  177.37  5021.2  177.92  5035.4  177.84  5041.0  177.28
  5041.2  176.78  5044.7  176.78  5045.0  177.28  5063.9  178.23  5092.3  177.87
  5113.2  178.44  5180.8  178.74  5205.3  180.57  5214.7  181.77  5244.7  185.28
  5284.3  188.20  5291.8  189.34  5322.4  191.08  5383.6  192.11  5506.2  191.62
#Mann=5,-1,0
  4592.9    0.04       0  5041.0    0.04       0  5045.0    0.04       0
  5214.7    0.05       0  5284.3    0.04       0
Bank Sta=5041,5045
Exp/Cntr=0.3,0.1

Type RM Length L Ch R = 1,434,220,220,220
BEGIN DESCRIPTION:
TRIB 1 TO LOST CREEK 1.0
END DESCRIPTION:
XS GIS Cut Line= 3
      2497957.36     13587225.34      2497895.06     13586775.13
      2497321.97     13586610.72
#Sta/Elev= 30
  4545.5  196.75  4646.8  193.96  4717.5  190.87  4778.0  186.19  4788.1  185.93
  4838.6  181.28  4858.8  179.87  4949.7  176.14  5002.6  175.76  5010.5  175.27
  5015.1  174.38  5015.4  173.88  5018.9  173.88  5019.1  174.38  5022.3  175.40
  5031.3  176.02  5056.1  176.85  5083.3  176.66  5123.5  177.63  5156.1  177.84
  5201.4  177.55  5228.9  178.73  5291.4  183.22  5333.0  188.62  5364.2  190.34
  5453.2  191.87  5458.4  191.55  5520.2  191.92  5564.8  191.21  5596.2  191.62
#Mann=3,-1,0
  4545.5    0.04       0  5015.1    0.04       0  5019.1    0.04       0
Bank Sta=5015.1,5019.1
Exp/Cntr=0.3,0.1

Type RM Length L Ch R = 1,214,0,0,0
BEGIN DESCRIPTION:
TRIB 1 TO LOST CREEK 0.5
END DESCRIPTION:
XS GIS Cut Line= 4
      2498273.32     13587026.34      2498095.45     13586688.67
      2497841.48     13586515.55      2497379.63     13586510.79
#Sta/Elev= 30
  4589.2  194.68  4592.8  194.68  4596.4  193.79  4656.8  192.08  4722.9  188.63
  4728.5  187.87  4766.9  186.11  4794.6  183.61  4871.5  178.92  4943.2  175.89
  4970.1  175.22  4981.9  175.52  5002.8  173.83  5008.9  174.03  5021.8  172.53
  5022.1  172.03  5025.6  172.03  5025.8  172.53  5038.7  175.16  5059.7  174.31
  5074.6  174.69  5110.6  174.02  5239.3  176.04  5364.7  176.11  5464.7  179.76
  5514.7  182.98  5614.7  186.84  5654.7  187.36  5704.7  186.91  5740.1  188.31
#Mann=3,-1,0
  4589.2    0.04       0  5021.8    0.04       0  5025.8    0.04       0
Bank Sta=5021.8,5025.8
Exp/Cntr=0.3,0.1

Chan Stop Cuts=-1