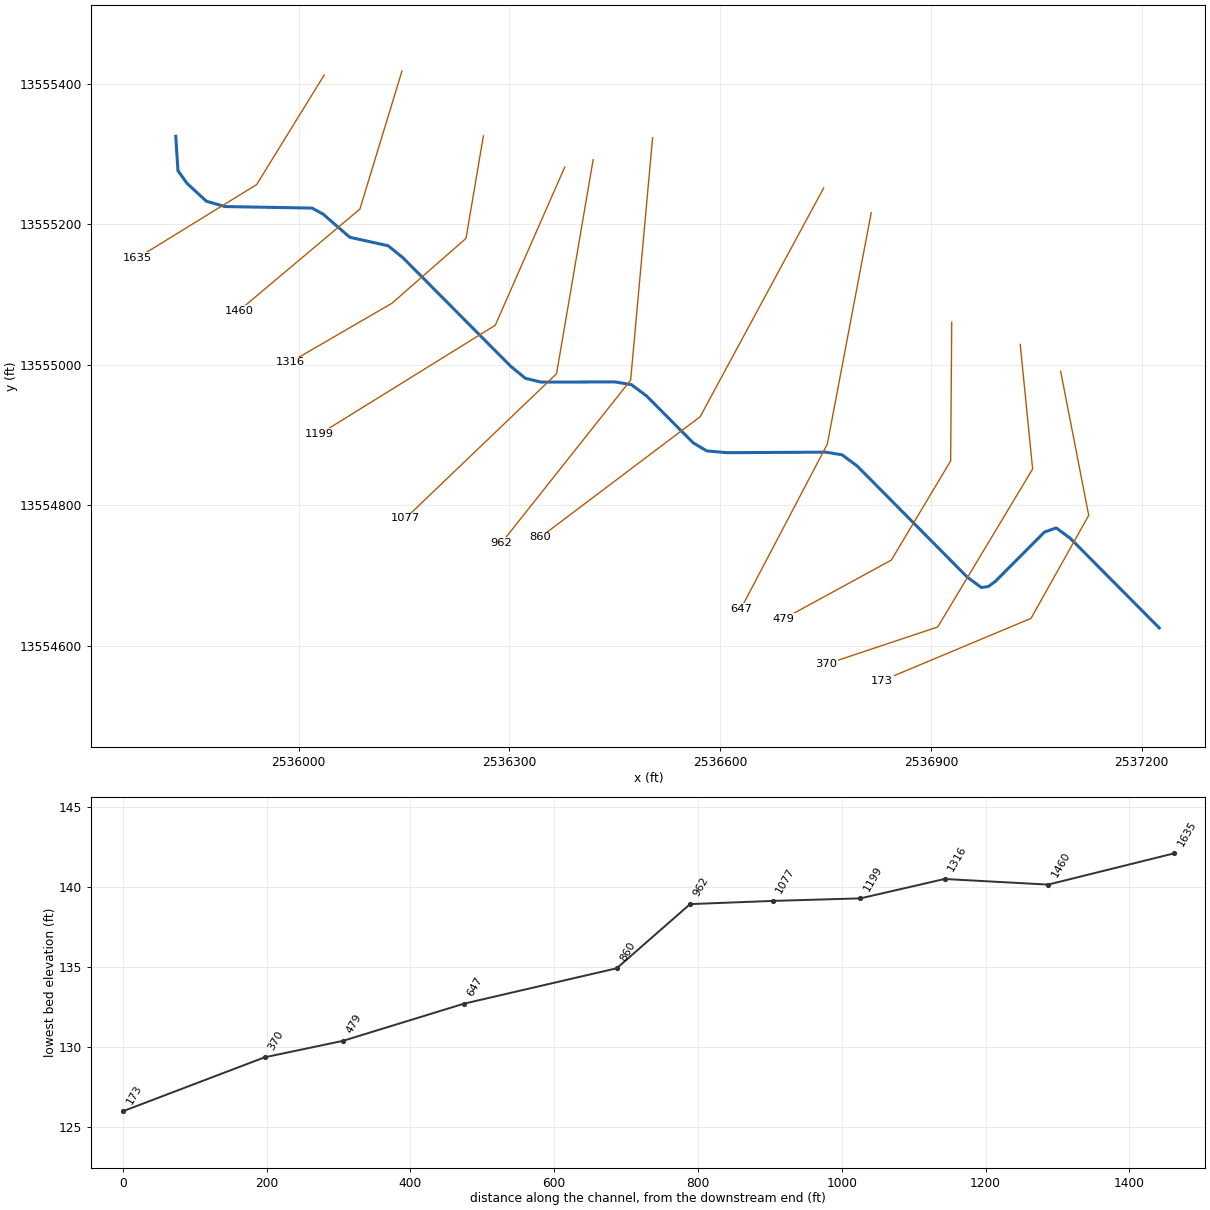
--- TRIB 1 TO NORTH FORK CREEK.prj (project) ---

Proj Title=TRIB 1 TO NORTH FORK CREEK Base Level Engineering
Current Plan=p01
Default Exp/Contr=0.3,0.1
English Units
Geom File=g01
Flow File=f01
Plan File=p01
BEGIN DESCRIPTION:
TRIB 1 TO NORTH FORK CREEK
END DESCRIPTION:

--- TRIB 1 TO NORTH FORK CREEK.p01 (plan) ---

Plan Title=Multiple Run
Short Identifier=Multiple
Geom File=g01
Flow File=f01
Subcritical Flow
K Sum by GR= 0
Std Step Tol= 0.01
Critical Tol= 0.01
Num of Std Step Trials= 20
Max Error Tol= 0.3
Flow Tol Ratio= 0.001
Split Flow NTrial= 30
Split Flow Tol= 0.02
Split Flow Ratio= 0.02
Log Output Level= 0
Friction Slope Method= 1
Unsteady Friction Slope Method= 2
Unsteady Bridges Friction Slope Method= 1
Parabolic Critical Depth
Global Vel Dist=  1 , 1 , 1
Global Log Level= 0
CheckData=True
Encroach Param= -1, 0, 0, 0
BEGIN DESCRIPTION:
Multiple Run
END DESCRIPTION:

--- TRIB 1 TO NORTH FORK CREEK.f01 (steady flow) ---

Flow Title=Multiple
Number of Profiles=7
Profile Names=10-year,25-year,50-year,1pct_min,100-year,1pct_plu,500-year
River Rch & RM= TRIB 1 TO NORTH ,Reach-1,1635
     354     551     724     462     922    1840    1479
Boundary for River Rch & Prof#=TRIB 1 TO NORTH ,Reach-1,1
Up Type=0
Dn Type=3
Dn Slope=0.005
Boundary for River Rch & Prof#=TRIB 1 TO NORTH ,Reach-1,2
Up Type=0
Dn Type=3
Dn Slope=0.005
Boundary for River Rch & Prof#=TRIB 1 TO NORTH ,Reach-1,3
Up Type=0
Dn Type=3
Dn Slope=0.005
Boundary for River Rch & Prof#=TRIB 1 TO NORTH ,Reach-1,4
Up Type=0
Dn Type=3
Dn Slope=0.005
Boundary for River Rch & Prof#=TRIB 1 TO NORTH ,Reach-1,5
Up Type=0
Dn Type=3
Dn Slope=0.005
Boundary for River Rch & Prof#=TRIB 1 TO NORTH ,Reach-1,6
Up Type=0
Dn Type=3
Dn Slope=0.005
Boundary for River Rch & Prof#=TRIB 1 TO NORTH ,Reach-1,7
Up Type=0
Dn Type=3
Dn Slope=0.005

--- TRIB 1 TO NORTH FORK CREEK.g01 (geometry) ---

Geom Title=Existing Conditions

River Reach=TRIB 1 TO NORTH ,Reach-1
Reach XY= 30
      2535825.00     13555325.00      2535828.12     13555275.98
      2535841.31     13555257.65      2535868.53     13555232.59
      2535894.91     13555224.93      2536019.07     13555222.75
      2536034.67     13555214.20      2536072.83     13555181.14
      2536127.30     13555169.17      2536148.47     13555151.99
      2536301.47     13554997.86      2536322.55     13554980.47
      2536344.99     13554974.98      2536450.11     13554975.27
      2536473.53     13554971.44      2536495.14     13554955.35
      2536561.69     13554888.40      2536580.86     13554877.07
      2536609.80     13554874.51      2536750.12     13554875.29
      2536773.54     13554871.46      2536795.16     13554855.40
      2536951.67     13554697.39      2536971.67     13554682.61
      2536981.67     13554683.99      2536991.67     13554691.26
      2537061.67     13554761.54      2537078.33     13554767.40
      2537098.33     13554752.63      2537225.00     13554625.00

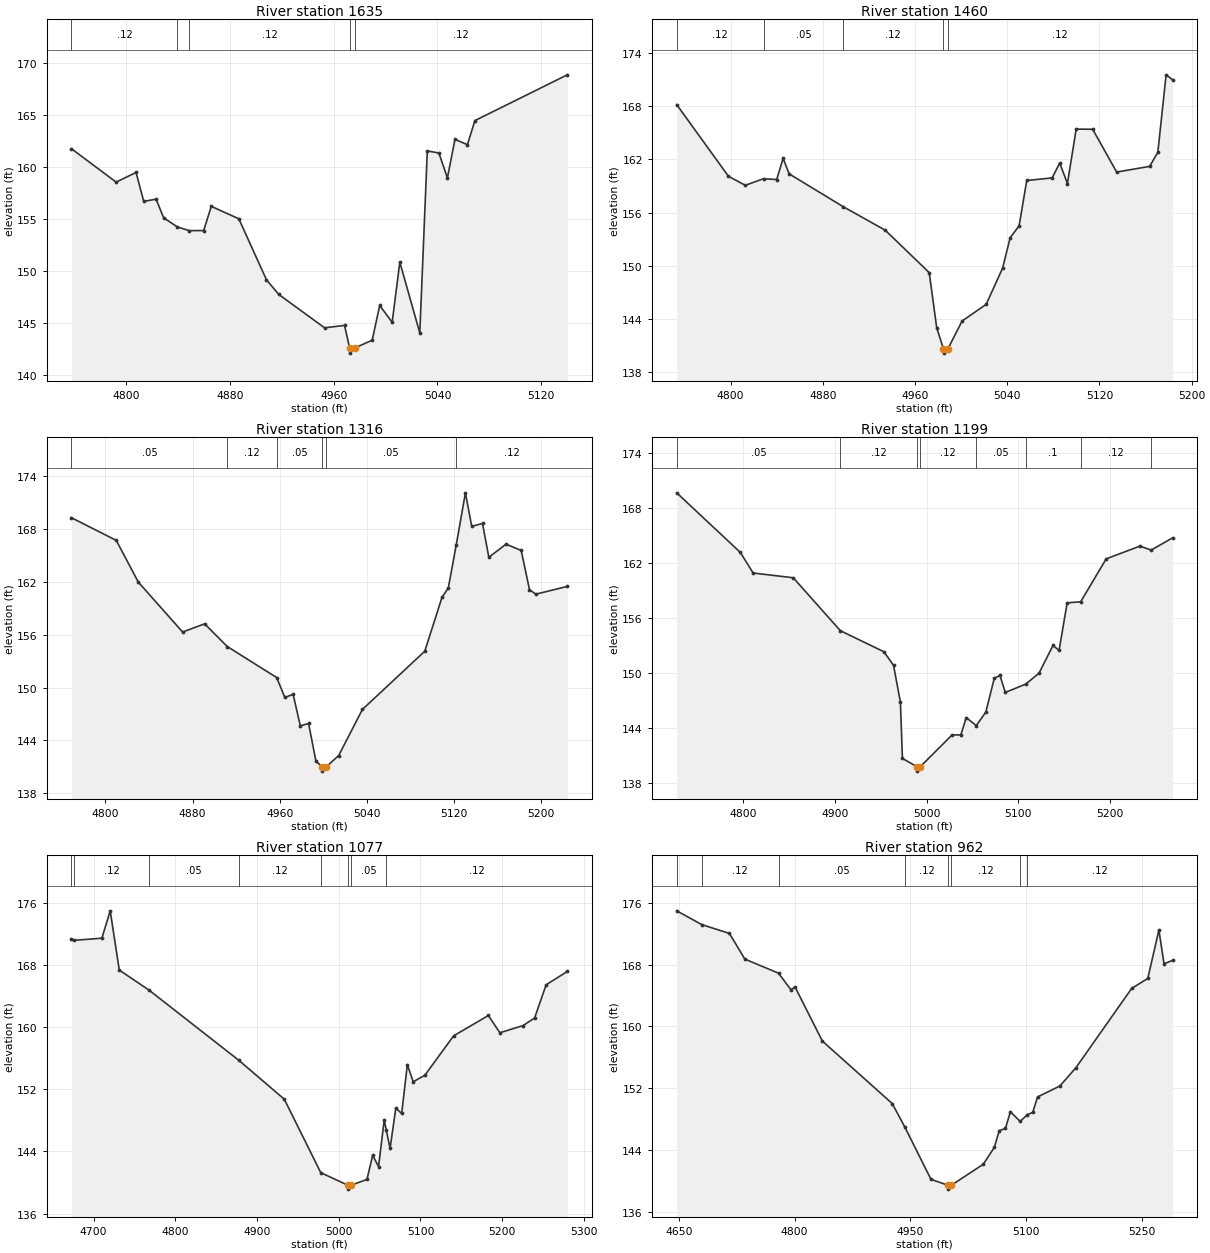
Type RM Length L Ch R = 1,1635,175,175,175
BEGIN DESCRIPTION:
TRIB 1 TO NORTH FORK CREEK 3.0
END DESCRIPTION:
XS GIS Cut Line= 3
      2536036.27     13555412.16      2535940.15     13555256.19
      2535770.65     13555151.95
#Sta/Elev= 30
  4757.9  161.73  4792.3  158.53  4807.7  159.45  4813.6  156.68  4823.1  156.89
  4829.0  155.10  4839.5  154.23  4848.8  153.87  4859.8  153.88  4865.7  156.20
  4886.9  155.01  4908.2  149.16  4917.7  147.75  4953.0  144.55  4968.4  144.78
  4972.3  142.62  4972.5  142.12  4976.3  142.62  4989.7  143.36  4995.5  146.69
  5005.1  145.08  5011.0  150.85  5026.4  144.06  5032.2  161.52  5041.1  161.32
  5047.7  158.93  5053.5  162.63  5063.1  162.12  5068.9  164.43  5140.1  168.82
#Mann=5,-1,0
  4757.9    0.12       0  4839.5    0.05       0  4848.8    0.12       0
  4972.3    0.05       0  4976.3    0.12       0
Bank Sta=4972.3,4976.3
Exp/Cntr=0.3,0.1

Type RM Length L Ch R = 1,1460,144,144,144
BEGIN DESCRIPTION:
Mapping XS a6662817
END DESCRIPTION:
XS GIS Cut Line= 3
      2536147.01     13555417.94      2536087.11     13555221.33
      2535915.23     13555076.80
#Sta/Elev= 30
  4753.3  168.15  4798.2  160.08  4812.8  159.07  4828.6  159.81  4840.0  159.72
  4845.6  162.11  4850.8  160.36  4897.7  156.66  4934.1  154.02  4972.3  149.24
  4978.8  143.04  4984.6  140.67  4984.8  140.17  4988.6  140.67  5000.8  143.78
  5021.7  145.66  5036.0  149.75  5042.5  153.16  5050.3  154.51  5056.9  159.61
  5078.9  159.90  5085.5  161.57  5092.2  159.27  5099.8  165.40  5114.1  165.38
  5134.9  160.56  5163.5  161.20  5170.6  162.77  5177.8  171.51  5183.4  170.96
#Mann=5,-1,0
  4753.3    0.12       0  4828.6    0.05       0  4897.7    0.12       0
  4984.6    0.05       0  4988.6    0.12       0
Bank Sta=4984.6,4988.6
Exp/Cntr=0.3,0.1

Type RM Length L Ch R = 1,1316,117,117,117
BEGIN DESCRIPTION:
Mapping XS 4c41293c
END DESCRIPTION:
XS GIS Cut Line= 4
      2536262.90     13555325.53      2536238.16     13555179.67
      2536132.69     13555087.22      2535988.42     13555003.49
#Sta/Elev= 30
  4768.8  169.30  4809.9  166.73  4830.2  161.98  4870.8  156.32  4891.0  157.25
  4911.8  154.67  4957.1  151.15  4964.6  148.89  4972.2  149.24  4978.8  145.66
  4986.4  145.93  4993.1  141.67  4998.7  141.02  4998.9  140.52  5002.7  141.02
  5014.0  142.29  5035.8  147.53  5093.0  154.14  5108.8  160.25  5114.6  161.32
  5121.9  166.22  5130.3  172.13  5136.1  168.32  5146.0  168.65  5151.8  164.81
  5167.6  166.30  5181.5  165.58  5189.1  161.13  5194.9  160.62  5223.8  161.50
#Mann=6,-1,0
  4768.8    0.05       0  4911.8    0.12       0  4957.1    0.05       0
  4998.7    0.05       0  5002.7    0.05       0  5121.9    0.12       0
Bank Sta=4998.7,5002.7
Exp/Cntr=0.3,0.1

Type RM Length L Ch R = 1,1199,122,122,122
BEGIN DESCRIPTION:
Mapping XS aa47849b
END DESCRIPTION:
XS GIS Cut Line= 3
      2536378.76     13555281.19      2536279.82     13555055.97
      2536029.92     13554901.08
#Sta/Elev= 30
  4727.9  169.65  4797.1  163.16  4811.1  160.91  4854.8  160.39  4906.1  154.62
  4953.6  152.32  4964.0  150.84  4971.5  146.84  4973.7  140.69  4989.3  139.81
  4989.6  139.31  4993.3  139.81  5027.8  143.26  5037.3  143.26  5043.2  145.15
  5054.1  144.27  5064.5  145.74  5073.7  149.42  5079.9  149.75  5085.7  147.89
  5107.9  148.79  5122.4  149.98  5137.7  153.01  5144.3  152.47  5153.1  157.66
  5167.8  157.77  5195.6  162.45  5232.3  163.84  5244.6  163.41  5267.9  164.74
#Mann=8,-1,0
  4727.9    0.05       0  4906.1    0.12       0  4989.3    0.05       0
  4993.3    0.12       0  5054.1    0.05       0  5107.9     0.1       0
  5167.8    0.12       0  5244.6     0.1       0
Bank Sta=4989.3,4993.3
Exp/Cntr=0.3,0.1

Type RM Length L Ch R = 1,1077,115,115,115
BEGIN DESCRIPTION:
Mapping XS ff720d6b
END DESCRIPTION:
XS GIS Cut Line= 3
      2536419.15     13555291.69      2536367.06     13554986.96
      2536152.23     13554781.24
#Sta/Elev= 30
  4673.0  171.29  4676.6  171.15  4710.2  171.42  4720.4  174.94  4731.5  167.32
  4767.8  164.75  4877.6  155.73  4933.4  150.71  4978.0  141.27  5011.2  139.65
  5011.4  139.15  5015.2  139.65  5034.5  140.40  5041.5  143.49  5048.7  142.05
  5055.6  148.04  5058.1  146.77  5062.8  144.38  5069.8  149.57  5077.0  148.88
  5083.9  155.16  5091.1  152.96  5105.3  153.79  5140.5  158.86  5183.0  161.48
  5197.1  159.26  5225.4  160.18  5239.6  161.16  5253.7  165.43  5279.6  167.14
#Mann=8,-1,0
  4673.0    0.05       0  4676.6    0.12       0  4767.8    0.05       0
  4877.6    0.12       0  4978.0    0.05       0  5011.2    0.05       0
  5015.2    0.05       0  5058.1    0.12       0
Bank Sta=5011.2,5015.2
Exp/Cntr=0.3,0.1

Type RM Length L Ch R = 1,962,102,102,102
BEGIN DESCRIPTION:
Mapping XS 6596f40a
END DESCRIPTION:
XS GIS Cut Line= 3
      2536503.78     13555322.87      2536472.53     13554977.84
      2536288.85     13554746.30
#Sta/Elev= 30
  4647.4  174.97  4680.0  173.18  4715.6  172.05  4735.6  168.72  4779.2  166.90
  4795.5  164.72  4800.5  165.13  4836.0  158.11  4926.4  150.03  4942.7  146.99
  4976.6  140.21  4998.9  139.45  4999.1  138.95  5002.9  139.45  5044.2  142.16
  5058.6  144.34  5065.0  146.52  5073.0  146.80  5079.4  148.97  5092.0  147.72
  5101.5  148.59  5108.3  148.88  5114.6  150.88  5143.5  152.30  5164.3  154.67
  5236.4  164.92  5257.3  166.22  5271.7  172.49  5278.3  168.12  5289.4  168.55
#Mann=8,-1,0
  4647.4    0.05       0  4680.0    0.12       0  4779.2    0.05       0
  4942.7    0.12       0  4998.9    0.05       0  5002.9    0.12       0
  5092.0    0.05       0  5101.5    0.12       0
Bank Sta=4998.9,5002.9
Exp/Cntr=0.3,0.1

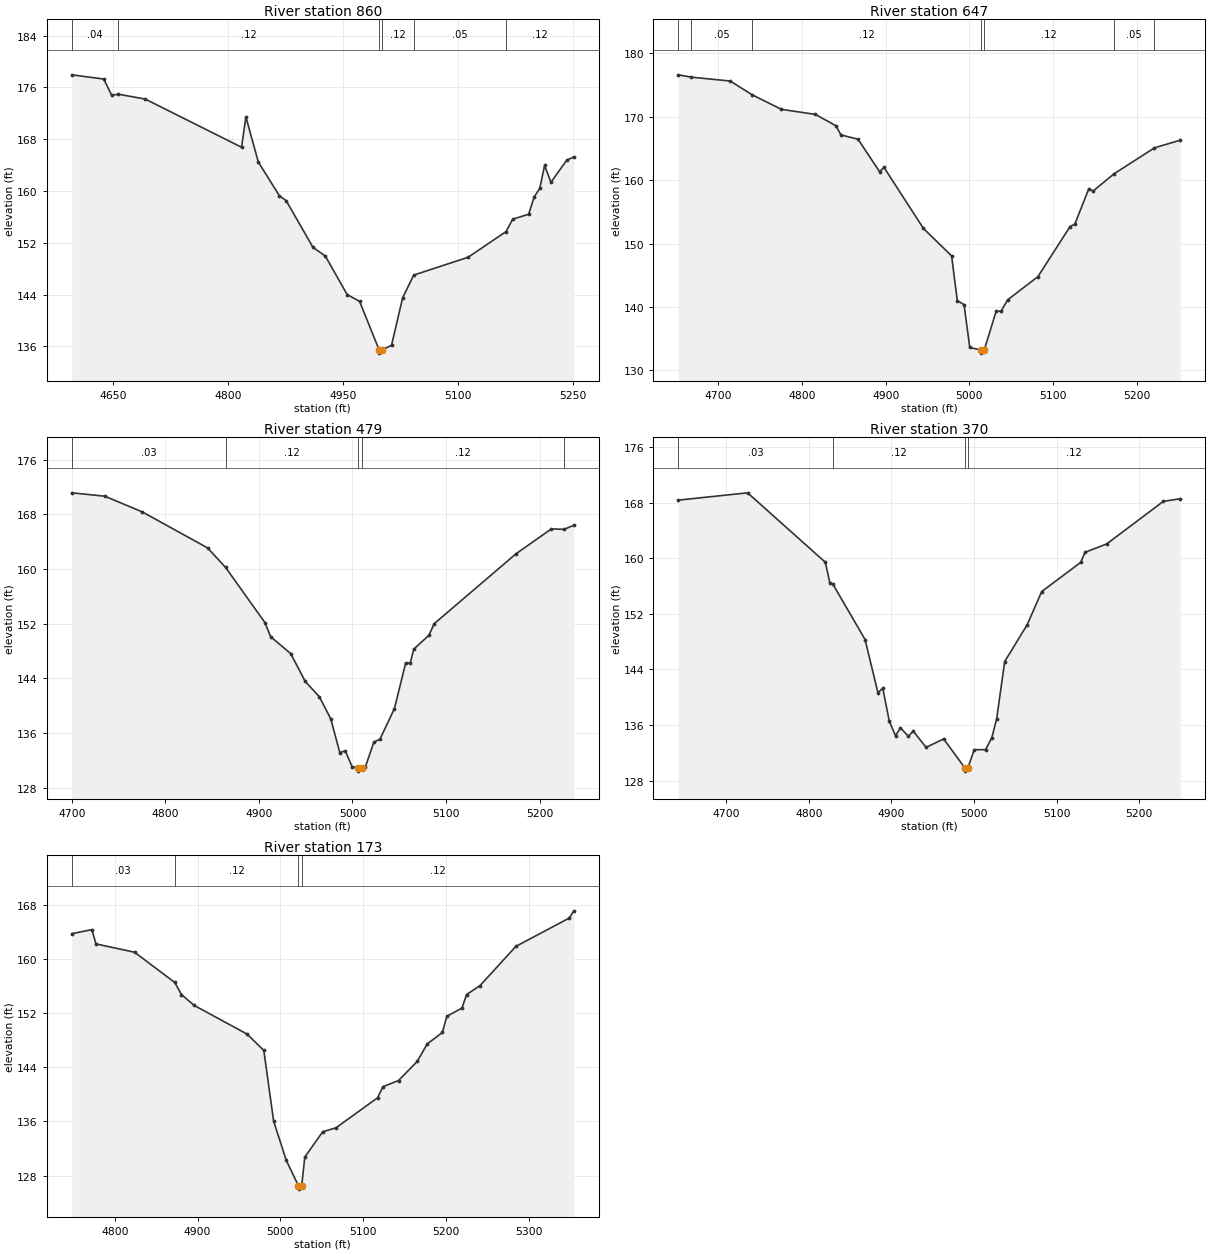
Type RM Length L Ch R = 1,860,213,213,213
BEGIN DESCRIPTION:
Mapping XS 507da652
END DESCRIPTION:
XS GIS Cut Line= 3
      2536747.28     13555251.31      2536571.49     13554925.76
      2536343.62     13554753.88
#Sta/Elev= 30
  4595.9  177.95  4637.6  177.30  4648.1  174.77  4656.5  174.96  4691.9  174.20
  4817.5  166.76  4823.2  171.44  4839.4  164.48  4867.0  159.25  4875.8  158.50
  4910.7  151.30  4926.9  149.94  4955.4  143.99  4971.6  142.94  4997.1  135.44
  4997.3  134.94  5001.1  135.44  5013.3  136.15  5027.8  143.48  5042.3  147.00
  5113.2  149.75  5162.9  153.73  5171.4  155.64  5192.3  156.40  5199.5  159.08
  5206.8  160.39  5213.1  163.94  5221.4  161.34  5242.2  164.79  5251.3  165.24
#Mann=6,-1,0
  4595.9    0.04       0  4656.5    0.12       0  4997.1    0.05       0
  5001.1    0.12       0  5042.3    0.05       0  5162.9    0.12       0
Bank Sta=4997.1,5001.1
Exp/Cntr=0.3,0.1

Type RM Length L Ch R = 1,647,168,168,168
BEGIN DESCRIPTION:
Mapping XS bb185171
END DESCRIPTION:
XS GIS Cut Line= 3
      2536814.98     13555216.12      2536752.48     13554886.70
      2536629.37     13554652.14
#Sta/Elev= 30
  4651.9  176.59  4667.7  176.22  4714.1  175.61  4740.3  173.44  4775.2  171.15
  4815.9  170.35  4840.4  168.56  4846.4  167.12  4866.8  166.44  4892.7  161.30
  4897.8  162.01  4945.0  152.38  4978.7  148.05  4985.5  141.00  4993.6  140.36
  5000.4  133.61  5013.7  133.22  5014.0  132.72  5017.7  133.22  5032.1  139.38
  5037.8  139.30  5045.6  141.11  5081.9  144.78  5120.3  152.67  5126.0  153.05
  5142.4  158.53  5148.0  158.29  5173.0  161.00  5221.2  165.08  5252.1  166.29
#Mann=7,-1,0
  4651.9    0.04       0  4667.7    0.05       0  4740.3    0.12       0
  5013.7    0.05       0  5017.7    0.12       0  5173.0    0.05       0
  5221.2    0.12       0
Bank Sta=5013.7,5017.7
Exp/Cntr=0.3,0.1

Type RM Length L Ch R = 1,479,109,109,109
BEGIN DESCRIPTION:
Mapping XS 109ad7f2
END DESCRIPTION:
XS GIS Cut Line= 4
      2536929.60     13555060.18      2536928.06     13554862.84
      2536843.61     13554721.57      2536690.06     13554637.89
#Sta/Elev= 30
  4699.9  171.14  4735.1  170.65  4775.1  168.36  4845.1  163.08  4864.3  160.23
  4906.4  152.15  4912.6  150.07  4934.0  147.60  4949.5  143.53  4964.6  141.29
  4976.8  138.05  4986.5  133.10  4992.3  133.38  4999.6  131.05  5005.9  130.90
  5006.2  130.40  5009.9  130.90  5013.7  130.97  5022.9  134.66  5029.3  135.05
  5044.9  139.56  5056.9  146.23  5061.8  146.23  5065.5  148.25  5081.7  150.28
  5087.4  151.98  5174.7  162.20  5212.7  165.86  5226.4  165.80  5236.7  166.39
#Mann=5,-1,0
  4699.9    0.03       0  4864.3    0.12       0  5005.9    0.05       0
  5009.9    0.12       0  5226.4    0.05       0
Bank Sta=5005.9,5009.9
Exp/Cntr=0.3,0.1

Type RM Length L Ch R = 1,370,197,197,197
BEGIN DESCRIPTION:
Mapping XS 9e9dc307
END DESCRIPTION:
XS GIS Cut Line= 4
      2537027.10     13555028.63      2537044.76     13554851.32
      2536909.64     13554626.37      2536750.73     13554573.40
#Sta/Elev= 30
  4641.8  168.35  4725.8  169.40  4820.0  159.41  4825.4  156.47  4828.7  156.34
  4868.1  148.30  4883.7  140.62  4889.5  141.32  4897.4  136.55  4905.0  134.45
  4910.9  135.61  4920.6  134.37  4926.4  135.13  4942.0  132.79  4963.3  134.00
  4988.7  129.87  4988.9  129.37  4992.7  129.87  5000.3  132.45  5014.0  132.46
  5021.6  134.17  5027.5  136.92  5037.2  145.13  5064.4  150.42  5082.0  155.20
  5129.2  159.39  5134.4  160.84  5160.8  162.05  5229.3  168.17  5249.9  168.55
#Mann=4,-1,0
  4641.8    0.03       0  4828.7    0.12       0  4988.7    0.05       0
  4992.7    0.12       0
Bank Sta=4988.7,4992.7
Exp/Cntr=0.3,0.1

Type RM Length L Ch R = 1,173,0,0,0
BEGIN DESCRIPTION:
Mapping XS 018e5f13
END DESCRIPTION:
XS GIS Cut Line= 4
      2537084.68     13554990.27      2537124.60     13554785.30
      2537042.46     13554638.66      2536830.41     13554549.86
#Sta/Elev= 30
  4747.9  163.75  4772.1  164.35  4777.2  162.24  4823.8  161.01  4872.4  156.54
  4880.5  154.75  4895.9  153.15  4959.8  148.91  4980.0  146.50  4991.9  136.03
  5007.1  130.27  5021.8  126.50  5022.1  126.00  5025.8  126.50  5029.5  130.73
  5051.2  134.48  5067.2  135.06  5117.5  139.50  5124.0  141.14  5142.8  142.05
  5165.4  144.87  5177.4  147.45  5195.8  149.15  5201.2  151.54  5219.5  152.76
  5225.0  154.75  5241.3  156.08  5284.7  161.88  5349.3  166.07  5354.7  167.13
#Mann=4,-1,0
  4747.9    0.03       0  4872.4    0.12       0  5021.8    0.05       0
  5025.8    0.12       0
Bank Sta=5021.8,5025.8
Exp/Cntr=0.3,0.1

Chan Stop Cuts=-1