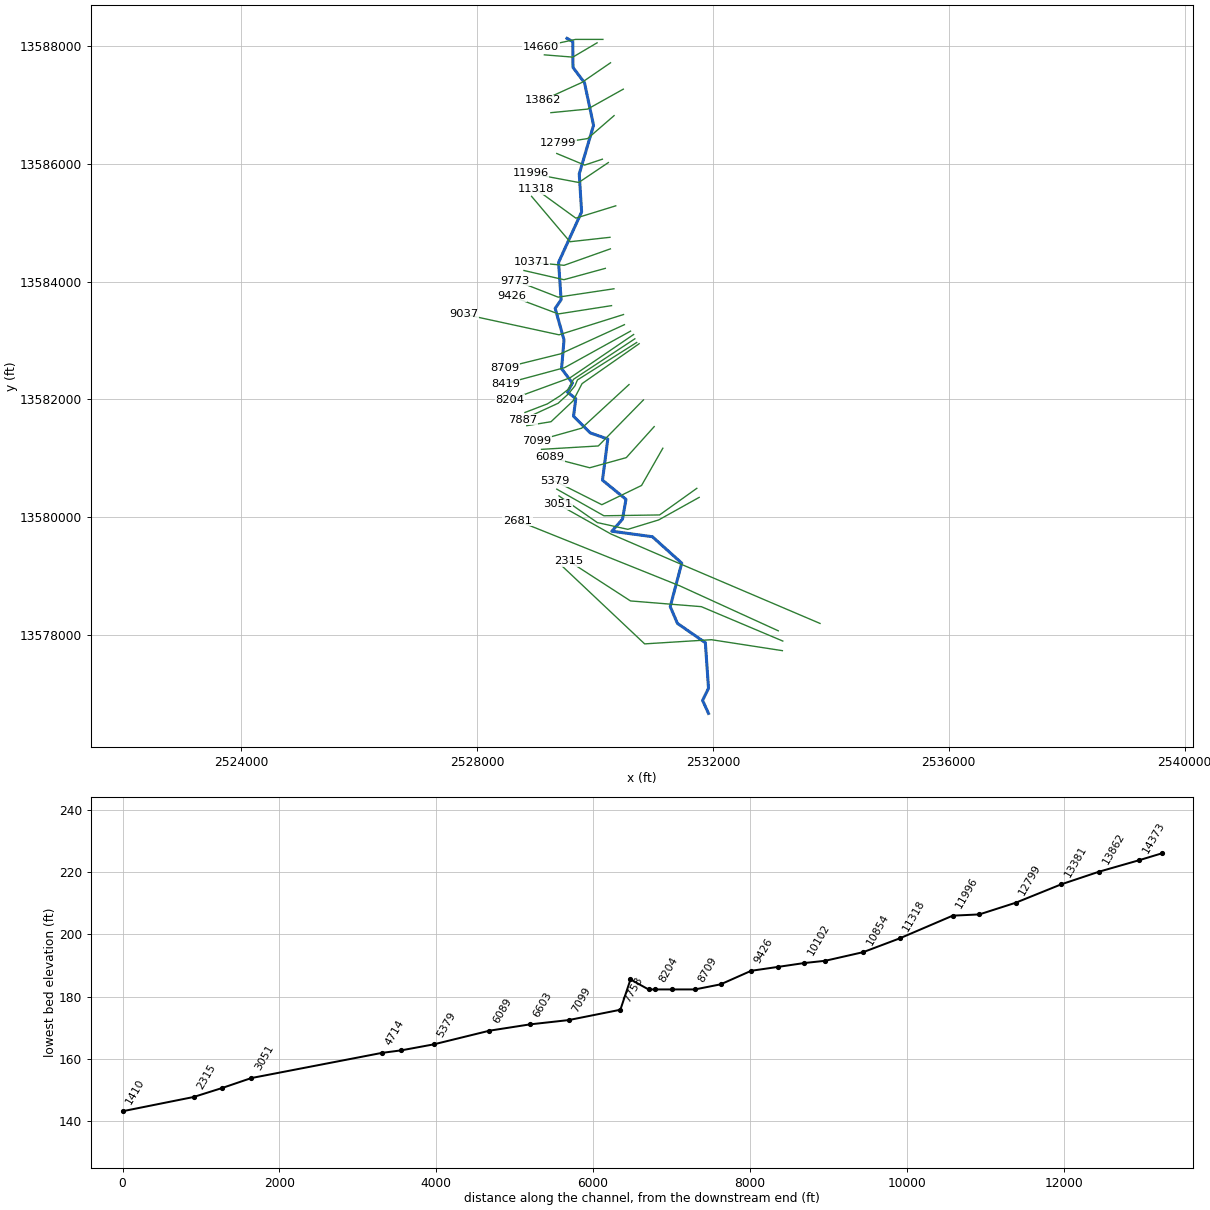
--- TRIB 1 TO OAXLEY BRANCH.prj (project) ---

Proj Title=TRIB 1 TO OAXLEY BRANCH Base Level Engineering
Current Plan=p01
Default Exp/Contr=0.3,0.1
English Units
Geom File=g01
Flow File=f01
Plan File=p01
BEGIN DESCRIPTION:
TRIB 1 TO OAXLEY BRANCH
END DESCRIPTION:

--- TRIB 1 TO OAXLEY BRANCH.p01 (plan) ---

Plan Title=Multiple Run
Short Identifier=Multiple
Geom File=g01
Flow File=f01
Subcritical Flow
K Sum by GR= 0
Std Step Tol= 0.01
Critical Tol= 0.01
Num of Std Step Trials= 20
Max Error Tol= 0.3
Flow Tol Ratio= 0.001
Split Flow NTrial= 30
Split Flow Tol= 0.02
Split Flow Ratio= 0.02
Log Output Level= 0
Friction Slope Method= 1
Unsteady Friction Slope Method= 2
Unsteady Bridges Friction Slope Method= 1
Parabolic Critical Depth
Global Vel Dist=  1 , 1 , 1
Global Log Level= 0
CheckData=True
Encroach Param= -1, 0, 0, 0
BEGIN DESCRIPTION:
Multiple Run
END DESCRIPTION:

--- TRIB 1 TO OAXLEY BRANCH.f01 (steady flow) ---

Flow Title=Multiple
Number of Profiles=7
Profile Names=10-year,25-year,50-year,1pct_min,100-year,1pct_plu,500-year
River Rch & RM= TRIB 1 TO OAXLEY,Reach-1,14660
     292     451     590     375     749    1494    1191
River Rch & RM= TRIB 1 TO OAXLEY,Reach-1,13862
     345     538     708     453     904    1804    1455
River Rch & RM= TRIB 1 TO OAXLEY,Reach-1,12335
     662    1081    1465     964    1923    3836    3276
River Rch & RM= TRIB 1 TO OAXLEY,Reach-1,10371
     889    1472    2012    1332    2658    5304    4597
River Rch & RM= TRIB 1 TO OAXLEY,Reach-1,4966
    1084    1813    2495    1662    3316    6616    5803
River Rch & RM= TRIB 1 TO OAXLEY,Reach-1,2681
    1680    2861    3988    2687    5360   10695    9596
Boundary for River Rch & Prof#=TRIB 1 TO OAXLEY,Reach-1,1
Up Type=0
Dn Type=3
Dn Slope=0.005
Boundary for River Rch & Prof#=TRIB 1 TO OAXLEY,Reach-1,2
Up Type=0
Dn Type=3
Dn Slope=0.005
Boundary for River Rch & Prof#=TRIB 1 TO OAXLEY,Reach-1,3
Up Type=0
Dn Type=3
Dn Slope=0.005
Boundary for River Rch & Prof#=TRIB 1 TO OAXLEY,Reach-1,4
Up Type=0
Dn Type=3
Dn Slope=0.005
Boundary for River Rch & Prof#=TRIB 1 TO OAXLEY,Reach-1,5
Up Type=0
Dn Type=3
Dn Slope=0.005
Boundary for River Rch & Prof#=TRIB 1 TO OAXLEY,Reach-1,6
Up Type=0
Dn Type=3
Dn Slope=0.005
Boundary for River Rch & Prof#=TRIB 1 TO OAXLEY,Reach-1,7
Up Type=0
Dn Type=3
Dn Slope=0.005

--- TRIB 1 TO OAXLEY BRANCH.g01 (geometry) ---

Geom Title=Existing Conditions

River Reach=TRIB 1 TO OAXLEY,Reach-1
Reach XY= 30
      2529525.00     13588125.00      2529623.07     13588069.31
      2529627.15     13587630.97      2529821.46     13587373.53
      2529975.49     13586649.96      2529732.56     13585825.00
      2529773.04     13585180.89      2529382.32     13584325.10
      2529425.04     13583690.34      2529324.64     13583545.21
      2529474.61     13583009.84      2529432.79     13582521.58
      2529616.98     13582278.31      2529532.28     13582124.90
      2529673.87     13582012.97      2529636.24     13581715.00
      2529918.55     13581432.74      2530217.23     13581328.44
      2530127.06     13580630.85      2530525.47     13580304.84
      2530465.87     13579968.26      2530285.82     13579764.57
      2530973.45     13579671.25      2531471.47     13579223.54
      2531276.20     13578485.51      2531398.01     13578201.53
      2531871.96     13577873.58      2531925.41     13577100.00
      2531824.71     13576895.18      2531925.00     13576675.00

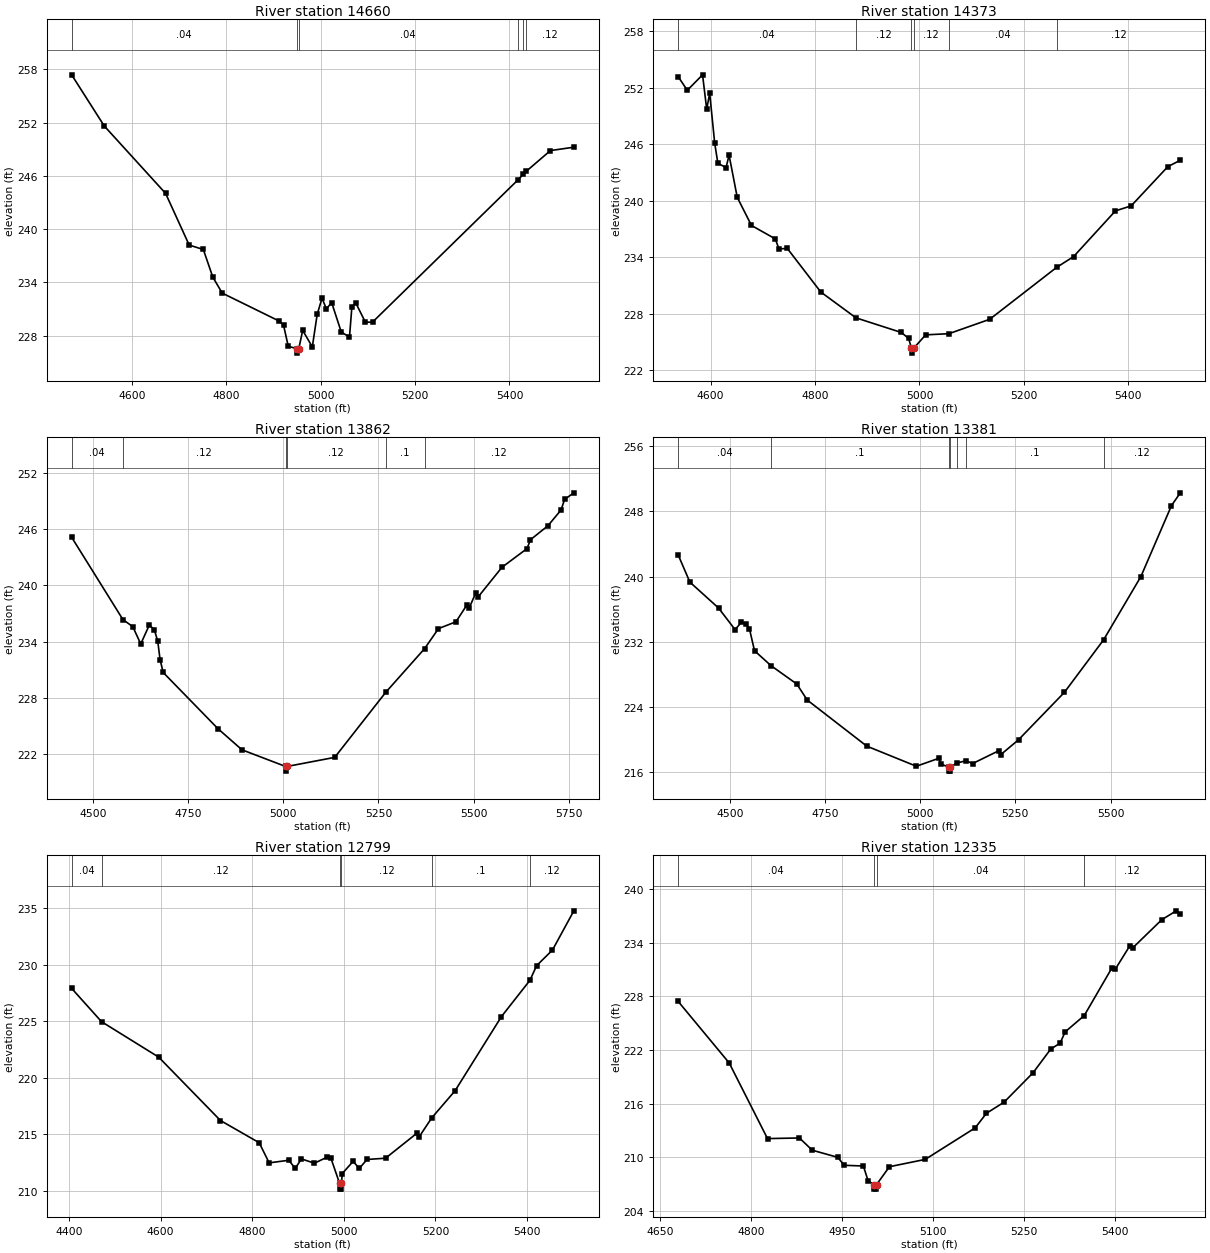
Type RM Length L Ch R = 1,14660,287,287,287
BEGIN DESCRIPTION:
TRIB 1 TO OAKLEY BRANCH 29.0
END DESCRIPTION:
XS GIS Cut Line= 3
      2530134.09     13588106.93      2529669.40     13588106.93
      2529083.50     13587978.98
#Sta/Elev= 30
  4472.1  257.37  4541.2  251.61  4671.2  244.02  4721.2  238.20  4751.2  237.70
  4771.2  234.60  4791.2  232.79  4911.2  229.66  4921.2  229.18  4931.2  226.80
  4949.5  226.53  4949.8  226.03  4953.5  226.53  4961.8  228.59  4982.2  226.73
  4992.5  230.39  5002.7  232.21  5012.0  231.02  5023.2  231.72  5043.6  228.40
  5061.0  227.84  5066.1  231.28  5074.4  231.67  5094.8  229.50  5110.0  229.53
  5417.5  245.51  5429.2  246.16  5435.5  246.50  5486.9  248.84  5536.5  249.22
#Mann=6,-1,0
  4472.1    0.04       0  4949.5    0.04       0  4953.5    0.04       0
  5417.5    0.12       0  5429.2    0.04       0  5435.5    0.12       0
Bank Sta=4949.5,4953.5
Exp/Cntr=0.3,0.1

Type RM Length L Ch R = 1,14373,511,511,511
BEGIN DESCRIPTION:
TRIB 1 TO OAKLEY BRANCH 28.0
END DESCRIPTION:
XS GIS Cut Line= 3
      2530035.31     13588048.82      2529623.84     13587806.28
      2529141.21     13587844.84
#Sta/Elev= 30
  4537.8  253.17  4555.4  251.72  4584.6  253.36  4592.5  249.73  4598.3  251.39
  4607.8  246.14  4613.9  243.98  4629.6  243.52  4635.4  244.84  4651.0  240.37
  4678.3  237.38  4723.9  235.96  4731.0  234.88  4746.7  234.96  4811.1  230.32
  4878.5  227.58  4965.3  226.03  4979.3  225.40  4984.7  224.34  4985.0  223.84
  4988.7  224.34  5011.9  225.78  5056.3  225.90  5134.6  227.43  5262.6  232.93
  5295.2  234.08  5375.4  238.93  5405.5  239.46  5475.7  243.62  5499.6  244.30
#Mann=6,-1,0
  4537.8    0.04       0  4878.5    0.12       0  4984.7    0.05       0
  4988.7    0.12       0  5056.3    0.04       0  5262.6    0.12       0
Bank Sta=4984.7,4988.7
Exp/Cntr=0.3,0.1

Type RM Length L Ch R = 1,13862,481,481,481
BEGIN DESCRIPTION:
TRIB 1 TO OAKLEY BRANCH 27.0
END DESCRIPTION:
XS GIS Cut Line= 3
      2530263.21     13587710.30      2529775.00     13587375.00
      2529113.00     13587074.43
#Sta/Elev= 30
  4444.1  245.14  4578.9  236.34  4604.7  235.59  4625.6  233.74  4648.2  235.77
  4661.5  235.24  4670.3  234.02  4676.4  232.07  4684.6  230.69  4828.6  224.68
  4891.5  222.43  5006.0  220.65  5006.2  220.15  5010.0  220.65  5135.2  221.62
  5269.0  228.56  5371.3  233.24  5407.8  235.38  5453.7  236.11  5482.5  237.91
  5488.0  237.53  5505.6  239.19  5511.1  238.72  5574.5  241.93  5640.4  243.93
  5649.5  244.88  5695.3  246.37  5729.7  248.05  5739.2  249.19  5763.4  249.89
#Mann=6,-1,0
  4444.1    0.04       0  4578.9    0.12       0  5006.0    0.05       0
  5010.0    0.12       0  5269.0     0.1       0  5371.3    0.12       0
Bank Sta=5006,5010
Exp/Cntr=0.3,0.1

Type RM Length L Ch R = 1,13381,582,582,582
BEGIN DESCRIPTION:
TRIB 1 TO OAKLEY BRANCH 26.0
END DESCRIPTION:
XS GIS Cut Line= 3
      2530480.22     13587263.25      2529875.00     13586925.00
      2529251.91     13586863.94
#Sta/Elev= 30
  4364.0  242.68  4394.9  239.32  4470.2  236.14  4513.7  233.48  4529.6  234.36
  4541.8  234.20  4551.3  233.60  4564.7  230.89  4608.0  229.06  4675.8  226.80
  4703.3  224.83  4859.7  219.17  4989.9  216.70  5049.3  217.68  5054.5  216.96
  5075.4  216.60  5075.7  216.10  5079.2  216.10  5079.4  216.60  5096.3  217.09
  5120.3  217.38  5137.7  217.03  5207.1  218.62  5212.1  218.14  5258.3  219.95
  5378.9  225.78  5482.0  232.24  5579.8  240.00  5660.2  248.72  5683.4  250.29
#Mann=7,-1,0
  4364.0    0.04       0  4608.0     0.1       0  5075.4    0.05       0
  5079.4     0.1       0  5096.3    0.12       0  5120.3     0.1       0
  5482.0    0.12       0
Bank Sta=5075.4,5079.4
Exp/Cntr=0.3,0.1

Type RM Length L Ch R = 1,12799,464,464,464
BEGIN DESCRIPTION:
TRIB 1 TO OAKLEY BRANCH 25.0
END DESCRIPTION:
XS GIS Cut Line= 3
      2530323.93     13586813.99      2529875.00     13586425.00
      2529378.91     13586347.62
#Sta/Elev= 30
  4405.9  227.90  4471.1  224.96  4595.8  221.83  4730.7  216.23  4815.2  214.27
  4837.0  212.49  4879.8  212.72  4894.0  212.00  4907.3  212.84  4935.8  212.46
  4964.3  213.01  4971.9  212.89  4990.8  210.67  4991.0  210.17  4994.5  210.17
  4994.8  210.67  4996.6  211.55  5020.2  212.62  5033.8  212.00  5050.5  212.79
  5091.0  212.90  5159.5  215.11  5164.5  214.80  5192.0  216.47  5242.8  218.86
  5344.0  225.41  5406.1  228.61  5420.8  229.91  5455.4  231.29  5502.0  234.75
#Mann=6,-1,0
  4405.9    0.04       0  4471.1    0.12       0  4990.8    0.05       0
  4994.8    0.12       0  5192.0     0.1       0  5406.1    0.12       0
Bank Sta=4990.8,4994.8
Exp/Cntr=0.3,0.1

Type RM Length L Ch R = 1,12335,339,339,339
BEGIN DESCRIPTION:
TRIB 1 TO OAKLEY BRANCH 24.0
END DESCRIPTION:
XS GIS Cut Line= 3
      2530124.97     13586074.99      2529825.00     13585975.00
      2529351.73     13586171.67
#Sta/Elev= 30
  4679.3  227.45  4763.6  220.55  4826.8  212.08  4879.5  212.15  4900.6  210.78
  4942.8  209.98  4953.3  209.09  4985.0  209.01  4992.9  207.34  5002.7  206.92
  5003.0  206.42  5006.5  206.42  5006.7  206.92  5028.0  208.93  5087.1  209.75
  5169.5  213.28  5188.0  214.91  5217.2  216.16  5265.0  219.45  5294.2  222.11
  5309.5  222.76  5318.1  224.04  5349.5  225.86  5395.1  231.19  5400.5  231.03
  5424.4  233.64  5429.8  233.46  5477.5  236.60  5501.4  237.59  5508.0  237.27
#Mann=4,-1,0
  4679.3    0.04       0  5002.7    0.04       0  5006.7    0.04       0
  5349.5    0.12       0
Bank Sta=5002.7,5006.7
Exp/Cntr=0.3,0.1

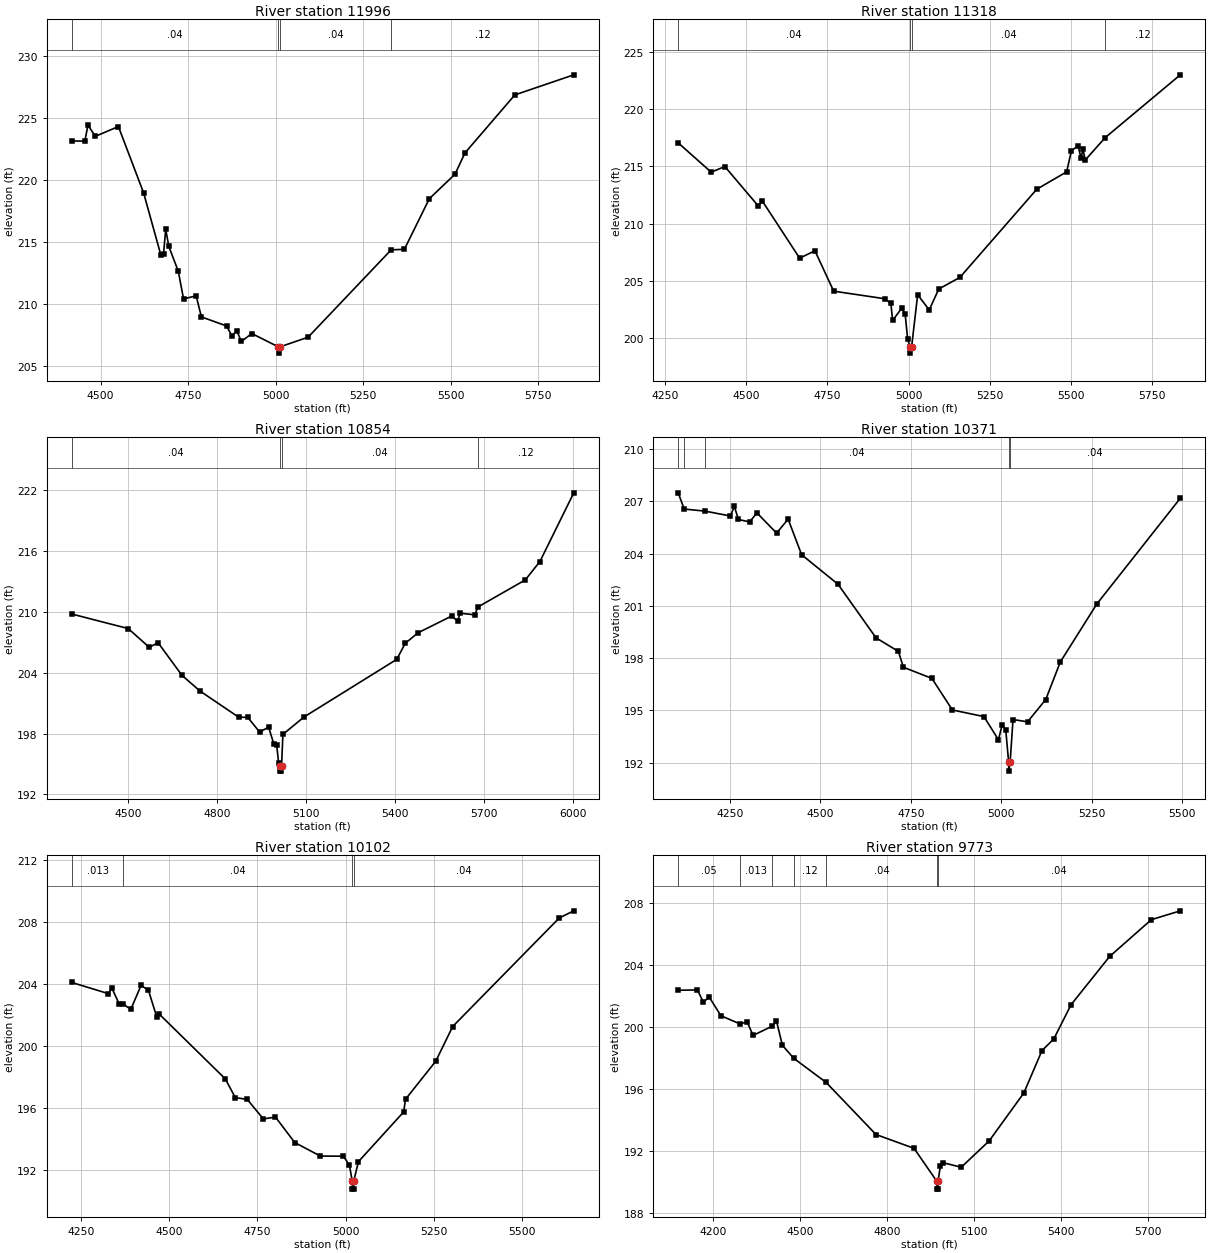
Type RM Length L Ch R = 1,11996,678,678,678
BEGIN DESCRIPTION:
TRIB 1 TO OAKLEY BRANCH 23.0
END DESCRIPTION:
XS GIS Cut Line= 3
      2530226.27     13586017.56      2529724.56     13585680.18
      2528909.56     13585833.02
#Sta/Elev= 30
  4417.3  223.13  4455.0  223.11  4463.8  224.41  4484.9  223.50  4550.8  224.29
  4622.8  218.94  4671.9  213.94  4679.8  214.03  4685.8  216.01  4694.8  214.62
  4721.8  212.62  4736.8  210.39  4772.8  210.64  4787.8  208.94  4859.8  208.21
  4874.8  207.40  4888.8  207.83  4901.8  206.96  4931.8  207.60  5007.8  206.52
  5008.1  206.02  5011.8  206.52  5092.7  207.31  5329.7  214.35  5367.4  214.39
  5438.6  218.47  5512.0  220.45  5540.3  222.16  5682.8  226.84  5851.1  228.46
#Mann=4,-1,0
  4417.3    0.04       0  5007.8    0.04       0  5011.8    0.04       0
  5329.7    0.12       0
Bank Sta=5007.8,5011.8
Exp/Cntr=0.3,0.1

Type RM Length L Ch R = 1,11318,464,464,464
BEGIN DESCRIPTION:
TRIB 1 TO OAKLEY BRANCH 22.0
END DESCRIPTION:
XS GIS Cut Line= 3
      2530352.18     13585284.08      2529675.00     13585075.00
      2528998.04     13585566.17
#Sta/Elev= 30
  4291.0  217.06  4392.7  214.50  4434.6  214.99  4538.1  211.53  4549.7  211.99
  4664.8  206.99  4711.8  207.64  4769.5  204.11  4926.5  203.45  4945.5  203.05
  4950.8  201.55  4978.2  202.60  4989.3  202.15  4997.1  199.92  5005.1  199.20
  5005.3  198.70  5009.1  199.20  5027.9  203.80  5063.5  202.47  5092.9  204.30
  5157.8  205.31  5394.4  213.01  5486.4  214.53  5501.1  216.38  5521.9  216.79
  5530.5  215.72  5536.6  216.53  5543.3  215.55  5605.1  217.52  5836.1  223.00
#Mann=4,-1,0
  4291.0    0.04       0  5005.1    0.04       0  5009.1    0.04       0
  5605.1    0.12       0
Bank Sta=5005.1,5009.1
Exp/Cntr=0.3,0.1

Type RM Length L Ch R = 1,10854,483,483,483
BEGIN DESCRIPTION:
TRIB 1 TO OAKLEY BRANCH 21.0
END DESCRIPTION:
XS GIS Cut Line= 3
      2530254.53     13584750.22      2529575.00     13584675.00
      2528924.22     13585444.67
#Sta/Elev= 30
  4311.0  209.80  4501.7  208.36  4572.1  206.52  4602.3  206.96  4682.8  203.74
  4743.2  202.20  4873.9  199.61  4904.1  199.60  4944.3  198.15  4974.6  198.63
  4992.2  196.96  5001.8  196.85  5008.4  195.07  5014.1  194.79  5014.4  194.29
  5017.9  194.29  5018.1  194.79  5022.7  197.92  5094.1  199.64  5406.1  205.32
  5434.7  206.90  5477.6  207.94  5590.7  209.59  5611.6  209.11  5619.3  209.88
  5668.7  209.72  5680.1  210.50  5839.1  213.16  5888.5  214.98  6002.6  221.76
#Mann=4,-1,0
  4311.0    0.04       0  5014.1    0.04       0  5018.1    0.04       0
  5680.1    0.12       0
Bank Sta=5014.1,5018.1
Exp/Cntr=0.3,0.1

Type RM Length L Ch R = 1,10371,269,269,269
BEGIN DESCRIPTION:
TRIB 1 TO OAKLEY BRANCH 20.0
END DESCRIPTION:
XS GIS Cut Line= 3
      2530261.07     13584554.06      2529475.00     13584275.00
      2528925.00     13584325.00
#Sta/Elev= 30
  4107.8  207.49  4124.4  206.56  4181.9  206.44  4252.2  206.16  4262.8  206.72
  4274.1  205.96  4305.2  205.82  4325.2  206.34  4379.5  205.18  4411.4  205.98
  4448.6  203.94  4549.3  202.24  4654.0  199.17  4715.8  198.39  4729.7  197.48
  4808.4  196.84  4864.8  195.03  4952.0  194.65  4992.1  193.32  5002.2  194.17
  5012.2  193.90  5020.3  192.02  5020.5  191.52  5024.3  192.02  5032.3  194.48
  5072.5  194.35  5122.7  195.63  5162.8  197.78  5263.3  201.10  5494.2  207.18
#Mann=5,-1,0
  4107.8    0.04       0  4124.4   0.013       0  4181.9    0.04       0
  5020.3    0.04       0  5024.3    0.04       0
Bank Sta=5020.3,5024.3
Exp/Cntr=0.3,0.1

Type RM Length L Ch R = 1,10102,329,329,329
BEGIN DESCRIPTION:
TRIB 1 TO OAKLEY BRANCH 19.0
END DESCRIPTION:
XS GIS Cut Line= 3
      2530175.09     13584223.31      2529472.74     13584030.94
      2528794.86     13584186.86
#Sta/Elev= 30
  4223.4  204.10  4327.2  203.38  4337.5  203.73  4358.3  202.71  4370.4  202.70
  4391.0  202.36  4420.3  203.91  4441.2  203.59  4465.1  201.85  4472.3  202.05
  4659.0  197.89  4687.5  196.68  4721.2  196.57  4766.9  195.31  4801.3  195.43
  4856.0  193.79  4928.5  192.92  4993.8  192.91  5010.9  192.35  5019.1  191.29
  5019.4  190.79  5022.9  190.79  5023.1  191.29  5036.6  192.56  5164.8  195.76
  5170.2  196.58  5255.9  199.03  5303.8  201.26  5606.0  208.25  5647.2  208.71
#Mann=4,-1,0
  4223.4   0.013       0  4370.4    0.04       0  5019.1    0.04       0
  5023.1    0.04       0
Bank Sta=5019.1,5023.1
Exp/Cntr=0.3,0.1

Type RM Length L Ch R = 1,9773,347,347,347
BEGIN DESCRIPTION:
TRIB 1 TO OAKLEY BRANCH 18.0
END DESCRIPTION:
XS GIS Cut Line= 3
      2530320.97     13583876.96      2529374.89     13583735.05
      2528649.56     13584017.38
#Sta/Elev= 30
  4078.3  202.39  4145.0  202.41  4165.2  201.62  4185.5  201.95  4225.9  200.75
  4290.6  200.23  4316.9  200.34  4337.1  199.48  4403.9  200.08  4418.0  200.41
  4438.2  198.85  4477.1  198.01  4589.4  196.45  4761.8  193.09  4893.3  192.20
  4972.2  190.07  4972.4  189.57  4975.9  189.57  4976.2  190.07  4984.3  191.07
  4994.4  191.27  5056.3  190.98  5152.9  192.68  5272.7  195.77  5335.3  198.50
  5376.1  199.25  5435.9  201.46  5569.2  204.57  5713.2  206.94  5813.3  207.51
#Mann=7,-1,0
  4078.3    0.05       0  4290.6   0.013       0  4403.9    0.04       0
  4477.1    0.12       0  4589.4    0.04       0  4972.2    0.04       0
  4976.2    0.04       0
Bank Sta=4972.2,4976.2
Exp/Cntr=0.3,0.1

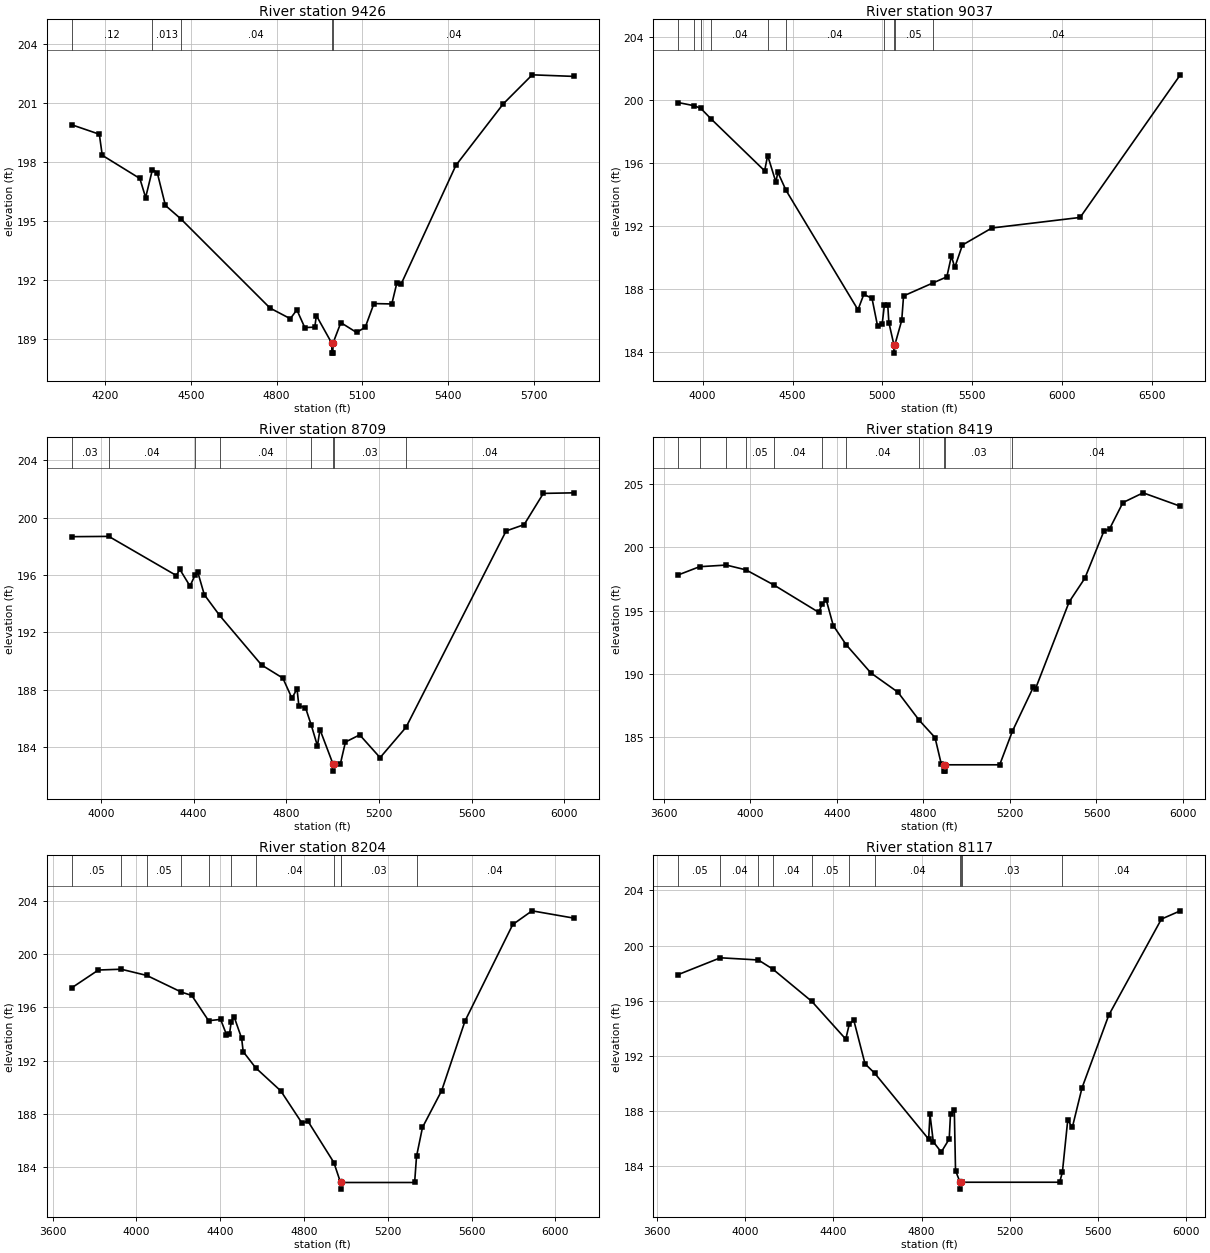
Type RM Length L Ch R = 1,9426,389,389,389
BEGIN DESCRIPTION:
Mapping XS 72035986
END DESCRIPTION:
XS GIS Cut Line= 3
      2530280.29     13583591.02      2529379.26     13583450.40
      2528588.75     13583746.83
#Sta/Elev= 30
  4083.6  199.91  4180.0  199.43  4190.2  198.36  4321.7  197.18  4342.0  196.21
  4365.7  197.63  4382.5  197.48  4411.1  195.81  4464.8  195.13  4777.2  190.59
  4848.0  190.05  4870.9  190.50  4898.6  189.60  4933.7  189.62  4939.1  190.21
  4993.2  188.80  4993.4  188.30  4996.9  188.30  4997.2  188.80  5024.8  189.85
  5080.0  189.35  5110.3  189.62  5140.5  190.82  5203.0  190.80  5220.6  191.86
  5235.0  191.79  5427.3  197.85  5592.7  200.97  5694.3  202.45  5839.8  202.37
#Mann=5,-1,0
  4083.6    0.12       0  4365.7   0.013       0  4464.8    0.04       0
  4993.2    0.04       0  4997.2    0.04       0
Bank Sta=4993.2,4997.2
Exp/Cntr=0.3,0.1

Type RM Length L Ch R = 1,9037,328,328,328
BEGIN DESCRIPTION:
Mapping XS d1469f56
END DESCRIPTION:
XS GIS Cut Line= 3
      2530483.44     13583439.99      2529389.67     13583096.23
      2527780.29     13583445.19
#Sta/Elev= 30
  3864.2  199.85  3952.9  199.65  3989.8  199.48  4047.1  198.81  4344.8  195.52
  4361.7  196.49  4407.6  194.80  4418.1  195.43  4463.9  194.28  4864.2  186.70
  4896.6  187.68  4942.2  187.43  4973.7  185.64  4999.0  185.81  5010.9  186.98
  5029.7  187.03  5036.0  185.89  5064.7  184.45  5064.9  183.95  5068.7  184.45
  5107.6  186.03  5117.8  187.58  5282.6  188.41  5358.6  188.79  5383.9  190.11
  5402.6  189.39  5445.3  190.81  5609.0  191.89  6100.1  192.56  6657.5  201.61
#Mann=10,-1,0
  3864.2    0.05       0  3952.9    0.12       0  3989.8    0.03       0
  4047.1    0.04       0  4361.7   0.013       0  4463.9    0.04       0
  5010.9    0.05       0  5064.7    0.04       0  5068.7    0.05       0
  5282.6    0.04       0
Bank Sta=5064.7,5068.7
Exp/Cntr=0.3,0.1

Type RM Length L Ch R = 1,8709,290,290,290
BEGIN DESCRIPTION:
Mapping XS c1f4cb98
END DESCRIPTION:
XS GIS Cut Line= 3
      2530499.06     13583268.11      2529415.71     13582773.31
      2528468.92     13582539.22
#Sta/Elev= 30
  3874.2  198.67  4034.0  198.69  4325.4  195.96  4340.4  196.39  4384.4  195.22
  4405.7  195.98  4417.4  196.22  4446.1  194.62  4512.4  193.17  4692.9  189.72
  4785.0  188.80  4824.1  187.40  4846.1  188.05  4854.1  186.86  4882.6  186.74
  4907.4  185.53  4934.2  184.07  4945.1  185.21  5001.2  182.81  5001.5  182.31
  5005.2  182.81  5033.0  182.81  5055.0  184.34  5116.5  184.84  5204.5  183.25
  5316.4  185.37  5748.3  199.07  5826.0  199.51  5908.9  201.69  6040.5  201.73
#Mann=8,-1,0
  3874.2    0.03       0  4034.0    0.04       0  4405.7   0.013       0
  4512.4    0.04       0  4907.4    0.03       0  5001.2    0.03       0
  5005.2    0.03       0  5316.4    0.04       0
Bank Sta=5001.2,5005.2
Exp/Cntr=0.3,0.1

Type RM Length L Ch R = 1,8419,215,215,215
BEGIN DESCRIPTION:
Mapping XS 6432f5ca
END DESCRIPTION:
XS GIS Cut Line= 3
      2530603.26     13583158.75      2529483.42     13582538.94
      2528479.06     13582268.33
#Sta/Elev= 30
  3667.2  197.82  3765.8  198.47  3889.3  198.60  3980.2  198.22  4110.7  197.01
  4316.7  194.86  4332.1  195.53  4351.4  195.83  4383.5  193.82  4442.8  192.31
  4557.5  190.07  4682.4  188.55  4780.2  186.34  4853.9  184.96  4882.7  182.87
  4896.7  182.81  4897.0  182.31  4900.6  182.31  4900.8  182.81  5152.6  182.81
  5211.5  185.47  5308.0  188.94  5318.3  188.83  5473.7  195.69  5546.2  197.56
  5634.6  201.30  5660.1  201.45  5722.2  203.54  5815.4  204.31  5987.3  203.25
#Mann=11,-1,0
  3667.2    0.03       0  3765.8    0.05       0  3889.3    0.04       0
  3980.2    0.05       0  4110.7    0.04       0  4332.1   0.013       0
  4442.8    0.04       0  4780.2    0.03       0  4896.7    0.03       0
  4900.8    0.03       0  5211.5    0.04       0
Bank Sta=4896.7,4900.8
Exp/Cntr=0.3,0.1

Type RM Length L Ch R = 1,8204,87,87,87
BEGIN DESCRIPTION:
Mapping XS a4f959eb
END DESCRIPTION:
XS GIS Cut Line= 3
      2530655.27     13583101.42      2529577.17     13582367.06
      2528551.10     13581992.05
#Sta/Elev= 30
  3691.4  197.48  3818.5  198.82  3927.3  198.88  4049.7  198.41  4214.2  197.16
  4264.4  196.90  4344.6  195.00  4402.0  195.10  4429.8  193.96  4444.0  193.97
  4452.6  194.90  4466.1  195.31  4502.4  193.67  4509.7  192.67  4569.4  191.45
  4689.3  189.71  4791.0  187.27  4818.0  187.45  4942.8  184.31  4974.5  182.81
  4974.8  182.31  4978.6  182.81  5328.2  182.81  5337.3  184.78  5365.7  186.96
  5457.3  189.73  5568.8  194.98  5796.7  202.25  5888.8  203.28  6088.3  202.73
#Mann=11,-1,0
  3691.4    0.05       0  3927.3    0.04       0  4049.7    0.05       0
  4214.2    0.04       0  4344.6    0.05       0  4452.6   0.013       0
  4569.4    0.04       0  4942.8    0.03       0  4974.5    0.03       0
  4978.6    0.03       0  5337.3    0.04       0
Bank Sta=4974.5,4978.6
Exp/Cntr=0.3,0.1

Type RM Length L Ch R = 1,8117,230,230,230
BEGIN DESCRIPTION:
Mapping XS a3bb1b13
END DESCRIPTION:
XS GIS Cut Line= 6
      2530676.15     13583028.53      2529634.46     13582341.02
      2529556.34     13582179.56      2529405.30     13582059.77
      2529191.76     13581924.35      2528811.58     13581778.53
#Sta/Elev= 30
  3695.1  197.89  3886.7  199.11  4059.0  198.95  4124.4  198.29  4302.0  195.94
  4456.1  193.20  4471.5  194.27  4492.2  194.59  4543.4  191.41  4587.2  190.73
  4832.4  185.94  4838.4  187.76  4853.5  185.75  4889.6  185.00  4925.8  185.95
  4931.7  187.78  4948.9  188.09  4954.5  183.66  4974.9  182.81  4975.2  182.31
  4979.1  182.81  4982.0  182.81  5427.6  182.81  5439.9  183.55  5464.0  187.31
  5485.2  186.81  5528.9  189.66  5650.4  194.94  5889.5  201.92  5975.4  202.52
#Mann=11,-1,0
  3695.1    0.05       0  3886.7    0.04       0  4059.0    0.05       0
  4124.4    0.04       0  4302.0    0.05       0  4471.5   0.013       0
  4587.2    0.04       0  4974.9    0.03       0  4979.1    0.04       0
  4982.0    0.03       0  5439.9    0.04       0
Bank Sta=4974.9,4979.1
Exp/Cntr=0.3,0.1

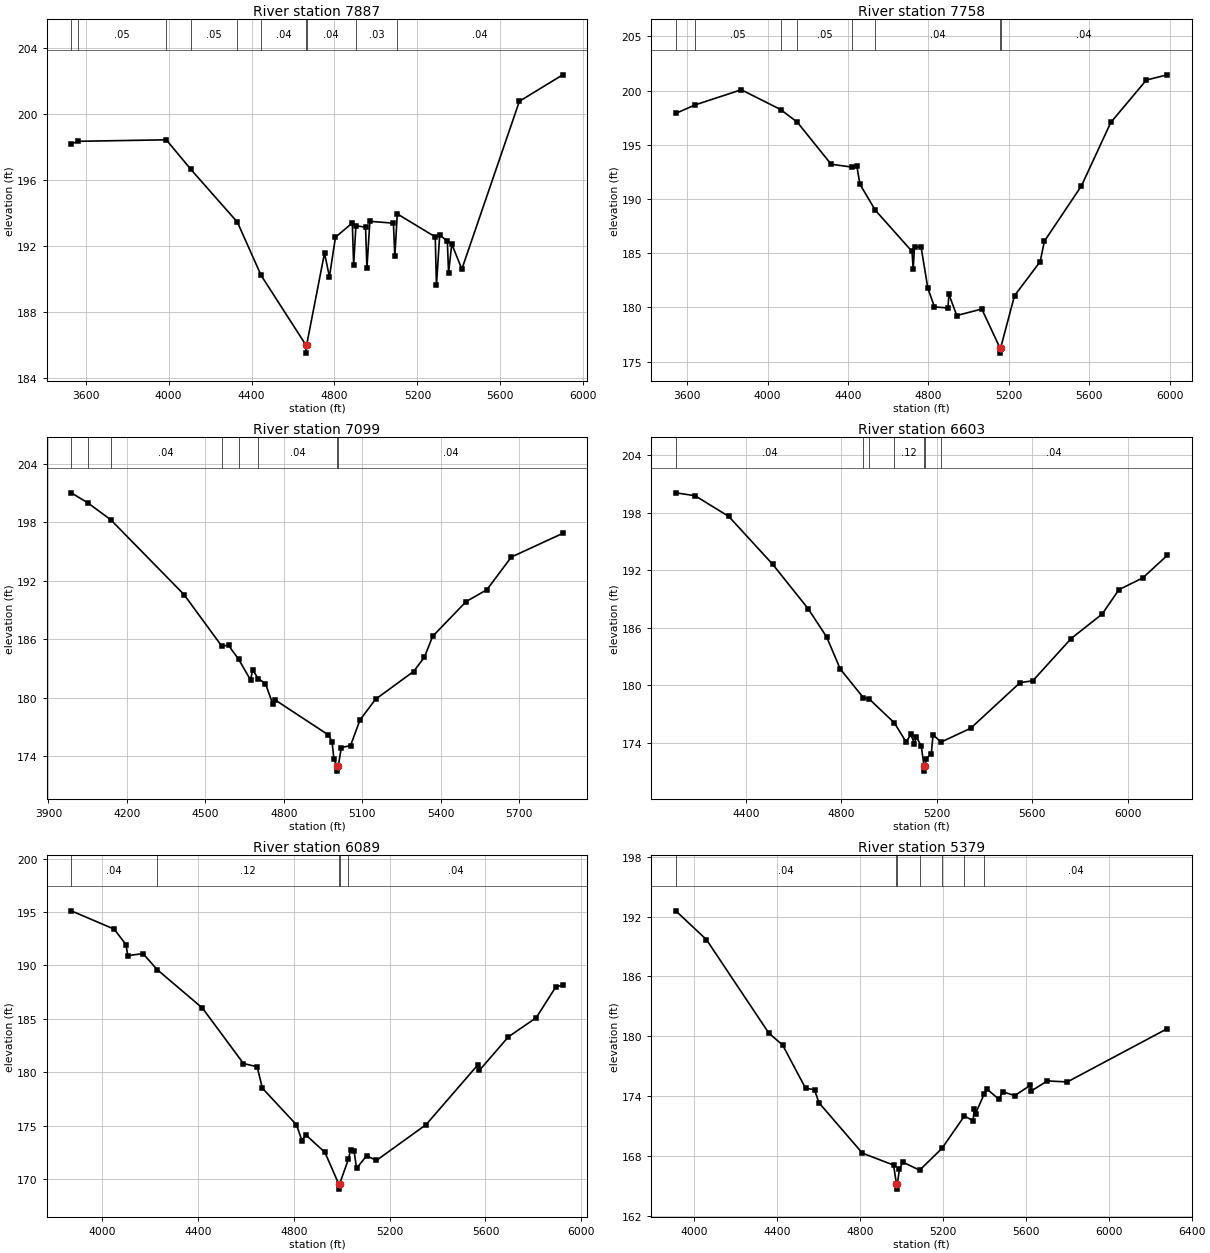
Type RM Length L Ch R = 1,7887,129,129,129
BEGIN DESCRIPTION:
Mapping XS 35a5d13b
END DESCRIPTION:
XS GIS Cut Line= 6
      2530707.38     13582966.02      2529702.17     13582330.60
      2529660.51     13582231.65      2529551.13     13582096.23
      2529374.05     13581934.77      2528776.62     13581659.37
#Sta/Elev= 30
  3530.5  198.17  3564.2  198.33  3988.9  198.42  4107.5  196.63  4331.9  193.44
  4446.3  190.22  4661.8  186.02  4662.1  185.52  4666.0  186.02  4752.0  191.57
  4775.7  190.14  4804.9  192.53  4886.1  193.39  4892.5  190.84  4903.5  193.22
  4950.0  193.14  4956.5  190.66  4970.9  193.49  5084.3  193.38  5091.2  191.37
  5103.0  193.94  5286.1  192.55  5291.9  189.61  5307.6  192.67  5344.5  192.29
  5350.3  190.37  5365.9  192.12  5414.4  190.60  5691.9  200.75  5900.8  202.35
#Mann=10,-1,0
  3530.5    0.04       0  3564.2    0.05       0  3988.9    0.04       0
  4107.5    0.05       0  4331.9   0.013       0  4446.3    0.04       0
  4661.8    0.03       0  4666.0    0.04       0  4903.5    0.03       0
  5103.0    0.04       0
Bank Sta=4661.8,4666
Exp/Cntr=0.3,0.1

Type RM Length L Ch R = 1,7758,659,659,659
BEGIN DESCRIPTION:
Mapping XS d0fef641
END DESCRIPTION:
XS GIS Cut Line= 5
      2530749.04     13582945.18      2529780.30     13582268.10
      2529629.26     13581976.44      2529254.26     13581622.27
      2528842.76     13581554.56
#Sta/Elev= 30
  3543.9  197.90  3639.2  198.68  3869.6  200.08  4064.9  198.26  4148.0  197.09
  4316.2  193.21  4418.0  192.95  4444.4  193.01  4459.2  191.37  4535.7  188.97
  4718.2  185.17  4724.2  183.56  4730.7  185.55  4763.1  185.61  4797.1  181.76
  4830.1  180.04  4896.5  179.95  4902.1  181.19  4940.8  179.25  5065.3  179.85
  5155.0  176.28  5155.3  175.78  5159.2  176.28  5227.9  181.08  5355.4  184.22
  5376.5  186.11  5560.5  191.21  5706.7  197.07  5883.5  200.98  5987.1  201.46
#Mann=8,-1,0
  3543.9    0.04       0  3639.2    0.05       0  4064.9    0.04       0
  4148.0    0.05       0  4418.0   0.013       0  4535.7    0.04       0
  5155.0    0.04       0  5159.2    0.04       0
Bank Sta=5155,5159.2
Exp/Cntr=0.3,0.1

Type RM Length L Ch R = 1,7099,496,496,496
BEGIN DESCRIPTION:
Mapping XS a5a1bfba
END DESCRIPTION:
XS GIS Cut Line= 3
      2530577.18     13582252.49      2529775.09     13581512.90
      2529015.79     13581299.67
#Sta/Elev= 30
  3987.3  201.01  4050.2  199.99  4138.3  198.25  4418.8  190.57  4562.5  185.30
  4588.8  185.36  4627.7  183.93  4673.4  181.80  4680.7  182.86  4702.3  181.96
  4730.1  181.44  4758.4  179.32  4765.6  179.79  4970.5  176.18  4984.7  175.49
  4992.1  173.69  5004.1  172.96  5004.4  172.46  5008.4  172.96  5020.4  174.88
  5055.6  175.08  5091.5  177.70  5151.1  179.83  5296.6  182.68  5338.1  184.14
  5369.3  186.28  5497.5  189.85  5577.0  191.07  5670.5  194.42  5867.0  196.85
#Mann=8,-1,0
  3987.3    0.04       0  4050.2    0.05       0  4138.3    0.04       0
  4562.5    0.05       0  4627.7   0.013       0  4702.3    0.04       0
  5004.1    0.04       0  5008.4    0.04       0
Bank Sta=5004.1,5008.4
Exp/Cntr=0.3,0.1

Type RM Length L Ch R = 1,6603,514,514,514
BEGIN DESCRIPTION:
Mapping XS 92f20995
END DESCRIPTION:
XS GIS Cut Line= 3
      2530821.99     13581992.09      2530056.34     13581210.81
      2529092.84     13581153.52
#Sta/Elev= 30
  4106.9  200.09  4187.5  199.79  4328.9  197.63  4512.8  192.64  4661.4  188.01
  4739.1  185.06  4795.7  181.73  4893.0  178.72  4916.9  178.60  5022.7  176.10
  5071.5  174.13  5092.7  174.89  5106.9  173.87  5113.9  174.67  5135.2  173.71
  5147.2  171.57  5147.5  171.07  5151.5  171.57  5156.3  172.38  5177.6  172.87
  5184.6  174.86  5218.5  174.10  5342.4  175.54  5549.6  180.30  5602.8  180.49
  5763.1  184.89  5893.4  187.45  5963.5  189.99  6063.7  191.22  6166.0  193.57
#Mann=7,-1,0
  4106.9    0.04       0  4893.0    0.12       0  4916.9   0.013       0
  5022.7    0.12       0  5147.2    0.03       0  5151.5    0.12       0
  5218.5    0.04       0
Bank Sta=5147.2,5151.5
Exp/Cntr=0.3,0.1

Type RM Length L Ch R = 1,6089,710,710,710
BEGIN DESCRIPTION:
Mapping XS ab63c684
END DESCRIPTION:
XS GIS Cut Line= 4
      2531004.27     13581538.95      2530530.30     13581012.90
      2529910.51     13580841.02      2529233.44     13581018.10
#Sta/Elev= 30
  3871.3  195.11  4050.9  193.39  4100.2  191.93  4107.0  190.92  4171.2  191.10
  4229.7  189.61  4418.6  186.01  4590.1  180.81  4647.1  180.51  4669.1  178.50
  4811.4  175.07  4833.9  173.60  4850.8  174.12  4929.8  172.50  4987.4  169.55
  4987.7  169.05  4991.7  169.55  5028.3  171.87  5037.8  172.76  5051.9  172.58
  5062.2  170.99  5103.7  172.17  5145.3  171.74  5352.3  175.09  5569.2  180.71
  5574.4  180.16  5695.7  183.31  5811.8  185.10  5892.7  187.95  5922.4  188.18
#Mann=5,-1,0
  3871.3    0.04       0  4229.7    0.12       0  4987.4    0.05       0
  4991.7    0.12       0  5028.3    0.04       0
Bank Sta=4987.4,4991.7
Exp/Cntr=0.3,0.1

Type RM Length L Ch R = 1,5379,413,413,413
BEGIN DESCRIPTION:
Mapping XS c08f8728
END DESCRIPTION:
XS GIS Cut Line= 4
      2531150.67     13581172.62      2530789.56     13580540.67
      2530115.95     13580214.28      2529318.67     13580616.39
#Sta/Elev= 30
  3912.9  192.57  4060.5  189.69  4361.4  180.31  4428.4  179.10  4538.5  174.78
  4581.7  174.63  4603.3  173.32  4812.5  168.27  4962.9  167.07  4976.9  165.16
  4977.3  164.66  4981.4  165.16  4991.1  166.69  5008.1  167.36  5088.5  166.56
  5196.3  168.75  5304.2  171.99  5345.9  171.53  5352.3  172.69  5357.9  172.23
  5400.4  174.23  5412.7  174.71  5471.4  173.65  5488.1  174.43  5547.1  174.04
  5622.0  175.07  5627.6  174.51  5703.9  175.51  5800.4  175.41  6282.2  180.75
#Mann=7,-1,0
  3912.9    0.04       0  4976.9    0.04       0  4981.4    0.04       0
  5088.5    0.12       0  5196.3    0.04       0  5304.2   0.013       0
  5400.4    0.04       0
Bank Sta=4976.9,4981.4
Exp/Cntr=0.3,0.1

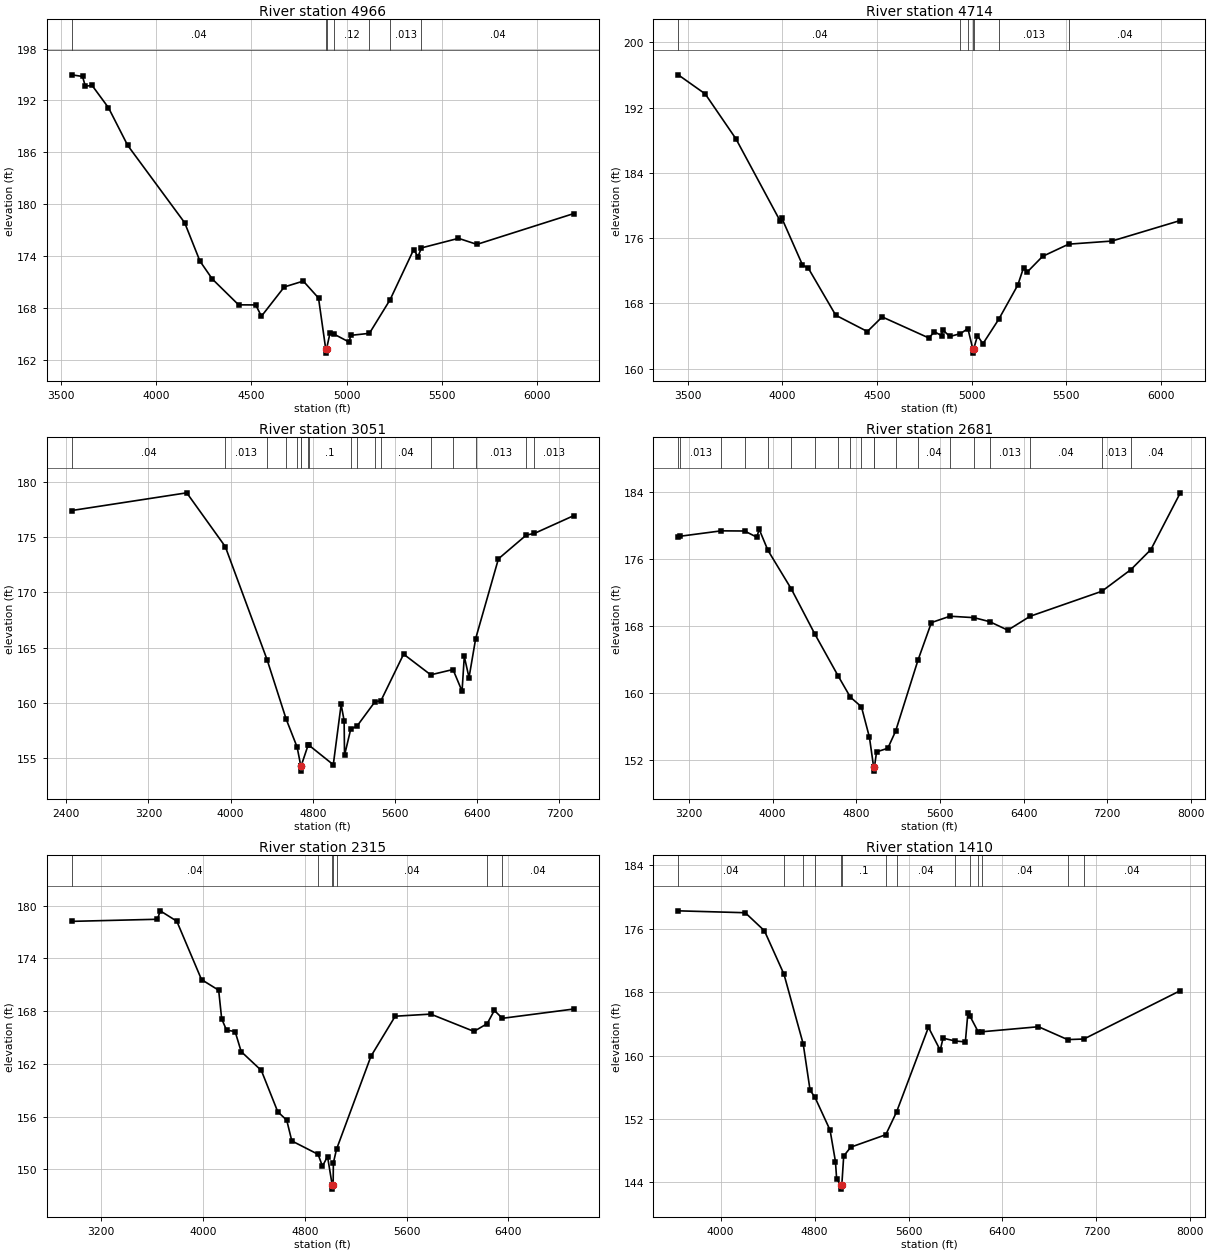
Type RM Length L Ch R = 1,4966,252,252,252
BEGIN DESCRIPTION:
Mapping XS e7f2b3ba
END DESCRIPTION:
XS GIS Cut Line= 4
      2531727.04     13580492.05      2531095.11     13580040.67
      2530150.67     13580026.78      2529352.03     13580478.19
#Sta/Elev= 30
  3555.7  194.96  3612.2  194.77  3626.9  193.65  3662.6  193.73  3748.6  191.15
  3849.3  186.80  4149.2  177.83  4229.1  173.40  4294.2  171.32  4432.4  168.33
  4522.4  168.32  4552.4  167.01  4672.4  170.40  4772.4  171.08  4852.4  169.12
  4890.1  163.24  4890.4  162.74  4894.7  163.24  4912.4  165.02  4933.7  164.94
  5012.5  164.03  5022.5  164.80  5119.8  165.03  5228.7  168.93  5352.3  174.72
  5375.2  173.92  5393.1  174.92  5588.0  176.03  5684.7  175.33  6194.2  178.90
#Mann=7,-1,0
  3555.7    0.04       0  4890.1    0.05       0  4894.7    0.04       0
  4933.7    0.12       0  5119.8    0.04       0  5228.7   0.013       0
  5393.1    0.04       0
Bank Sta=4890.1,4894.7
Exp/Cntr=0.3,0.1

Type RM Length L Ch R = 1,4714,1663,1663,1663
BEGIN DESCRIPTION:
Mapping XS a1bfbffa
END DESCRIPTION:
XS GIS Cut Line= 5
      2531766.43     13580338.35      2531080.69     13579956.42
      2530557.31     13579796.64      2530039.95     13579911.23
      2529389.01     13580363.69
#Sta/Elev= 30
  3449.1  196.02  3591.7  193.68  3754.0  188.18  3988.7  178.07  3997.5  178.41
  4106.1  172.71  4137.5  172.29  4281.8  166.55  4449.1  164.55  4527.5  166.34
  4774.1  163.76  4804.1  164.52  4841.5  164.04  4846.6  164.78  4885.1  163.94
  4941.3  164.29  4980.7  164.91  5006.7  162.40  5007.0  161.90  5011.3  162.40
  5031.3  164.04  5060.2  163.05  5144.1  166.06  5244.5  170.24  5275.3  172.39
  5295.7  171.87  5375.5  173.76  5513.4  175.26  5742.2  175.64  6103.9  178.16
#Mann=7,-1,0
  3449.1    0.04       0  4941.3    0.05       0  4980.7    0.04       0
  5006.7    0.04       0  5011.3    0.04       0  5144.1   0.013       0
  5513.4    0.04       0
Bank Sta=5006.7,5011.3
Exp/Cntr=0.3,0.1

Type RM Length L Ch R = 1,3051,370,370,370
BEGIN DESCRIPTION:
Mapping XS 7c038dd5
END DESCRIPTION:
XS GIS Cut Line= 4
      2533817.38     13578200.38      2531372.89     13579242.06
      2530268.50     13579718.56      2529374.02     13580222.18
#Sta/Elev= 30
  2454.2  177.39  3573.3  178.99  3948.6  174.12  4355.8  163.88  4540.2  158.54
  4647.5  155.99  4682.5  154.32  4682.9  153.82  4687.8  154.32  4755.7  156.21
  4763.0  156.16  4999.5  154.40  5075.8  159.85  5104.9  158.38  5108.8  155.25
  5169.5  157.63  5229.4  157.88  5405.5  160.10  5462.9  160.18  5683.8  164.40
  5947.7  162.53  6164.6  163.01  6252.7  161.05  6274.4  164.19  6320.5  162.28
  6385.3  165.81  6606.7  173.02  6877.9  175.17  6956.9  175.32  7340.7  176.93
#Mann=18,-1,0
  2454.2    0.04       0  3948.6   0.013       0  4355.8     0.1       0
  4540.2    0.12       0  4647.5     0.1       0  4682.5    0.05       0
  4687.8     0.1       0  4755.7   0.013       0  4763.0     0.1       0
  5169.5   0.013       0  5229.4    0.04       0  5405.5   0.013       0
  5462.9    0.04       0  5947.7    0.05       0  6164.6    0.04       0
  6385.3   0.013       0  6877.9    0.04       0  6956.9   0.013       0
Bank Sta=4682.5,4687.8
Exp/Cntr=0.3,0.1

Type RM Length L Ch R = 1,2681,366,366,366
BEGIN DESCRIPTION:
Mapping XS cbdd457b
END DESCRIPTION:
XS GIS Cut Line= 3
      2533108.98     13578075.41      2531435.39     13578839.28
      2528685.36     13579943.46
#Sta/Elev= 30
  3096.8  178.71  3112.9  178.75  3508.0  179.40  3731.6  179.38  3848.7  178.64
  3870.6  179.60  3955.1  177.06  4178.7  172.44  4402.2  167.08  4625.8  162.05
  4743.0  159.50  4849.4  158.34  4925.9  154.69  4966.0  151.14  4966.5  150.64
  4973.8  151.14  4994.1  152.94  5101.7  153.38  5175.9  155.41  5390.3  163.92
  5518.8  168.42  5696.2  169.18  5926.3  169.01  6076.0  168.53  6249.8  167.51
  6462.2  169.17  7149.8  172.17  7427.0  174.76  7618.5  177.16  7899.9  183.95
#Mann=20,-1,0
  3096.8    0.05       0  3112.9   0.013       0  3508.0   0.013       0
  3731.6   0.013       0  3955.1   0.013       0  4178.7   0.013       0
  4402.2   0.013       0  4625.8   0.013       0  4743.0    0.04       0
  4849.4   0.013       0  4966.0    0.05       0  4973.8     0.1       0
  5175.9    0.04       0  5390.3    0.04       0  5696.2   0.013       0
  5926.3    0.05       0  6076.0   0.013       0  6462.2    0.04       0
  7149.8   0.013       0  7427.0    0.04       0
Bank Sta=4966,4973.8
Exp/Cntr=0.3,0.1

Type RM Length L Ch R = 1,2315,905,905,905
BEGIN DESCRIPTION:
Mapping XS c44ef5d2
END DESCRIPTION:
XS GIS Cut Line= 4
      2533185.43     13577901.77      2531803.45     13578485.12
      2530602.06     13578582.34      2529560.36     13579255.97
#Sta/Elev= 30
  2969.3  178.22  3642.7  178.46  3664.5  179.42  3794.7  178.24  3989.0  171.59
  4123.8  170.38  4147.5  167.12  4185.5  165.84  4253.2  165.67  4300.7  163.39
  4459.2  161.24  4588.2  156.54  4658.7  155.58  4698.6  153.22  4905.3  151.69
  4939.3  150.34  4979.5  151.44  5015.6  148.23  5016.1  147.73  5023.5  148.23
  5025.2  150.72  5050.3  152.28  5320.6  162.86  5511.2  167.42  5790.3  167.66
  6130.2  165.69  6233.9  166.57  6290.4  168.08  6353.2  167.18  6915.2  168.24
#Mann=7,-1,0
  2969.3    0.04       0  4905.3     0.1       0  5015.6    0.05       0
  5023.5     0.1       0  5050.3    0.04       0  6233.9   0.013       0
  6353.2    0.04       0
Bank Sta=5015.6,5023.5
Exp/Cntr=0.3,0.1

Type RM Length L Ch R = 1,1410,891,891,891
BEGIN DESCRIPTION:
LGII4463
END DESCRIPTION:
XS GIS Cut Line= 4
      2533178.74     13577738.70      2531974.94     13577924.58
      2530841.94     13577853.76      2529444.79     13579171.33
#Sta/Elev= 30
  3639.9  178.24  4210.3  178.00  4373.3  175.73  4539.9  170.25  4703.8  161.45
  4762.1  155.63  4803.8  154.73  4932.2  150.60  4978.1  146.64  4988.2  144.45
  5024.2  143.66  5024.7  143.16  5032.2  143.66  5048.3  147.33  5108.4  148.45
  5406.5  150.02  5498.1  152.88  5769.7  163.56  5869.9  160.67  5894.1  162.19
  5997.4  161.83  6084.0  161.72  6105.0  165.32  6120.7  165.04  6194.2  162.96
  6228.2  163.00  6706.2  163.63  6953.9  162.01  7092.8  162.08  7913.6  168.18
#Mann=14,-1,0
  3639.9    0.04       0  4539.9    0.12       0  4703.8    0.05       0
  4803.8     0.1       0  5024.2    0.05       0  5032.2     0.1       0
  5406.5    0.05       0  5498.1    0.04       0  5997.4    0.05       0
  6120.7    0.12       0  6194.2    0.05       0  6228.2    0.04       0
  6953.9   0.013       0  7092.8    0.04       0
Bank Sta=5024.2,5032.2
Exp/Cntr=0.3,0.1