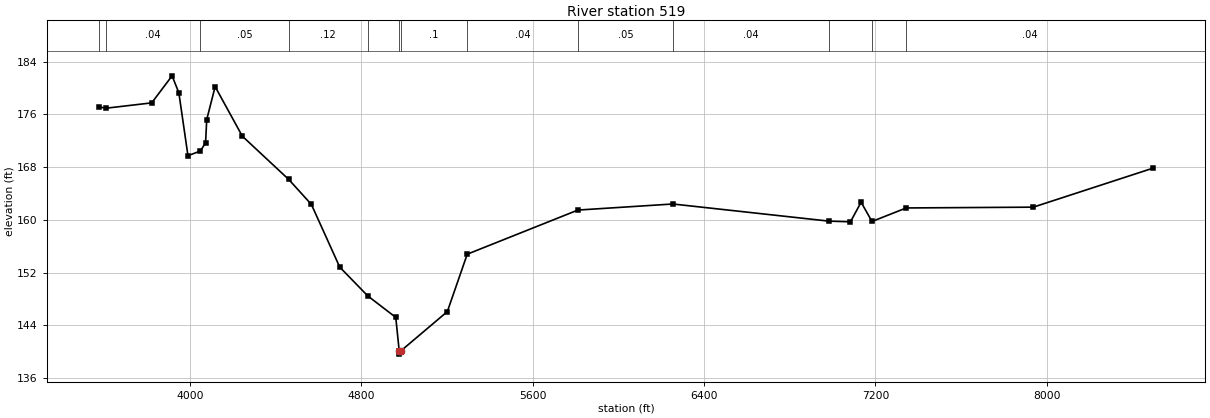
HEC-RAS study TRIB 1 TO OAXLEY BRANCH.prj: TRIB 1 TO OAXLEY BRANCH Base Level Engineering

--- TRIB 1 TO OAXLEY BRANCH.g01 (geometry) --- (continued)

Type RM Length L Ch R = 1,519,0,0,0
BEGIN DESCRIPTION:
LGII4464
END DESCRIPTION:
XS GIS Cut Line= 4
      2533276.14     13577552.82      2532019.20     13577119.09
      2530850.79     13577216.45      2529328.32     13579092.99
#Sta/Elev= 30
  3576.6  177.12  3607.6  176.92  3821.1  177.73  3916.3  181.83  3947.9  179.26
  3990.4  169.72  4048.7  170.44  4072.7  171.69  4078.0  175.19  4117.3  180.19
  4244.3  172.68  4460.9  166.12  4566.6  162.34  4699.1  152.83  4829.8  148.47
  4960.7  145.21  4976.7  140.14  4977.2  139.64  4984.8  140.14  5201.5  146.09
  5294.4  154.79  5811.1  161.48  6254.4  162.40  6983.5  159.80  7083.8  159.70
  7133.4  162.67  7184.3  159.75  7344.3  161.80  7937.3  161.92  8495.2  167.82
#Mann=13,-1,0
  3576.6    0.12       0  3607.6    0.04       0  4048.7    0.05       0
  4460.9    0.12       0  4829.8     0.1       0  4976.7    0.05       0
  4984.8     0.1       0  5294.4    0.04       0  5811.1    0.05       0
  6254.4    0.04       0  6983.5    0.05       0  7184.3   0.013       0
  7344.3    0.04       0
Bank Sta=4976.7,4984.8
Exp/Cntr=0.3,0.1

Chan Stop Cuts=-1