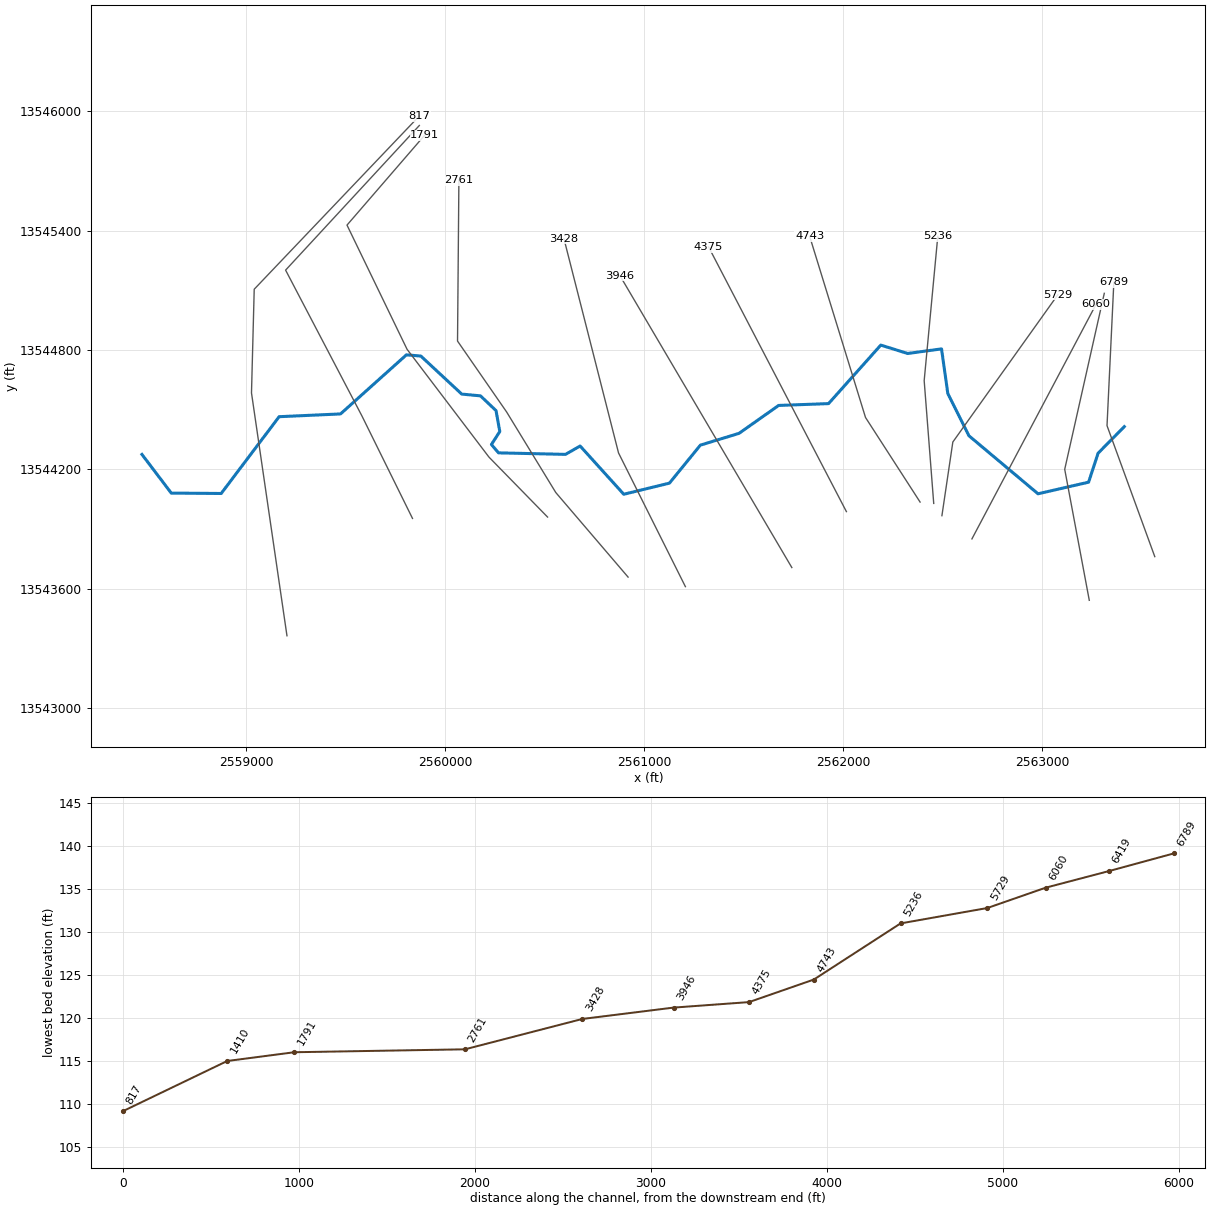
--- TRIB 1 TO PRICE CREEK.prj (project) ---

Proj Title=TRIB 1 TO PRICE CREEK Base Level Engineering
Current Plan=p01
Default Exp/Contr=0.3,0.1
English Units
Geom File=g01
Flow File=f01
Plan File=p01
BEGIN DESCRIPTION:
TRIB 1 TO PRICE CREEK
END DESCRIPTION:

--- TRIB 1 TO PRICE CREEK.p01 (plan) ---

Plan Title=Multiple Run
Short Identifier=Multiple
Geom File=g01
Flow File=f01
Subcritical Flow
K Sum by GR= 0
Std Step Tol= 0.01
Critical Tol= 0.01
Num of Std Step Trials= 20
Max Error Tol= 0.3
Flow Tol Ratio= 0.001
Split Flow NTrial= 30
Split Flow Tol= 0.02
Split Flow Ratio= 0.02
Log Output Level= 0
Friction Slope Method= 1
Unsteady Friction Slope Method= 2
Unsteady Bridges Friction Slope Method= 1
Parabolic Critical Depth
Global Vel Dist=  1 , 1 , 1
Global Log Level= 0
CheckData=True
Encroach Param= -1, 0, 0, 0
BEGIN DESCRIPTION:
Multiple Run
END DESCRIPTION:

--- TRIB 1 TO PRICE CREEK.f01 (steady flow) ---

Flow Title=Multiple
Number of Profiles=7
Profile Names=10-year,25-year,50-year,1pct_min,100-year,1pct_plu,500-year
River Rch & RM= TRIB 1 TO PRICE ,Reach-1,6789
     936    1517    2045    1333    2661    5309    4450
River Rch & RM= TRIB 1 TO PRICE ,Reach-1,817
    1345    2229    3049    2014    4019    8020    6909
Boundary for River Rch & Prof#=TRIB 1 TO PRICE ,Reach-1,1
Up Type=0
Dn Type=3
Dn Slope=0.005
Boundary for River Rch & Prof#=TRIB 1 TO PRICE ,Reach-1,2
Up Type=0
Dn Type=3
Dn Slope=0.005
Boundary for River Rch & Prof#=TRIB 1 TO PRICE ,Reach-1,3
Up Type=0
Dn Type=3
Dn Slope=0.005
Boundary for River Rch & Prof#=TRIB 1 TO PRICE ,Reach-1,4
Up Type=0
Dn Type=3
Dn Slope=0.005
Boundary for River Rch & Prof#=TRIB 1 TO PRICE ,Reach-1,5
Up Type=0
Dn Type=3
Dn Slope=0.005
Boundary for River Rch & Prof#=TRIB 1 TO PRICE ,Reach-1,6
Up Type=0
Dn Type=3
Dn Slope=0.005
Boundary for River Rch & Prof#=TRIB 1 TO PRICE ,Reach-1,7
Up Type=0
Dn Type=3
Dn Slope=0.005

--- TRIB 1 TO PRICE CREEK.g01 (geometry) ---

Geom Title=Existing Conditions

River Reach=TRIB 1 TO PRICE ,Reach-1
Reach XY= 30
      2563414.55     13544414.55      2563282.85     13544281.17
      2563235.16     13544135.36      2562980.89     13544076.97
      2562633.14     13544368.94      2562527.24     13544580.93
      2562495.65     13544805.62      2562325.00     13544782.57
      2562190.21     13544824.75      2561927.45     13544530.46
      2561676.55     13544521.25      2561477.29     13544380.84
      2561283.05     13544321.68      2561127.43     13544130.52
      2560897.75     13544074.63      2560678.42     13544317.21
      2560605.02     13544275.19      2560268.16     13544282.80
      2560232.22     13544324.65      2560274.48     13544390.21
      2560255.44     13544495.20      2560177.38     13544569.46
      2560083.06     13544578.35      2559877.42     13544769.59
      2559804.92     13544775.68      2559473.54     13544478.54
      2559164.88     13544464.66      2558873.55     13544078.53
      2558622.53     13544080.45      2558475.00     13544275.00

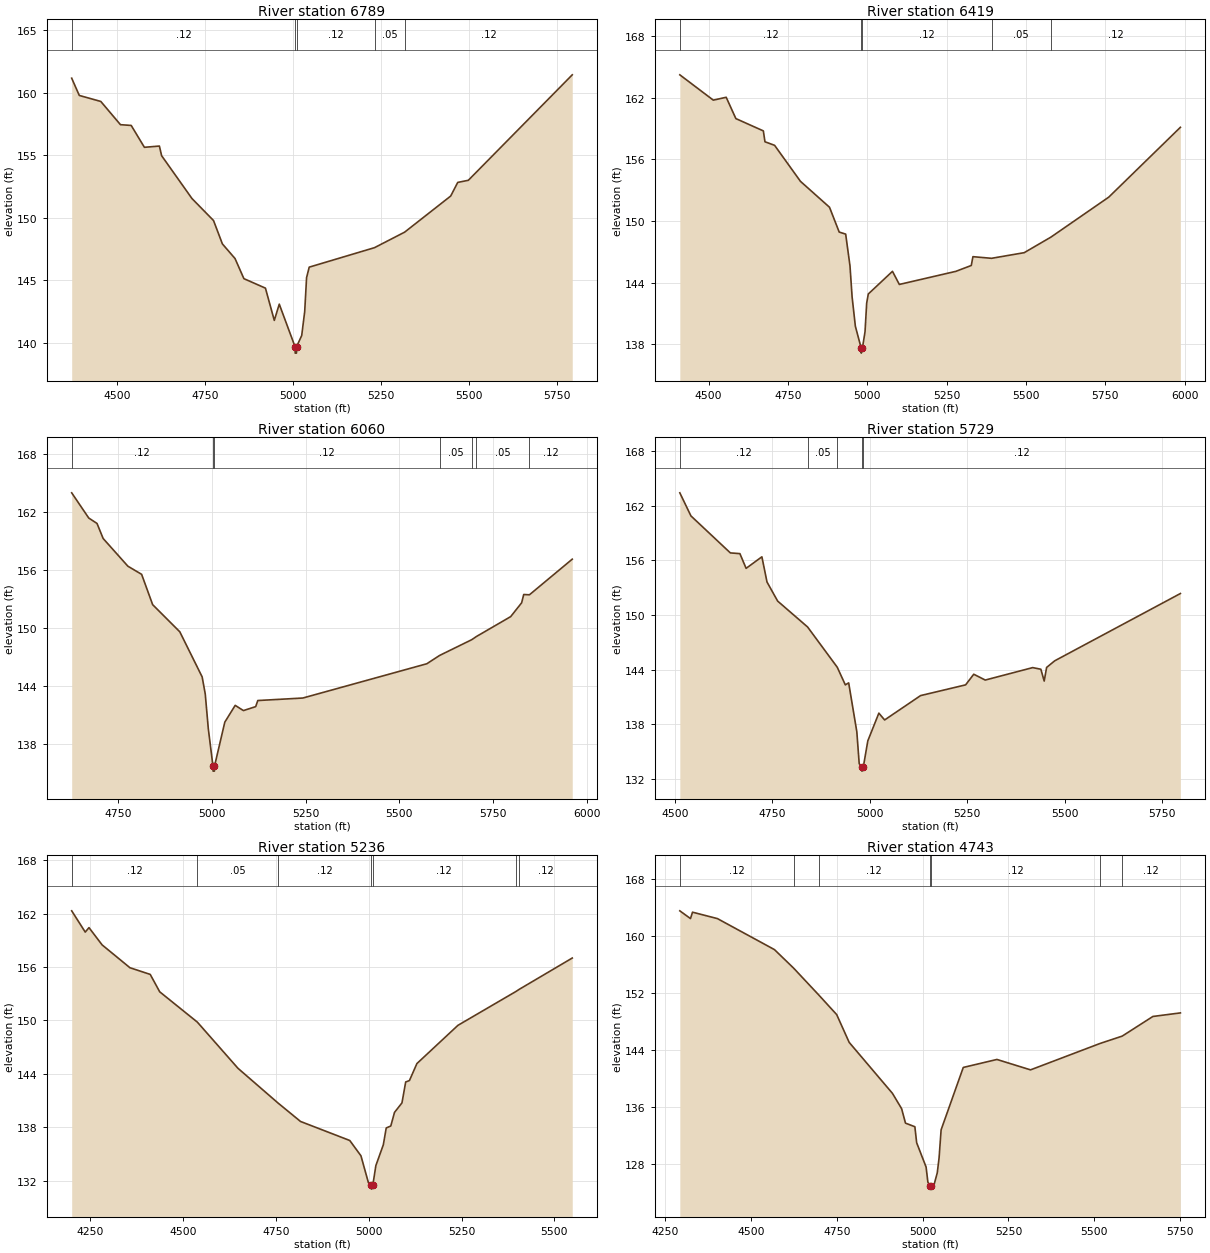
Type RM Length L Ch R = 1,6789,370,370,370
BEGIN DESCRIPTION:
LGII3021
END DESCRIPTION:
XS GIS Cut Line= 3
      2563567.85     13543760.92      2563327.71     13544419.60
      2563362.01     13545139.99
#Sta/Elev= 30
  4370.5  161.17  4392.1  159.79  4453.2  159.31  4509.1  157.45  4539.6  157.39
  4577.1  155.64  4619.7  155.74  4626.0  154.97  4712.3  151.54  4773.5  149.78
  4798.7  147.91  4834.6  146.74  4859.8  145.13  4921.0  144.37  4946.2  141.79
  4960.3  143.09  5005.3  139.67  5005.6  139.17  5009.1  139.17  5009.3  139.67
  5024.1  140.58  5032.6  142.51  5037.9  145.21  5045.4  146.05  5231.0  147.61
  5316.5  148.85  5447.4  151.74  5467.4  152.83  5497.5  153.00  5792.8  161.44
#Mann=5,-1,0
  4370.5    0.12       0  5005.3    0.05       0  5009.3    0.12       0
  5231.0    0.05       0  5316.5    0.12       0
Bank Sta=5005.3,5009.3
Exp/Cntr=0.3,0.1

Type RM Length L Ch R = 1,6419,359,359,359
BEGIN DESCRIPTION:
LGII3020
END DESCRIPTION:
XS GIS Cut Line= 3
      2563238.52     13543541.39      2563115.02     13544200.05
      2563313.99     13545085.13
#Sta/Elev= 30
  4409.1  164.26  4514.6  161.79  4555.2  162.07  4585.7  159.99  4672.3  158.79
  4677.4  157.73  4707.8  157.38  4789.2  153.87  4880.8  151.34  4911.3  148.92
  4931.7  148.72  4945.3  145.62  4952.0  142.58  4962.2  139.74  4980.5  137.61
  4980.8  137.11  4984.5  137.61  4992.7  139.20  4997.9  141.99  5003.0  142.88
  5079.2  145.09  5100.8  143.81  5279.1  145.09  5327.5  145.66  5332.7  146.52
  5391.3  146.36  5494.3  146.91  5578.6  148.43  5760.8  152.33  5986.4  159.14
#Mann=5,-1,0
  4409.1    0.12       0  4980.5    0.05       0  4984.5    0.12       0
  5391.3    0.05       0  5578.6    0.12       0
Bank Sta=4980.5,4984.5
Exp/Cntr=0.3,0.1

Type RM Length L Ch R = 1,6060,331,331,331
BEGIN DESCRIPTION:
LGII3019
END DESCRIPTION:
XS GIS Cut Line= 2
      2562648.49     13543850.17      2563272.76     13545030.10
#Sta/Elev= 30
  4626.2  164.00  4671.7  161.39  4693.7  160.83  4710.1  159.27  4776.1  156.40
  4812.7  155.56  4842.1  152.42  4914.5  149.61  4974.1  144.94  4982.4  143.16
  4990.5  139.58  5003.0  135.68  5003.3  135.18  5006.8  135.18  5007.0  135.68
  5034.5  140.25  5062.2  141.99  5084.2  141.45  5116.9  141.86  5122.5  142.49
  5242.6  142.75  5573.3  146.30  5607.4  147.16  5693.0  148.79  5705.1  149.11
  5796.9  151.18  5826.1  152.61  5831.7  153.47  5846.9  153.44  5961.1  157.13
#Mann=7,-1,0
  4626.2    0.12       0  5003.0    0.05       0  5007.0    0.12       0
  5607.4    0.05       0  5693.0    0.12       0  5705.1    0.05       0
  5846.9    0.12       0
Bank Sta=5003,5007
Exp/Cntr=0.3,0.1

Type RM Length L Ch R = 1,5729,493,493,493
BEGIN DESCRIPTION:
LGII3018
END DESCRIPTION:
XS GIS Cut Line= 3
      2562497.54     13543966.82      2562552.42     13544337.27
      2563080.35     13545077.74
#Sta/Elev= 30
  4512.9  163.44  4541.4  160.90  4642.5  156.83  4667.0  156.75  4682.9  155.13
  4723.4  156.40  4736.5  153.63  4763.8  151.53  4840.6  148.68  4916.7  144.25
  4937.4  142.31  4946.0  142.53  4966.9  137.15  4973.0  133.64  4979.7  133.32
  4979.9  132.82  4983.7  133.32  4995.1  136.15  5023.4  139.20  5038.2  138.45
  5130.4  141.13  5245.9  142.31  5266.8  143.48  5296.3  142.84  5418.0  144.21
  5438.9  144.03  5447.5  142.73  5453.7  144.23  5474.6  144.96  5796.8  152.36
#Mann=5,-1,0
  4512.9    0.12       0  4840.6    0.05       0  4916.7    0.12       0
  4979.7    0.05       0  4983.7    0.12       0
Bank Sta=4979.7,4983.7
Exp/Cntr=0.3,0.1

Type RM Length L Ch R = 1,5236,493,493,493
BEGIN DESCRIPTION:
LGII3017
END DESCRIPTION:
XS GIS Cut Line= 3
      2562456.36     13544028.57      2562408.34     13544646.01
      2562476.79     13545371.59
#Sta/Elev= 30
  4200.1  162.33  4236.6  159.94  4246.7  160.44  4282.0  158.50  4357.0  155.93
  4411.6  155.18  4437.2  153.22  4538.6  149.81  4647.9  144.62  4756.2  140.70
  4816.4  138.64  4949.0  136.50  4979.1  134.78  4999.2  131.76  5007.1  131.53
  5007.4  131.03  5011.3  131.53  5019.3  133.68  5039.4  136.02  5047.2  137.91
  5059.5  138.13  5069.5  139.66  5089.6  140.73  5099.6  143.08  5109.7  143.24
  5129.8  145.15  5240.3  149.45  5396.2  153.25  5405.4  153.50  5548.2  157.02
#Mann=7,-1,0
  4200.1    0.12       0  4538.6    0.05       0  4756.2    0.12       0
  5007.1    0.05       0  5011.3    0.12       0  5396.2    0.05       0
  5405.4    0.12       0
Bank Sta=5007.1,5011.3
Exp/Cntr=0.3,0.1

Type RM Length L Ch R = 1,4743,368,368,368
BEGIN DESCRIPTION:
LGII3016
END DESCRIPTION:
XS GIS Cut Line= 3
      2562387.78     13544035.35      2562113.32     13544460.77
      2561832.53     13545371.60
#Sta/Elev= 30
  4292.0  163.54  4323.1  162.45  4329.0  163.35  4401.6  162.45  4567.9  158.10
  4623.8  155.50  4696.6  151.76  4749.4  148.98  4785.7  145.09  4912.0  137.93
  4938.7  135.78  4949.9  133.76  4977.3  133.25  4982.5  131.01  5010.0  127.60
  5015.2  125.49  5020.4  125.00  5020.6  124.50  5024.6  125.00  5032.9  125.06
  5042.6  126.79  5047.9  128.90  5053.8  132.82  5118.4  141.57  5216.5  142.69
  5314.5  141.23  5517.0  144.93  5582.0  145.97  5671.2  148.72  5751.4  149.22
#Mann=7,-1,0
  4292.0    0.12       0  4623.8    0.05       0  4696.6    0.12       0
  5020.4    0.05       0  5024.6    0.12       0  5517.0    0.05       0
  5582.0    0.12       0
Bank Sta=5020.4,5024.6
Exp/Cntr=0.3,0.1

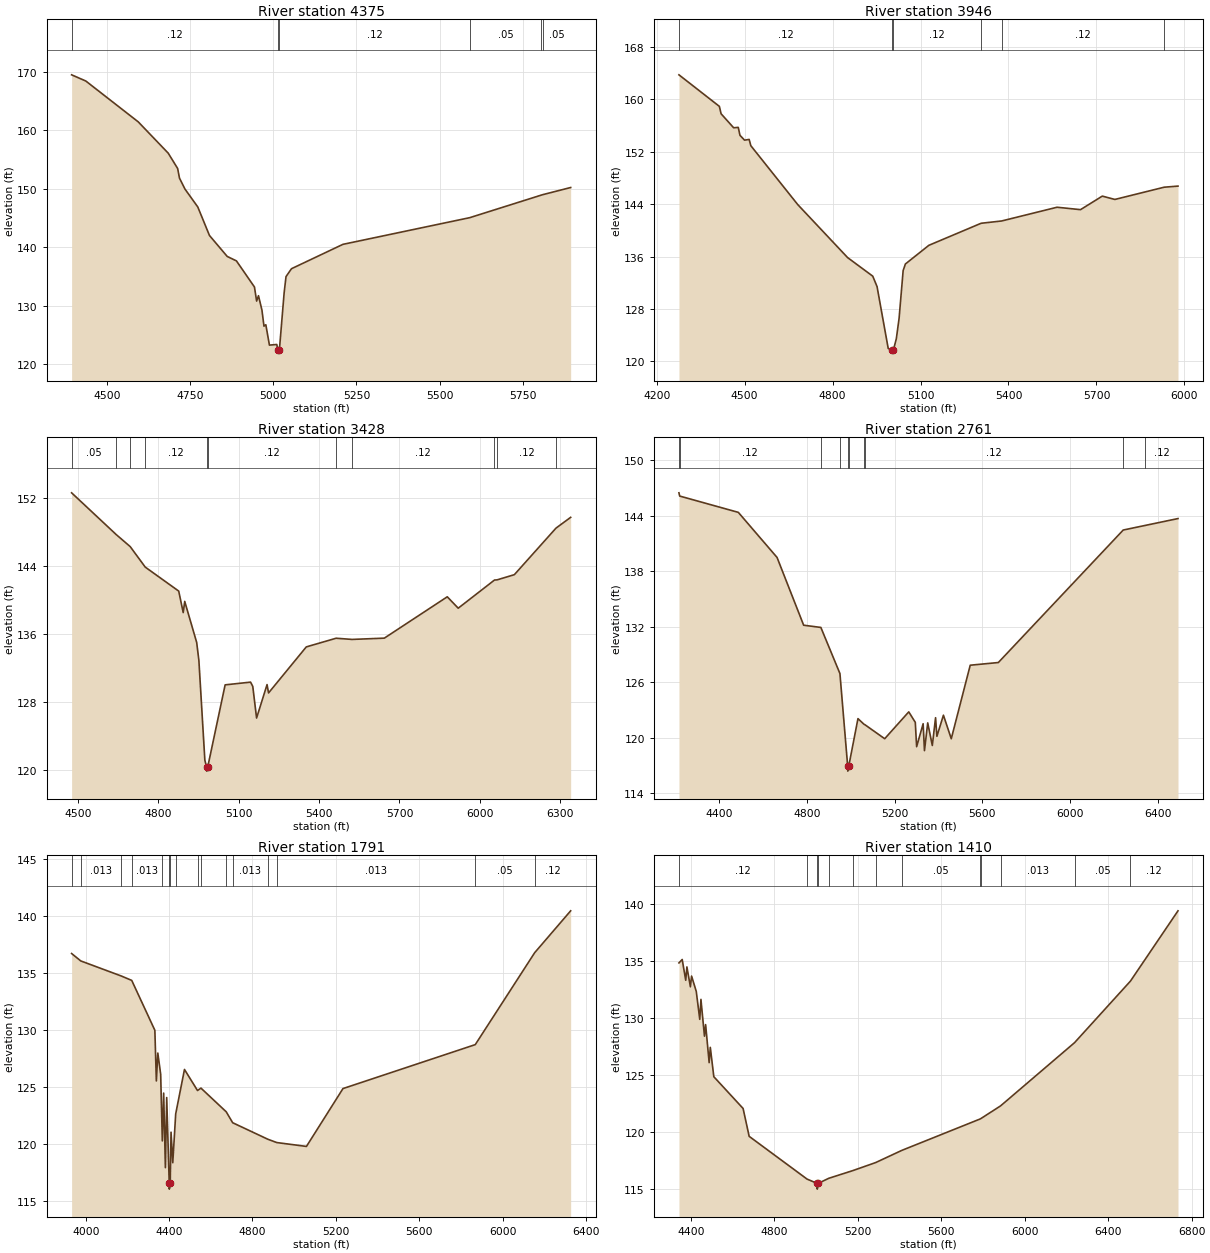
Type RM Length L Ch R = 1,4375,429,429,429
BEGIN DESCRIPTION:
LGII3015
END DESCRIPTION:
XS GIS Cut Line= 2
      2562017.27     13543987.35      2561324.31     13545318.37
#Sta/Elev= 30
  4393.5  169.52  4436.2  168.46  4593.8  161.47  4684.0  156.11  4712.3  153.49
  4717.9  151.83  4734.4  149.96  4772.9  146.90  4808.0  142.02  4861.4  138.43
  4889.1  137.67  4943.3  133.20  4949.8  130.79  4955.4  131.71  4965.8  129.25
  4971.9  126.50  4977.5  126.74  4988.3  123.25  5010.4  123.36  5013.9  122.38
  5014.2  121.88  5018.2  122.38  5032.5  132.19  5038.2  134.98  5054.6  136.33
  5209.3  140.50  5590.8  145.07  5806.3  148.94  5809.8  149.00  5894.1  150.23
#Mann=6,-1,0
  4393.5    0.12       0  5013.9    0.05       0  5018.2    0.12       0
  5590.8    0.05       0  5806.3    0.12       0  5809.8    0.05       0
Bank Sta=5013.9,5018.2
Exp/Cntr=0.3,0.1

Type RM Length L Ch R = 1,3946,518,518,518
BEGIN DESCRIPTION:
LGII3014
END DESCRIPTION:
XS GIS Cut Line= 2
      2561742.84     13543706.03      2560879.19     13545172.87
#Sta/Elev= 30
  4276.0  163.76  4413.9  158.94  4419.7  157.81  4462.6  155.67  4478.3  155.73
  4484.1  154.52  4499.7  153.78  4515.4  153.89  4521.2  152.93  4681.3  143.93
  4851.2  135.84  4937.0  133.00  4951.7  131.41  4989.8  121.95  5003.3  121.74
  5003.6  121.24  5007.6  121.74  5017.5  123.45  5026.9  126.57  5040.7  133.85
  5048.4  134.86  5128.4  137.71  5306.6  141.08  5376.6  141.43  5565.7  143.53
  5645.7  143.16  5720.0  145.23  5762.9  144.72  5931.0  146.59  5978.2  146.76
#Mann=6,-1,0
  4276.0    0.12       0  5003.3    0.05       0  5007.6    0.12       0
  5306.6    0.05       0  5376.6    0.12       0  5931.0    0.05       0
Bank Sta=5003.3,5007.6
Exp/Cntr=0.3,0.1

Type RM Length L Ch R = 1,3428,667,667,667
BEGIN DESCRIPTION:
LGII3013
END DESCRIPTION:
XS GIS Cut Line= 3
      2561207.68     13543609.99      2560871.48     13544282.38
      2560597.05     13545359.52
#Sta/Elev= 30
  4476.0  152.63  4642.3  147.73  4694.7  146.31  4750.9  143.90  4875.9  141.08
  4892.7  138.55  4898.3  139.87  4943.0  135.04  4951.2  132.92  4973.5  121.20
  4979.9  120.42  4980.2  119.92  4984.3  120.42  5049.2  130.06  5144.2  130.38
  5152.4  129.88  5166.6  126.16  5205.7  130.09  5211.3  129.11  5352.2  134.52
  5463.6  135.54  5522.9  135.40  5643.6  135.55  5878.6  140.41  5919.5  139.07
  6054.9  142.38  6064.7  142.40  6129.1  143.01  6284.5  148.48  6339.3  149.75
#Mann=11,-1,0
  4476.0    0.05       0  4642.3    0.12       0  4694.7    0.05       0
  4750.9    0.12       0  4979.9    0.05       0  4984.3    0.12       0
  5463.6    0.05       0  5522.9    0.12       0  6054.9    0.05       0
  6064.7    0.12       0  6284.5    0.05       0
Bank Sta=4979.9,4984.3
Exp/Cntr=0.3,0.1

Type RM Length L Ch R = 1,2761,970,970,970
BEGIN DESCRIPTION:
LGII3012
END DESCRIPTION:
XS GIS Cut Line= 5
      2560919.48     13543658.07      2560555.88     13544083.41
      2560308.88     13544488.21      2560061.89     13544844.98
      2560068.75     13545654.55
#Sta/Elev= 30
  4216.0  146.45  4219.4  146.10  4486.9  144.34  4663.7  139.47  4785.1  132.15
  4863.6  131.91  4950.6  126.93  4986.1  116.89  4986.4  116.39  4990.5  116.89
  5032.9  122.06  5061.5  121.43  5064.2  121.41  5154.9  119.89  5264.7  122.79
  5294.5  121.66  5300.6  119.03  5330.3  121.51  5336.4  118.60  5351.2  121.60
  5372.2  119.16  5387.0  122.16  5393.1  120.15  5422.9  122.43  5458.7  119.89
  5545.2  127.83  5673.5  128.12  6243.3  142.43  6341.9  142.92  6493.3  143.67
#Mann=10,-1,0
  4216.0    0.05       0  4219.4    0.12       0  4863.6    0.05       0
  4950.6    0.12       0  4986.1    0.05       0  4990.5    0.12       0
  5061.5    0.05       0  5064.2    0.12       0  6243.3   0.013       0
  6341.9    0.12       0
Bank Sta=4986.1,4990.5
Exp/Cntr=0.3,0.1

Type RM Length L Ch R = 1,1791,381,381,381
BEGIN DESCRIPTION:
LGII3011
END DESCRIPTION:
XS GIS Cut Line= 5
      2560514.70     13543959.92      2560219.69     13544261.80
      2559808.03     13544803.81      2559506.15     13545428.16
      2559896.81     13545880.51
#Sta/Elev= 30
  3932.4  136.74  3976.3  136.09  4171.6  134.76  4220.8  134.38  4331.7  130.00
  4338.9  125.55  4345.9  128.00  4359.6  126.14  4367.5  120.29  4373.9  124.48
  4382.2  117.94  4388.5  124.09  4400.7  116.55  4401.1  116.05  4405.3  116.55
  4409.3  121.05  4417.6  118.37  4431.7  122.66  4473.8  126.56  4536.3  124.71
  4552.9  124.92  4674.1  122.84  4705.0  121.88  4873.8  120.43  4916.5  120.14
  5058.9  119.80  5234.1  124.88  5868.7  128.74  6153.6  136.81  6326.3  140.49
#Mann=16,-1,0
  3932.4    0.12       0  3976.3   0.013       0  4171.6    0.12       0
  4220.8   0.013       0  4367.5    0.05       0  4400.7    0.03       0
  4405.3    0.05       0  4431.7   0.013       0  4536.3    0.05       0
  4552.9   0.013       0  4674.1    0.12       0  4705.0   0.013       0
  4873.8    0.05       0  4916.5   0.013       0  5868.7    0.05       0
  6153.6    0.12       0
Bank Sta=4400.7,4405.3
Exp/Cntr=0.3,0.1

Type RM Length L Ch R = 1,1410,593,593,593
BEGIN DESCRIPTION:
LGII3010
END DESCRIPTION:
XS GIS Cut Line= 4
      2559835.46     13543953.07      2559581.62     13544467.63
      2559197.40     13545201.75      2559869.78     13545929.01
#Sta/Elev= 30
  4341.9  134.83  4357.5  135.13  4374.4  133.31  4380.0  134.48  4396.8  132.74
  4402.4  133.68  4424.9  132.34  4441.7  129.89  4447.3  131.64  4464.2  128.42
  4469.8  129.43  4486.7  126.10  4492.2  127.44  4509.1  124.87  4649.4  122.09
  4678.6  119.65  4956.0  115.91  5004.7  115.53  5005.1  115.03  5009.3  115.53
  5060.5  115.98  5175.3  116.65  5284.5  117.35  5410.4  118.42  5784.6  121.16
  5788.2  121.19  5884.3  122.32  6238.7  127.85  6506.8  133.24  6734.7  139.39
#Mann=13,-1,0
  4341.9    0.12       0  4956.0    0.05       0  5004.7    0.05       0
  5009.3    0.05       0  5060.5    0.12       0  5175.3    0.05       0
  5284.5    0.12       0  5410.4    0.05       0  5784.6    0.12       0
  5788.2    0.05       0  5884.3   0.013       0  6238.7    0.05       0
  6506.8    0.12       0
Bank Sta=5004.7,5009.3
Exp/Cntr=0.3,0.1

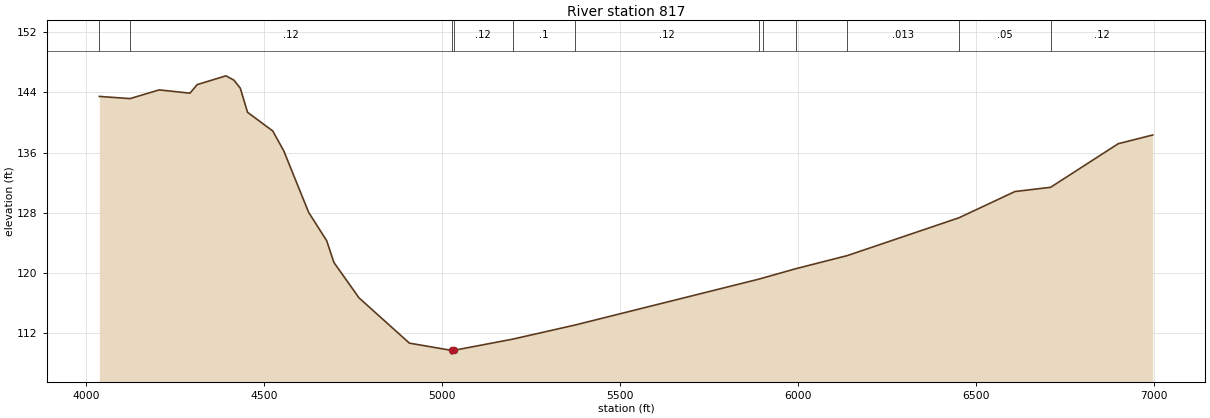
Type RM Length L Ch R = 1,817,0,0,0
BEGIN DESCRIPTION:
LGII3009
END DESCRIPTION:
XS GIS Cut Line= 4
      2559204.26     13543363.04      2559025.88     13544584.26
      2559039.60     13545105.70      2559869.77     13545977.04
#Sta/Elev= 30
  4037.9  143.47  4124.0  143.18  4206.2  144.34  4292.5  143.90  4312.7  145.04
  4393.6  146.21  4416.1  145.63  4434.0  144.56  4454.2  141.36  4525.0  138.88
  4556.0  136.23  4626.0  128.04  4676.6  124.28  4696.8  121.39  4767.5  116.67
  4909.0  110.65  5027.3  109.69  5027.8  109.19  5033.3  109.69  5198.9  111.18
  5373.4  113.05  5890.3  119.16  5903.0  119.33  5995.1  120.56  6139.4  122.30
  6453.0  127.33  6610.3  130.82  6710.2  131.38  6900.3  137.18  6997.2  138.34
#Mann=12,-1,0
  4037.9    0.05       0  4124.0    0.12       0  5027.3    0.05       0
  5033.3    0.12       0  5198.9     0.1       0  5373.4    0.12       0
  5890.3    0.05       0  5903.0    0.12       0  5995.1    0.05       0
  6139.4   0.013       0  6453.0    0.05       0  6710.2    0.12       0
Bank Sta=5027.3,5033.3
Exp/Cntr=0.3,0.1

Chan Stop Cuts=-1