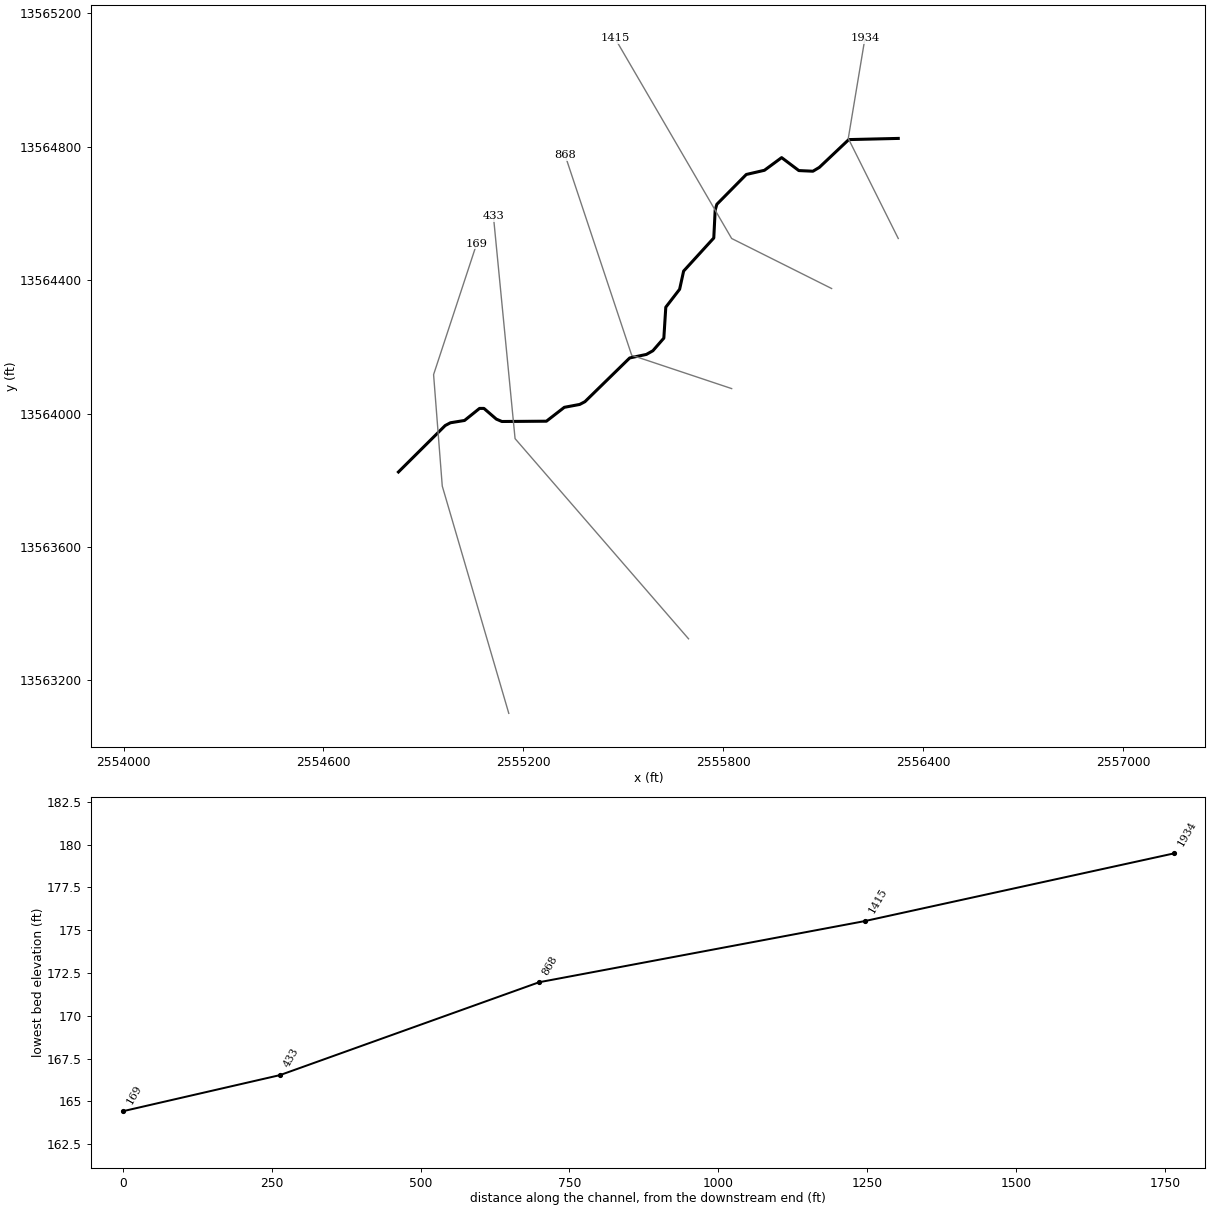
--- TRIB 1 TO REEDS BRANCH.prj (project) ---

Proj Title=TRIB 1 TO REEDS BRANCH Base Level Engineering
Current Plan=p01
Default Exp/Contr=0.3,0.1
English Units
Geom File=g01
Flow File=f01
Plan File=p01
BEGIN DESCRIPTION:
TRIB 1 TO REEDS BRANCH
END DESCRIPTION:

--- TRIB 1 TO REEDS BRANCH.p01 (plan) ---

Plan Title=Multiple Run
Short Identifier=Multiple
Geom File=g01
Flow File=f01
Subcritical Flow
K Sum by GR= 0
Std Step Tol= 0.01
Critical Tol= 0.01
Num of Std Step Trials= 20
Max Error Tol= 0.3
Flow Tol Ratio= 0.001
Split Flow NTrial= 30
Split Flow Tol= 0.02
Split Flow Ratio= 0.02
Log Output Level= 0
Friction Slope Method= 1
Unsteady Friction Slope Method= 2
Unsteady Bridges Friction Slope Method= 1
Parabolic Critical Depth
Global Vel Dist=  1 , 1 , 1
Global Log Level= 0
CheckData=True
Encroach Param= -1, 0, 0, 0
BEGIN DESCRIPTION:
Multiple Run
END DESCRIPTION:

--- TRIB 1 TO REEDS BRANCH.f01 (steady flow) ---

Flow Title=Multiple
Number of Profiles=7
Profile Names=10-year,25-year,50-year,1pct_min,100-year,1pct_plu,500-year
River Rch & RM= TRIB 1 TO REEDS ,Reach-1,1934
     408     638     841     539    1075    2145    1734
Boundary for River Rch & Prof#=TRIB 1 TO REEDS ,Reach-1,1
Up Type=0
Dn Type=3
Dn Slope=0.005
Boundary for River Rch & Prof#=TRIB 1 TO REEDS ,Reach-1,2
Up Type=0
Dn Type=3
Dn Slope=0.005
Boundary for River Rch & Prof#=TRIB 1 TO REEDS ,Reach-1,3
Up Type=0
Dn Type=3
Dn Slope=0.005
Boundary for River Rch & Prof#=TRIB 1 TO REEDS ,Reach-1,4
Up Type=0
Dn Type=3
Dn Slope=0.005
Boundary for River Rch & Prof#=TRIB 1 TO REEDS ,Reach-1,5
Up Type=0
Dn Type=3
Dn Slope=0.005
Boundary for River Rch & Prof#=TRIB 1 TO REEDS ,Reach-1,6
Up Type=0
Dn Type=3
Dn Slope=0.005
Boundary for River Rch & Prof#=TRIB 1 TO REEDS ,Reach-1,7
Up Type=0
Dn Type=3
Dn Slope=0.005

--- TRIB 1 TO REEDS BRANCH.g01 (geometry) ---

Geom Title=Existing Conditions

River Reach=TRIB 1 TO REEDS ,Reach-1
Reach XY= 30
      2556325.00     13564825.00      2556176.45     13564821.49
      2556088.20     13564738.16      2556068.95     13564726.67
      2556026.65     13564728.58      2555975.00     13564767.44
      2555923.35     13564729.45      2555868.93     13564716.89
      2555780.52     13564627.44      2555775.52     13564609.79
      2555771.37     13564526.50      2555680.85     13564427.29
      2555668.86     13564372.83      2555627.34     13564319.03
      2555621.48     13564226.28      2555588.63     13564188.46
      2555569.15     13564177.45      2555518.97     13564166.83
      2555384.68     13564035.76      2555368.97     13564027.50
      2555322.83     13564018.86      2555269.07     13563977.23
      2555135.44     13563976.37      2555118.82     13563983.45
      2555081.59     13564015.56      2555068.38     13564015.59
      2555023.35     13563979.45      2554981.05     13563972.55
      2554965.32     13563964.26      2554825.00     13563825.00

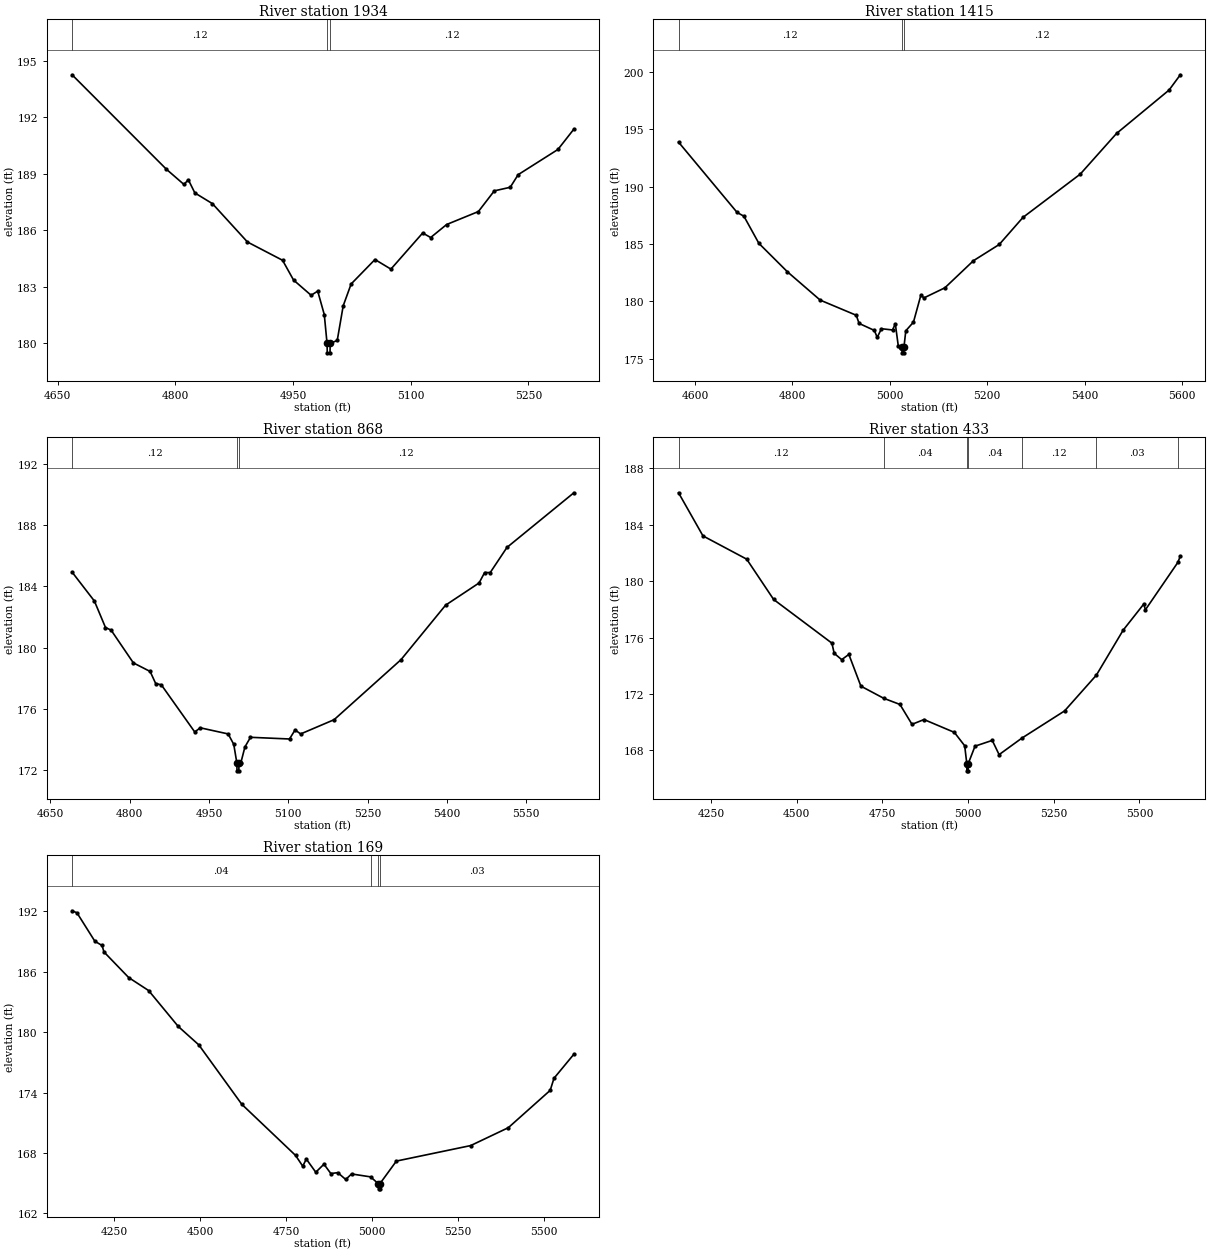
Type RM Length L Ch R = 1,1934,519,519,519
BEGIN DESCRIPTION:
TRIB 1 TO REEDS BRANCH 4.0
END DESCRIPTION:
XS GIS Cut Line= 3
      2556325.01     13564524.99      2556175.00     13564825.00
      2556225.01     13565125.04
#Sta/Elev= 30
  4668.4  194.26  4788.6  189.24  4811.0  188.43  4816.6  188.68  4824.9  187.98
  4847.3  187.41  4892.0  185.37  4936.7  184.40  4950.7  183.35  4973.1  182.54
  4981.5  182.76  4989.9  181.51  4993.4  179.98  4993.7  179.48  4997.2  179.48
  4997.4  179.98  5006.4  180.14  5014.0  181.98  5024.1  183.14  5054.5  184.44
  5074.8  183.93  5115.3  185.85  5125.5  185.61  5145.8  186.30  5186.3  186.99
  5206.6  188.09  5226.9  188.28  5237.0  188.95  5287.7  190.29  5308.0  191.37
#Mann=3,-1,0
  4668.4    0.12       0  4993.4    0.05       0  4997.4    0.12       0
Bank Sta=4993.4,4997.4
Exp/Cntr=0.3,0.1

Type RM Length L Ch R = 1,1415,547,547,547
BEGIN DESCRIPTION:
TRIB 1 TO REEDS BRANCH 3.0
END DESCRIPTION:
XS GIS Cut Line= 3
      2556125.00     13564375.00      2555825.00     13564525.00
      2555475.02     13565124.97
#Sta/Elev= 30
  4566.4  193.87  4686.6  187.75  4700.6  187.42  4731.3  185.06  4790.0  182.58
  4857.1  180.12  4931.2  178.80  4937.0  178.09  4968.4  177.48  4974.2  176.87
  4982.9  177.63  5005.6  177.52  5011.4  178.05  5017.6  176.09  5025.1  176.03
  5025.3  175.53  5028.8  175.53  5029.1  176.03  5032.9  177.45  5048.6  178.20
  5063.9  180.56  5070.1  180.31  5113.1  181.19  5171.8  183.55  5224.7  184.96
  5273.5  187.32  5390.9  191.08  5465.4  194.62  5573.3  198.40  5596.4  199.73
#Mann=3,-1,0
  4566.4    0.12       0  5025.1    0.05       0  5029.1    0.12       0
Bank Sta=5025.1,5029.1
Exp/Cntr=0.3,0.1

Type RM Length L Ch R = 1,868,435,435,435
BEGIN DESCRIPTION:
TRIB 1 TO REEDS BRANCH 2.0
END DESCRIPTION:
XS GIS Cut Line= 3
      2555825.00     13564075.00      2555525.00     13564175.00
      2555324.99     13564775.02
#Sta/Elev= 30
  4691.2  184.94  4733.4  183.05  4754.4  181.32  4765.0  181.15  4807.1  179.01
  4838.8  178.45  4849.3  177.66  4859.9  177.58  4923.1  174.50  4933.6  174.77
  4986.3  174.37  4996.9  173.69  5002.8  172.46  5003.0  171.96  5006.5  171.96
  5006.8  172.46  5010.1  172.46  5018.0  173.52  5028.5  174.15  5102.3  174.04
  5112.8  174.63  5123.4  174.37  5186.6  175.30  5313.1  179.22  5397.4  182.78
  5460.7  184.23  5471.2  184.91  5481.8  184.91  5513.4  186.55  5639.9  190.12
#Mann=3,-1,0
  4691.2    0.12       0  5002.8    0.05       0  5006.8    0.12       0
Bank Sta=5002.8,5006.8
Exp/Cntr=0.3,0.1

Type RM Length L Ch R = 1,433,264,264,264
BEGIN DESCRIPTION:
TRIB 1 TO REEDS BRANCH 1.0
END DESCRIPTION:
XS GIS Cut Line= 3
      2555695.61     13563324.86      2555175.00     13563925.00
      2555110.10     13564591.06
#Sta/Elev= 30
  4155.7  186.27  4227.0  183.21  4354.5  181.56  4433.1  178.70  4603.1  175.60
  4609.7  174.88  4631.6  174.43  4652.5  174.80  4687.6  172.55  4754.0  171.69
  4801.6  171.25  4836.7  169.84  4871.8  170.18  4960.2  169.27  4990.4  168.32
  4996.6  167.04  4996.8  166.54  5000.3  166.54  5000.6  167.04  5020.5  168.29
  5070.8  168.70  5090.8  167.69  5157.1  168.86  5281.7  170.79  5374.5  173.33
  5452.6  176.52  5512.6  178.37  5517.6  177.97  5612.2  181.33  5619.4  181.78
#Mann=7,-1,0
  4155.7    0.12       0  4754.0    0.04       0  4996.6    0.04       0
  5000.6    0.04       0  5157.1    0.12       0  5374.5    0.03       0
  5612.2    0.05       0
Bank Sta=4996.6,5000.6
Exp/Cntr=0.3,0.1

Type RM Length L Ch R = 1,169,0,0,0
BEGIN DESCRIPTION:
TRIB 1 TO REEDS BRANCH 0.5
END DESCRIPTION:
XS GIS Cut Line= 4
      2555156.15     13563101.36      2554956.51     13563782.75
      2554930.47     13564116.95      2555060.01     13564509.89
#Sta/Elev= 30
  4127.8  192.07  4142.0  191.87  4194.1  189.04  4215.0  188.62  4220.5  187.98
  4292.5  185.43  4350.4  184.14  4436.6  180.57  4496.3  178.74  4621.4  172.83
  4777.7  167.75  4798.5  166.68  4808.9  167.39  4836.4  166.08  4860.2  166.88
  4880.2  165.95  4900.3  166.04  4923.5  165.36  4940.4  165.91  4995.7  165.62
  5018.6  164.93  5018.9  164.43  5022.4  164.43  5022.6  164.93  5070.8  167.19
  5286.8  168.73  5396.3  170.51  5518.0  174.22  5529.0  175.42  5586.8  177.81
#Mann=4,-1,0
  4127.8    0.04       0  4995.7    0.03       0  5018.6    0.03       0
  5022.6    0.03       0
Bank Sta=5018.6,5022.6
Exp/Cntr=0.3,0.1

Chan Stop Cuts=-1