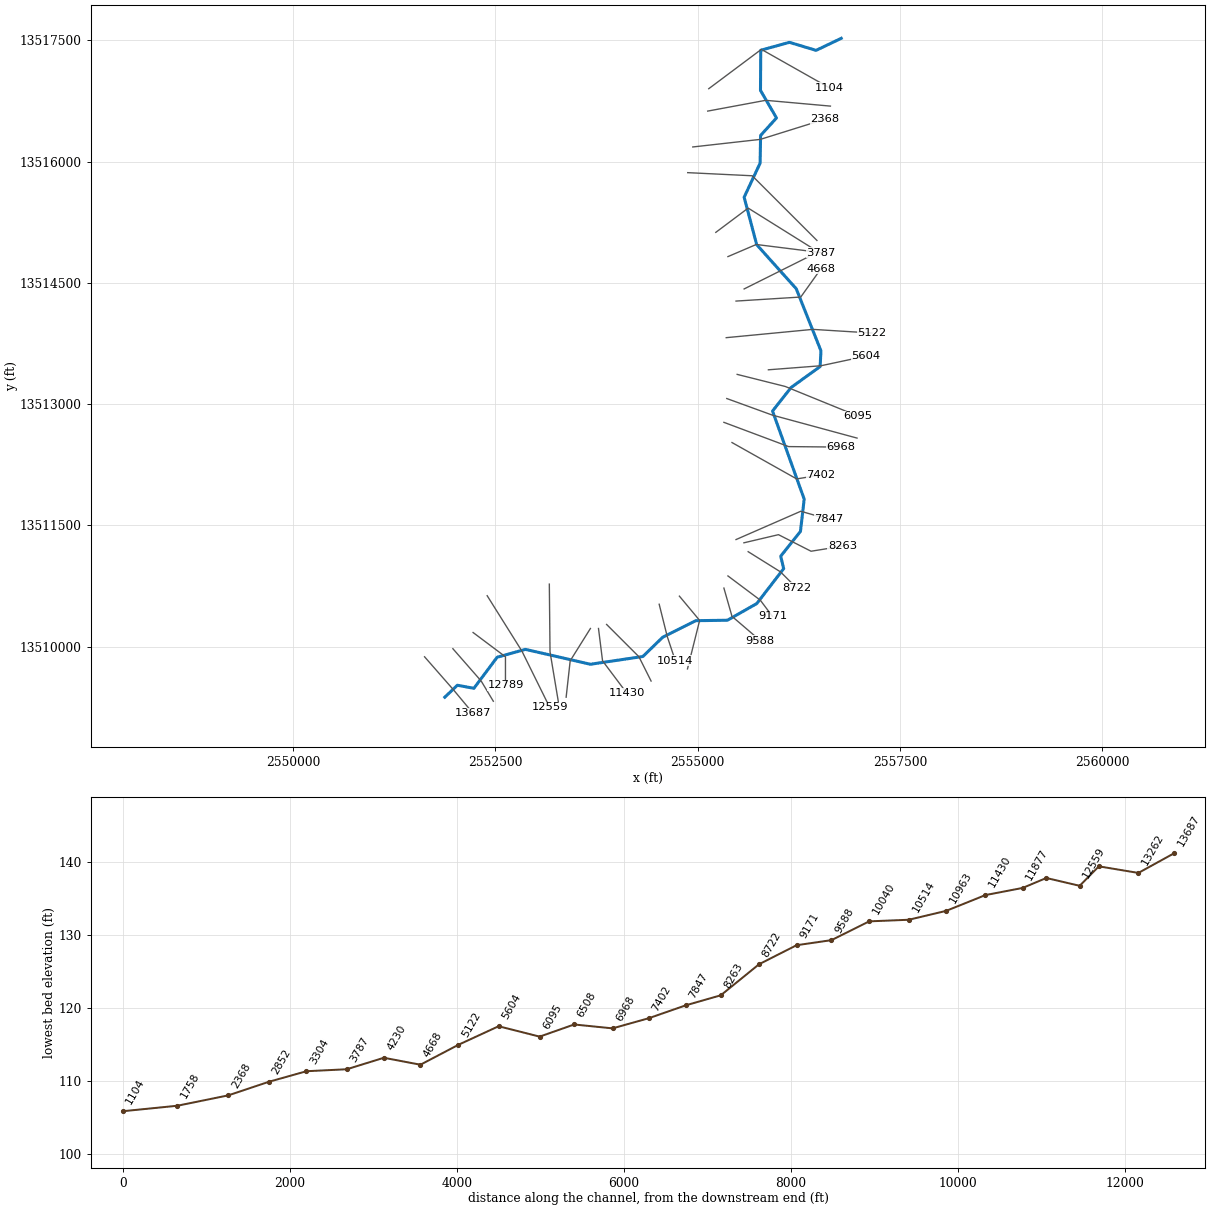
--- TRIB 1 TO ROCKY CREEK.prj (project) ---

Proj Title=TRIB 1 TO ROCKY CREEK Base Level Engineering
Current Plan=p01
Default Exp/Contr=0.3,0.1
English Units
Geom File=g01
Flow File=f01
Plan File=p01
Y Axis Title=Elevation
X Axis Title(PF)=Main Channel Distance
X Axis Title(XS)=Station
BEGIN DESCRIPTION:
TRIB 1 TO ROCKY CREEK
END DESCRIPTION:
DSS Export Rating Curves= 0
DSS Export Rating Curve Sorted= 0
DSS Export Volume Flow Curves= 0
DXF OffsetX= 0
DXF OffsetY= 0
DXF ScaleX= 1
DXF ScaleY= 10

--- TRIB 1 TO ROCKY CREEK.p01 (plan) ---

Plan Title=Multiple Run
Short Identifier=Multiple
Geom File=g01
Flow File=f01
Subcritical Flow
K Sum by GR= 0
Std Step Tol= 0.01
Critical Tol= 0.01
Num of Std Step Trials= 20
Max Error Tol= 0.3
Flow Tol Ratio= 0.001
Split Flow NTrial= 30
Split Flow Tol= 0.02
Split Flow Ratio= 0.02
Log Output Level= 0
Friction Slope Method= 1
Unsteady Friction Slope Method= 2
Unsteady Bridges Friction Slope Method= 1
Parabolic Critical Depth
Global Vel Dist=  1 , 1 , 1
Global Log Level= 0
CheckData=True
Encroach Param= -1, 0, 0, 0
BEGIN DESCRIPTION:
Multiple Run
END DESCRIPTION:

--- TRIB 1 TO ROCKY CREEK.f01 (steady flow) ---

Flow Title=Multiple
Number of Profiles=7
Profile Names=10-year,25-year,50-year,1pct_min,100-year,1pct_plu,500-year
River Rch & RM= TRIB 1 TO ROCKY ,Reach-1,13687
    1182    1942    2642    1735    3462    6908    5884
River Rch & RM= TRIB 1 TO ROCKY ,Reach-1,11877
    1228    2012    2731    1790    3572    7127    6042
River Rch & RM= TRIB 1 TO ROCKY ,Reach-1,10040
    1257    2062    2801    1838    3667    7317    6214
River Rch & RM= TRIB 1 TO ROCKY ,Reach-1,9588
    1616    2687    3682    2434    4857    9692    8363
River Rch & RM= TRIB 1 TO ROCKY ,Reach-1,8722
    2010    3374    4654    3096    6177   12325   10765
River Rch & RM= TRIB 1 TO ROCKY ,Reach-1,6095
    2137    3587    4948    3289    6562   13093   11420
Boundary for River Rch & Prof#=TRIB 1 TO ROCKY ,Reach-1,1
Up Type=0
Dn Type=3
Dn Slope=0.005
Boundary for River Rch & Prof#=TRIB 1 TO ROCKY ,Reach-1,2
Up Type=0
Dn Type=3
Dn Slope=0.005
Boundary for River Rch & Prof#=TRIB 1 TO ROCKY ,Reach-1,3
Up Type=0
Dn Type=3
Dn Slope=0.005
Boundary for River Rch & Prof#=TRIB 1 TO ROCKY ,Reach-1,4
Up Type=0
Dn Type=3
Dn Slope=0.005
Boundary for River Rch & Prof#=TRIB 1 TO ROCKY ,Reach-1,5
Up Type=0
Dn Type=3
Dn Slope=0.005
Boundary for River Rch & Prof#=TRIB 1 TO ROCKY ,Reach-1,6
Up Type=0
Dn Type=3
Dn Slope=0.005
Boundary for River Rch & Prof#=TRIB 1 TO ROCKY ,Reach-1,7
Up Type=0
Dn Type=3
Dn Slope=0.005

--- TRIB 1 TO ROCKY CREEK.g01 (geometry) ---

Geom Title=Existing Conditions
Program Version=4.10

River Reach=TRIB 1 TO ROCKY ,Reach-1
Reach XY= 30
        2551875.       13509375.      2552030.89     13509523.04
      2552234.68     13509485.19      2552522.29      13509869.6
      2552871.71      13509966.9        2553675.     13509782.56
      2554323.53     13509878.54      2554568.83     13510117.14
       2554976.5     13510321.38      2555369.03     13510327.14
      2555731.07     13510533.13       2556063.9     13510964.94
      2556027.15     13511119.03      2556271.46     13511426.46
      2556317.44       13511825.      2555926.04     13512914.56
       2556154.8     13513205.39      2556514.52      13513465.2
      2556524.48     13513659.78      2556219.17      13514427.3
      2555730.52     13514972.57      2555575.09     13515559.61
      2555772.76     13515980.93      2555778.54     13516323.54
      2555975.05     13516540.34      2555777.24     13516880.93
      2555780.34     13517377.74      2556135.19     13517475.55
       2556464.5      13517376.2        2556775.       13517525.

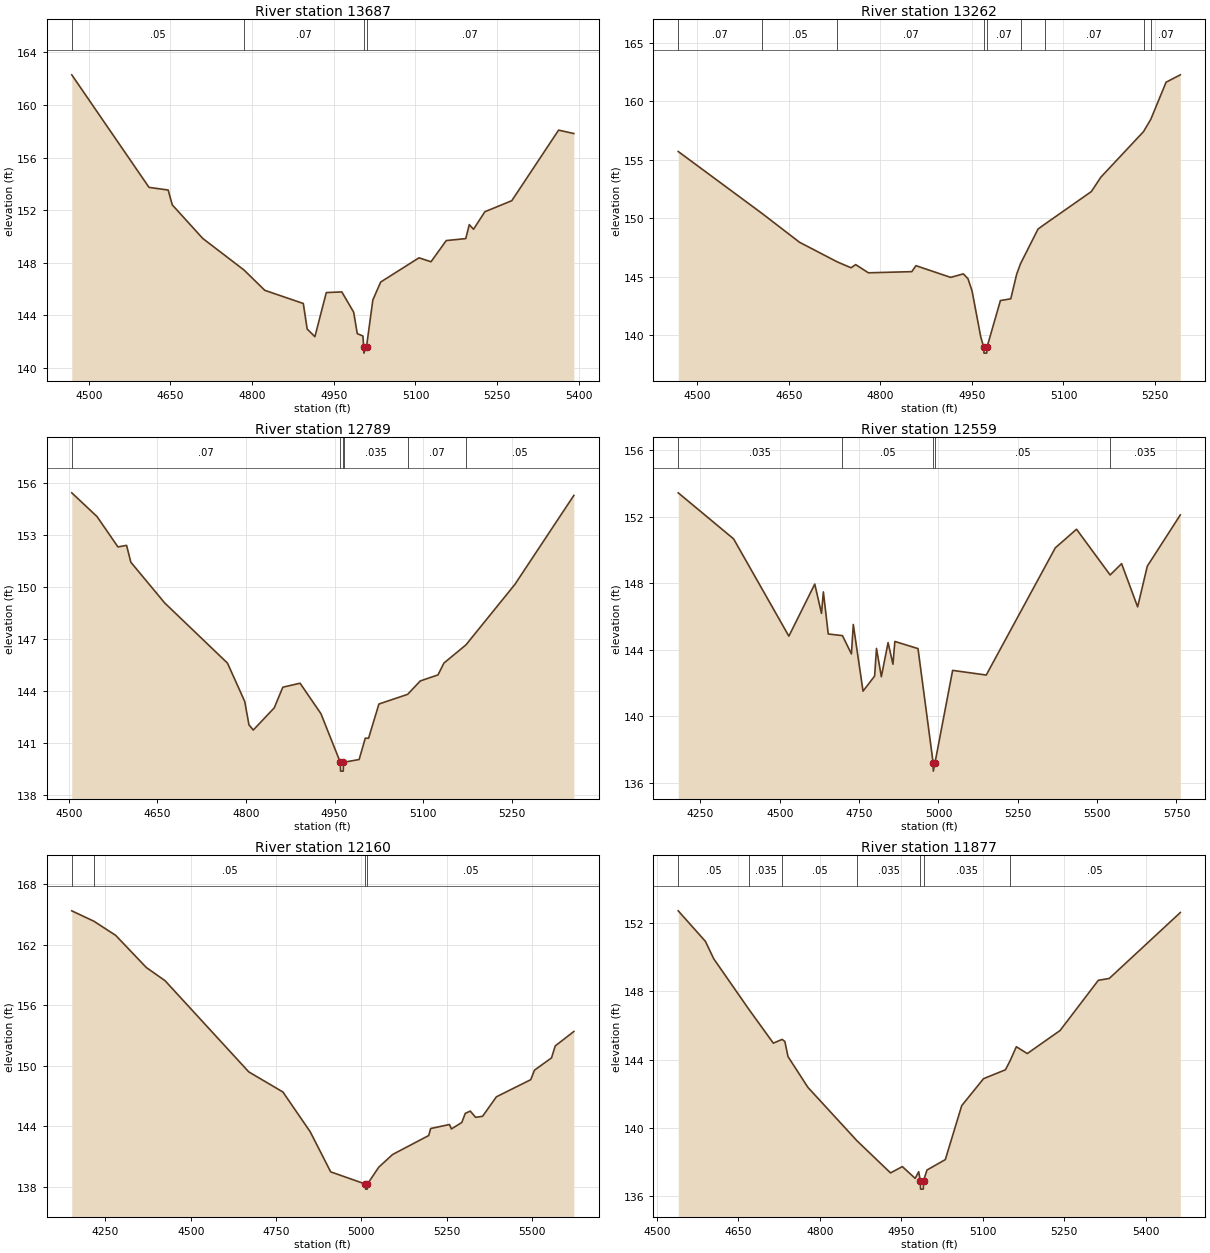
Type RM Length L Ch R = 1 ,13687   ,425,425,425
BEGIN DESCRIPTION:
TRIB 1 TO ROCKY CREEK 28.0
END DESCRIPTION:
XS GIS Cut Line= 3
      2551625.03     13509874.97        2551975.       13509475.
      2552225.01     13509174.98
#Sta/Elev= 30
  4468.8  162.28  4610.7  153.73  4645.8  153.53  4653.4   152.4  4709.4  149.85
  4785.2  147.45  4823.3  145.91    4894  144.91  4901.1  142.97  4915.3  142.39
  4936.2  145.74  4964.7  145.79  4986.5  144.25  4993.1  142.62  5003.5  142.44
  5004.8  141.64  5005.2  141.14  5010.1  141.64  5021.7  145.18  5036.1  146.54
  5106.4  148.38  5128.5  148.08  5156.5  149.69  5192.3  149.84  5198.8   150.9
  5206.6  150.55  5227.4  151.88  5276.9  152.72  5362.8  158.08  5390.8  157.82
#Mann= 4 ,-1 , 0
  4468.8     .05       0  4785.2     .07       0  5004.8     .05       0
  5010.1     .07       0
Bank Sta=5004.8,5010.1
XS Rating Curve= 0 ,0
Exp/Cntr=0.3,0.1

Type RM Length L Ch R = 1 ,13262   ,473,473,473
BEGIN DESCRIPTION:
TRIB 1 TO ROCKY CREEK 27.0
END DESCRIPTION:
XS GIS Cut Line= 3
      2551975.02     13509974.97        2552325.       13509575.
      2552474.99     13509325.01
#Sta/Elev= 30
  4468.5  155.69  4605.4  150.42  4667.3  147.94  4729.3  146.26  4751.8  145.76
  4759.4  146.03  4780.2  145.33  4851.4  145.43  4858.1  145.94    4915  144.94
  4935.9  145.24  4943.5  144.82  4950.1  143.79  4964.4  139.86  4969.3  138.97
  4969.7  138.47  4974.2  138.47  4974.6  138.97  4996.6  142.96  5013.6  143.11
  5023.3  145.22  5029.6  146.11  5058.3  149.07  5069.8   149.5  5145.7  152.27
  5161.3   153.5  5231.2  157.39  5243.2  158.45  5268.2  161.61  5291.5  162.24
#Mann= 9 ,-1 , 0
  4468.5     .07       0  4605.4     .05       0  4729.3     .07       0
  4969.3     .05       0  4974.6     .07       0  5029.6     .12       0
  5069.8     .07       0  5231.2     .12       0  5243.2     .07       0
Bank Sta=4969.3,4974.6
XS Rating Curve= 0 ,0
Exp/Cntr=0.3,0.1

Type RM Length L Ch R = 1 ,12789   ,230,230,230
BEGIN DESCRIPTION:
TRIB 1 TO ROCKY CREEK 26.0
END DESCRIPTION:
XS GIS Cut Line= 3
      2552224.96     13510175.03        2552625.       13509875.
        2552625.     13509525.04
#Sta/Elev= 30
    4505  155.42  4547.8  154.05  4583.2   152.3  4597.8  152.39    4605  151.42
  4662.3  149.07  4768.6   145.6  4797.8  143.39    4805  142.04  4812.3  141.74
  4847.8  143.02  4862.3  144.21  4891.5  144.44  4926.9  142.68  4959.7  139.87
  4960.1  139.37  4964.6  139.37    4965  139.87  4965.4  139.88  4991.5  140.04
  5001.9  141.27  5007.5  141.27    5025  143.24  5073.7   143.8    5095  144.57
    5125  144.92    5135   145.6  5172.3  146.65    5255  150.13    5355  155.27
#Mann= 6 ,-1 , 0
    4505     .07       0  4959.7    .035       0    4965     .07       0
  4965.4    .035       0  5073.7     .07       0  5172.3     .05       0
Bank Sta=4959.7,4965
XS Rating Curve= 0 ,0
Exp/Cntr=0.3,0.1

Type RM Length L Ch R = 1 ,12559   ,399,399,399
BEGIN DESCRIPTION:
Mapping XS cc4fec5d
END DESCRIPTION:
XS GIS Cut Line= 3
      2552398.97     13510630.43      2552828.63      13509944.7
      2553170.76     13509251.78
#Sta/Elev= 30
  4180.1  153.45  4354.6  150.68  4528.7  144.83  4610.3  147.96  4631.5   146.2
  4637.4  147.49  4652.8  144.96  4697.6  144.86  4725.8  143.76  4731.7  145.53
  4762.4  141.52  4798.9  142.43  4804.8  144.09  4820.1  142.39  4841.3  144.44
  4856.7  143.14  4862.6  144.51  4935.6  144.08  4983.3  137.21  4983.8  136.71
  4989.1  137.21  5044.7  142.77  5150.6  142.49  5368.2  150.14  5435.1  151.26
    5541  148.51  5577.1  149.19  5627.6  146.59  5658.1  149.04  5762.1  152.12
#Mann= 5 ,-1 , 0
  4180.1    .035       0  4697.6     .05       0  4983.3     .05       0
  4989.1     .05       0    5541    .035       0
Bank Sta=4983.3,4989.1
XS Rating Curve= 0 ,0
Exp/Cntr=0.3,0.1

Type RM Length L Ch R = 1 ,12160   ,283,283,283
BEGIN DESCRIPTION:
Mapping XS 7721f54b
END DESCRIPTION:
XS GIS Cut Line= 3
      2553167.18     13510773.66      2553175.86     13509936.02
      2553280.01     13509311.12
#Sta/Elev= 30
  4151.5  165.34  4216.3  164.31  4280.2  162.91  4370.2  159.72  4424.6  158.43
  4670.2  149.39  4770.2   147.4  4850.2  143.46  4910.2  139.49    5012  138.28
  5012.5  137.78  5017.4  137.78  5017.9  138.28    5051  139.95  5091.6  141.21
  5197.5  143.09  5203.1  143.78  5258.3  144.18  5263.9  143.74  5294.4  144.38
  5304.5  145.28  5319.1  145.51  5334.9  144.89  5355.2  144.99  5395.7  146.92
  5496.5  148.62  5507.3  149.56  5557.4  150.78  5568.1  151.96  5622.7  153.39
#Mann= 4 ,-1 , 0
  4151.5    .035       0  4216.3     .05       0    5012     .05       0
  5017.9     .05       0
Bank Sta=5012,5017.9
XS Rating Curve= 0 ,0
Exp/Cntr=0.3,0.1

Type RM Length L Ch R = 1 ,11877   ,447,447,447
BEGIN DESCRIPTION:
TRIB 1 TO ROCKY CREEK 24.0
END DESCRIPTION:
XS GIS Cut Line= 3
        2553675.     13510224.99        2553425.       13509825.
        2553375.     13509374.96
#Sta/Elev= 30
  4539.4  152.72  4589.5  150.93  4604.8  149.91  4669.5  146.95  4714.5  144.97
  4730.7  145.19  4735.7  145.07  4741.6  144.18  4778.2  142.38  4868.3  139.26
  4930.3  137.37  4952.1  137.74  4975.7  137.05  4982.2  137.44  4985.1  136.92
  4985.6  136.42  4990.6  136.42  4991.1  136.92  4997.5  137.54  5031.2  138.15
  5061.4  141.31  5101.6  142.89  5141.9  143.41  5150.2  143.92    5162  144.76
  5182.1  144.36  5242.5  145.71  5312.9  148.65  5333.1  148.76  5463.9  152.62
#Mann= 7 ,-1 , 0
  4539.4     .05       0  4669.5    .035       0  4730.7     .05       0
  4868.3    .035       0  4985.1    .035       0  4991.1    .035       0
  5150.2     .05       0
Bank Sta=4985.1,4991.1
XS Rating Curve= 0 ,0
Exp/Cntr=0.3,0.1

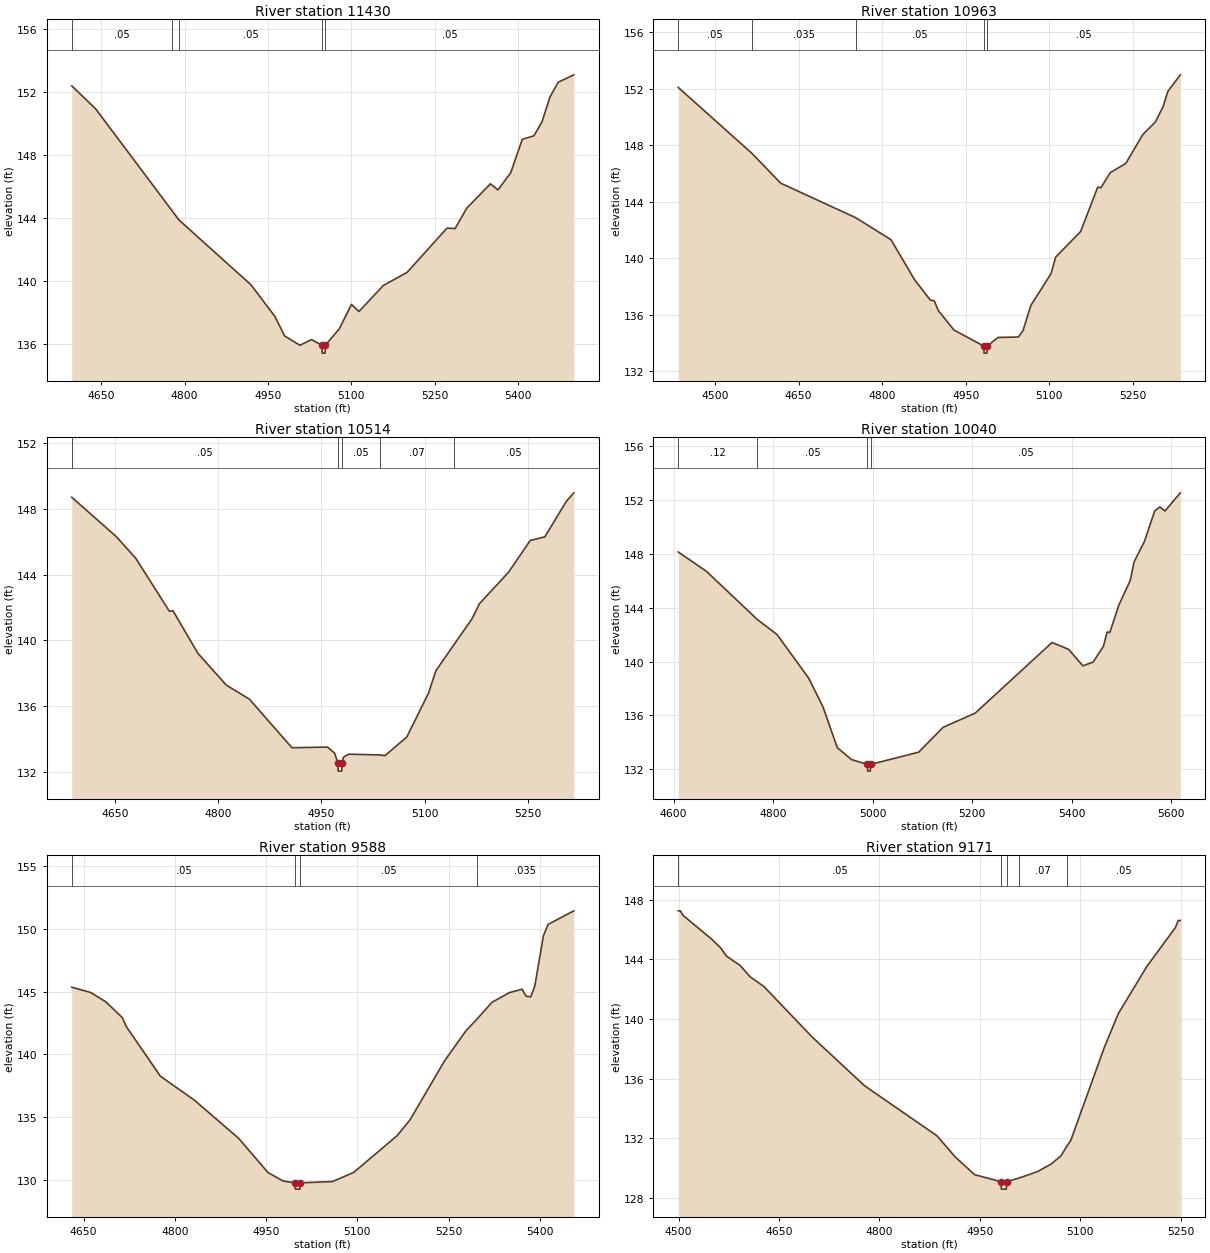
Type RM Length L Ch R = 1 ,11430   ,467,467,467
BEGIN DESCRIPTION:
TRIB 1 TO ROCKY CREEK 23.0
END DESCRIPTION:
XS GIS Cut Line= 3
        2553775.     13510224.97        2553825.       13509825.
      2554125.01     13509424.99
#Sta/Elev= 30
    4597  152.39  4639.8  150.94    4778  144.44  4789.9  143.88  4919.5  139.77
  4962.3  137.77  4979.9  136.53  5007.4  135.94  5028.2   136.3    5047  135.94
  5047.5  135.44  5052.6  135.44  5053.1  135.94  5078.2  136.98  5100.1  138.53
  5113.6  138.08  5157.4  139.73  5200.1  140.56    5272  143.37  5286.5  143.34
  5307.4  144.63  5350.1  146.18  5363.6  145.79  5386.5  146.88  5407.4     149
  5428.2  149.22  5442.8  150.11  5457.4   151.7    5472  152.62  5500.1  153.09
#Mann= 5 ,-1 , 0
    4597     .05       0    4778    .035       0  4789.9     .05       0
    5047     .05       0  5053.1     .05       0
Bank Sta=5047,5053.1
XS Rating Curve= 0 ,0
Exp/Cntr=0.3,0.1

Type RM Length L Ch R = 1 ,10963   ,449,449,449
BEGIN DESCRIPTION:
TRIB 1 TO ROCKY CREEK 22.0
END DESCRIPTION:
XS GIS Cut Line= 3
      2553875.03     13510274.97        2554275.       13509875.
      2554425.02     13509574.96
#Sta/Elev= 30
    4434  152.08    4567  147.39  4617.8  145.31  4752.4  142.87  4815.8  141.31
  4858.2  138.48  4886.5  137.04  4893.6  136.99  4900.6  136.31  4928.9  134.92
  4982.4  133.79  4982.9  133.29    4988  133.29  4988.5  133.79    5008   134.4
  5044.4  134.43  5052.7  134.87  5066.7  136.65  5103.1  138.91  5111.4  140.08
  5156.2  141.89  5186.9  145.03  5192.5  144.98  5209.3  146.05  5237.2   146.7
    5268  148.76  5290.3  149.63  5304.3  150.73  5312.7   151.8  5335.1  152.97
#Mann= 5 ,-1 , 0
    4434     .05       0    4567    .035       0  4752.4     .05       0
  4982.4     .05       0  4988.5     .05       0
Bank Sta=4982.4,4988.5
XS Rating Curve= 0 ,0
Exp/Cntr=0.3,0.1

Type RM Length L Ch R = 1 ,10514   ,474,474,474
BEGIN DESCRIPTION:
TRIB 1 TO ROCKY CREEK 21.0
END DESCRIPTION:
XS GIS Cut Line= 3
        2554525.     13510525.01        2554625.       13510125.
      2554724.99     13509825.04
#Sta/Elev= 30
  4587.7  148.69  4652.1  146.31  4680.5  144.99  4729.4  141.77  4734.6   141.8
  4770.7  139.22  4811.9  137.29  4845.4  136.44  4907.2  133.49  4958.8  133.53
  4969.1  133.16  4973.7  132.57  4974.2  132.07  4979.4  132.07  4979.9  132.57
    4982  132.92  4989.7   133.1  5035.6  133.05  5042.2  133.01  5073.8  134.14
  5105.4  136.81    5116  138.16  5142.5  139.76  5168.7  141.33  5179.2  142.23
  5221.4  144.14    5253  146.07  5274.1  146.29  5305.7  148.47  5316.2  148.96
#Mann= 5 ,-1 , 0
  4587.7     .05       0  4973.7     .05       0  4979.9     .05       0
  5035.6     .07       0  5142.5     .05       0
Bank Sta=4973.7,4979.9
XS Rating Curve= 0 ,0
Exp/Cntr=0.3,0.1

Type RM Length L Ch R = 1 ,10040   ,452,452,452
BEGIN DESCRIPTION:
TRIB 1 TO ROCKY CREEK 20.0
END DESCRIPTION:
XS GIS Cut Line= 3
      2554774.98     13510625.03        2555025.       13510325.
        2554875.     13509725.01
#Sta/Elev= 30
  4609.5  148.15  4666.2  146.71  4768.4  143.13    4808  142.01  4871.8  138.76
  4900.5  136.62  4929.1   133.6  4957.7  132.71  4989.7  132.35  4990.2  131.85
  4995.5  131.85    4996  132.35  5092.8  133.26  5141.8  135.11  5206.2  136.16
  5360.8  141.42  5394.3   140.9  5422.7  139.68  5443.3  139.96  5463.9  141.13
  5471.6   142.2  5476.8  142.16  5494.8  144.18    5518  146.05  5525.7  147.42
  5546.4  148.93    5567   151.2  5577.3   151.5  5587.6   151.2  5618.5  152.55
#Mann= 4 ,-1 , 0
  4609.5     .12       0  4768.4     .05       0  4989.7     .05       0
    4996     .05       0
Bank Sta=4989.7,4996
XS Rating Curve= 0 ,0
Exp/Cntr=0.3,0.1

Type RM Length L Ch R = 1 ,9588    ,417,417,417
BEGIN DESCRIPTION:
TRIB 1 TO ROCKY CREEK 19.0
END DESCRIPTION:
XS GIS Cut Line= 3
        2555325.     13510724.99        2555425.       13510375.
      2555775.02     13510074.98
#Sta/Elev= 30
  4630.7  145.35  4661.9  144.93  4686.6  144.19  4713.9  142.92  4720.4  142.21
  4776.3  138.27  4832.2  136.36    4905  133.32  4953.1   130.6  4977.8  129.93
  4997.7  129.78  4998.2  129.28  5005.5  129.28    5006  129.78  5058.9  129.88
    5094  130.61  5165.4  133.54  5186.2  134.77  5243.3  139.49  5278.4  141.88
  5295.8  142.77  5321.2  144.15  5349.8  144.92  5370.6  145.19  5377.2  144.64
  5384.9  144.58  5391.5  145.43  5405.7  149.44  5413.4  150.35  5455.7  151.43
#Mann= 4 ,-1 , 0
  4630.7     .05       0  4997.7     .05       0    5006     .05       0
  5295.8    .035       0
Bank Sta=4997.7,5006
XS Rating Curve= 0 ,0
Exp/Cntr=0.3,0.1

Type RM Length L Ch R = 1 ,9171    ,449,449,449
BEGIN DESCRIPTION:
TRIB 1 TO ROCKY CREEK 18.0
END DESCRIPTION:
XS GIS Cut Line= 3
      2555375.01     13510874.99        2555775.       13510575.
      2555925.01     13510374.99
#Sta/Elev= 30
  4499.5  147.25  4502.6  147.25  4506.8  146.94  4549.5  145.35    4563  144.76
  4571.4  144.22  4592.2  143.58  4606.8  142.83  4627.6  142.17  4699.5  138.79
  4777.6  135.53  4885.9  132.17    4913  130.76  4942.2  129.56  4981.7  129.09
  4982.2  128.59  4989.6  128.59  4990.1  129.09  5009.1  129.34  5035.9  129.76
  5056.8  130.28  5071.4  130.83  5080.1  131.48  5085.9  131.86  5135.9  138.08
  5156.8  140.35  5199.5  143.52  5242.2  146.13  5246.4   146.6  5249.5   146.6
#Mann= 5 ,-1 , 0
  4499.5     .05       0  4981.7     .05       0  4990.1     .05       0
  5009.1     .07       0  5080.1     .05       0
Bank Sta=4981.7,4990.1
XS Rating Curve= 0 ,0
Exp/Cntr=0.3,0.1

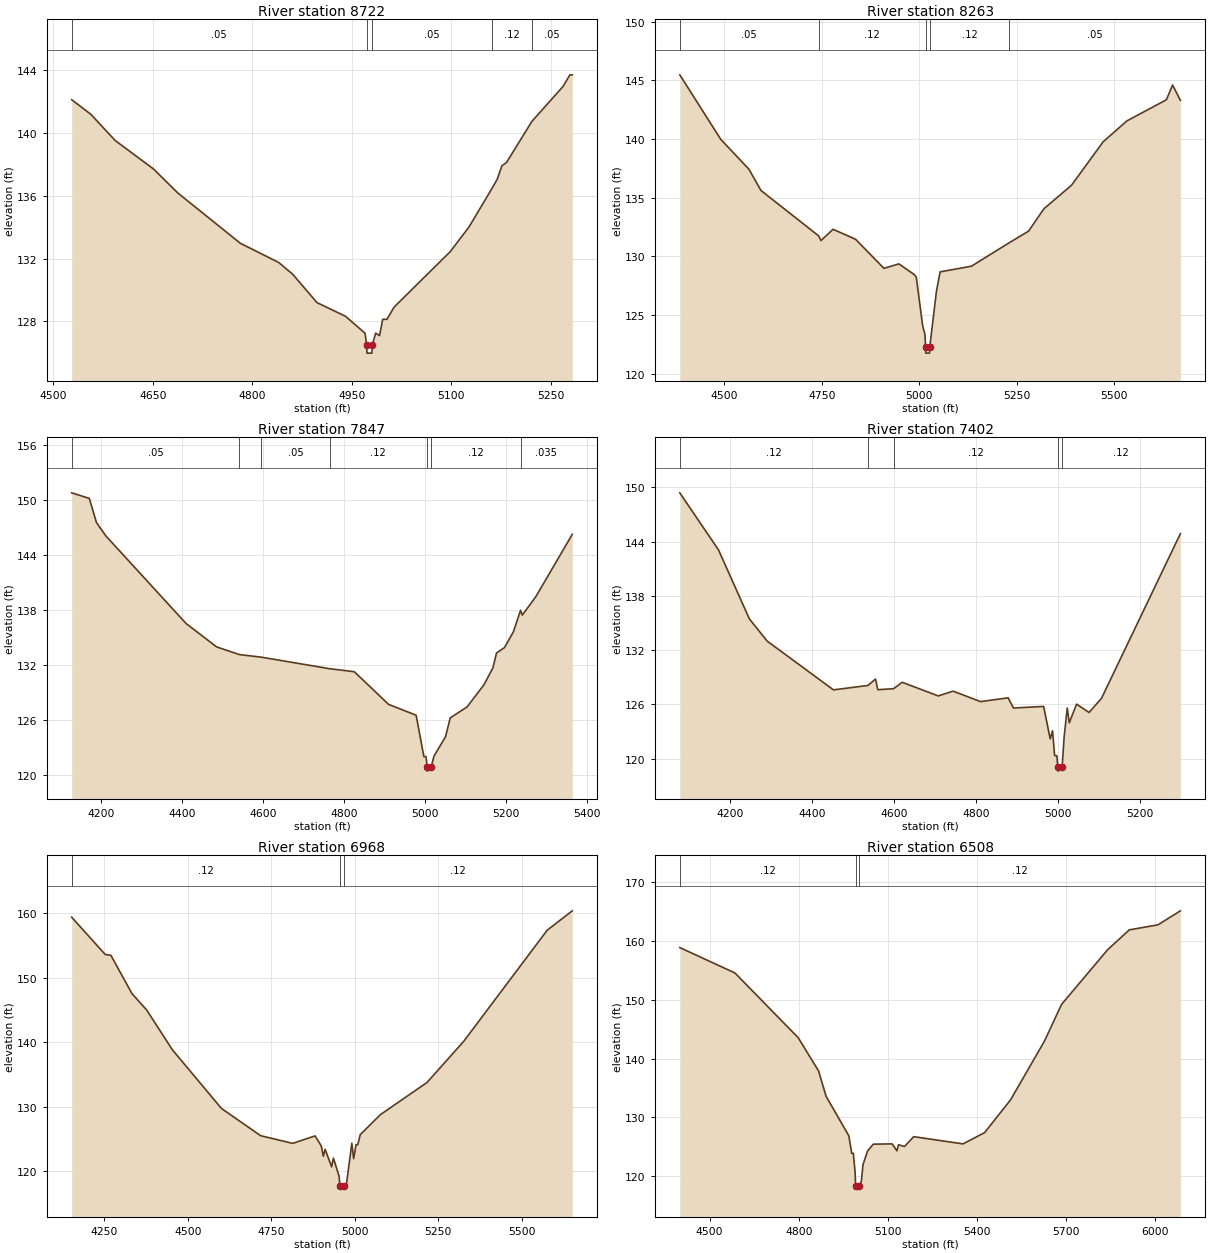
Type RM Length L Ch R = 1 ,8722    ,459,459,459
BEGIN DESCRIPTION:
TRIB 1 TO ROCKY CREEK 17.0
END DESCRIPTION:
XS GIS Cut Line= 3
      2555624.96     13511175.03        2556025.       13510925.
      2556225.01     13510724.99
#Sta/Elev= 30
  4527.9  142.09  4556.8  141.16  4593.4   139.5  4651.2  137.69  4687.7  136.17
  4782.1  132.97  4839.9  131.75  4861.1     131  4897.6   129.2  4940.7  128.33
  4970.2  127.25  4972.5  126.49    4973  125.99  4980.4  125.99  4980.9  126.49
  4986.1  127.26    4992   127.1  4996.7  128.14  5003.2  128.14  5013.8  128.91
  5098.6  132.44  5126.9  134.01  5161.4  136.45  5169.4  137.04  5176.4  137.89
  5183.5  138.11  5221.6  140.71  5268.3  142.92    5279  143.67  5282.5  143.67
#Mann= 5 ,-1 , 0
  4527.9     .05       0  4972.5     .05       0  4980.9     .05       0
  5161.4     .12       0  5221.6     .05       0
Bank Sta=4972.5,4980.9
XS Rating Curve= 0 ,0
Exp/Cntr=0.3,0.1

Type RM Length L Ch R = 1 ,8263    ,416,416,416
BEGIN DESCRIPTION:
Mapping XS 9b8a4ee5
END DESCRIPTION:
XS GIS Cut Line= 4
      2555572.36      13511284.8      2555999.47      13511385.5
      2556402.25     13511180.63      2556790.56     13511243.04
#Sta/Elev= 30
  4385.7  145.47  4490.8  139.97  4563.1  137.42  4593.9  135.61  4741.8  131.74
    4748  131.34  4778.8   132.3  4836.5  131.45  4909.3  128.97  4947.7  129.35
  4986.6  128.45  4992.2  128.23  5008.9  124.02  5014.5  123.34  5016.2  122.24
  5016.7  121.74  5026.3  121.74  5026.8  122.24  5043.9  126.99  5053.4  128.67
  5133.6  129.15  5231.1  131.16  5280.3  132.14  5319.7  134.05  5390.6  136.06
  5471.6  139.76  5532.4  141.54  5633.7  143.34  5649.7   144.6  5669.7   143.3
#Mann= 5 ,-1 , 0
  4385.7     .05       0  4741.8     .12       0  5016.2     .05       0
  5026.8     .12       0  5231.1     .05       0
Bank Sta=5016.2,5026.8
XS Rating Curve= 0 ,0
Exp/Cntr=0.3,0.1

Type RM Length L Ch R = 1 ,7847    ,445,445,445
BEGIN DESCRIPTION:
TRIB 1 TO ROCKY CREEK 15.0
END DESCRIPTION:
XS GIS Cut Line= 3
      2555475.03     13511325.01        2556275.       13511675.
      2556625.01       13511575.
#Sta/Elev= 30
  4126.9  150.76  4170.5  150.15  4188.1  147.52  4211.5  146.05  4409.5   136.5
  4485.1  133.94  4541.6   133.1  4595.6  132.82  4764.4  131.56  4825.4  131.23
    4910  127.67  4978.2  126.48  4997.4  121.96  5002.7  121.96  5005.2  120.88
  5005.7  120.38  5015.8  120.88  5022.2  122.01  5050.8  124.13  5062.5  126.19
  5104.1  127.39  5145.7   129.8  5167.8  131.64  5176.9  133.28  5196.4  133.86
  5218.5  135.58  5236.2  137.93  5240.6  137.41  5274.4  139.45  5364.1  146.23
#Mann= 7 ,-1 , 0
  4126.9     .05       0  4541.6     .12       0  4595.6     .05       0
  4764.4     .12       0  5005.2     .05       0  5015.8     .12       0
  5236.2    .035       0
Bank Sta=5005.2,5015.8
XS Rating Curve= 0 ,0
Exp/Cntr=0.3,0.1

Type RM Length L Ch R = 1 ,7402    ,434,434,434
BEGIN DESCRIPTION:
TRIB 1 TO ROCKY CREEK 14.0
END DESCRIPTION:
XS GIS Cut Line= 3
        2555425.       13512525.        2556225.       13512075.
      2556524.99       13512125.
#Sta/Elev= 30
  4077.4   149.4  4172.1  143.07  4247.3  135.45  4290.6     133  4452.5   127.6
  4536.8  128.09  4555.1   128.8  4560.9  127.62  4599.4  127.73  4620.2  128.44
  4708.4  126.93  4744.5  127.46  4811.7   126.3  4878.9  126.72    4892  125.59
  4965.6  125.77  4981.6  122.18  4987.3  123.07  4992.4  120.32  4997.8  120.32
  5000.1  119.11  5000.6  118.61  5010.8  119.11  5015.6  122.37  5023.2  125.59
  5028.2  123.96    5046  126.02  5076.4   125.1  5106.8  126.66  5299.4  144.88
#Mann= 5 ,-1 , 0
  4077.4     .12       0  4536.8     .05       0  4599.4     .12       0
  5000.1     .05       0  5010.8     .12       0
Bank Sta=5000.1,5010.8
XS Rating Curve= 0 ,0
Exp/Cntr=0.3,0.1

Type RM Length L Ch R = 1 ,6968    ,460,460,460
BEGIN DESCRIPTION:
TRIB 1 TO ROCKY CREEK 13.0
END DESCRIPTION:
XS GIS Cut Line= 3
      2555325.04     13512774.98        2556125.       13512475.
      2556770.11     13512468.83
#Sta/Elev= 30
  4151.8  159.36  4252.3  153.58  4269.2  153.46  4332.4  147.52    4376  145.01
  4453.5  138.81  4600.3  129.73  4717.8   125.5  4813.9  124.31  4880.7  125.47
  4899.4  123.92  4905.6  122.31  4910.9  123.39  4930.5  120.68  4935.8  122.02
  4952.8  119.22  4955.3  117.72  4955.8  117.22  4966.3  117.72  4974.1  117.72
    4991  124.33  4996.4  121.94  5003.5   124.1  5008.7   124.1  5016.2  125.67
  5076.2  128.75  5216.2  133.75  5326.2  140.13  5576.2  157.35  5651.3  160.35
#Mann= 3 ,-1 , 0
  4151.8     .12       0  4955.3     .05       0  4966.3     .12       0
Bank Sta=4955.3,4966.3
XS Rating Curve= 0 ,0
Exp/Cntr=0.3,0.1

Type RM Length L Ch R = 1 ,6508    ,413,413,413
BEGIN DESCRIPTION:
Mapping XS 6057fd6e
END DESCRIPTION:
XS GIS Cut Line= 3
      2555360.63     13513069.51      2555923.08     13512864.66
      2556970.75      13512580.2
#Sta/Elev= 30
  4399.9  158.91  4585.5  154.58  4798.3  143.55  4866.8  137.89    4892  133.58
  4968.6  126.84  4978.4  123.84  4983.7  123.86  4989.9  120.54  4991.3  118.25
  4991.8  117.75  5002.4  118.25  5010.8  119.07  5016.2  121.92  5031.6  124.23
  5050.8  125.41  5114.5  125.46  5130.4  124.28  5135.6  125.31  5155.9  125.02
    5187  126.69  5352.8  125.46  5425.3  127.37  5512.9  132.97  5627.1     143
  5684.4  149.23  5839.8  158.57  5912.3  161.93  6008.5  162.78  6084.1  165.17
#Mann= 3 ,-1 , 0
  4399.9     .12       0  4991.3     .05       0  5002.4     .12       0
Bank Sta=4991.3,5002.4
XS Rating Curve= 0 ,0
Exp/Cntr=0.3,0.1

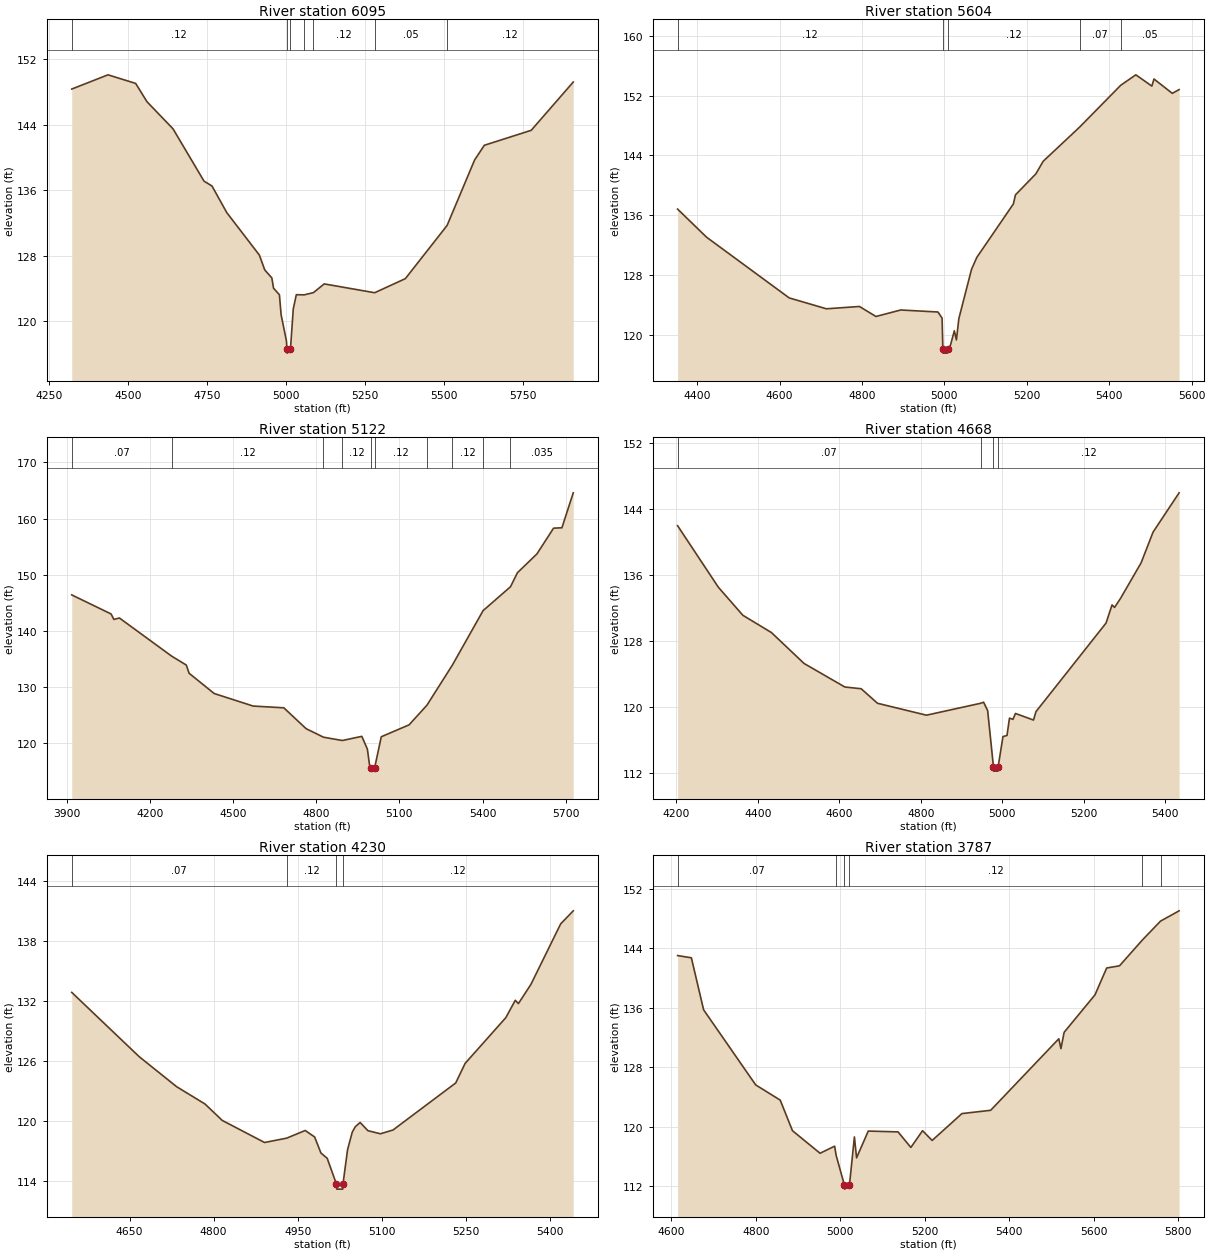
Type RM Length L Ch R = 1 ,6095    ,491,491,491
BEGIN DESCRIPTION:
Mapping XS b63bc919
END DESCRIPTION:
XS GIS Cut Line= 3
      2555489.09     13513368.13       2556082.8     13513218.83
      2556985.56     13512850.78
#Sta/Elev= 30
  4322.4  148.36  4437.2   150.1  4524.7  149.05  4560.6  146.81  4642.9   143.5
    4741  137.11  4766.3  136.51  4813.1  133.26  4916.2  128.07  4933.2  126.26
  4955.6  125.28    4961  124.03  4979.6  123.22    4985  120.78  5001.8  117.59
  5003.5  116.59    5004  116.09  5014.6  116.59  5023.4  121.48  5033.1  123.23
  5057.9  123.21  5087.1  123.48  5121.4  124.55    5281  123.47  5378.1  125.19
  5510.2  131.69  5597.4   139.7  5628.1  141.49  5776.5  143.32  5909.5  149.22
#Mann= 7 ,-1 , 0
  4322.4     .12       0  5003.5     .05       0  5014.6     .12       0
  5057.9     .07       0  5087.1     .12       0    5281     .05       0
  5510.2     .12       0
Bank Sta=5003.5,5014.6
XS Rating Curve= 0 ,0
Exp/Cntr=0.3,0.1

Type RM Length L Ch R = 1 ,5604    ,482,482,482
BEGIN DESCRIPTION:
TRIB 1 TO ROCKY CREEK 10.0
END DESCRIPTION:
XS GIS Cut Line= 3
      2555874.99       13513425.        2556525.       13513475.
      2557077.68     13513593.15
#Sta/Elev= 30
  4352.5  136.81  4422.7  133.05  4623.3  124.91  4713.6  123.45  4793.8  123.76
  4833.9  122.42  4894.1  123.29  4984.4  123.02  4994.4   122.2  4996.3  118.01
  4996.8  117.51  5007.1  117.51  5007.6  118.01  5014.7  118.57  5024.1   120.5
  5029.2  119.28  5035.1  122.14  5065.8  128.73  5078.7  130.34  5167.4   137.5
  5172.5  138.72    5222  141.53  5239.6  143.21  5327.9  147.78  5427.9   153.4
  5464.6   154.8  5503.5  153.29  5508.6  154.24    5553  152.32  5569.6  152.82
#Mann= 5 ,-1 , 0
  4352.5     .12       0  4996.3     .05       0  5007.6     .12       0
  5327.9     .07       0  5427.9     .05       0
Bank Sta=4996.3,5007.6
XS Rating Curve= 0 ,0
Exp/Cntr=0.3,0.1

Type RM Length L Ch R = 1 ,5122    ,454,454,454
BEGIN DESCRIPTION:
TRIB 1 TO ROCKY CREEK 9.0
END DESCRIPTION:
XS GIS Cut Line= 3
      2555353.76     13513822.33        2556425.       13513925.
      2557155.84     13513879.61
#Sta/Elev= 30
  3918.6  146.39  4060.5  142.99  4070.5  142.02  4090.6  142.27  4279.2  135.46
  4331.7  133.88  4341.8  132.42  4432.2  128.81  4572.8  126.57  4683.3  126.26
  4763.7  122.54  4826.3  121.02  4894.4  120.43  4964.6  121.17  4984.7  118.89
  4992.2  116.14  4999.1  115.47  4999.6  114.97  5010.4  115.47  5034.8   121.1
    5135  123.22  5199.5  126.73  5291.4   133.9  5401.9  143.59  5500.6  147.84
  5525.8  150.35  5595.9  153.69    5656  158.29  5686.1  158.36    5727  164.59
#Mann= 10 ,-1 , 0
  3918.6     .07       0  4279.2     .12       0  4826.3     .07       0
  4894.4     .12       0  4999.1     .05       0  5010.4     .12       0
  5199.5     .07       0  5291.4     .12       0  5401.9     .07       0
  5500.6    .035       0
Bank Sta=4999.1,5010.4
XS Rating Curve= 0 ,0
Exp/Cntr=0.3,0.1

Type RM Length L Ch R = 1 ,4668    ,438,438,438
BEGIN DESCRIPTION:
TRIB 1 TO ROCKY CREEK 8.0
END DESCRIPTION:
XS GIS Cut Line= 3
      2555474.98       13514275.        2556275.       13514325.
        2556525.       13514675.
#Sta/Elev= 30
  4202.9  141.95  4303.1   134.5  4363.2  131.11  4433.4  129.02  4513.5  125.28
  4613.7  122.43  4653.8  122.22  4693.9  120.46  4814.1  119.02    4947  120.46
  4954.4  120.59  4964.4  119.58  4978.7  112.75  4979.2  112.25  4989.6  112.25
  4990.1  112.75    5002  116.43  5011.9  116.57    5018  118.66  5026.6  118.52
  5032.7  119.23    5077  118.43  5083.1  119.45  5255.2  130.17  5269.9  132.37
  5276.1  132.06  5290.8  133.16  5341.2  137.45  5370.7  141.18  5434.6  145.93
#Mann= 4 ,-1 , 0
  4202.9     .07       0    4947     .12       0  4978.7     .05       0
  4990.1     .12       0
Bank Sta=4978.7,4990.1
XS Rating Curve= 0 ,0
Exp/Cntr=0.3,0.1

Type RM Length L Ch R = 1 ,4230    ,443,443,443
BEGIN DESCRIPTION:
TRIB 1 TO ROCKY CREEK 7.0
END DESCRIPTION:
XS GIS Cut Line= 3
      2555575.03     13514425.01        2555975.       13514625.
        2556375.       13514825.
#Sta/Elev= 30
  4546.9  132.86  4667.1  126.44  4734.1  123.43  4784.5  121.71  4815.2  120.07
  4890.7  117.86    4930  118.29  4963.3  119.06  4980.1  118.41  4991.3  116.81
  5002.5  116.28    5019   113.7  5019.5   113.2  5030.1   113.2  5030.6   113.7
  5038.8  117.14  5047.2   118.9  5052.8  119.45  5061.2  119.86  5075.1  119.04
  5097.5  118.73  5119.9  119.11  5231.7  123.81  5248.4  125.76  5321.1  130.34
  5337.9  132.07  5343.5  131.74  5365.8  133.66  5418.9  139.71  5441.3  141.01
#Mann= 4 ,-1 , 0
  4546.9     .07       0    4930     .12       0    5019     .05       0
  5030.6     .12       0
Bank Sta=5019,5030.6
XS Rating Curve= 0 ,0
Exp/Cntr=0.3,0.1

Type RM Length L Ch R = 1 ,3787    ,483,483,483
BEGIN DESCRIPTION:
TRIB 1 TO ROCKY CREEK 6.0
END DESCRIPTION:
XS GIS Cut Line= 3
      2555375.04     13514825.02        2555725.       13514975.
      2556525.03       13514875.
#Sta/Elev= 30
  4614.6  143.01  4647.2  142.71  4676.2  135.72  4799.5  125.63  4857.5  123.59
  4886.5  119.48  4951.8  116.45  4986.3   117.4  4989.8  116.19  5009.6  112.13
  5010.1  111.63  5021.3  112.13  5033.1  118.64  5038.2  115.83  5065.9  119.43
  5136.4  119.32  5166.7  117.23  5194.4  119.48  5217.1  118.17  5287.6  121.78
  5355.6  122.22  5516.9  131.83  5521.9  130.51  5529.5   132.7  5602.5  137.73
  5630.2  141.34  5660.5  141.63  5714.5  145.09  5757.7  147.64  5801.6  149.02
#Mann= 6 ,-1 , 0
  4614.6     .07       0  4989.8     .12       0  5009.6     .05       0
  5021.3     .12       0  5714.5     .07       0  5757.7     .12       0
Bank Sta=5009.6,5021.3
XS Rating Curve= 0 ,0
Exp/Cntr=0.3,0.1

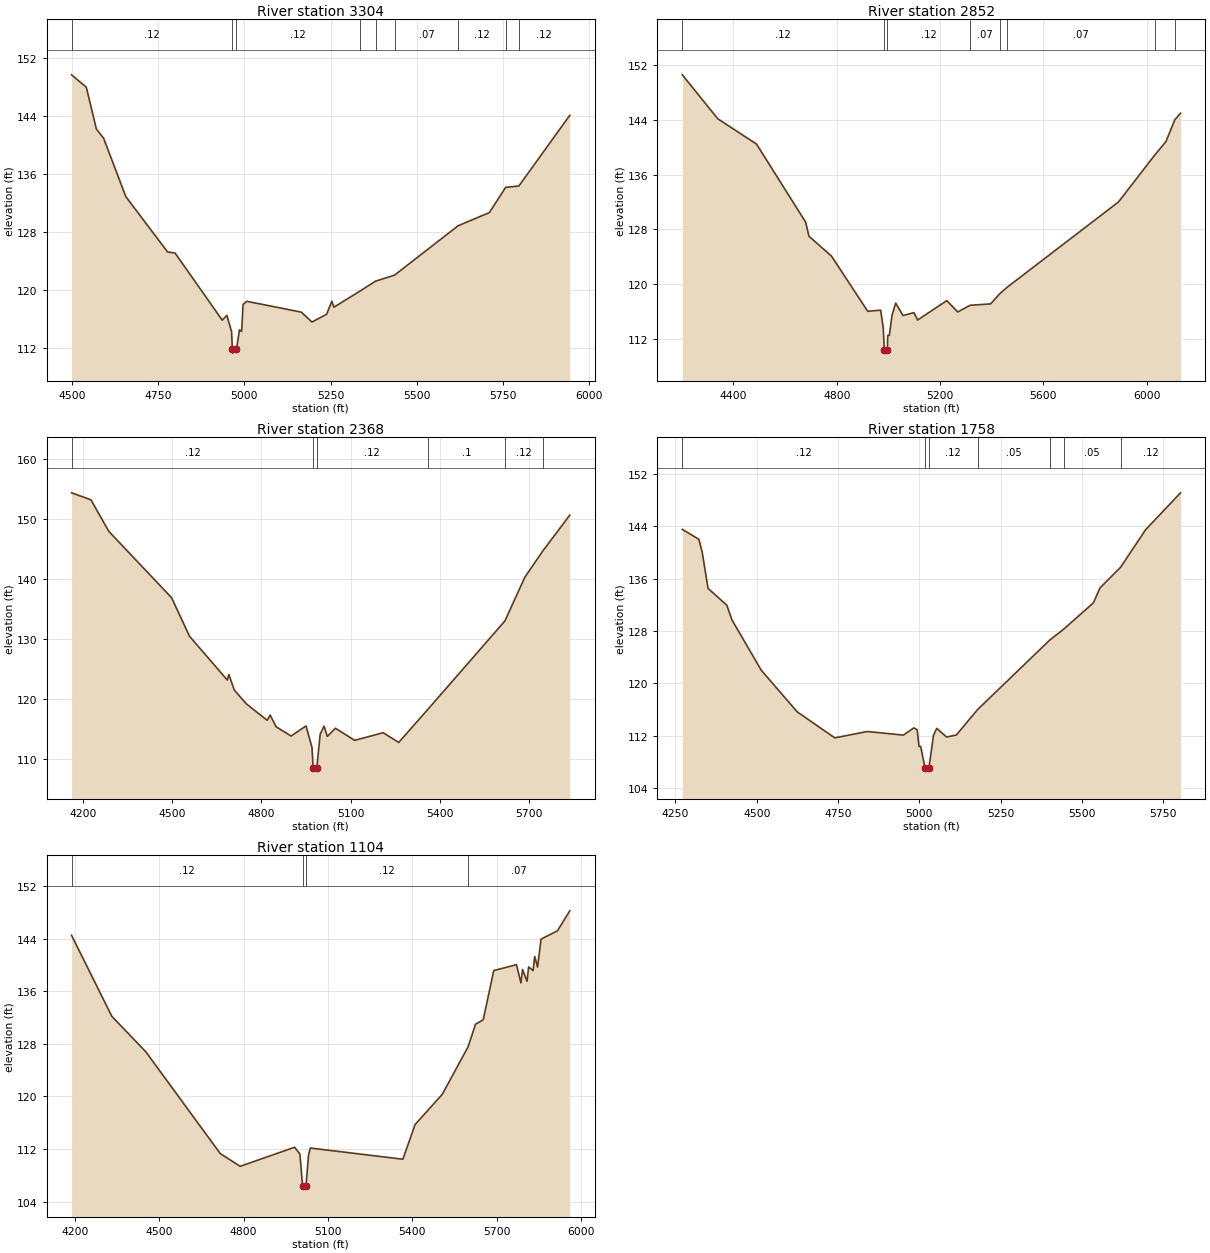
Type RM Length L Ch R = 1 ,3304    ,452,452,452
BEGIN DESCRIPTION:
TRIB 1 TO ROCKY CREEK 5.0
END DESCRIPTION:
XS GIS Cut Line= 3
      2555225.03     13515125.03        2555625.       13515425.
      2556425.04     13514924.98
#Sta/Elev= 30
  4499.6  149.65  4542.3  147.95  4571.4   142.2  4592.3  140.94  4656.8  132.89
  4777.7  125.28  4799.6  125.12    4936   115.9  4949.6  116.55  4963.1  114.33
  4965.6  111.86  4966.1  111.36  4977.3  111.86    4986  114.56  4992.3  114.35
  4996.4  118.05  5007.2  118.49  5165.2     117  5195.9  115.64  5238.4   116.7
  5253.7   118.5  5259.6  117.68  5334.3  119.87  5380.3  121.26  5435.3  122.09
  5619.4  128.88  5710.1   130.7  5757.2  134.17  5795.4  134.35    5943  144.08
#Mann= 9 ,-1 , 0
  4499.6     .12       0  4965.6     .05       0  4977.3     .12       0
  5334.3     .07       0  5380.3     .12       0  5435.3     .07       0
  5619.4     .12       0  5757.2     .07       0  5795.4     .12       0
Bank Sta=4965.6,4977.3
XS Rating Curve= 0 ,0
Exp/Cntr=0.3,0.1

Type RM Length L Ch R = 1 ,2852    ,484,484,484
BEGIN DESCRIPTION:
TRIB 1 TO ROCKY CREEK 4.0
END DESCRIPTION:
XS GIS Cut Line= 3
       2554877.7      13515863.6        2555675.       13515825.
      2556474.99     13515025.01
#Sta/Elev= 30
  4201.8  150.61  4339.3  144.18  4489.4  140.48  4679.7  129.05  4692.3  127.01
  4779.8  124.09  4919.9  116.03    4970  116.19    4980  113.67  4984.1  110.41
  4984.6  109.91    4996  110.41  4997.5  112.51  5003.6  112.51  5014.2  115.47
  5028.3  117.22  5056.6  115.41    5099  115.83  5113.2  114.75  5226.3  117.59
  5268.7  115.93  5316.8  116.91    5396  117.11  5431.6  118.61  5459.9  119.54
    5891  132.01    6032  138.89  6074.8  140.84  6109.7  144.05  6131.4     145
#Mann= 8 ,-1 , 0
  4201.8     .12       0  4984.1     .05       0    4996     .12       0
  5316.8     .07       0  5431.6     .12       0  5459.9     .07       0
    6032     .12       0  6109.7     .07       0
Bank Sta=4984.1,4996
XS Rating Curve= 0 ,0
Exp/Cntr=0.3,0.1

Type RM Length L Ch R = 1 ,2368    ,610,610,610
BEGIN DESCRIPTION:
TRIB 1 TO ROCKY CREEK 3.0
END DESCRIPTION:
XS GIS Cut Line= 3
       2554940.2     13516181.31        2555775.       13516275.
      2556575.01       13516525.
#Sta/Elev= 30
  4160.4  154.36  4225.6   153.2    4286  147.94  4497.3  136.91  4557.7   130.5
    4685  123.21  4690.1  124.14  4708.6  121.55  4748.9  119.26  4819.3  116.52
  4829.4  117.38  4849.5  115.44  4899.8   113.9  4950.1  115.58  4970.2  112.01
  4974.3  108.56  4974.8  108.06  4986.4  108.56  4997.9  114.21  5010.9  115.54
  5021.9  113.84  5049.2  115.19  5114.1  113.18    5210  114.45  5262.4  112.83
    5360   118.3  5620.3  133.06  5687.2  140.32  5747.6  144.68  5838.6  150.65
#Mann= 6 ,-1 , 0
  4160.4     .12       0  4974.3     .05       0  4986.4     .12       0
    5360      .1       0  5620.3     .12       0  5747.6     .05       0
Bank Sta=4974.3,4986.4
XS Rating Curve= 0 ,0
Exp/Cntr=0.3,0.1

Type RM Length L Ch R = 1 ,1758    ,654,654,654
BEGIN DESCRIPTION:
TRIB 1 TO ROCKY CREEK 2.0
END DESCRIPTION:
XS GIS Cut Line= 3
      2555124.97     13516624.99      2555841.67     13516758.34
      2556641.67     13516686.66
#Sta/Elev= 30
    4271  143.49  4321.9  141.98  4332.1  140.03  4350.2   134.5    4408  131.92
  4423.6   129.7  4513.6  122.04  4624.2  115.68  4739.9  111.71  4840.3  112.68
  4950.9  112.13    4983  113.23  4993.2  112.95  4999.1  110.39  5004.2  110.39
  5017.4  107.14  5017.9  106.64  5029.5  107.14  5043.5  112.09  5053.5  113.16
  5083.7  111.84  5113.8  112.15  5179.5  116.04  5401.8  126.65  5443.8  128.27
  5535.5   132.3  5555.5  134.56    5619  137.72  5696.1  143.45  5803.2  149.06
#Mann= 7 ,-1 , 0
    4271     .12       0  5017.4     .05       0  5029.5     .12       0
  5179.5     .05       0  5401.8     .12       0  5443.8     .05       0
    5619     .12       0
Bank Sta=5017.4,5029.5
XS Rating Curve= 0 ,0
Exp/Cntr=0.3,0.1

Type RM Length L Ch R = 1 ,1104    ,0,0,0
BEGIN DESCRIPTION:
TRIB 1 TO ROCKY CREEK 1.0
END DESCRIPTION:
XS GIS Cut Line= 3
      2555137.84     13516902.05       2555788.2     13517388.74
      2556623.94     13516915.97
#Sta/Elev= 30
  4187.7   144.5  4331.1  132.17    4452  126.78  4716.7   111.3  4787.5  109.36
  4981.3  112.26    5000  111.23  5009.6  106.39  5010.1  105.89  5021.7  106.39
  5030.8  111.08  5037.3  112.14  5366.4  110.44  5409.9  115.72  5506.4   120.3
  5598.5  127.55  5624.8  130.98  5652.2  131.65  5689.7  139.14  5770.5  140.04
  5786.4  137.26  5792.2   139.3  5808.1  137.51  5813.8   139.7  5829.7  139.13
  5835.5  141.29  5845.6  139.67    5858  143.93  5916.3  145.19  5960.2  148.23
#Mann= 4 ,-1 , 0
  4187.7     .12       0  5009.6     .05       0  5021.7     .12       0
  5598.5     .07       0
Bank Sta=5009.6,5021.7
XS Rating Curve= 0 ,0
Exp/Cntr=0.3,0.1

Chan Stop Cuts=-1
Use User Specified Reach Order=0
Composite Channel Slope=5