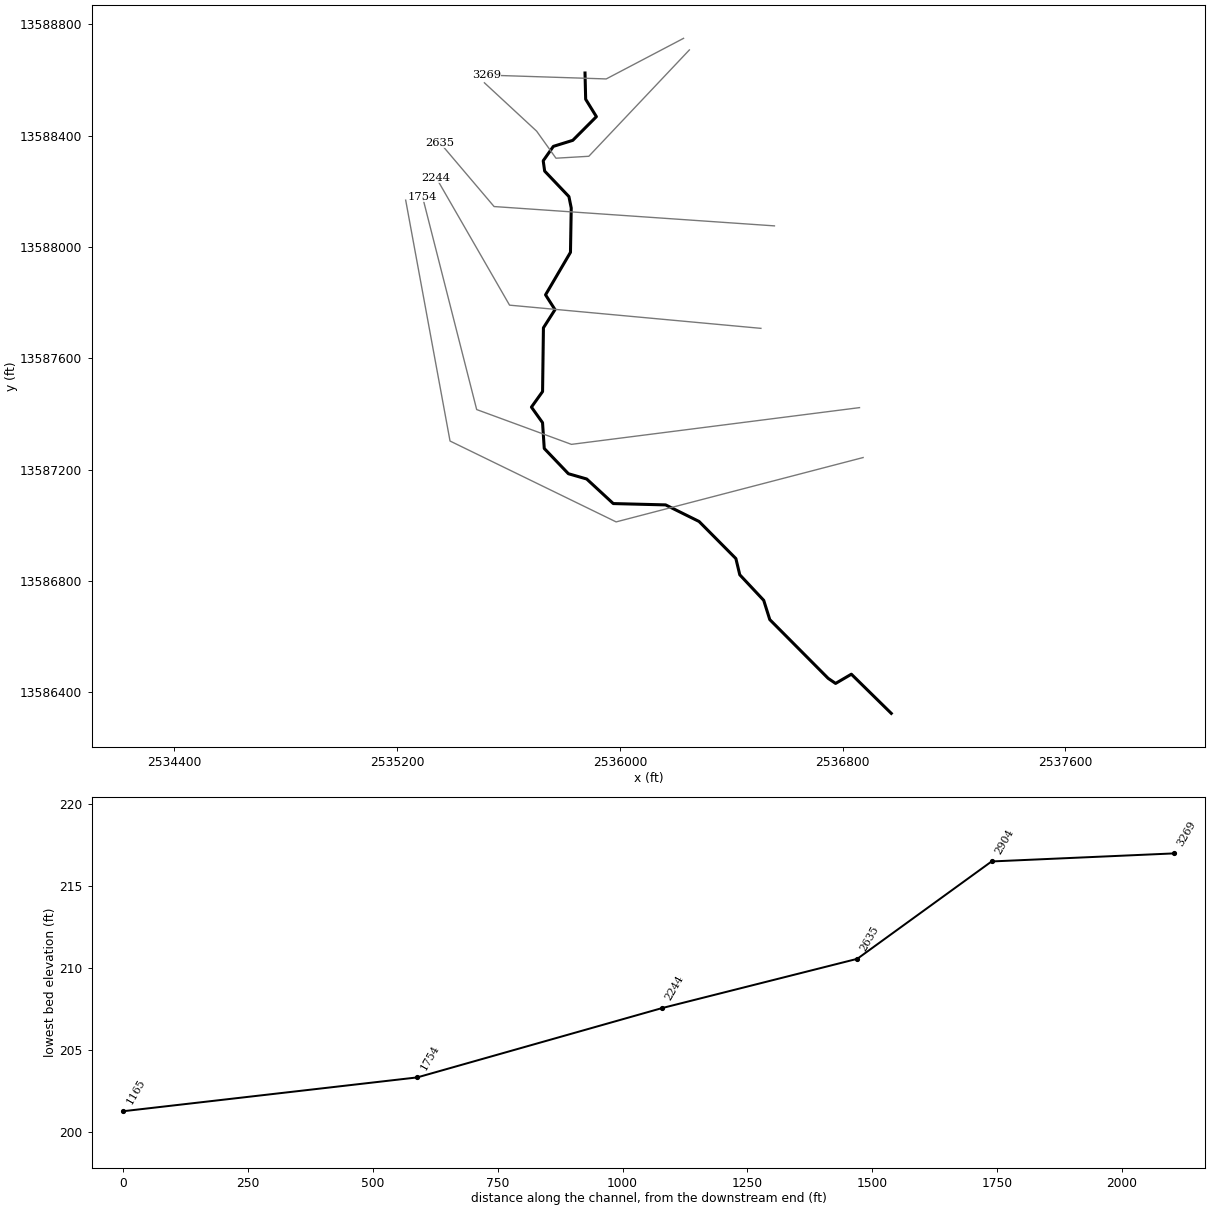
--- TRIB 1 TO SANDY FORK.prj (project) ---

Proj Title=TRIB 1 TO SANDY FORK Base Level Engineering
Current Plan=p01
Default Exp/Contr=0.3,0.1
English Units
Geom File=g01
Flow File=f01
Plan File=p01
BEGIN DESCRIPTION:
TRIB 1 TO SANDY FORK
END DESCRIPTION:

--- TRIB 1 TO SANDY FORK.p01 (plan) ---

Plan Title=Multiple Run
Short Identifier=Multiple
Geom File=g01
Flow File=f01
Subcritical Flow
K Sum by GR= 0
Std Step Tol= 0.01
Critical Tol= 0.01
Num of Std Step Trials= 20
Max Error Tol= 0.3
Flow Tol Ratio= 0.001
Split Flow NTrial= 30
Split Flow Tol= 0.02
Split Flow Ratio= 0.02
Log Output Level= 0
Friction Slope Method= 1
Unsteady Friction Slope Method= 2
Unsteady Bridges Friction Slope Method= 1
Parabolic Critical Depth
Global Vel Dist=  1 , 1 , 1
Global Log Level= 0
CheckData=True
Encroach Param= -1, 0, 0, 0
BEGIN DESCRIPTION:
Multiple Run
END DESCRIPTION:

--- TRIB 1 TO SANDY FORK.f01 (steady flow) ---

Flow Title=Multiple
Number of Profiles=7
Profile Names=10-year,25-year,50-year,1pct_min,100-year,1pct_plu,500-year
River Rch & RM= TRIB 1 TO SANDY ,Reach-1,3269
     342     532     698     445     889    1773    1422
Boundary for River Rch & Prof#=TRIB 1 TO SANDY ,Reach-1,1
Up Type=0
Dn Type=3
Dn Slope=0.005
Boundary for River Rch & Prof#=TRIB 1 TO SANDY ,Reach-1,2
Up Type=0
Dn Type=3
Dn Slope=0.005
Boundary for River Rch & Prof#=TRIB 1 TO SANDY ,Reach-1,3
Up Type=0
Dn Type=3
Dn Slope=0.005
Boundary for River Rch & Prof#=TRIB 1 TO SANDY ,Reach-1,4
Up Type=0
Dn Type=3
Dn Slope=0.005
Boundary for River Rch & Prof#=TRIB 1 TO SANDY ,Reach-1,5
Up Type=0
Dn Type=3
Dn Slope=0.005
Boundary for River Rch & Prof#=TRIB 1 TO SANDY ,Reach-1,6
Up Type=0
Dn Type=3
Dn Slope=0.005
Boundary for River Rch & Prof#=TRIB 1 TO SANDY ,Reach-1,7
Up Type=0
Dn Type=3
Dn Slope=0.005

--- TRIB 1 TO SANDY FORK.g01 (geometry) ---

Geom Title=Existing Conditions

River Reach=TRIB 1 TO SANDY ,Reach-1
Reach XY= 30
      2535875.00     13588625.00      2535877.35     13588530.77
      2535915.91     13588468.25      2535831.06     13588383.17
      2535761.29     13588361.51      2535724.84     13588309.76
      2535730.07     13588272.74      2535817.17     13588181.19
      2535825.49     13588140.20      2535822.76     13587980.93
      2535733.24     13587828.23      2535767.20     13587775.10
      2535725.65     13587709.84      2535722.54     13587480.86
      2535682.56     13587425.00      2535722.44     13587369.10
      2535728.60     13587276.49      2535815.30     13587185.77
      2535881.04     13587166.82      2535976.47     13587078.55
      2536164.50     13587073.80      2536284.68     13587014.24
      2536416.84     13586881.05      2536430.87     13586822.72
      2536516.82     13586731.04      2536538.63     13586661.79
      2536748.33     13586450.77      2536775.00     13586432.56
      2536831.67     13586465.71      2536975.00     13586325.00

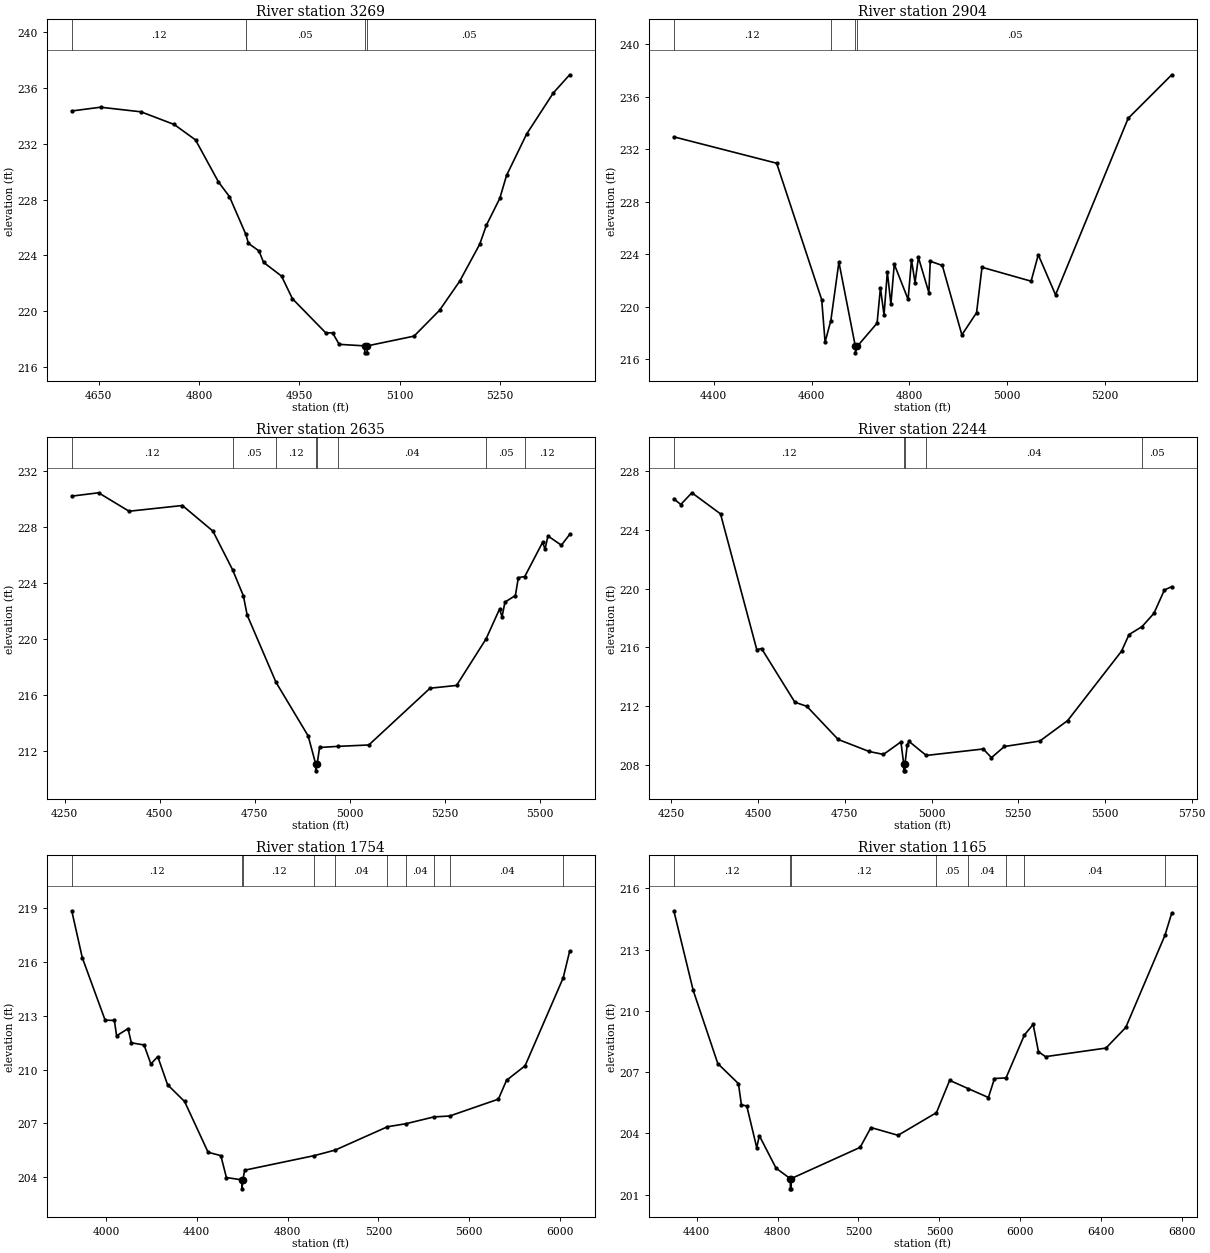
Type RM Length L Ch R = 1,3269,365,365,365
BEGIN DESCRIPTION:
LGII3954
END DESCRIPTION:
XS GIS Cut Line= 3
      2536228.93     13588749.53      2535951.18     13588603.71
      2535520.60     13588617.60
#Sta/Elev= 30
  4609.9  234.36  4652.9  234.63  4713.4  234.30  4763.1  233.39  4795.0  232.28
  4829.3  229.26  4845.7  228.21  4870.2  225.50  4874.1  224.85  4889.8  224.31
  4896.7  223.49  4923.6  222.50  4939.8  220.88  4989.8  218.42  4999.8  218.43
  5009.8  217.60  5047.8  217.49  5048.1  216.99  5051.6  216.99  5051.8  217.49
  5121.7  218.19  5159.9  220.05  5189.9  222.13  5219.9  224.79  5229.9  226.16
  5249.9  228.08  5260.0  229.73  5290.0  232.70  5330.0  235.66  5354.4  236.96
#Mann=4,-1,0
  4609.9    0.12       0  4870.2    0.05       0  5047.8    0.05       0
  5051.8    0.05       0
Bank Sta=5047.8,5051.8
Exp/Cntr=0.3,0.1

Type RM Length L Ch R = 1,2904,269,269,269
BEGIN DESCRIPTION:
LGII3953
END DESCRIPTION:
XS GIS Cut Line= 5
      2536249.81     13588707.90      2535888.68     13588325.94
      2535770.62     13588318.99      2535701.18     13588416.21
      2535513.69     13588589.81
#Sta/Elev= 30
  4318.2  232.96  4528.6  230.95  4620.8  220.55  4627.7  217.32  4639.5  218.96
  4656.0  223.41  4689.6  217.00  4689.9  216.50  4693.6  217.00  4734.1  218.76
  4741.0  221.45  4748.3  219.38  4755.1  222.66  4762.4  220.21  4769.3  223.26
  4797.6  220.57  4804.5  223.58  4811.8  221.86  4818.7  223.77  4840.1  221.09
  4842.9  223.48  4867.6  223.16  4907.6  217.87  4937.7  219.56  4948.8  223.02
  5049.3  221.96  5064.0  223.97  5099.3  220.92  5247.9  234.37  5337.1  237.69
#Mann=4,-1,0
  4318.2    0.12       0  4639.5    0.05       0  4689.6    0.05       0
  4693.6    0.05       0
Bank Sta=4689.6,4693.6
Exp/Cntr=0.3,0.1

Type RM Length L Ch R = 1,2635,391,391,391
BEGIN DESCRIPTION:
LGII3952
END DESCRIPTION:
XS GIS Cut Line= 3
      2536555.38     13588075.93      2535548.40     13588145.38
      2535353.97     13588374.54
#Sta/Elev= 30
  4268.3  230.22  4338.8  230.46  4419.0  229.14  4559.4  229.55  4639.6  227.72
  4691.5  224.95  4719.8  223.09  4729.8  221.71  4805.9  216.89  4890.2  213.07
  4910.0  211.07  4910.2  210.57  4914.0  211.07  4920.2  212.24  4967.9  212.32
  5049.8  212.42  5210.9  216.48  5280.7  216.68  5358.3  220.01  5393.7  222.14
  5400.3  221.59  5408.0  222.64  5435.4  223.11  5443.2  224.39  5460.1  224.47
  5506.9  226.91  5513.4  226.43  5521.1  227.37  5556.3  226.71  5578.2  227.48
#Mann=8,-1,0
  4268.3    0.12       0  4691.5    0.05       0  4805.9    0.12       0
  4910.0    0.04       0  4914.0    0.12       0  4967.9    0.04       0
  5358.3    0.05       0  5460.1    0.12       0
Bank Sta=4910,4914
Exp/Cntr=0.3,0.1

Type RM Length L Ch R = 1,2244,490,490,490
BEGIN DESCRIPTION:
LGII3951
END DESCRIPTION:
XS GIS Cut Line= 3
      2536506.78     13587707.88      2535603.96     13587791.21
      2535340.08     13588249.52
#Sta/Elev= 30
  4257.1  226.12  4277.1  225.73  4309.1  226.53  4391.7  225.09  4496.3  215.83
  4510.0  215.91  4606.0  212.25  4640.5  211.97  4730.9  209.71  4820.2  208.89
  4861.4  208.69  4911.7  209.54  4919.7  208.07  4919.9  207.57  4923.4  207.57
  4923.7  208.07  4929.8  209.31  4934.9  209.58  4984.8  208.62  5149.1  209.06
  5172.8  208.47  5210.1  209.23  5312.2  209.60  5392.6  211.00  5547.8  215.73
  5569.4  216.86  5607.2  217.41  5641.2  218.31  5671.4  219.90  5692.6  220.13
#Mann=5,-1,0
  4257.1    0.12       0  4919.7    0.04       0  4923.7    0.12       0
  4984.8    0.04       0  5607.2    0.05       0
Bank Sta=4919.7,4923.7
Exp/Cntr=0.3,0.1

Type RM Length L Ch R = 1,1754,589,589,589
BEGIN DESCRIPTION:
LGII3950
END DESCRIPTION:
XS GIS Cut Line= 4
      2536860.89     13587423.16      2535826.18     13587291.21
      2535485.90     13587416.21      2535291.47     13588180.05
#Sta/Elev= 30
  3849.1  218.85  3895.4  216.24  3996.2  212.75  4036.9  212.74  4046.6  211.88
  4097.0  212.28  4111.7  211.49  4167.6  211.37  4197.8  210.31  4228.0  210.72
  4271.4  209.15  4346.2  208.22  4449.8  205.39  4505.9  205.20  4530.5  203.98
  4599.0  203.85  4599.3  203.35  4603.0  203.85  4611.1  204.39  4917.1  205.20
  5009.6  205.51  5240.0  206.81  5321.4  206.98  5445.2  207.36  5514.3  207.41
  5728.9  208.35  5764.7  209.40  5846.5  210.21  6014.3  215.11  6042.9  216.60
#Mann=10,-1,0
  3849.1    0.12       0  4599.0    0.05       0  4603.0    0.12       0
  4917.1    0.05       0  5009.6    0.04       0  5240.0    0.03       0
  5321.4    0.04       0  5445.2    0.03       0  5514.3    0.04       0
  6014.3    0.05       0
Bank Sta=4599,4603
Exp/Cntr=0.3,0.1

Type RM Length L Ch R = 1,1165,0,0,0
BEGIN DESCRIPTION:
LGII3950a
END DESCRIPTION:
XS GIS Cut Line= 4
      2536873.87     13587243.88      2535986.76     13587012.73
      2535390.18     13587303.21      2535230.89     13588168.40
#Sta/Elev= 30
  4287.7  214.90  4383.5  211.00  4505.0  207.42  4606.9  206.44  4621.4  205.41
  4648.2  205.34  4697.2  203.31  4710.2  203.89  4792.9  202.30  4863.2  201.79
  4863.5  201.29  4867.0  201.29  4867.2  201.79  5208.2  203.32  5261.6  204.29
  5395.5  203.91  5585.2  205.02  5650.4  206.60  5741.0  206.20  5841.9  205.76
  5871.9  206.69  5928.9  206.72  6019.7  208.82  6063.0  209.34  6089.1  208.00
  6124.0  207.76  6422.6  208.18  6520.5  209.19  6714.1  213.70  6747.7  214.79
#Mann=8,-1,0
  4287.7    0.12       0  4863.2    0.05       0  4867.2    0.12       0
  5585.2    0.05       0  5741.0    0.04       0  5928.9    0.03       0
  6019.7    0.04       0  6714.1    0.05       0
Bank Sta=4863.2,4867.2
Exp/Cntr=0.3,0.1

Chan Stop Cuts=-1