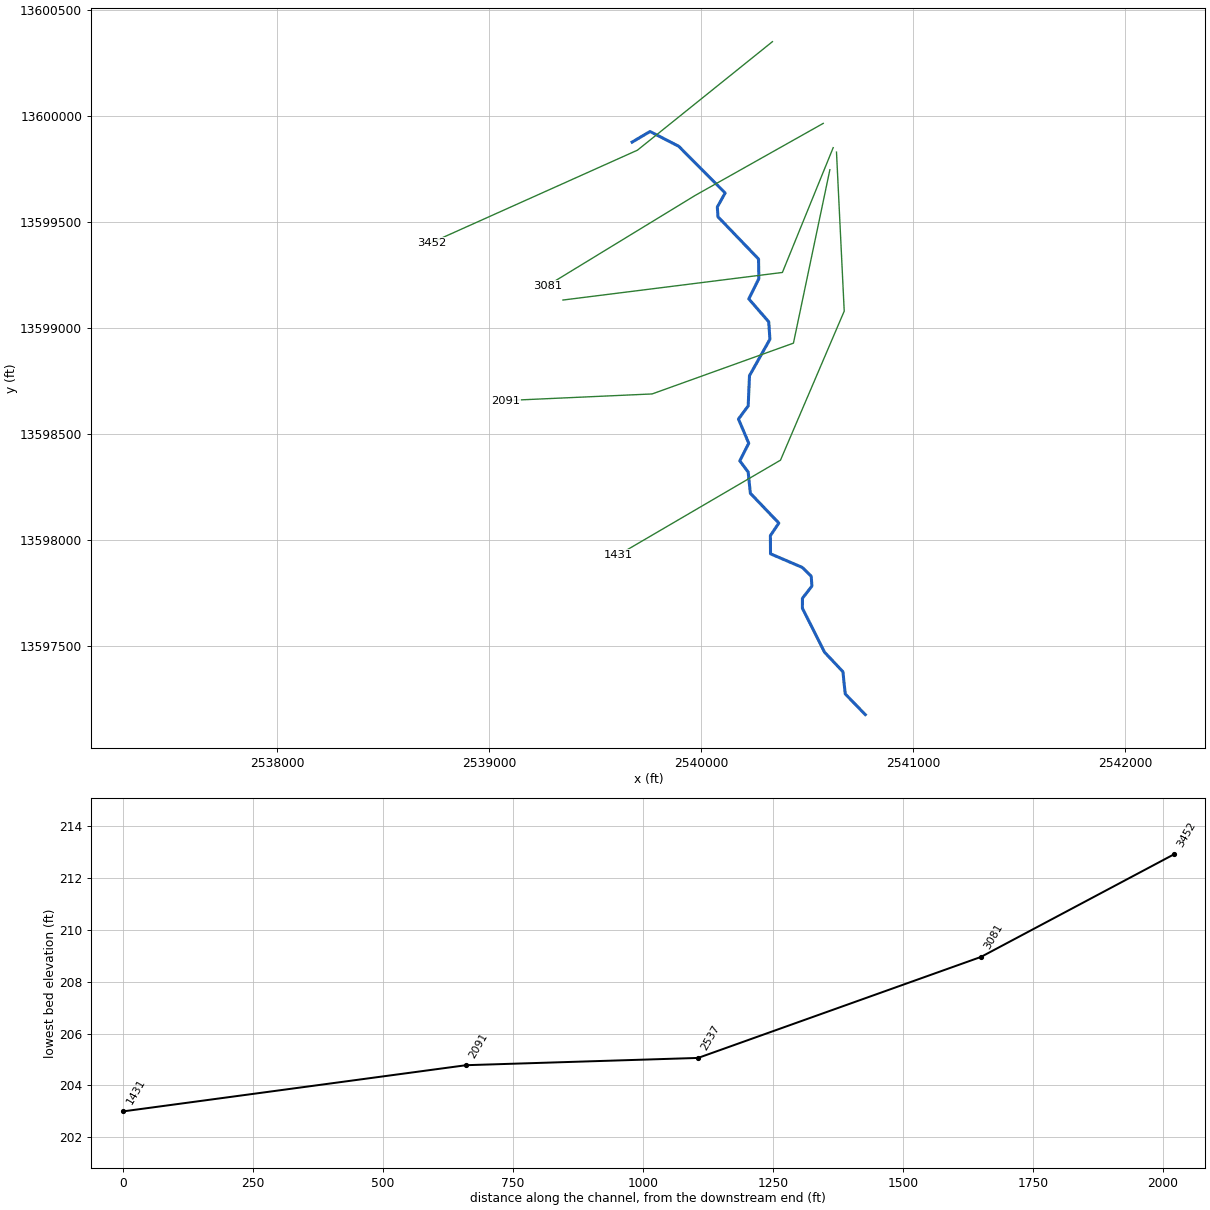
--- TRIB 10 TO IRISH CREEK.prj (project) ---

Proj Title=TRIB 10 TO IRISH CREEK Base Level Engineering
Current Plan=p01
Default Exp/Contr=0.3,0.1
English Units
Geom File=g01
Flow File=f01
Plan File=p01
BEGIN DESCRIPTION:
TRIB 10 TO IRISH CREEK
END DESCRIPTION:

--- TRIB 10 TO IRISH CREEK.p01 (plan) ---

Plan Title=Multiple Run
Short Identifier=Multiple
Geom File=g01
Flow File=f01
Subcritical Flow
K Sum by GR= 0
Std Step Tol= 0.01
Critical Tol= 0.01
Num of Std Step Trials= 20
Max Error Tol= 0.3
Flow Tol Ratio= 0.001
Split Flow NTrial= 30
Split Flow Tol= 0.02
Split Flow Ratio= 0.02
Log Output Level= 0
Friction Slope Method= 1
Unsteady Friction Slope Method= 2
Unsteady Bridges Friction Slope Method= 1
Parabolic Critical Depth
Global Vel Dist=  1 , 1 , 1
Global Log Level= 0
CheckData=True
Encroach Param= -1, 0, 0, 0
BEGIN DESCRIPTION:
Multiple Run
END DESCRIPTION:

--- TRIB 10 TO IRISH CREEK.f01 (steady flow) ---

Flow Title=Multiple
Number of Profiles=7
Profile Names=10-year,25-year,50-year,1pct_min,100-year,1pct_plu,500-year
River Rch & RM= TRIB 10 TO IRISH,Reach-1,3452
     572     912    1216     786    1569    3130    2584
Boundary for River Rch & Prof#=TRIB 10 TO IRISH,Reach-1,1
Up Type=0
Dn Type=3
Dn Slope=0.005
Boundary for River Rch & Prof#=TRIB 10 TO IRISH,Reach-1,2
Up Type=0
Dn Type=3
Dn Slope=0.005
Boundary for River Rch & Prof#=TRIB 10 TO IRISH,Reach-1,3
Up Type=0
Dn Type=3
Dn Slope=0.005
Boundary for River Rch & Prof#=TRIB 10 TO IRISH,Reach-1,4
Up Type=0
Dn Type=3
Dn Slope=0.005
Boundary for River Rch & Prof#=TRIB 10 TO IRISH,Reach-1,5
Up Type=0
Dn Type=3
Dn Slope=0.005
Boundary for River Rch & Prof#=TRIB 10 TO IRISH,Reach-1,6
Up Type=0
Dn Type=3
Dn Slope=0.005
Boundary for River Rch & Prof#=TRIB 10 TO IRISH,Reach-1,7
Up Type=0
Dn Type=3
Dn Slope=0.005

--- TRIB 10 TO IRISH CREEK.g01 (geometry) ---

Geom Title=Existing Conditions

River Reach=TRIB 10 TO IRISH,Reach-1
Reach XY= 30
      2539675.00     13599875.00      2539759.68     13599925.05
      2539895.09     13599855.22      2540113.89     13599635.05
      2540076.99     13599568.95      2540080.12     13599522.71
      2540271.54     13599323.50      2540272.81     13599230.97
      2540225.61     13599135.62      2540319.59     13599027.42
      2540325.11     13598945.10      2540228.76     13598773.44
      2540222.70     13598630.93      2540176.83     13598568.88
      2540225.20     13598454.80      2540183.10     13598371.71
      2540222.45     13598319.10      2540232.86     13598218.83
      2540367.20     13598078.42      2540327.33     13598019.02
      2540327.97     13597933.32      2540477.62     13597869.27
      2540520.01     13597827.55      2540523.21     13597781.16
      2540478.40     13597723.28      2540478.34     13597676.72
      2540583.16     13597468.95      2540669.46     13597377.42
      2540680.46     13597272.55      2540775.00     13597175.00

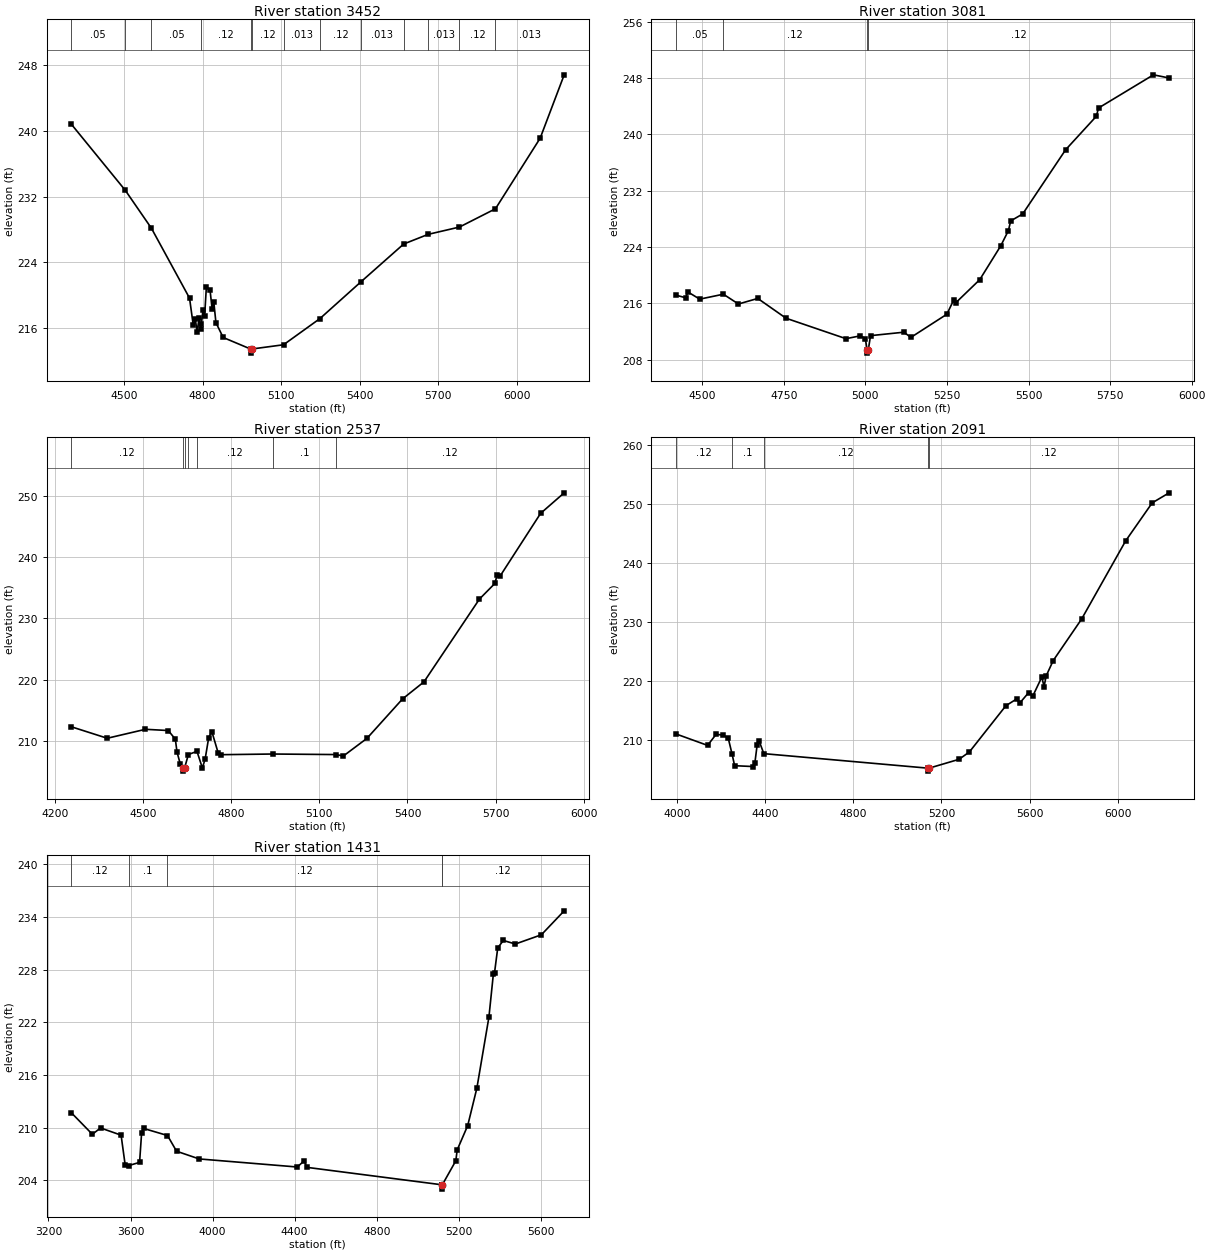
Type RM Length L Ch R = 1,3452,371,371,371
BEGIN DESCRIPTION:
TRIB 10 TO IRISH CREEK 3.0
END DESCRIPTION:
XS GIS Cut Line= 3
      2540337.11     13600348.77      2539700.26     13599836.99
      2538728.87     13599401.37
#Sta/Elev= 30
  4298.6  240.85  4505.1  232.76  4604.9  228.13  4750.3  219.61  4764.6  216.28
  4772.6  217.03  4779.0  215.45  4787.0  217.24  4793.4  215.83  4795.6  216.46
  4801.4  218.13  4807.8  217.40  4814.5  220.95  4828.6  220.58  4836.6  218.25
  4843.0  219.11  4851.0  216.62  4878.6  214.81  4983.4  213.40  4983.6  212.90
  4987.4  213.40  5109.0  213.92  5248.2  217.12  5404.2  221.59  5567.6  226.21
  5661.0  227.39  5780.5  228.28  5917.9  230.51  6088.5  239.12  6180.2  246.85
#Mann=13,-1,0
  4298.6    0.05       0  4505.1    0.12       0  4604.9    0.05       0
  4795.6    0.12       0  4983.4    0.05       0  4987.4    0.12       0
  5109.0   0.013       0  5248.2    0.12       0  5404.2   0.013       0
  5567.6    0.12       0  5661.0   0.013       0  5780.5    0.12       0
  5917.9   0.013       0
Bank Sta=4983.4,4987.4
Exp/Cntr=0.3,0.1

Type RM Length L Ch R = 1,3081,544,544,544
BEGIN DESCRIPTION:
TRIB 10 TO IRISH CREEK 2.0
END DESCRIPTION:
XS GIS Cut Line= 3
      2540576.74     13599963.39      2539975.00     13599625.00
      2539274.60     13599197.73
#Sta/Elev= 30
  4420.1  217.17  4449.1  216.81  4456.5  217.62  4492.4  216.61  4564.9  217.31
  4611.0  215.92  4670.3  216.71  4757.0  213.90  4940.6  211.00  4984.3  211.40
  4999.9  211.02  5005.2  209.45  5005.5  208.95  5009.2  209.45  5015.8  211.43
  5118.2  211.92  5139.5  211.18  5249.8  214.47  5271.1  216.52  5277.0  216.09
  5350.5  219.37  5415.0  224.18  5438.4  226.34  5445.4  227.71  5482.2  228.70
  5613.8  237.81  5707.9  242.56  5714.5  243.73  5882.9  248.44  5930.9  247.99
#Mann=4,-1,0
  4420.1    0.05       0  4564.9    0.12       0  5005.2    0.05       0
  5009.2    0.12       0
Bank Sta=5005.2,5009.2
Exp/Cntr=0.3,0.1

Type RM Length L Ch R = 1,2537,446,446,446
BEGIN DESCRIPTION:
Mapping XS bcf0d18a
END DESCRIPTION:
XS GIS Cut Line= 3
      2540623.59     13599848.77      2540384.01     13599260.25
      2539348.77     13599130.19
#Sta/Elev= 30
  4254.9  212.30  4377.7  210.42  4507.9  211.88  4585.5  211.68  4609.5  210.27
  4615.3  208.17  4626.1  206.27  4637.0  205.56  4637.2  205.06  4641.0  205.56
  4653.9  207.76  4683.2  208.29  4701.6  205.57  4711.2  207.07  4723.2  210.54
  4734.0  211.49  4755.6  208.00  4764.7  207.74  4941.9  207.85  5157.2  207.76
  5181.6  207.52  5262.2  210.41  5383.2  216.83  5456.3  219.62  5645.2  233.12
  5697.6  235.66  5705.7  237.10  5715.8  236.89  5853.4  247.09  5933.7  250.44
#Mann=7,-1,0
  4254.9    0.12       0  4637.0    0.05       0  4641.0    0.12       0
  4653.9     0.1       0  4683.2    0.12       0  4941.9     0.1       0
  5157.2    0.12       0
Bank Sta=4637,4641
Exp/Cntr=0.3,0.1

Type RM Length L Ch R = 1,2091,660,660,660
BEGIN DESCRIPTION:
Mapping XS 22db9e3a
END DESCRIPTION:
XS GIS Cut Line= 4
      2540607.96     13599744.60      2540436.10     13598926.92
      2539769.43     13598687.33      2539078.39     13598656.16
#Sta/Elev= 30
  3996.6  211.07  4139.2  209.14  4178.1  211.02  4210.8  210.87  4233.1  210.34
  4250.3  207.67  4261.9  205.70  4343.6  205.56  4353.8  206.19  4364.1  209.23
  4372.4  209.95  4394.3  207.74  5139.5  205.28  5139.7  204.78  5143.5  205.28
  5279.6  206.78  5326.6  208.03  5492.1  215.86  5540.3  216.99  5555.0  216.31
  5595.0  218.07  5615.1  217.58  5655.1  220.72  5665.1  219.10  5675.1  220.94
  5706.7  223.51  5835.3  230.53  6035.5  243.80  6155.6  250.22  6232.3  251.92
#Mann=5,-1,0
  3996.6    0.12       0  4250.3     0.1       0  4394.3    0.12       0
  5139.5    0.05       0  5143.5    0.12       0
Bank Sta=5139.5,5143.5
Exp/Cntr=0.3,0.1

Type RM Length L Ch R = 1,1431,0,0,0
BEGIN DESCRIPTION:
TRIB 10 TO IRISH CREEK 1.0
END DESCRIPTION:
XS GIS Cut Line= 4
      2540639.22     13599827.94      2540675.68     13599077.96
      2540375.00     13598375.00      2539608.97     13597927.50
#Sta/Elev= 30
  3310.9  211.72  3414.0  209.25  3454.0  209.97  3554.1  209.15  3574.2  205.71
  3590.8  205.68  3644.2  206.05  3654.2  209.45  3664.3  209.91  3780.2  209.11
  3824.4  207.32  3934.6  206.44  4413.0  205.52  4445.7  206.22  4459.8  205.48
  5115.7  203.50  5116.0  203.00  5119.7  203.50  5185.4  206.23  5192.1  207.47
  5243.3  210.24  5288.0  214.51  5346.7  222.60  5368.2  227.48  5374.0  227.65
  5389.7  230.49  5417.0  231.33  5475.7  230.93  5602.3  231.98  5713.5  234.71
#Mann=5,-1,0
  3310.9    0.12       0  3590.8     0.1       0  3780.2    0.12       0
  5115.7    0.05       0  5119.7    0.12       0
Bank Sta=5115.7,5119.7
Exp/Cntr=0.3,0.1

Chan Stop Cuts=-1