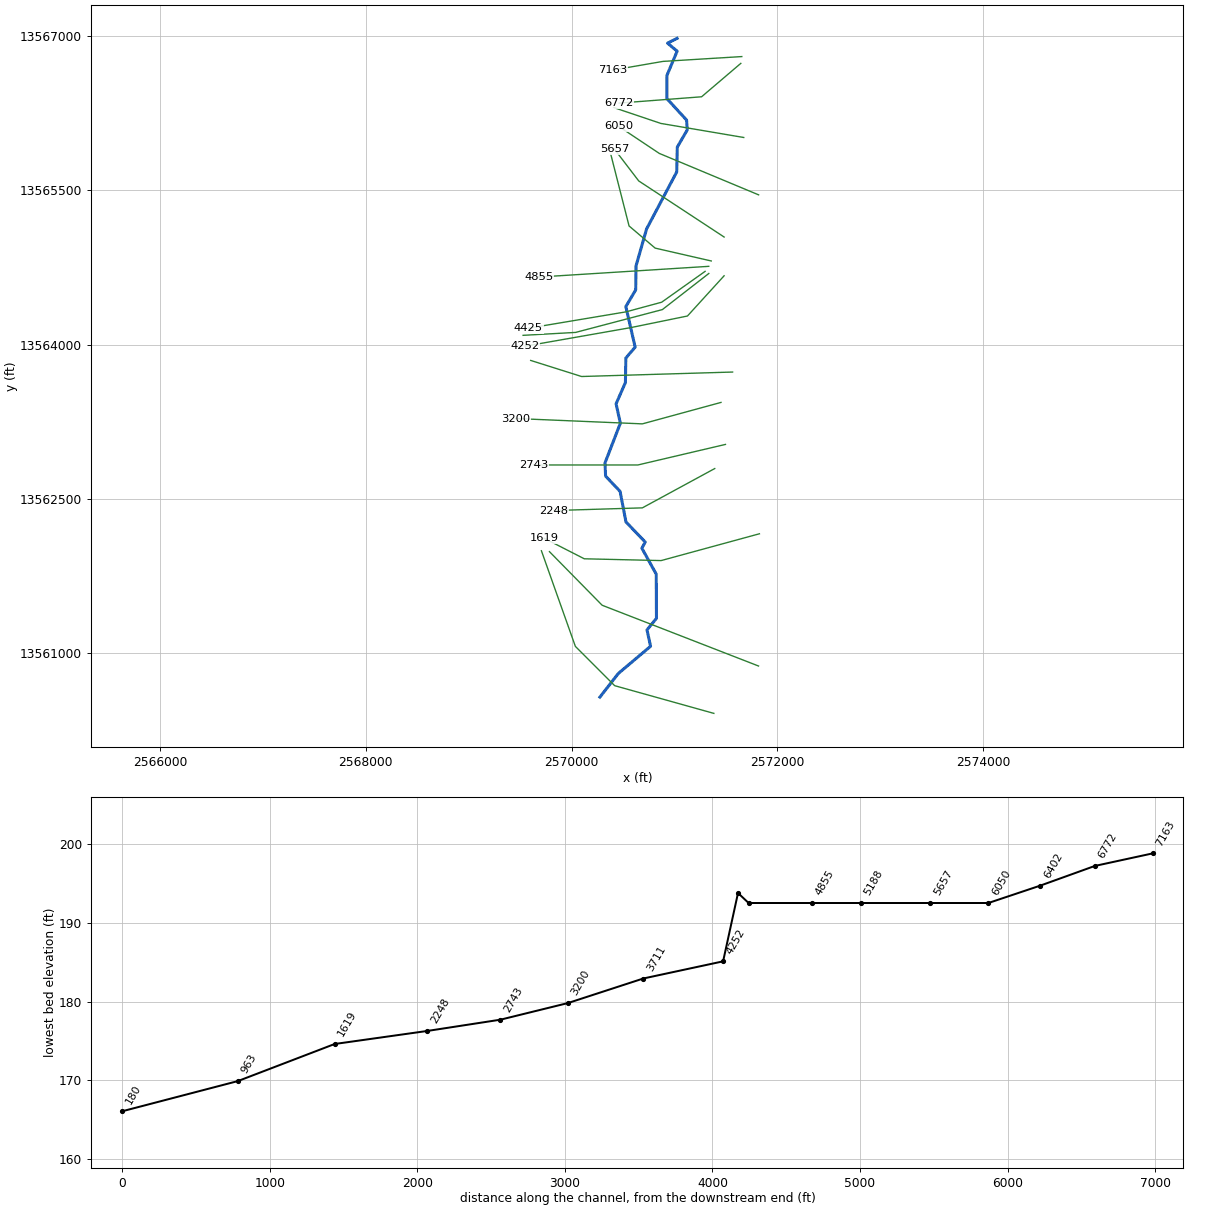
--- TRIB 10 TO PRICE CREEK.prj (project) ---

Proj Title=TRIB 10 TO PRICE CREEK Base Level Engineering
Current Plan=p01
Default Exp/Contr=0.3,0.1
English Units
Geom File=g01
Flow File=f01
Plan File=p01
BEGIN DESCRIPTION:
TRIB 10 TO PRICE CREEK
END DESCRIPTION:

--- TRIB 10 TO PRICE CREEK.p01 (plan) ---

Plan Title=Multiple Run
Short Identifier=Multiple
Geom File=g01
Flow File=f01
Subcritical Flow
K Sum by GR= 0
Std Step Tol= 0.01
Critical Tol= 0.01
Num of Std Step Trials= 20
Max Error Tol= 0.3
Flow Tol Ratio= 0.001
Split Flow NTrial= 30
Split Flow Tol= 0.02
Split Flow Ratio= 0.02
Log Output Level= 0
Friction Slope Method= 1
Unsteady Friction Slope Method= 2
Unsteady Bridges Friction Slope Method= 1
Parabolic Critical Depth
Global Vel Dist=  1 , 1 , 1
Global Log Level= 0
CheckData=True
Encroach Param= -1, 0, 0, 0
BEGIN DESCRIPTION:
Multiple Run
END DESCRIPTION:

--- TRIB 10 TO PRICE CREEK.f01 (steady flow) ---

Flow Title=Multiple
Number of Profiles=7
Profile Names=10-year,25-year,50-year,1pct_min,100-year,1pct_plu,500-year
River Rch & RM= TRIB 10 TO PRICE,Reach-1,7163
     436     677     889     566    1129    2253    1801
River Rch & RM= TRIB 10 TO PRICE,Reach-1,5657
     448     697     913     581    1160    2314    1847
River Rch & RM= TRIB 10 TO PRICE,Reach-1,3200
     693    1107    1479     956    1908    3807    3143
River Rch & RM= TRIB 10 TO PRICE,Reach-1,1619
     946    1538    2078    1359    2711    5409    4565
Boundary for River Rch & Prof#=TRIB 10 TO PRICE,Reach-1,1
Up Type=0
Dn Type=3
Dn Slope=0.005
Boundary for River Rch & Prof#=TRIB 10 TO PRICE,Reach-1,2
Up Type=0
Dn Type=3
Dn Slope=0.005
Boundary for River Rch & Prof#=TRIB 10 TO PRICE,Reach-1,3
Up Type=0
Dn Type=3
Dn Slope=0.005
Boundary for River Rch & Prof#=TRIB 10 TO PRICE,Reach-1,4
Up Type=0
Dn Type=3
Dn Slope=0.005
Boundary for River Rch & Prof#=TRIB 10 TO PRICE,Reach-1,5
Up Type=0
Dn Type=3
Dn Slope=0.005
Boundary for River Rch & Prof#=TRIB 10 TO PRICE,Reach-1,6
Up Type=0
Dn Type=3
Dn Slope=0.005
Boundary for River Rch & Prof#=TRIB 10 TO PRICE,Reach-1,7
Up Type=0
Dn Type=3
Dn Slope=0.005

--- TRIB 10 TO PRICE CREEK.g01 (geometry) ---

Geom Title=Existing Conditions

River Reach=TRIB 10 TO PRICE,Reach-1
Reach XY= 30
      2571025.00     13566975.00      2570932.22     13566928.33
      2571025.51     13566850.12      2570926.22     13566614.50
      2570925.50     13566390.20      2571117.25     13566181.19
      2571123.92     13566085.55      2571027.24     13565919.07
      2571021.25     13565676.55      2570728.83     13565123.42
      2570626.22     13564764.50      2570622.76     13564530.93
      2570527.23     13564369.07      2570617.64     13563974.92
      2570527.07     13563869.15      2570523.11     13563630.78
      2570432.51     13563425.01      2570473.80     13563235.51
      2570324.77     13562850.07      2570330.45     13562722.55
      2570471.39     13562573.50      2570528.54     13562276.47
      2570715.70     13562081.67      2570683.02     13562021.67
      2570822.74     13561769.06      2570824.61     13561340.16
      2570732.81     13561228.41      2570767.24     13561068.83
      2570454.61     13560805.16      2570275.00     13560575.00

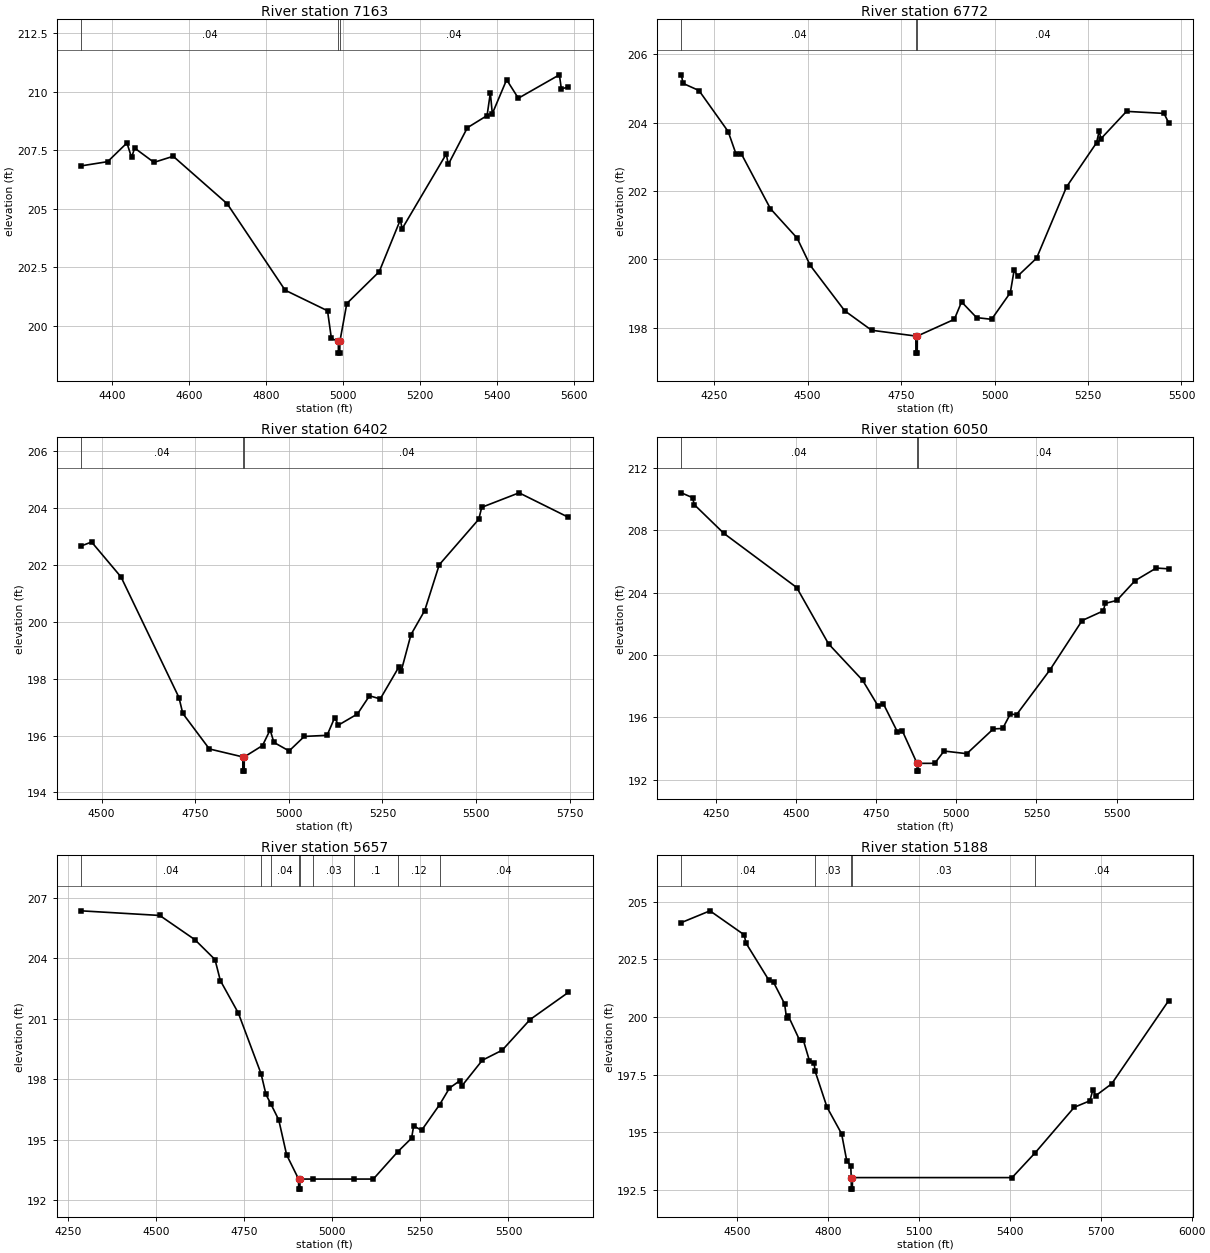
Type RM Length L Ch R = 1,7163,391,391,391
BEGIN DESCRIPTION:
LGII3179
END DESCRIPTION:
XS GIS Cut Line= 3
      2571653.70     13566797.83      2570886.47     13566750.76
      2570397.02     13566666.04
#Sta/Elev= 30
  4320.4  206.84  4389.2  207.02  4439.3  207.82  4451.3  207.20  4459.4  207.60
  4509.5  206.99  4559.5  207.25  4699.8  205.22  4850.1  201.53  4960.3  200.65
  4970.3  199.47  4988.4  199.34  4988.6  198.84  4992.1  198.84  4992.4  199.34
  5010.4  200.96  5094.6  202.32  5149.3  204.53  5154.3  204.16  5268.8  207.35
  5273.9  206.90  5323.5  208.47  5374.7  208.99  5383.2  209.96  5388.3  209.07
  5425.5  210.52  5455.9  209.73  5562.5  210.73  5567.6  210.13  5585.8  210.21
#Mann=3,-1,0
  4320.4    0.04       0  4988.4    0.04       0  4992.4    0.04       0
Bank Sta=4988.4,4992.4
Exp/Cntr=0.3,0.1

Type RM Length L Ch R = 1,6772,370,370,370
BEGIN DESCRIPTION:
LGII3178
END DESCRIPTION:
XS GIS Cut Line= 3
      2571644.25     13566731.91      2571263.02     13566407.16
      2570462.85     13566345.97
#Sta/Elev= 30
  4162.3  205.40  4166.6  205.15  4209.4  204.94  4287.4  203.74  4308.2  203.09
  4322.5  203.09  4400.5  201.48  4471.8  200.62  4507.0  199.82  4599.2  198.49
  4671.1  197.92  4789.5  197.75  4789.7  197.25  4793.2  197.25  4793.5  197.75
  4892.5  198.24  4911.8  198.75  4952.0  198.29  4992.1  198.24  5042.2  199.02
  5052.3  199.67  5062.3  199.51  5112.4  200.03  5192.7  202.12  5272.9  203.41
  5279.8  203.75  5284.8  203.53  5353.1  204.33  5453.4  204.27  5465.6  204.00
#Mann=3,-1,0
  4162.3    0.04       0  4789.5    0.04       0  4793.5    0.04       0
Bank Sta=4789.5,4793.5
Exp/Cntr=0.3,0.1

Type RM Length L Ch R = 1,6402,352,352,352
BEGIN DESCRIPTION:
LGII3177
END DESCRIPTION:
XS GIS Cut Line= 3
      2571672.55     13566011.78      2570867.65     13566148.29
      2570408.20     13566303.00
#Sta/Elev= 30
  4445.2  202.67  4473.1  202.81  4551.7  201.58  4706.4  197.34  4716.6  196.78
  4787.6  195.53  4876.9  195.25  4877.1  194.75  4880.6  194.75  4880.9  195.25
  4929.6  195.65  4949.9  196.20  4960.0  195.76  5000.6  195.46  5041.1  195.97
  5102.0  196.01  5122.3  196.63  5132.4  196.37  5183.1  196.76  5215.3  197.40
  5244.0  197.29  5294.5  198.43  5299.8  198.26  5326.0  199.55  5362.8  200.40
  5401.6  202.01  5507.1  203.61  5515.0  204.03  5614.8  204.54  5746.4  203.68
#Mann=3,-1,0
  4445.2    0.04       0  4876.9    0.04       0  4880.9    0.04       0
Bank Sta=4876.9,4880.9
Exp/Cntr=0.3,0.1

Type RM Length L Ch R = 1,6050,393,393,393
BEGIN DESCRIPTION:
LGII3176
END DESCRIPTION:
XS GIS Cut Line= 3
      2571817.16     13565454.46      2570851.87     13565857.24
      2570456.85     13566120.58
#Sta/Elev= 30
  4141.7  210.41  4176.5  210.10  4182.0  209.65  4274.1  207.81  4501.6  204.33
  4601.1  200.71  4707.5  198.37  4754.8  196.75  4772.5  196.85  4815.8  195.07
  4831.7  195.11  4877.3  193.04  4877.6  192.54  4881.1  192.54  4881.3  193.04
  4932.4  193.04  4961.6  193.83  5032.6  193.66  5115.4  195.25  5144.6  195.28
  5168.4  196.21  5187.7  196.16  5292.1  199.04  5392.6  202.21  5458.7  202.83
  5464.7  203.31  5500.7  203.50  5557.8  204.77  5623.9  205.58  5662.4  205.53
#Mann=3,-1,0
  4141.7    0.04       0  4877.3    0.04       0  4881.3    0.04       0
Bank Sta=4877.3,4881.3
Exp/Cntr=0.3,0.1

Type RM Length L Ch R = 1,5657,469,469,469
BEGIN DESCRIPTION:
LGII3175
END DESCRIPTION:
XS GIS Cut Line= 3
      2571482.08     13565044.74      2570652.21     13565589.88
      2570416.11     13565898.90
#Sta/Elev= 30
  4288.0  206.36  4511.0  206.13  4610.4  204.93  4667.6  203.94  4682.7  202.90
  4733.9  201.28  4798.3  198.27  4812.2  197.24  4826.0  196.77  4848.4  195.98
  4870.8  194.24  4904.7  193.04  4904.9  192.54  4908.4  192.54  4908.7  193.04
  4945.8  193.04  5060.7  193.04  5116.6  193.04  5185.6  194.39  5225.1  195.07
  5231.1  195.68  5253.6  195.46  5304.9  196.74  5332.7  197.56  5361.7  197.92
  5368.0  197.67  5425.8  198.94  5482.3  199.44  5561.2  200.96  5669.8  202.31
#Mann=9,-1,0
  4288.0    0.04       0  4798.3    0.03       0  4826.0    0.04       0
  4904.7    0.03       0  4908.7    0.04       0  4945.8    0.03       0
  5060.7     0.1       0  5185.6    0.12       0  5304.9    0.04       0
Bank Sta=4904.7,4908.7
Exp/Cntr=0.3,0.1

Type RM Length L Ch R = 1,5188,333,333,333
BEGIN DESCRIPTION:
LGII3174
END DESCRIPTION:
XS GIS Cut Line= 4
      2571357.04     13564812.11      2570811.94     13564937.10
      2570558.46     13565152.38      2570381.37     13565846.85
#Sta/Elev= 30
  4315.3  204.10  4409.7  204.61  4522.6  203.57  4528.6  203.21  4604.7  201.59
  4619.6  201.51  4656.0  200.58  4662.4  199.97  4667.6  200.07  4705.3  199.01
  4717.5  199.02  4738.0  198.11  4753.4  198.02  4756.7  197.66  4796.2  196.09
  4844.3  194.94  4861.1  193.78  4874.5  193.54  4876.1  193.04  4876.3  192.54
  4879.8  192.54  4880.1  193.04  5407.1  193.04  5482.9  194.11  5612.3  196.09
  5663.9  196.37  5674.2  196.86  5683.0  196.59  5736.1  197.11  5923.8  200.71
#Mann=5,-1,0
  4315.3    0.04       0  4756.7    0.03       0  4876.1    0.03       0
  4880.1    0.03       0  5482.9    0.04       0
Bank Sta=4876.1,4880.1
Exp/Cntr=0.3,0.1

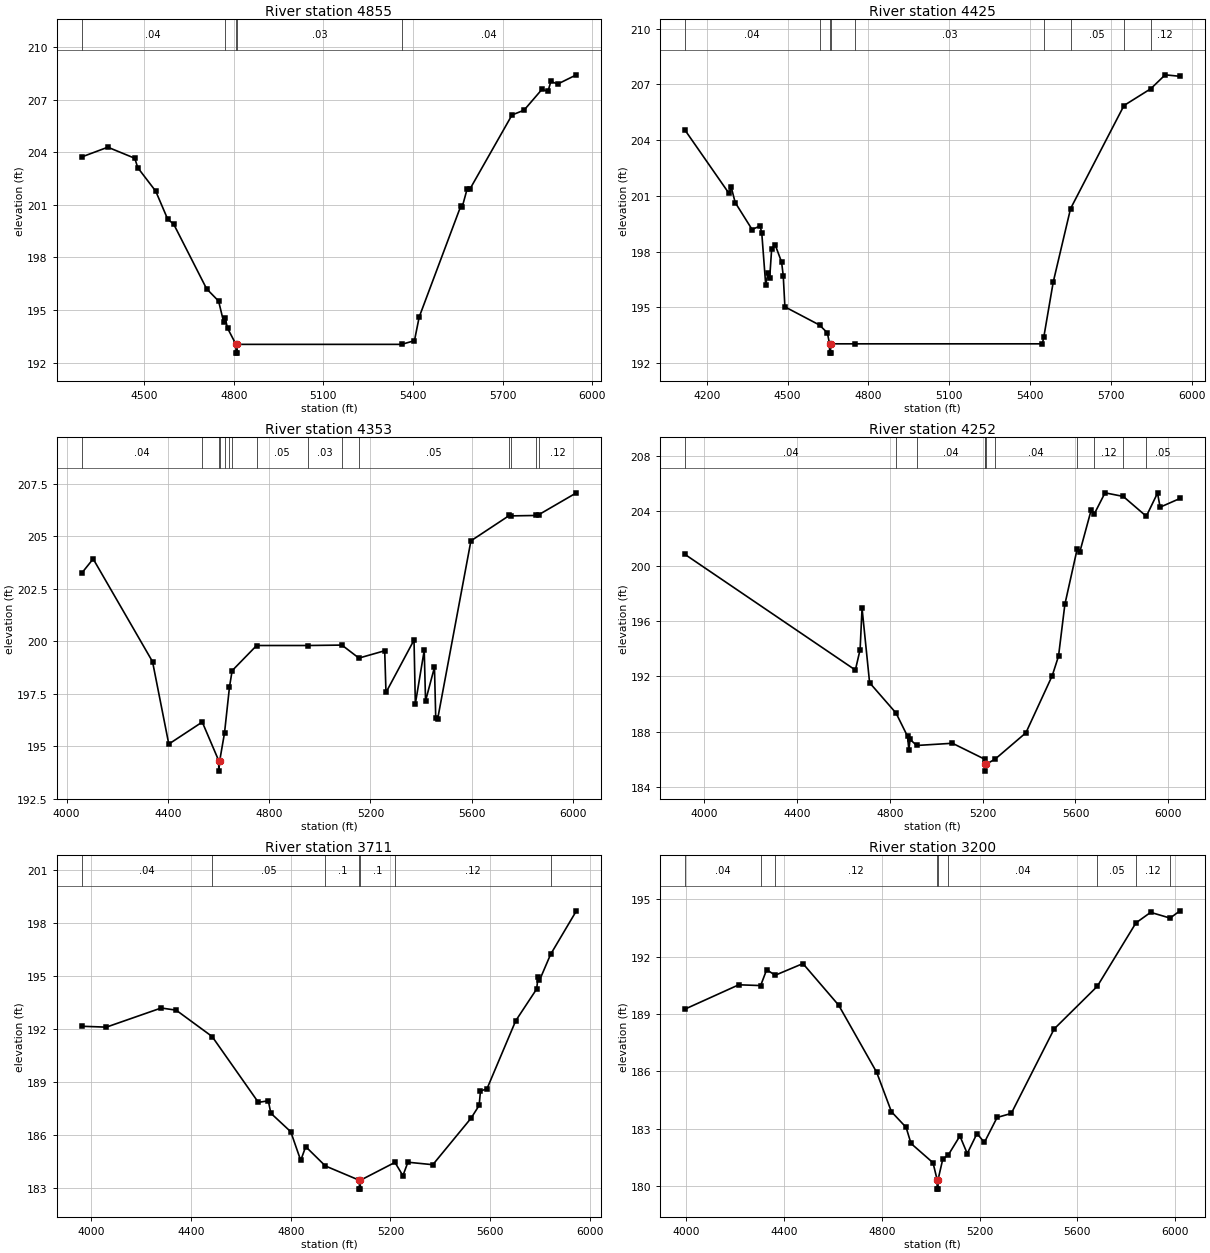
Type RM Length L Ch R = 1,4855,430,430,430
BEGIN DESCRIPTION:
LGII3188
END DESCRIPTION:
XS GIS Cut Line= 2
      2571332.78     13564760.02      2569679.96     13564655.85
#Sta/Elev= 30
  4290.5  203.73  4378.5  204.29  4468.6  203.66  4478.7  203.12  4538.8  201.78
  4578.9  200.18  4598.9  199.90  4709.1  196.21  4749.2  195.51  4766.0  194.32
  4770.7  194.57  4779.2  193.96  4807.3  193.04  4807.6  192.54  4811.1  192.54
  4811.3  193.04  5361.7  193.04  5404.6  193.25  5420.5  194.60  5559.2  200.91
  5564.2  200.86  5580.8  201.90  5590.9  201.92  5731.1  206.13  5771.2  206.40
  5831.3  207.59  5851.4  207.48  5861.4  208.05  5883.5  207.89  5946.6  208.42
#Mann=5,-1,0
  4290.5    0.04       0  4770.7    0.03       0  4807.3    0.03       0
  4811.3    0.03       0  5361.7    0.04       0
Bank Sta=4807.3,4811.3
Exp/Cntr=0.3,0.1

Type RM Length L Ch R = 1,4425,72,72,72
BEGIN DESCRIPTION:
Mapping XS caf3dae3
END DESCRIPTION:
XS GIS Cut Line= 4
      2571297.13     13564711.03      2570875.29     13564411.57
      2570528.94     13564317.82      2569581.00     13564158.97
#Sta/Elev= 30
  4119.4  204.53  4282.1  201.14  4290.8  201.46  4305.5  200.64  4368.2  199.19
  4397.8  199.38  4404.1  199.01  4418.7  196.22  4427.3  196.84  4433.4  196.56
  4440.9  198.15  4454.3  198.35  4477.7  197.44  4483.9  196.70  4490.0  195.03
  4618.6  194.05  4647.7  193.63  4655.7  193.04  4656.0  192.54  4659.5  192.54
  4659.7  193.04  4751.9  193.04  5445.7  193.04  5451.2  193.40  5486.2  196.36
  5550.5  200.31  5749.0  205.86  5848.3  206.76  5901.9  207.51  5956.7  207.43
#Mann=9,-1,0
  4119.4    0.04       0  4618.6    0.05       0  4655.7    0.03       0
  4659.7    0.05       0  4751.9    0.03       0  5451.2    0.04       0
  5550.5    0.05       0  5749.0    0.04       0  5848.3    0.12       0
Bank Sta=4655.7,4659.7
Exp/Cntr=0.3,0.1

Type RM Length L Ch R = 1,4353,101,101,101
BEGIN DESCRIPTION:
LGII3187
END DESCRIPTION:
XS GIS Cut Line= 4
      2571333.21     13564690.49      2570881.97     13564339.81
      2570038.82     13564118.06      2569529.11     13564089.74
#Sta/Elev= 30
  4059.3  203.24  4105.2  203.93  4339.6  199.03  4403.8  195.10  4535.9  196.15
  4600.9  194.31  4601.2  193.81  4604.9  194.31  4623.8  195.63  4643.4  197.82
  4653.9  198.60  4750.6  199.80  4952.5  199.80  5087.3  199.82  5154.4  199.20
  5256.2  199.55  5261.3  197.56  5372.0  200.06  5377.2  197.02  5412.3  199.57
  5417.5  197.16  5452.7  198.76  5457.8  196.32  5465.2  196.29  5596.6  204.79
  5748.2  206.00  5753.5  205.98  5851.8  206.00  5863.5  206.03  6013.1  207.08
#Mann=15,-1,0
  4059.3    0.04       0  4535.9    0.05       0  4600.9    0.03       0
  4604.9    0.05       0  4623.8    0.04       0  4643.4    0.05       0
  4653.9    0.03       0  4750.6    0.05       0  4952.5    0.03       0
  5087.3    0.04       0  5154.4    0.05       0  5748.2    0.12       0
  5753.5    0.04       0  5851.8    0.05       0  5863.5    0.12       0
Bank Sta=4600.9,4604.9
Exp/Cntr=0.3,0.1

Type RM Length L Ch R = 1,4252,541,541,541
BEGIN DESCRIPTION:
Mapping XS 3ad567f1
END DESCRIPTION:
XS GIS Cut Line= 4
      2571481.80     13564668.18      2571125.87     13564277.53
      2570574.66     13564164.68      2569549.90     13563984.51
#Sta/Elev= 30
  3918.3  200.84  4651.8  192.46  4672.2  193.94  4680.6  196.94  4713.1  191.54
  4827.0  189.34  4876.4  187.66  4882.3  186.68  4887.4  187.43  4915.9  186.99
  5070.0  187.15  5209.4  185.99  5211.5  185.63  5211.7  185.13  5215.5  185.63
  5255.2  186.02  5386.4  187.91  5500.0  192.06  5526.9  193.47  5554.3  197.23
  5606.9  201.21  5618.7  201.03  5667.8  204.08  5680.6  203.77  5727.2  205.31
  5805.6  205.05  5905.0  203.61  5953.3  205.29  5964.5  204.27  6049.9  204.90
#Mann=11,-1,0
  3918.3    0.04       0  4827.0    0.05       0  4915.9    0.04       0
  5209.4    0.05       0  5211.5    0.04       0  5215.5    0.05       0
  5255.2    0.04       0  5606.9    0.05       0  5680.6    0.12       0
  5805.6    0.04       0  5905.0    0.05       0
Bank Sta=5211.5,5215.5
Exp/Cntr=0.3,0.1

Type RM Length L Ch R = 1,3711,511,511,511
BEGIN DESCRIPTION:
LGII3186
END DESCRIPTION:
XS GIS Cut Line= 3
      2571564.51     13563733.11      2570097.53     13563689.70
      2569602.74     13563845.95
#Sta/Elev= 30
  3960.2  192.15  4059.8  192.10  4279.9  193.18  4339.9  193.06  4484.4  191.57
  4670.0  187.85  4710.0  187.94  4720.0  187.24  4800.1  186.19  4840.1  184.57
  4860.1  185.35  4938.9  184.26  5075.4  183.45  5075.7  182.95  5079.2  182.95
  5079.4  183.45  5218.3  184.46  5250.3  183.71  5270.3  184.47  5370.3  184.33
  5524.0  186.96  5556.3  187.68  5561.6  188.49  5587.8  188.62  5703.1  192.46
  5787.0  194.25  5793.2  194.95  5798.4  194.74  5843.1  196.21  5946.7  198.67
#Mann=7,-1,0
  3960.2    0.04       0  4484.4    0.05       0  4938.9     0.1       0
  5075.4    0.05       0  5079.4     0.1       0  5218.3    0.12       0
  5843.1    0.05       0
Bank Sta=5075.4,5079.4
Exp/Cntr=0.3,0.1

Type RM Length L Ch R = 1,3200,457,457,457
BEGIN DESCRIPTION:
LGII3173
END DESCRIPTION:
XS GIS Cut Line= 3
      2571451.67     13563437.96      2570687.80     13563229.63
      2569455.17     13563281.72
#Sta/Elev= 30
  3994.5  189.25  4214.3  190.52  4303.9  190.48  4328.4  191.31  4363.4  191.02
  4476.9  191.63  4623.3  189.45  4778.8  185.94  4839.1  183.88  4899.2  183.06
  4919.2  182.22  5009.3  181.21  5026.0  180.33  5026.3  179.83  5029.8  179.83
  5030.0  180.33  5049.3  181.40  5071.9  181.62  5119.4  182.61  5149.4  181.69
  5189.4  182.74  5219.5  182.27  5271.6  183.58  5329.6  183.79  5505.1  188.21
  5681.6  190.44  5840.0  193.76  5900.1  194.31  5979.8  194.01  6020.0  194.39
#Mann=9,-1,0
  3994.5    0.04       0  4303.9    0.05       0  4363.4    0.12       0
  5026.0    0.05       0  5030.0    0.12       0  5071.9    0.04       0
  5681.6    0.05       0  5840.0    0.12       0  5979.8    0.05       0
Bank Sta=5026,5030
Exp/Cntr=0.3,0.1

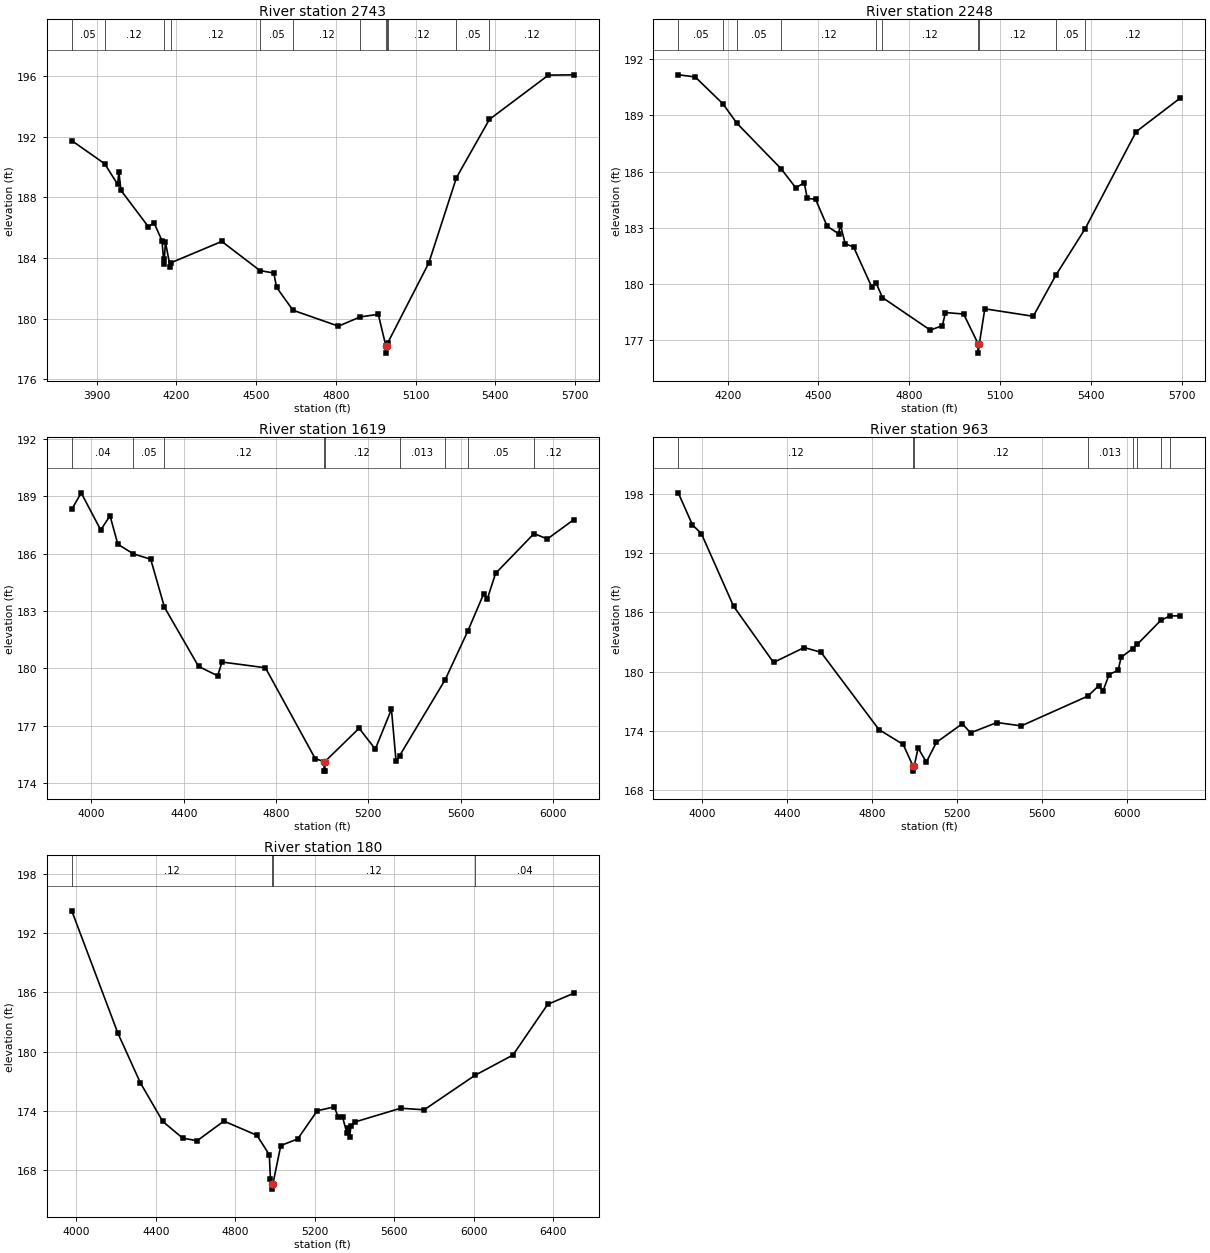
Type RM Length L Ch R = 1,2743,495,495,495
BEGIN DESCRIPTION:
LGII3172
END DESCRIPTION:
XS GIS Cut Line= 3
      2571495.13     13563029.99      2570644.40     13562830.33
      2569629.34     13562830.33
#Sta/Elev= 30
  3806.3  191.74  3930.3  190.21  3978.6  188.86  3983.8  189.65  3991.3  188.46
  4094.0  186.07  4116.2  186.30  4145.4  185.15  4151.7  183.93  4153.5  183.58
  4158.6  185.06  4176.2  183.43  4180.6  183.69  4370.7  185.09  4514.0  183.17
  4566.5  183.00  4576.8  182.06  4638.5  180.55  4809.5  179.50  4891.7  180.11
  4959.5  180.28  4987.5  178.22  4987.8  177.72  4991.5  178.22  4994.9  178.39
  5149.5  183.67  5253.6  189.30  5377.6  193.14  5599.5  196.06  5695.2  196.08
#Mann=12,-1,0
  3806.3    0.05       0  3930.3    0.12       0  4151.7    0.05       0
  4180.6    0.12       0  4514.0    0.05       0  4638.5    0.12       0
  4891.7    0.05       0  4987.5    0.05       0  4991.5    0.05       0
  4994.9    0.12       0  5253.6    0.05       0  5377.6    0.12       0
Bank Sta=4987.5,4991.5
Exp/Cntr=0.3,0.1

Type RM Length L Ch R = 1,2248,629,629,629
BEGIN DESCRIPTION:
LGII3171
END DESCRIPTION:
XS GIS Cut Line= 3
      2571390.94     13562795.61      2570687.80     13562413.66
      2569829.18     13562387.64
#Sta/Elev= 30
  4036.5  191.17  4092.3  191.06  4184.8  189.61  4229.8  188.59  4376.8  186.14
  4424.9  185.13  4452.9  185.40  4462.9  184.57  4490.5  184.51  4528.5  183.08
  4566.5  182.67  4572.2  183.16  4588.4  182.13  4615.9  181.97  4675.8  179.83
  4689.8  180.06  4711.4  179.26  4869.5  177.52  4909.5  177.76  4919.5  178.46
  4979.6  178.38  5027.6  176.79  5027.8  176.29  5031.6  176.79  5049.6  178.66
  5209.7  178.26  5284.2  180.45  5381.5  182.95  5549.8  188.13  5695.7  189.93
#Mann=10,-1,0
  4036.5    0.05       0  4184.8    0.12       0  4229.8    0.05       0
  4376.8    0.12       0  4689.8    0.05       0  4711.4    0.12       0
  5027.6    0.05       0  5031.6    0.12       0  5284.2    0.05       0
  5381.5    0.12       0
Bank Sta=5027.6,5031.6
Exp/Cntr=0.3,0.1

Type RM Length L Ch R = 1,1619,656,656,656
BEGIN DESCRIPTION:
LGII3170
END DESCRIPTION:
XS GIS Cut Line= 4
      2571824.92     13562161.92      2570870.10     13561901.51
      2570123.57     13561918.87      2569732.96     13562118.51
#Sta/Elev= 30
  3915.1  188.30  3955.8  189.17  4040.5  187.23  4080.9  187.97  4114.8  186.48
  4182.4  185.98  4257.1  185.70  4316.7  183.19  4464.4  180.10  4547.3  179.61
  4565.7  180.33  4754.0  180.03  4969.9  175.28  5007.8  175.13  5008.1  174.63
  5011.7  174.63  5012.0  175.13  5160.0  176.87  5230.0  175.78  5300.0  177.86
  5320.0  175.15  5335.6  175.44  5532.5  179.40  5630.9  181.95  5699.2  183.88
  5715.8  183.64  5751.0  184.96  5917.7  187.04  5975.6  186.76  6090.2  187.77
#Mann=9,-1,0
  3915.1    0.04       0  4182.4    0.05       0  4316.7    0.12       0
  5007.8    0.05       0  5012.0    0.12       0  5335.6   0.013       0
  5532.5    0.12       0  5630.9    0.05       0  5917.7    0.12       0
Bank Sta=5007.8,5012
Exp/Cntr=0.3,0.1

Type RM Length L Ch R = 1,963,783,783,783
BEGIN DESCRIPTION:
LGII3169
END DESCRIPTION:
XS GIS Cut Line= 3
      2571816.26     13560877.21      2570297.18     13561467.48
      2569785.02     13561988.33
#Sta/Elev= 30
  3888.2  198.09  3955.2  194.84  3996.8  193.97  4148.4  186.61  4336.2  180.92
  4480.3  182.43  4559.3  181.95  4831.5  174.13  4945.7  172.62  4992.1  170.42
  4992.5  169.92  4997.1  170.42  5016.0  172.25  5054.5  170.84  5101.9  172.83
  5223.2  174.71  5262.8  173.80  5386.5  174.84  5500.7  174.50  5814.3  177.52
  5864.3  178.56  5885.4  178.06  5913.7  179.70  5956.1  180.13  5970.3  181.44
  6024.3  182.32  6046.0  182.75  6157.1  185.19  6200.8  185.64  6248.4  185.63
#Mann=8,-1,0
  3888.2    0.12       0  4992.1    0.05       0  4997.1    0.12       0
  5814.3   0.013       0  6024.3    0.04       0  6046.0    0.05       0
  6157.1    0.04       0  6200.8    0.12       0
Bank Sta=4992.1,4997.1
Exp/Cntr=0.3,0.1

Type RM Length L Ch R = 1,180,0,0,0
BEGIN DESCRIPTION:
LGII3168
END DESCRIPTION:
XS GIS Cut Line= 4
      2571382.25     13560417.13      2570418.71     13560686.23
      2570036.76     13561068.18      2569706.91     13561996.98
#Sta/Elev= 30
  3976.9  194.23  4209.1  181.85  4322.0  176.84  4434.9  172.93  4534.7  171.25
  4607.4  170.98  4742.4  172.97  4908.5  171.53  4970.8  169.57  4976.6  167.09
  4983.6  166.59  4984.0  166.09  4988.6  166.59  5028.6  170.50  5113.4  171.16
  5212.4  174.02  5297.3  174.40  5318.5  173.34  5339.7  173.37  5360.9  171.75
  5368.0  172.29  5375.0  171.39  5382.1  172.52  5403.3  172.89  5631.7  174.27
  5749.9  174.11  6005.1  177.59  6196.8  179.65  6371.3  184.77  6503.1  185.90
#Mann=4,-1,0
  3976.9    0.12       0  4983.6    0.05       0  4988.6    0.12       0
  6005.1    0.04       0
Bank Sta=4983.6,4988.6
Exp/Cntr=0.3,0.1

Chan Stop Cuts=-1