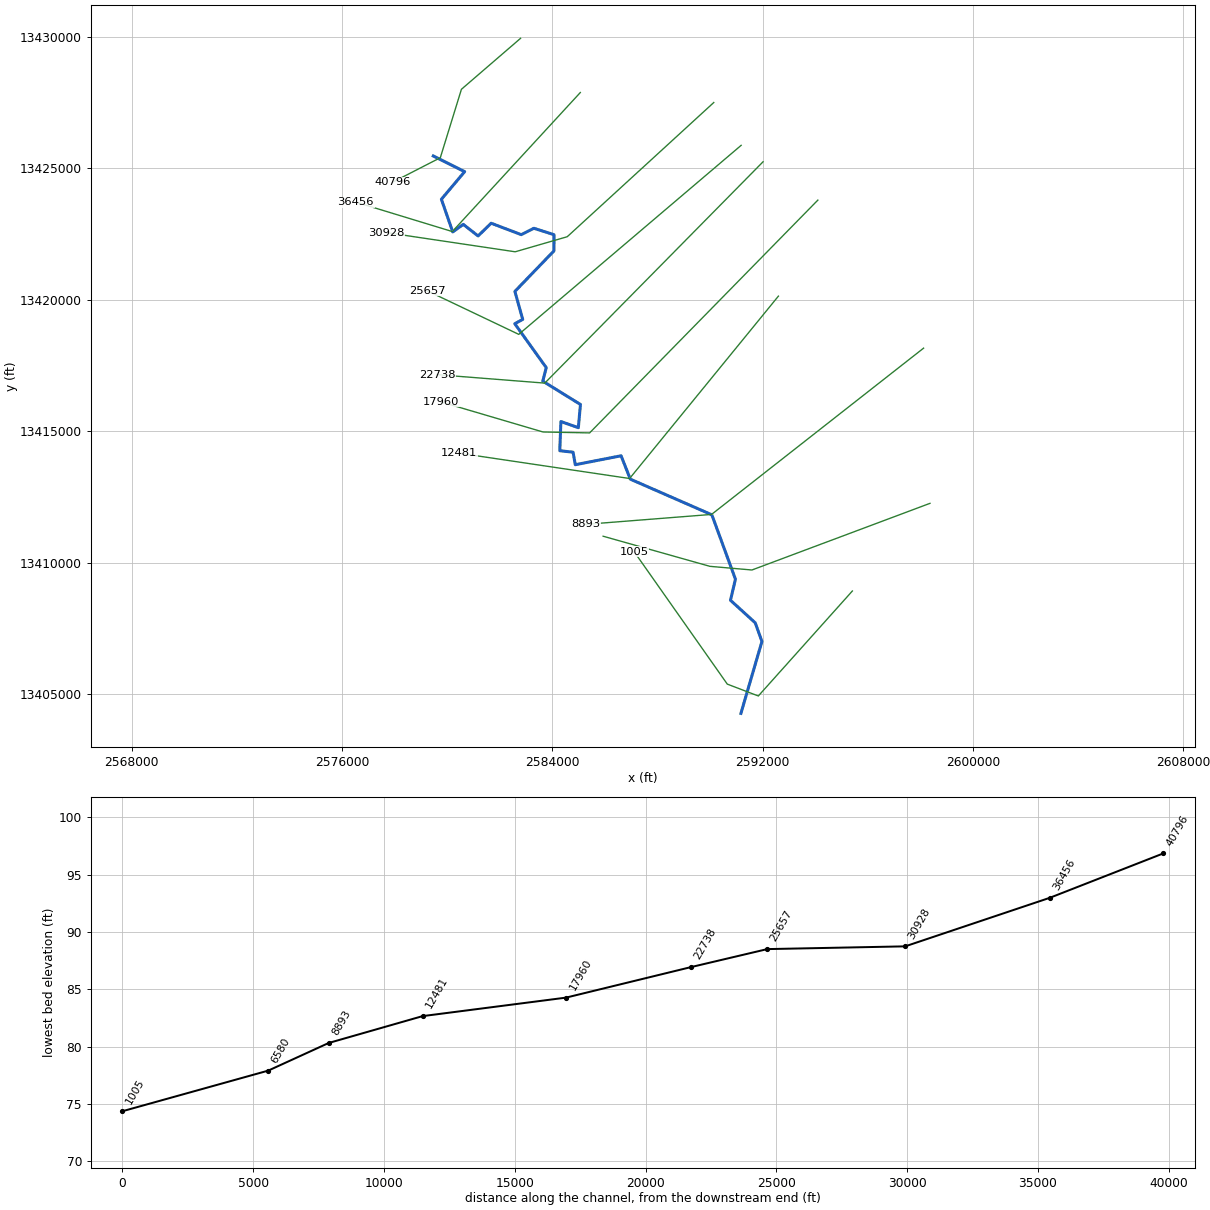
--- TRIB 10 TO KUY CREEK.prj (project) ---

Proj Title=TRIB 10 TO KUY CREEK Base Level Engineering
Current Plan=p01
Default Exp/Contr=0.3,0.1
English Units
Geom File=g01
Flow File=f01
Plan File=p01
BEGIN DESCRIPTION:
TRIB 10 TO KUY CREEK
END DESCRIPTION:

--- TRIB 10 TO KUY CREEK.p01 (plan) ---

Plan Title=Multiple Run
Short Identifier=Multiple
Geom File=g01
Flow File=f01
Subcritical Flow
K Sum by GR= 0
Std Step Tol= 0.01
Critical Tol= 0.01
Num of Std Step Trials= 20
Max Error Tol= 0.3
Flow Tol Ratio= 0.001
Split Flow NTrial= 30
Split Flow Tol= 0.02
Split Flow Ratio= 0.02
Log Output Level= 0
Friction Slope Method= 1
Unsteady Friction Slope Method= 2
Unsteady Bridges Friction Slope Method= 1
Parabolic Critical Depth
Global Vel Dist=  1 , 1 , 1
Global Log Level= 0
CheckData=True
Encroach Param= -1, 0, 0, 0
BEGIN DESCRIPTION:
Multiple Run
END DESCRIPTION:

--- TRIB 10 TO KUY CREEK.f01 (steady flow) ---

Flow Title=Multiple
Number of Profiles=7
Profile Names=10-year,25-year,50-year,1pct_min,100-year,1pct_plu,500-year
River Rch & RM= TRIB 10 TO KUY C,Reach-1,40796
     486     726     923     566    1130    2254    1673
River Rch & RM= TRIB 10 TO KUY C,Reach-1,25657
     801    1225    1583     984    1964    3918    2991
River Rch & RM= TRIB 10 TO KUY C,Reach-1,12481
    1148    1789    2341    1474    2940    5867    4588
River Rch & RM= TRIB 10 TO KUY C,Reach-1,6580
    1455    2295    3029    1921    3833    7649    6076
Boundary for River Rch & Prof#=TRIB 10 TO KUY C,Reach-1,1
Up Type=0
Dn Type=3
Dn Slope=0.005
Boundary for River Rch & Prof#=TRIB 10 TO KUY C,Reach-1,2
Up Type=0
Dn Type=3
Dn Slope=0.005
Boundary for River Rch & Prof#=TRIB 10 TO KUY C,Reach-1,3
Up Type=0
Dn Type=3
Dn Slope=0.005
Boundary for River Rch & Prof#=TRIB 10 TO KUY C,Reach-1,4
Up Type=0
Dn Type=3
Dn Slope=0.005
Boundary for River Rch & Prof#=TRIB 10 TO KUY C,Reach-1,5
Up Type=0
Dn Type=3
Dn Slope=0.005
Boundary for River Rch & Prof#=TRIB 10 TO KUY C,Reach-1,6
Up Type=0
Dn Type=3
Dn Slope=0.005
Boundary for River Rch & Prof#=TRIB 10 TO KUY C,Reach-1,7
Up Type=0
Dn Type=3
Dn Slope=0.005

--- TRIB 10 TO KUY CREEK.g01 (geometry) ---

Geom Title=Existing Conditions

River Reach=TRIB 10 TO KUY C,Reach-1
Reach XY= 30
      2579475.00     13425475.00      2580667.53     13424878.62
      2579782.59     13423828.33      2580215.01     13422585.98
      2580614.48     13422874.54      2581178.35     13422432.59
      2581675.00     13422917.46      2582821.60     13422482.78
      2583300.04     13422725.50      2584065.83     13422481.95
      2584063.90     13421864.94      2582578.37     13420323.72
      2582875.56     13419259.75      2582574.53     13419095.17
      2583771.96     13417423.64      2583638.42     13416911.61
      2585072.02     13416023.57      2584991.70     13415141.28
      2584328.46     13415373.97      2584285.48     13414264.44
      2584791.74     13414208.35      2584875.00     13413732.54
      2586616.89     13414072.49      2586968.93     13413183.13
      2590069.55     13411827.47      2590966.93     13409378.31
      2590778.34     13408576.72      2591719.74     13407719.53
      2591974.48     13407009.78      2591175.00     13404275.00

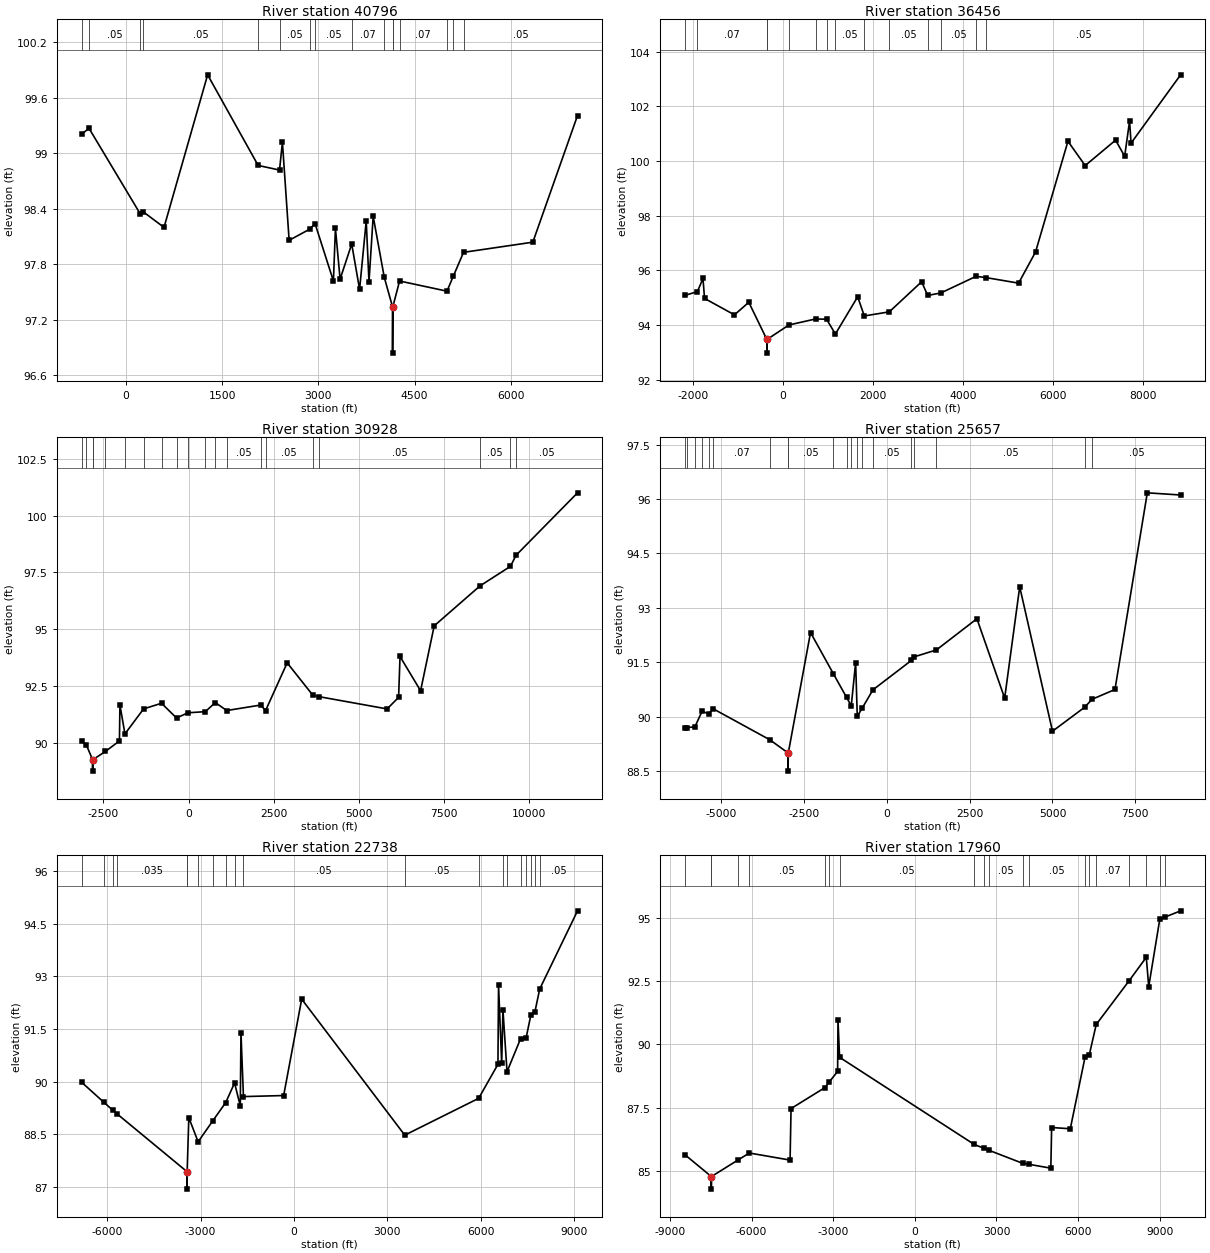
Type RM Length L Ch R = 1,40796,4340,4340,4340
BEGIN DESCRIPTION:
TRIB 10 TO KUY CREEK 33.0
END DESCRIPTION:
XS GIS Cut Line= 4
      2582793.67     13429949.39      2580544.78     13428011.17
      2579741.74     13425408.51      2577925.04     13424475.02
#Sta/Elev= 30
  -692.6   99.21  -575.5   99.27   218.9   98.35   265.8   98.37   593.0   98.20
  1273.2   99.85  2061.0   98.87  2394.3   98.82  2439.7   99.12  2544.4   98.06
  2863.4   98.18  2949.2   98.24  3235.1   97.62  3266.5   98.19  3339.2   97.64
  3520.5   98.02  3643.2   97.53  3746.8   98.27  3789.9   97.61  3855.2   98.32
  4028.3   97.66  4157.5   97.34  4157.8   96.84  4161.6   97.34  4266.8   97.62
  5006.4   97.51  5103.7   97.67  5264.4   97.93  6345.5   98.04  7042.5   99.41
#Mann=16,-1,0
  -692.6    0.07       0  -575.5    0.05       0   218.9    0.07       0
   265.8    0.05       0  2061.0    0.07       0  2394.3    0.05       0
  2863.4    0.07       0  2949.2    0.05       0  3520.5    0.07       0
  4028.3    0.05       0  4157.5    0.07       0  4161.6    0.05       0
  4266.8    0.07       0  5006.4    0.05       0  5103.7    0.07       0
  5264.4    0.05       0
Bank Sta=4157.5,4161.6
Exp/Cntr=0.3,0.1

Type RM Length L Ch R = 1,36456,5528,5528,5528
BEGIN DESCRIPTION:
TRIB 10 TO KUY CREEK 26.0
END DESCRIPTION:
XS GIS Cut Line= 3
      2585066.73     13427887.96      2580198.36     13422600.73
      2576525.09     13423721.33
#Sta/Elev= 30
 -2187.2   95.08 -1904.2   95.22 -1780.4   95.70 -1745.3   94.97 -1080.1   94.37
  -761.3   94.83  -360.4   93.47  -360.1   92.97  -355.9   93.47   130.5   94.00
   725.2   94.22   966.8   94.21  1164.0   93.67  1659.1   95.03  1807.5   94.33
  2363.2   94.48  3081.3   95.58  3216.4   95.08  3507.4   95.17  4294.0   95.78
  4522.3   95.73  5238.1   95.53  5614.8   96.67  6335.3  100.72  6718.1   99.83
  7394.5  100.76  7596.3  100.17  7705.5  101.46  7738.3  100.65  8840.4  103.15
#Mann=14,-1,0
 -2187.2    0.05       0 -1904.2    0.07       0  -360.4    0.05       0
  -355.9    0.07       0   130.5    0.12       0   725.2    0.05       0
   966.8    0.07       0  1164.0    0.05       0  1807.5    0.07       0
  2363.2    0.05       0  3216.4    0.07       0  3507.4    0.05       0
  4294.0    0.12       0  4522.3    0.05       0
Bank Sta=-360.4,-355.9
Exp/Cntr=0.3,0.1

Type RM Length L Ch R = 1,30928,5271,5271,5271
BEGIN DESCRIPTION:
Mapping XS c9dc23d0
END DESCRIPTION:
XS GIS Cut Line= 4
      2590142.70     13427508.21      2584569.79     13422404.05
      2582590.63     13421831.13      2577695.84     13422560.15
#Sta/Elev= 30
 -3142.2   90.07 -2999.0   89.88 -2818.6   89.24 -2818.2   88.74 -2813.7   89.24
 -2440.1   89.61 -2030.5   90.07 -2016.3   91.66 -1869.1   90.38 -1322.5   91.48
  -794.9   91.73  -353.5   91.08   -20.7   91.31   492.1   91.36   784.8   91.76
  1121.8   91.41  2115.5   91.65  2262.6   91.41  2895.9   93.51  3652.3   92.08
  3833.7   92.02  5831.3   91.48  6168.9   91.99  6210.5   93.79  6814.6   92.28
  7214.2   95.14  8559.6   96.90  9452.9   97.76  9619.1   98.25 11424.1  101.00
#Mann=20,-1,0
 -3142.2    0.05       0 -2999.0    0.07       0 -2818.6    0.05       0
 -2813.7    0.07       0 -2440.1    0.05       0 -1869.1    0.07       0
 -1322.5    0.05       0  -794.9    0.07       0  -353.5    0.05       0
   -20.7    0.05       0   492.1    0.07       0   784.8    0.07       0
  1121.8    0.05       0  2115.5    0.07       0  2262.6    0.05       0
  3652.3    0.07       0  3833.7    0.05       0  8559.6    0.05       0
  9452.9   0.035       0  9619.1    0.05       0
Bank Sta=-2818.6,-2813.7
Exp/Cntr=0.3,0.1

Type RM Length L Ch R = 1,25657,2919,2919,2919
BEGIN DESCRIPTION:
TRIB 10 TO KUY CREEK 27.0
END DESCRIPTION:
XS GIS Cut Line= 3
      2591184.36     13425879.73      2582725.01     13418690.36
      2579233.38     13420353.29
#Sta/Elev= 30
 -6101.7   89.70 -6034.0   89.70 -5793.9   89.72 -5575.9   90.15 -5378.9   90.08
 -5244.9   90.22 -3524.1   89.36 -2981.0   89.00 -2980.5   88.50 -2974.4   89.00
 -2303.3   92.32 -1611.5   91.18 -1213.8   90.53 -1073.8   90.30  -941.5   91.49
  -892.1   90.01  -734.6   90.25  -419.7   90.74   740.0   91.55   825.5   91.65
  1496.7   91.84  2719.1   92.70  3556.4   90.51  4010.7   93.58  5000.0   89.60
  5970.3   90.26  6194.3   90.48  6885.7   90.75  7861.5   96.17  8867.4   96.11
#Mann=20,-1,0
 -6101.7    0.07       0 -6034.0    0.05       0 -5793.9    0.07       0
 -5575.9    0.05       0 -5378.9    0.07       0 -5244.9    0.07       0
 -3524.1    0.05       0 -2981.0    0.05       0 -2974.4    0.05       0
 -1611.5    0.07       0 -1213.8    0.05       0 -1073.8   0.035       0
  -892.1    0.05       0  -734.6    0.07       0  -419.7    0.05       0
   740.0    0.05       0   825.5    0.07       0  1496.7    0.05       0
  5970.3    0.07       0  6194.3    0.05       0
Bank Sta=-2981,-2974.4
Exp/Cntr=0.3,0.1

Type RM Length L Ch R = 1,22738,4778,4778,4778
BEGIN DESCRIPTION:
TRIB 10 TO KUY CREEK 28.0
END DESCRIPTION:
XS GIS Cut Line= 3
      2592017.68     13425254.71      2583714.89     13416836.10
      2579615.38     13417158.82
#Sta/Elev= 30
 -6824.1   89.98 -6111.7   89.41 -5820.5   89.18 -5687.9   89.08 -3439.0   87.43
 -3438.5   86.93 -3431.6   87.43 -3378.7   88.97 -3079.3   88.28 -2615.1   88.87
 -2192.8   89.40 -1907.9   89.96 -1724.1   89.30 -1702.8   91.39 -1622.9   89.57
  -331.0   89.60   248.8   92.35  3560.9   88.47  5934.6   89.52  6554.7   90.49
  6574.2   92.74  6675.1   90.53  6715.7   92.04  6846.6   90.28  7281.6   91.22
  7461.4   91.25  7610.9   91.89  7740.8   91.98  7897.0   92.64  9112.2   94.87
#Mann=20,-1,0
 -6824.1    0.05       0 -6111.7   0.035       0 -5820.5    0.07       0
 -5687.9   0.035       0 -3439.0    0.05       0 -3431.6   0.035       0
 -3079.3    0.07       0 -2615.1   0.035       0 -2192.8   0.035       0
 -1907.9   0.035       0 -1622.9    0.05       0  3560.9    0.05       0
  5934.6    0.07       0  6715.7    0.12       0  6846.6    0.07       0
  7281.6    0.05       0  7461.4    0.07       0  7610.9    0.05       0
  7740.8    0.07       0  7897.0    0.05       0
Bank Sta=-3439,-3431.6
Exp/Cntr=0.3,0.1

Type RM Length L Ch R = 1,17960,5479,5479,5479
BEGIN DESCRIPTION:
Mapping XS a18888b4
END DESCRIPTION:
XS GIS Cut Line= 4
      2594101.05     13423796.42      2585420.49     13414942.25
      2583649.65     13414976.97      2579760.76     13416122.80
#Sta/Elev= 30
 -8457.9   85.64 -7480.7   84.77 -7480.2   84.27 -7472.7   84.77 -6488.3   85.43
 -6080.8   85.70 -4584.6   85.42 -4549.1   87.46 -3305.0   88.29 -3155.2   88.50
 -2838.0   88.93 -2823.8   90.96 -2766.3   89.49  2181.5   86.04  2557.1   85.88
  2743.0   85.80  3966.5   85.29  4208.3   85.25  4997.3   85.10  5027.3   86.71
  5712.6   86.66  6255.4   89.50  6409.4   89.58  6665.5   90.79  7874.1   92.52
  8505.8   93.45  8595.0   92.29  9001.6   94.96  9210.9   95.05  9767.0   95.29
#Mann=20,-1,0
 -8457.9    0.05       0 -7480.7    0.05       0 -7472.7    0.05       0
 -6488.3    0.05       0 -6080.8    0.05       0 -3305.0    0.07       0
 -3155.2    0.05       0 -2766.3    0.05       0  2181.5    0.07       0
  2557.1    0.07       0  2743.0    0.05       0  3966.5    0.07       0
  4208.3    0.05       0  6255.4    0.07       0  6409.4    0.05       0
  6665.5    0.07       0  7874.1   0.035       0  8505.8    0.05       0
  9001.6    0.07       0  9210.9    0.05       0
Bank Sta=-7480.7,-7472.7
Exp/Cntr=0.3,0.1

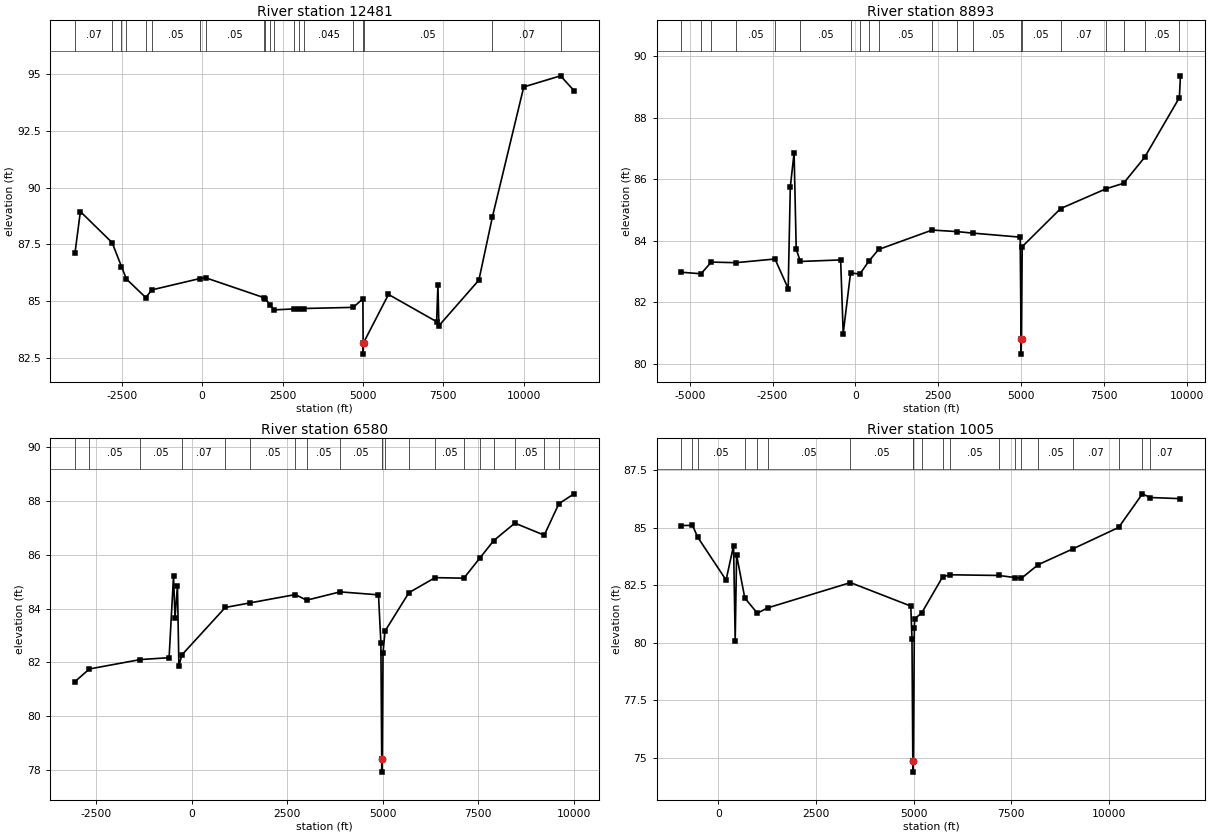
Type RM Length L Ch R = 1,12481,3588,3588,3588
BEGIN DESCRIPTION:
TRIB 10 TO KUY CREEK 29.0
END DESCRIPTION:
XS GIS Cut Line= 3
      2592601.46     13420144.92      2586941.42     13413207.92
      2580449.30     13414172.62
#Sta/Elev= 30
 -3953.1   87.12 -3785.4   88.94 -2798.2   87.57 -2508.2   86.52 -2354.9   85.97
 -1751.4   85.15 -1564.8   85.49   -68.7   85.99   116.8   86.02  1918.0   85.15
  1956.0   85.11  2120.8   84.82  2241.5   84.61  2842.2   84.65  3008.1   84.66
  3157.6   84.67  4701.6   84.72  4998.7   85.10  5007.0   83.16  5007.5   82.66
  5018.7   83.16  5795.1   85.29  7291.3   84.09  7332.1   85.71  7362.1   83.91
  8605.6   85.92  9027.1   88.71 10000.7   94.43 11143.9   94.92 11563.4   94.27
#Mann=20,-1,0
 -3953.1    0.07       0 -2798.2    0.05       0 -2508.2   0.035       0
 -2354.9    0.05       0 -1751.4    0.07       0 -1564.8    0.05       0
   -68.7    0.12       0   116.8    0.05       0  1918.0    0.07       0
  1956.0    0.05       0  2120.8    0.07       0  2241.5    0.05       0
  2842.2    0.07       0  3008.1    0.05       0  3157.6   0.045       0
  4701.6    0.05       0  5007.0    0.05       0  5018.7    0.05       0
  9027.1    0.07       0 11143.9    0.05       0
Bank Sta=5007,5018.7
Exp/Cntr=0.3,0.1

Type RM Length L Ch R = 1,8893,2313,2313,2313
BEGIN DESCRIPTION:
TRIB 10 TO KUY CREEK 30.0
END DESCRIPTION:
XS GIS Cut Line= 3
      2598122.27     13418165.74      2590058.58     13411841.80
      2585275.05     13411464.38
#Sta/Elev= 30
 -5247.7   82.98 -4658.4   82.93 -4347.2   83.31 -3609.6   83.29 -2427.3   83.41
 -2029.7   82.45 -1965.5   85.75 -1851.6   86.86 -1787.5   83.73 -1662.4   83.33
  -447.8   83.38  -370.9   80.99  -148.8   82.96   130.7   82.92   402.4   83.34
   697.1   83.72  2311.3   84.35  3058.1   84.30  3547.2   84.25  4965.3   84.12
  4992.5   80.82  4993.0   80.32  5005.8   80.82  5025.8   83.81  6187.7   85.05
  7552.4   85.69  8082.4   85.87  8716.0   86.71  9765.0   88.65  9798.4   89.36
#Mann=20,-1,0
 -5247.7    0.05       0 -4658.4    0.07       0 -4347.2    0.05       0
 -3609.6    0.05       0 -2427.3    0.05       0 -1662.4    0.05       0
  -148.8    0.07       0   130.7    0.05       0   402.4    0.07       0
   697.1    0.05       0  2311.3    0.07       0  3058.1    0.07       0
  3547.2    0.05       0  4992.5    0.05       0  5005.8    0.05       0
  6187.7    0.07       0  7552.4    0.07       0  8082.4    0.05       0
  8716.0    0.05       0  9765.0    0.07       0
Bank Sta=4992.5,5005.8
Exp/Cntr=0.3,0.1

Type RM Length L Ch R = 1,6580,5575,5575,5575
BEGIN DESCRIPTION:
TRIB 10 TO KUY CREEK 31.0
END DESCRIPTION:
XS GIS Cut Line= 4
      2598365.35     13412262.98      2591594.53     13409728.27
      2589997.31     13409867.16      2585934.77     13411013.00
#Sta/Elev= 30
 -3052.5   81.28 -2676.5   81.75 -1345.4   82.10  -591.0   82.17  -475.2   85.20
  -436.1   83.66  -372.0   84.85  -334.5   81.85  -259.0   82.27   879.3   84.04
  1527.4   84.21  2711.0   84.52  3007.0   84.31  3881.6   84.62  4887.1   84.51
  4949.6   82.72  4971.5   78.41  4972.0   77.91  4988.0   78.41  5005.0   82.34
  5057.6   83.16  5682.6   84.59  6368.1   85.15  7121.1   85.13  7544.4   85.89
  7902.5   86.53  8454.7   87.18  9222.9   86.73  9605.4   87.90 10001.5   88.27
#Mann=20,-1,0
 -3052.5    0.07       0 -2676.5    0.05       0 -1345.4    0.05       0
  -259.0    0.07       0   879.3    0.05       0  1527.4    0.05       0
  2711.0    0.07       0  3007.0    0.05       0  3881.6    0.05       0
  4971.5    0.05       0  4988.0    0.07       0  5057.6    0.07       0
  5682.6    0.07       0  6368.1    0.05       0  7121.1    0.05       0
  7544.4    0.07       0  7902.5    0.05       0  8454.7    0.05       0
  9222.9    0.05       0  9605.4    0.07       0
Bank Sta=4971.5,4988
Exp/Cntr=0.3,0.1

Type RM Length L Ch R = 1,1005,0,0,0
BEGIN DESCRIPTION:
TRIB 10 TO KUY CREEK 32.0
END DESCRIPTION:
XS GIS Cut Line= 4
      2595413.96     13408929.64      2591837.59     13404936.60
      2590657.03     13405387.99      2587116.30     13410421.39
#Sta/Elev= 30
  -942.2   85.09  -660.1   85.10  -524.3   84.58   200.6   82.72   392.0   84.22
   433.9   80.09   469.8   83.81   679.7   81.94  1001.2   81.28  1263.2   81.51
  3384.7   82.61  4930.7   81.59  4960.8   80.17  4982.3   74.87  4982.8   74.37
  4999.4   74.87  5020.9   80.65  5031.3   81.03  5213.6   81.30  5746.0   82.86
  5940.2   82.95  7185.5   82.92  7599.1   82.83  7764.2   82.80  8193.4   83.39
  9073.1   84.07 10253.9   85.01 10862.0   86.47 11059.7   86.31 11836.2   86.26
#Mann=20,-1,0
  -942.2    0.05       0  -660.1   0.035       0  -524.3    0.05       0
   679.7    0.05       0  1001.2    0.07       0  1263.2    0.05       0
  3384.7    0.05       0  4982.3    0.07       0  4999.4    0.07       0
  5213.6    0.05       0  5746.0    0.07       0  5940.2    0.05       0
  7185.5    0.07       0  7599.1    0.12       0  7764.2    0.05       0
  8193.4    0.05       0  9073.1    0.07       0 10253.9    0.07       0
 10862.0    0.05       0 11059.7    0.07       0
Bank Sta=4982.3,4999.4
Exp/Cntr=0.3,0.1

Chan Stop Cuts=-1