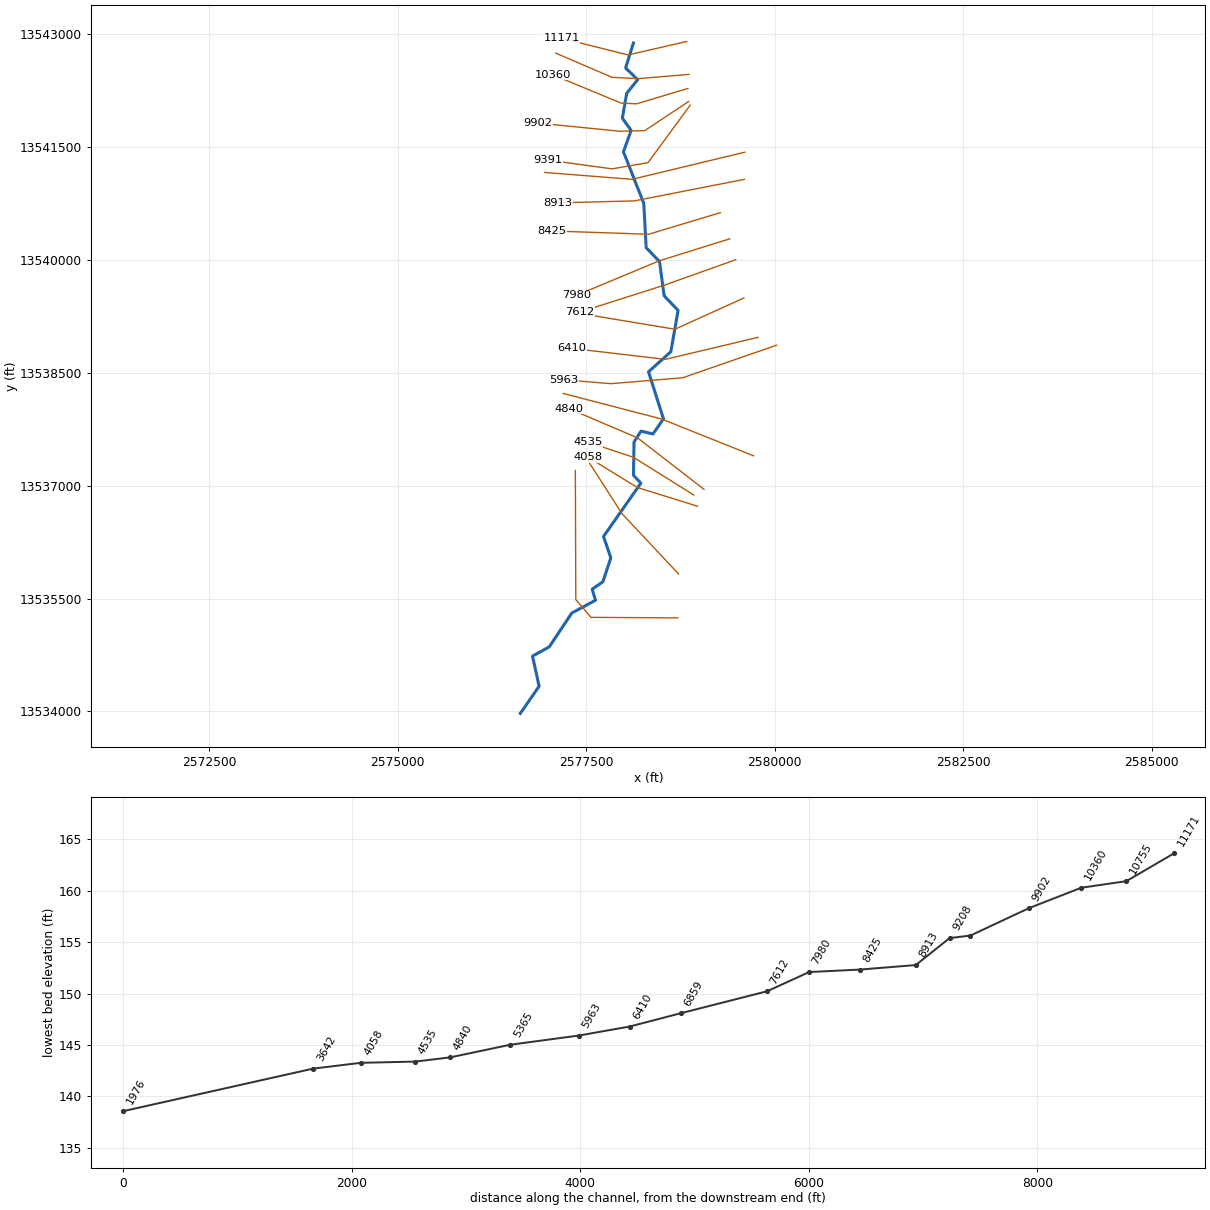
--- TRIB 10 TO SPRING CREEK.prj (project) ---

Proj Title=TRIB 10 TO SPRING CREEK Base Level Engineering
Current Plan=p01
Default Exp/Contr=0.3,0.1
English Units
Geom File=g01
Flow File=f01
Plan File=p01
Y Axis Title=Elevation
X Axis Title(PF)=Main Channel Distance
X Axis Title(XS)=Station
BEGIN DESCRIPTION:
TRIB 10 TO SPRING CREEK
END DESCRIPTION:
DSS Export Rating Curves= 0
DSS Export Rating Curve Sorted= 0
DSS Export Volume Flow Curves= 0
DXF OffsetX= 0
DXF OffsetY= 0
DXF ScaleX= 1
DXF ScaleY= 10

--- TRIB 10 TO SPRING CREEK.p01 (plan) ---

Plan Title=Multiple Run
Short Identifier=Multiple
Geom File=g01
Flow File=f01
Subcritical Flow
K Sum by GR= 0
Std Step Tol= 0.01
Critical Tol= 0.01
Num of Std Step Trials= 20
Max Error Tol= 0.3
Flow Tol Ratio= 0.001
Split Flow NTrial= 30
Split Flow Tol= 0.02
Split Flow Ratio= 0.02
Log Output Level= 0
Friction Slope Method= 1
Unsteady Friction Slope Method= 2
Unsteady Bridges Friction Slope Method= 1
Parabolic Critical Depth
Global Vel Dist=  1 , 1 , 1
Global Log Level= 0
CheckData=True
Encroach Param= -1, 0, 0, 0
BEGIN DESCRIPTION:
Multiple Run
END DESCRIPTION:

--- TRIB 10 TO SPRING CREEK.f01 (steady flow) ---

Flow Title=Multiple
Number of Profiles=7
Profile Names=10-year,25-year,50-year,1pct_min,100-year,1pct_plu,500-year
River Rch & RM= TRIB 10 TO SPRIN,Reach-1,11171
     597     931    1222     777    1550    3093    2461
River Rch & RM= TRIB 10 TO SPRIN,Reach-1,8913
     857    1364    1816    1168    2331    4652    3797
River Rch & RM= TRIB 10 TO SPRIN,Reach-1,6859
    1127    1819    2445    1586    3165    6315    5242
River Rch & RM= TRIB 10 TO SPRIN,Reach-1,4058
    1227    1988    2677    1740    3471    6926    5771
Boundary for River Rch & Prof#=TRIB 10 TO SPRIN,Reach-1,1
Up Type=0
Dn Type=3
Dn Slope=0.005
Boundary for River Rch & Prof#=TRIB 10 TO SPRIN,Reach-1,2
Up Type=0
Dn Type=3
Dn Slope=0.005
Boundary for River Rch & Prof#=TRIB 10 TO SPRIN,Reach-1,3
Up Type=0
Dn Type=3
Dn Slope=0.005
Boundary for River Rch & Prof#=TRIB 10 TO SPRIN,Reach-1,4
Up Type=0
Dn Type=3
Dn Slope=0.005
Boundary for River Rch & Prof#=TRIB 10 TO SPRIN,Reach-1,5
Up Type=0
Dn Type=3
Dn Slope=0.005
Boundary for River Rch & Prof#=TRIB 10 TO SPRIN,Reach-1,6
Up Type=0
Dn Type=3
Dn Slope=0.005
Boundary for River Rch & Prof#=TRIB 10 TO SPRIN,Reach-1,7
Up Type=0
Dn Type=3
Dn Slope=0.005

--- TRIB 10 TO SPRING CREEK.g01 (geometry) ---

Geom Title=Existing Conditions
Program Version=4.10

River Reach=TRIB 10 TO SPRIN,Reach-1
Reach XY= 30
        2578125.       13542875.      2578021.22     13542544.07
      2578181.81      13542388.9      2578035.33     13542205.53
      2577978.43     13541876.58      2578094.53     13541714.91
      2577992.71     13541431.29      2578262.36     13540746.56
      2578294.18     13540157.83      2578471.47     13539973.55
      2578532.76     13539518.83      2578717.71     13539325.09
      2578621.45     13538776.47      2578325.38     13538509.85
       2578523.8      13537885.5       2578384.7     13537685.18
      2578226.42     13537721.96      2578133.07     13537578.31
      2578126.01     13537135.29      2578223.57     13537031.43
      2577728.11     13536323.35      2577824.99     13536040.36
      2577719.64      13535722.3      2577578.04     13535623.58
      2577621.87     13535476.63      2577308.33     13535308.61
      2577008.36     13534858.25      2576786.08      13534735.1
      2576873.78      13534335.5        2576625.       13533975.

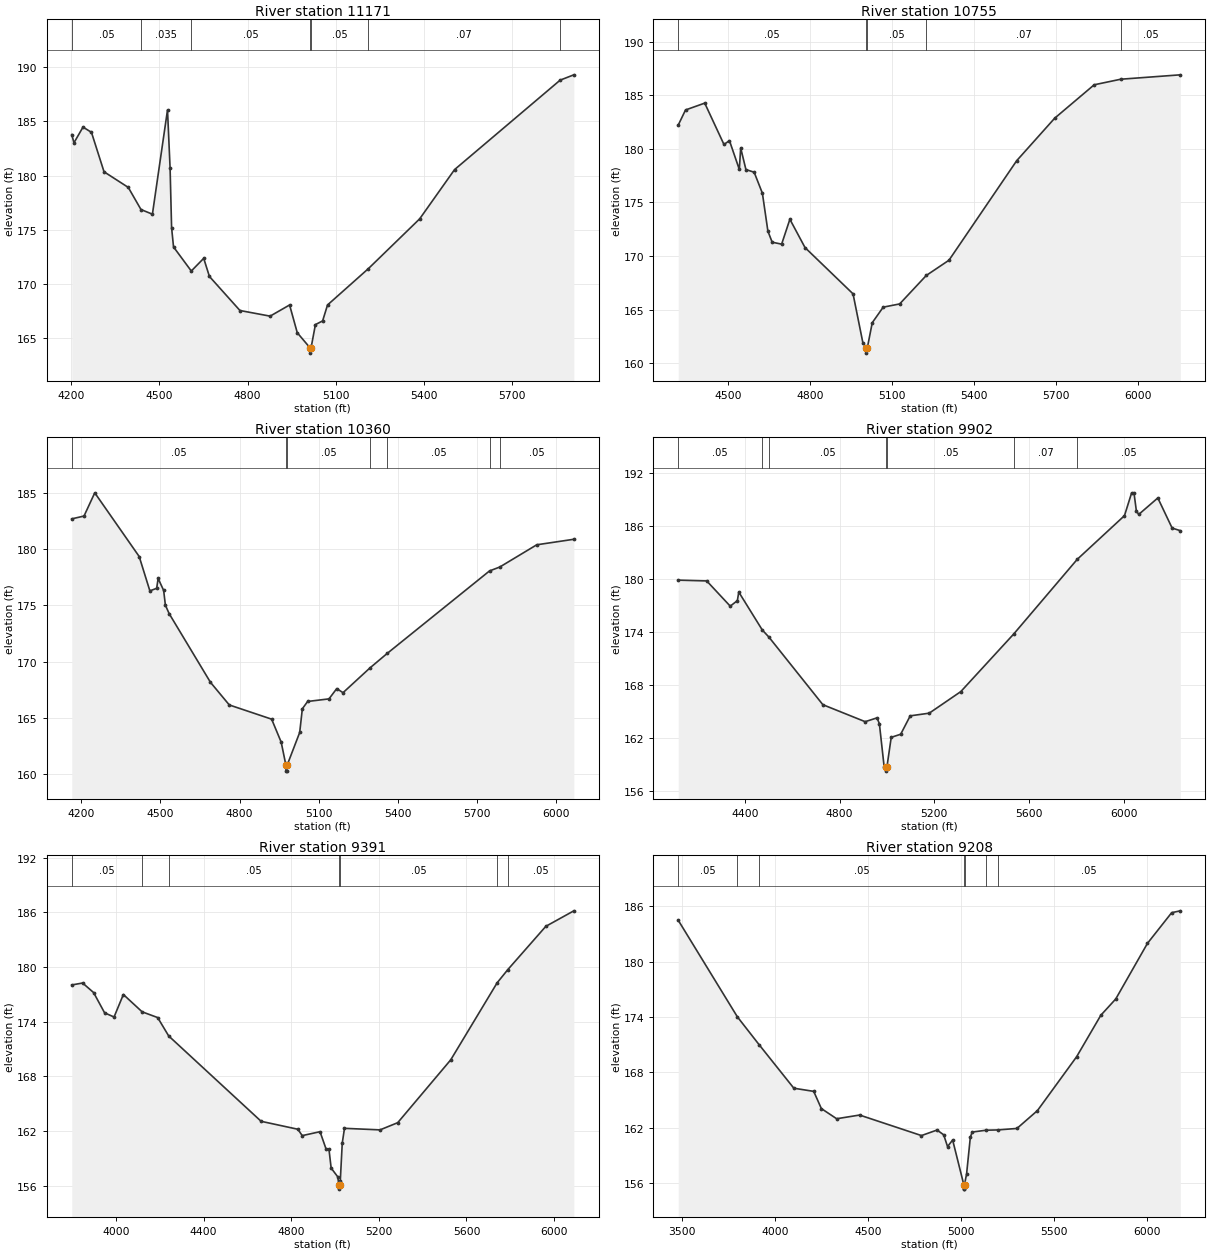
Type RM Length L Ch R = 1 ,11171   ,416,416,416
BEGIN DESCRIPTION:
TRIB 10 TO SPRING CREEK 10.0
END DESCRIPTION:
XS GIS Cut Line= 3
      2578832.25     13542895.65       2578054.4     13542717.01
       2577172.5     13542937.33
#Sta/Elev= 30
  4201.9  183.78  4209.3  183.02  4240.1  184.47  4268.8  183.99  4311.6  180.35
    4394  178.91  4437.2  176.87  4476.1  176.44  4527.4  186.05  4536.2  180.68
  4541.3   175.2  4547.9  173.42  4608.3   171.2  4650.5  172.37  4669.9   170.7
  4773.7  167.56  4876.3  167.04  4942.5  168.07  4968.6  165.51  5011.6  164.13
  5011.8  163.63  5015.6  164.13  5030.3  166.26  5054.8   166.6  5071.5  168.07
  5210.4  171.42  5384.8  176.01  5503.4  180.55  5862.4   188.8    5909  189.29
#Mann= 7 ,-1 , 0
  4201.9     .05       0  4437.2    .035       0  4608.3     .05       0
  5011.6     .05       0  5015.6     .05       0  5210.4     .07       0
  5862.4     .05       0
Bank Sta=5011.6,5015.6
XS Rating Curve= 0 ,0
Exp/Cntr=0.3,0.1

Type RM Length L Ch R = 1 ,10755   ,395,395,395
BEGIN DESCRIPTION:
Mapping XS 3005e1ca
END DESCRIPTION:
XS GIS Cut Line= 4
      2578861.47     13542458.73      2578188.73     13542402.31
      2577841.51     13542419.67      2577095.94     13542740.43
#Sta/Elev= 30
  4318.4  182.21    4345  183.62  4415.2  184.26  4485.5   180.4  4505.5  180.76
  4541.6  178.07  4546.6  180.07  4565.7  178.06  4595.8  177.81  4625.9  175.85
    4646  172.31  4661.6  171.28  4696.2   171.1  4726.3  173.42  4781.6  170.78
  4957.1  166.46  4992.9  161.91  5005.3  161.43  5005.5  160.93  5009.3  161.43
  5027.3  163.77  5067.3  165.22  5127.4  165.52  5224.8  168.18  5307.6   169.6
  5555.1  178.89  5693.7  182.85  5838.1  185.97  5935.3  186.49  6152.8   186.9
#Mann= 5 ,-1 , 0
  4318.4     .05       0  5005.3     .05       0  5009.3     .05       0
  5224.8     .07       0  5935.3     .05       0
Bank Sta=5005.3,5009.3
XS Rating Curve= 0 ,0
Exp/Cntr=0.3,0.1

Type RM Length L Ch R = 1 ,10360   ,458,458,458
BEGIN DESCRIPTION:
Mapping XS dc81393f
END DESCRIPTION:
XS GIS Cut Line= 4
      2578848.49     13542272.11      2578167.03      13542068.1
      2577963.04     13542076.78      2577051.58     13542454.39
#Sta/Elev= 30
  4164.4  182.67  4210.8  182.92  4251.5  184.98  4419.8  179.33  4460.3  176.28
    4486  176.51  4491.6  177.38  4512.5  176.32  4519.1  175.01  4533.4  174.26
  4689.8  168.17  4761.2  166.16  4921.6   164.9  4957.8  162.86  4975.9  160.79
  4976.1  160.29  4979.6  160.29  4979.9  160.79  5027.9  163.72  5037.9  165.82
  5057.9  166.47  5138.9   166.7  5168.2  167.61  5192.1  167.25  5294.3  169.45
  5360.3  170.75    5747  178.05  5786.1   178.4  5925.9  180.37  6066.5  180.86
#Mann= 7 ,-1 , 0
  4164.4     .05       0  4975.9     .05       0  4979.9     .05       0
  5294.3     .07       0  5360.3     .05       0    5747     .07       0
  5786.1     .05       0
Bank Sta=4975.9,4979.9
XS Rating Curve= 0 ,0
Exp/Cntr=0.3,0.1

Type RM Length L Ch R = 1 ,9902    ,511,511,511
BEGIN DESCRIPTION:
Mapping XS d8a1eec1
END DESCRIPTION:
XS GIS Cut Line= 4
      2578857.16      13542098.5      2578275.54      13541712.2
      2577950.02     13541703.52      2576860.57     13541812.03
#Sta/Elev= 30
  4119.4  179.89  4239.6   179.8  4338.8  176.95  4368.9  177.57  4374.9  178.54
  4474.2  174.25  4501.8  173.46  4729.7  165.81  4908.2  163.89  4958.2  164.32
  4968.2  163.66  4988.2  158.82  4996.2   158.8  4996.5   158.3  5000.2   158.8
  5018.2  162.12  5058.2  162.47  5098.3  164.55  5178.5  164.85  5311.8  167.29
  5535.4  173.81  5803.1  182.24  6002.5  187.18  6032.7  189.76  6042.7  189.74
  6052.8  187.69  6062.8  187.32  6143.2  189.18  6203.5  185.78  6238.1  185.48
#Mann= 7 ,-1 , 0
  4119.4     .05       0  4474.2     .07       0  4501.8     .05       0
  4996.2     .05       0  5000.2     .05       0  5535.4     .07       0
  5803.1     .05       0
Bank Sta=4996.2,5000.2
XS Rating Curve= 0 ,0
Exp/Cntr=0.3,0.1

Type RM Length L Ch R = 1 ,9391    ,183,183,183
BEGIN DESCRIPTION:
Mapping XS 7128747e
END DESCRIPTION:
XS GIS Cut Line= 4
      2578878.81     13542050.71      2578318.94     13541286.85
      2577841.51     13541204.39      2576988.25     13541321.33
#Sta/Elev= 30
  3797.6  178.04  3847.2  178.25  3897.4   177.2  3947.5  174.98  3990.7  174.52
  4033.2  176.99  4118.9  175.09  4189.9  174.46  4240.3  172.44  4662.3  163.08
  4829.8  162.21  4850.1  161.51  4931.3  161.94  4958.9  160.04  4971.9  160.06
  4982.1  157.95  5012.5  156.98  5016.8  156.14    5017  155.64  5020.8  156.14
  5023.8  156.52  5032.8  160.69    5043  162.31  5205.3  162.14  5286.2  162.93
  5528.4  169.83  5740.3  178.28  5789.2  179.73  5962.5  184.47  6090.4  186.17
#Mann= 7 ,-1 , 0
  3797.6     .05       0  4118.9     .07       0  4240.3     .05       0
  5016.8     .05       0  5020.8     .05       0  5740.3     .07       0
  5789.2     .05       0
Bank Sta=5016.8,5020.8
XS Rating Curve= 0 ,0
Exp/Cntr=0.3,0.1

Type RM Length L Ch R = 1 ,9208    ,295,295,295
BEGIN DESCRIPTION:
Mapping XS 9588b5c3
END DESCRIPTION:
XS GIS Cut Line= 3
      2579603.68     13541425.75      2578106.27      13541065.5
      2576948.68     13541156.55
#Sta/Elev= 30
  3480.1  184.46  3798.2  174.02  3914.7  171.02  4102.1   166.3    4209  165.96
  4250.1   164.1  4332.4     163  4455.9   163.4  4788.7  161.18  4872.6  161.78
  4908.4  161.26    4929  159.99  4956.5   160.7  5016.3  155.89  5016.6  155.39
  5020.1  155.39  5020.3  155.89  5031.5  157.02  5051.6  160.99  5061.6  161.56
  5136.7  161.76  5198.8  161.79  5302.4  161.95  5412.7  163.88  5623.4   169.7
  5753.8  174.19    5834  175.95  6004.5  181.96  6134.9  185.28  6181.4  185.48
#Mann= 7 ,-1 , 0
  3480.1     .05       0  3798.2     .07       0  3914.7     .05       0
  5016.3     .05       0  5020.3     .05       0  5136.7     .07       0
  5198.8     .05       0
Bank Sta=5016.3,5020.3
XS Rating Curve= 0 ,0
Exp/Cntr=0.3,0.1

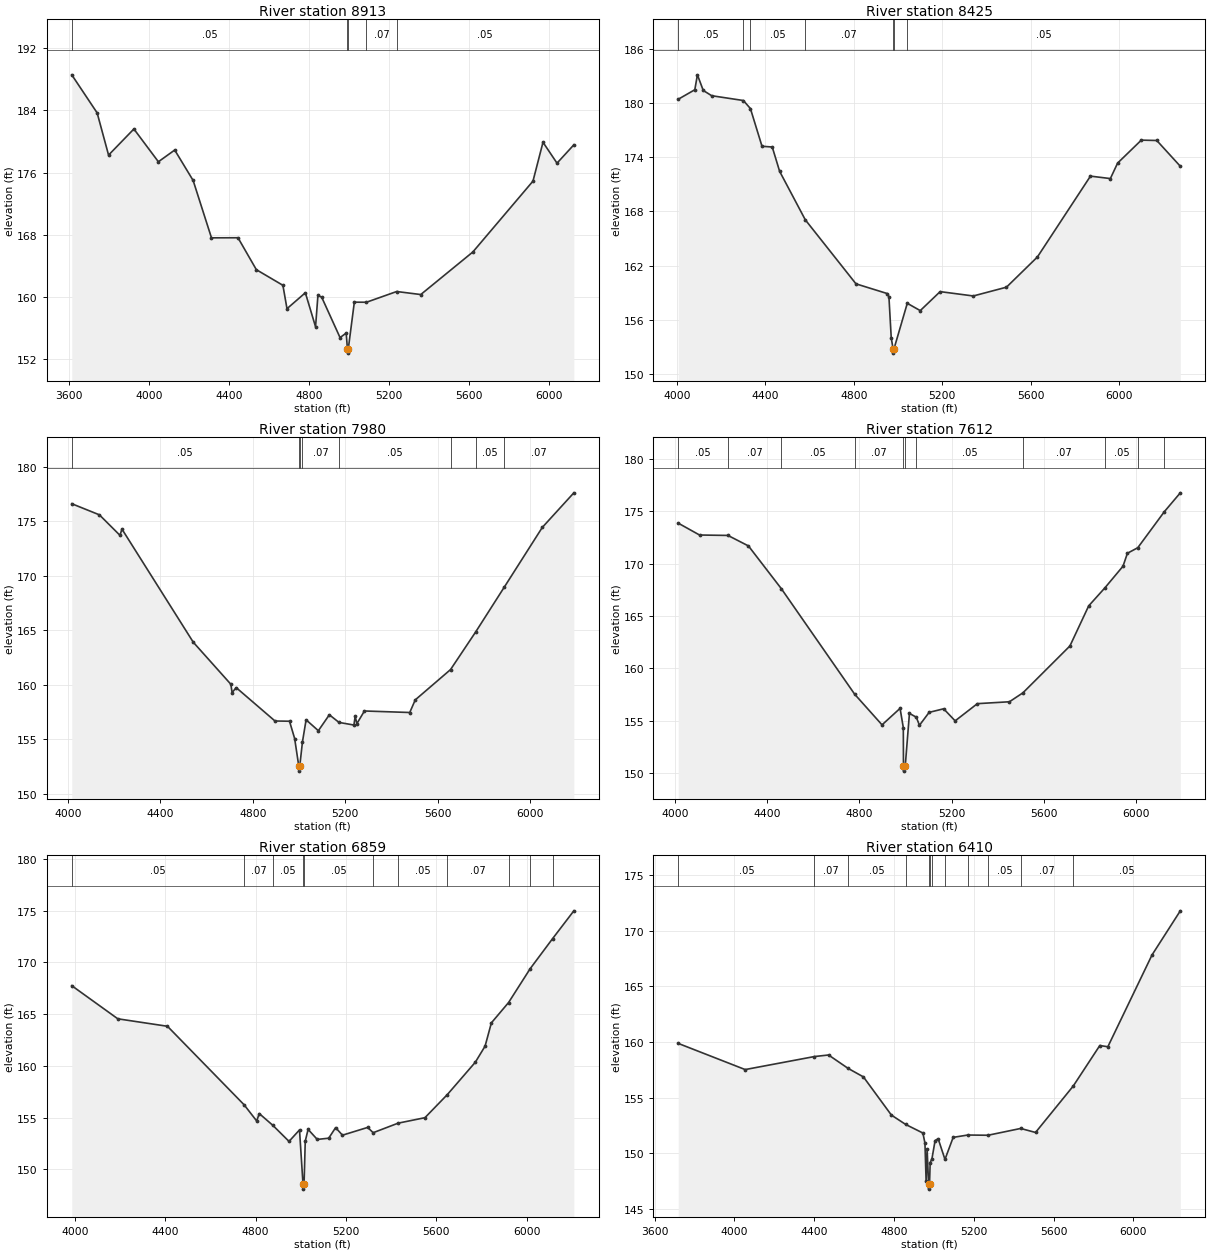
Type RM Length L Ch R = 1 ,8913    ,488,488,488
BEGIN DESCRIPTION:
Mapping XS a45a19b6
END DESCRIPTION:
XS GIS Cut Line= 3
      2579599.35     13541065.51      2578136.65     13540779.04
      2577121.07       13540753.
#Sta/Elev= 30
  3615.3  188.59    3742  183.69    3799  178.26  3925.4  181.62  4047.7   177.4
  4129.2  178.91  4221.2  174.99  4312.7  167.61  4445.1  167.62  4536.8  163.51
  4669.3   161.5  4689.7  158.49  4781.4  160.54  4832.3  156.16  4844.1  160.19
  4862.9  159.97  4954.6  154.77  4985.2  155.35  4991.5  153.27  4991.8  152.77
  4995.5  153.27  5025.9  159.33  5086.5  159.32  5237.4   160.7  5357.5  160.31
  5617.6  165.79  5917.7  174.91  5967.7  179.91  6037.7  177.22  6121.7  179.58
#Mann= 5 ,-1 , 0
  3615.3     .05       0  4991.5     .05       0  4995.5     .05       0
  5086.5     .07       0  5237.4     .05       0
Bank Sta=4991.5,4995.5
XS Rating Curve= 0 ,0
Exp/Cntr=0.3,0.1

Type RM Length L Ch R = 1 ,8425    ,445,445,445
BEGIN DESCRIPTION:
Mapping XS 9788391d
END DESCRIPTION:
XS GIS Cut Line= 3
      2579278.11     13540622.78      2578327.62     13540336.33
      2577048.57     13540379.69
#Sta/Elev= 30
  4005.1   180.4  4080.1  181.45  4091.9   183.1  4118.4  181.37  4156.6  180.79
  4299.9  180.26  4331.8  179.37  4384.3   175.2  4430.6  175.12    4464  172.43
  4580.2  167.07  4809.6  159.99    4952  158.91  4958.8  158.53  4969.2  154.01
  4977.4  152.83  4977.7  152.33    4982  152.83  5041.8  157.84  5100.5  157.03
  5190.5  159.13  5340.6  158.65  5490.7  159.62  5630.8  162.96  5870.9   171.9
    5961  171.63  5993.8  173.34  6101.1  175.88  6171.1  175.84  6277.6  172.99
#Mann= 7 ,-1 , 0
  4005.1     .05       0  4299.9    .035       0  4331.8     .05       0
  4580.2     .07       0  4977.4     .05       0    4982     .07       0
  5041.8     .05       0
Bank Sta=4977.4,4982
XS Rating Curve= 0 ,0
Exp/Cntr=0.3,0.1

Type RM Length L Ch R = 1 ,7980    ,368,368,368
BEGIN DESCRIPTION:
Mapping XS c53af98b
END DESCRIPTION:
XS GIS Cut Line= 3
      2579403.99     13540275.56      2578470.85     13539984.77
      2577369.23     13539525.04
#Sta/Elev= 30
  4017.4  176.63  4136.9  175.61  4225.8  173.73  4234.4   174.3  4542.8  163.92
  4705.4  160.06  4710.6   159.3  4728.6  159.75  4896.2  156.69    4959  156.67
  4981.2  155.08  4998.8  152.59  4999.1  152.09  5003.5  152.59    5015  154.78
  5030.7   156.8  5083.7   155.8  5131.2  157.26    5173  156.56  5237.5  156.32
  5242.9  157.11  5250.4  156.45  5282.9  157.61  5478.9  157.47  5502.8  158.63
  5655.3  161.41  5764.5  164.88  5886.9  168.95  6052.2  174.46  6188.5  177.63
#Mann= 8 ,-1 , 0
  4017.4     .05       0  4998.8     .05       0  5003.5     .05       0
    5015     .07       0    5173     .05       0  5655.3     .07       0
  5764.5     .05       0  5886.9     .07       0
Bank Sta=4998.8,5003.5
XS Rating Curve= 0 ,0
Exp/Cntr=0.3,0.1

Type RM Length L Ch R = 1 ,7612    ,753,753,753
BEGIN DESCRIPTION:
Mapping XS 9865fc17
END DESCRIPTION:
XS GIS Cut Line= 3
      2579482.11     13539997.78      2578557.66     13539667.93
       2577416.2     13539303.36
#Sta/Elev= 30
  4013.5  173.85    4106  172.72  4229.3  172.68  4318.3  171.68  4461.3   167.6
  4779.8  157.54  4898.3  154.63  4976.6   156.2  4990.7  154.36  4991.4  150.72
  4991.7  150.22  4996.2  150.72  4999.1  150.72  5017.3  155.72    5047  155.36
  5060.8  154.59  5102.8  155.82  5165.8  156.16  5215.7  155.01  5312.2  156.65
  5451.4  156.83  5509.9  157.68  5714.1  162.15  5795.6  165.97  5866.1  167.69
  5944.6  169.75  5963.6  170.98  6008.7  171.51  6124.2  174.95  6193.3  176.74
#Mann= 11 ,-1 , 0
  4013.5     .05       0  4229.3     .07       0  4461.3     .05       0
  4779.8     .07       0  4991.4     .05       0  4996.2     .07       0
    5047     .05       0  5509.9     .07       0  5866.1     .05       0
  6008.7     .07       0  6124.2     .05       0
Bank Sta=4991.4,4996.2
XS Rating Curve= 0 ,0
Exp/Cntr=0.3,0.1

Type RM Length L Ch R = 1 ,6859    ,449,449,449
BEGIN DESCRIPTION:
TRIB 10 TO SPRING CREEK 9.0
END DESCRIPTION:
XS GIS Cut Line= 3
      2579590.65     13539489.98        2578675.       13539075.
      2577475.05     13539274.99
#Sta/Elev= 30
  3986.8  167.74  4190.6  164.54  4410.2  163.82  4749.7  156.23  4805.2  154.67
  4816.4  155.39  4876.1  154.26  4948.2   152.7  4994.6  153.81    5010  148.59
  5010.3  148.09  5014.8  148.59    5020  152.72  5032.6  153.86  5073.2  152.89
  5123.9  153.01  5154.3  154.03  5184.7   153.3  5296.2  154.05  5320.6  153.54
  5430.8  154.46  5549.7  154.99  5648.7  157.22  5772.7  160.35  5815.8   161.9
  5843.7  164.15  5919.7  166.11  6015.3  169.38  6114.4  172.28  6208.6  174.97
#Mann= 11 ,-1 , 0
  3986.8     .05       0  4749.7     .07       0  4876.1     .05       0
    5010     .05       0  5014.8     .05       0  5320.6     .07       0
  5430.8     .05       0  5648.7     .07       0  5919.7     .05       0
  6015.3     .07       0  6114.4     .05       0
Bank Sta=5010,5014.8
XS Rating Curve= 0 ,0
Exp/Cntr=0.3,0.1

Type RM Length L Ch R = 1 ,6410    ,447,447,447
BEGIN DESCRIPTION:
Mapping XS bc721919
END DESCRIPTION:
XS GIS Cut Line= 3
      2579778.18     13538967.04      2578549.05     13538675.38
      2577304.22     13538821.22
#Sta/Elev= 30
  3718.6  159.88  4054.1  157.53  4401.3   158.7  4472.1  158.84  4569.7  157.64
  4646.9  156.87  4787.1  153.44  4858.7   152.6  4944.9  151.83  4955.2  150.93
  4961.1  147.48  4966.2  150.38  4973.3  147.29  4973.6  146.79  4978.2  147.29
  4981.4  149.17  4990.3  149.52  5006.1  151.15  5021.4  151.32  5055.6  149.46
  5096.7  151.44  5170.1  151.65  5271.4  151.63  5435.1  152.24  5509.5  151.88
  5698.5  156.05  5831.7  159.69    5872  159.58  6093.5  167.83  6235.2  171.79
#Mann= 12 ,-1 , 0
  3718.6     .05       0  4401.3     .07       0  4569.7     .05       0
  4858.7      .1       0  4973.3     .05       0  4978.2      .1       0
  4990.3     .05       0  5055.6      .1       0  5170.1     .07       0
  5271.4     .05       0  5435.1     .07       0  5698.5     .05       0
Bank Sta=4973.3,4978.2
XS Rating Curve= 0 ,0
Exp/Cntr=0.3,0.1

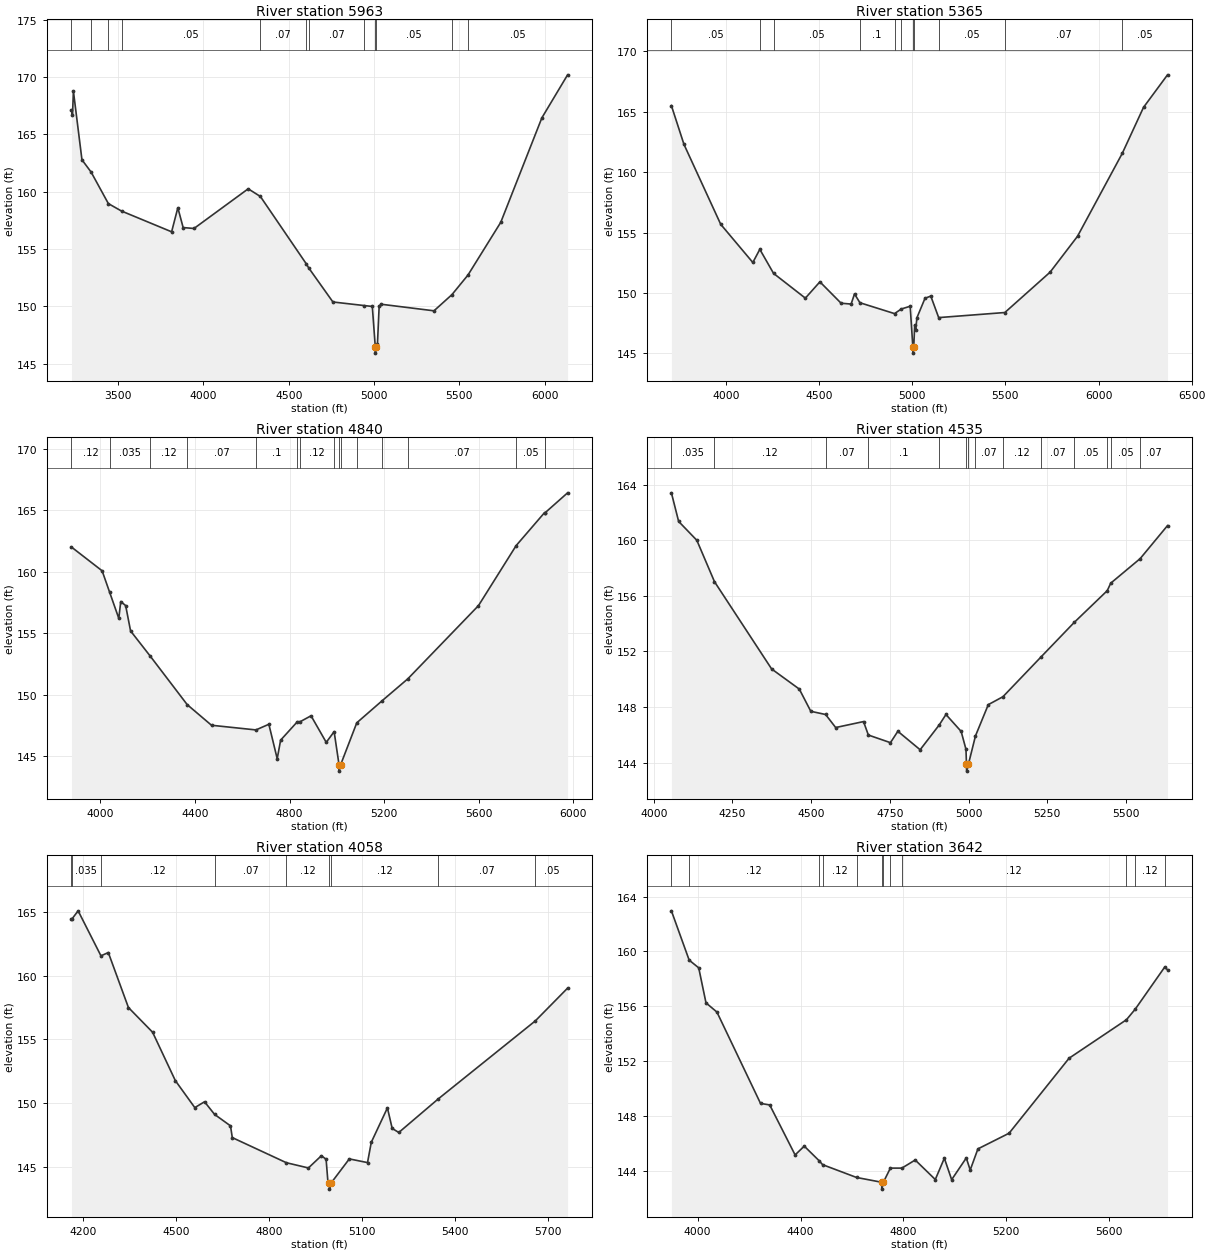
Type RM Length L Ch R = 1 ,5963    ,598,598,598
BEGIN DESCRIPTION:
Mapping XS ce51a715
END DESCRIPTION:
XS GIS Cut Line= 4
      2580022.99     13538862.87      2578778.22     13538430.59
      2577825.09     13538352.46      2577194.86     13538404.55
#Sta/Elev= 30
  3227.5  167.12  3233.5  166.64  3238.8  168.76  3288.9  162.77  3342.5   161.7
  3443.6  158.95  3520.7   158.3  3814.2  156.49  3850.6  158.59  3881.7  156.86
  3945.2  156.78  4262.8  160.24  4334.2  159.57    4602  153.72  4617.3  153.34
  4759.1  150.37  4941.4  150.06  4989.9  149.98  5007.5  146.41  5007.9  145.91
  5012.4  146.41    5020  146.72    5030  150.02  5043.6  150.17  5351.1   149.6
  5456.3  151.01  5550.3  152.72  5742.4  157.32  5983.2  166.43  6133.9  170.18
#Mann= 12 ,-1 , 0
  3227.5     .07       0  3342.5     .05       0  3443.6     .07       0
  3520.7     .05       0  4334.2     .07       0    4602     .05       0
  4617.3     .07       0  4941.4     .05       0  5007.5     .05       0
  5012.4     .05       0  5456.3     .07       0  5550.3     .05       0
Bank Sta=5007.5,5012.4
XS Rating Curve= 0 ,0
Exp/Cntr=0.3,0.1

Type RM Length L Ch R = 1 ,5365    ,525,525,525
BEGIN DESCRIPTION:
Mapping XS deedb0ef
END DESCRIPTION:
XS GIS Cut Line= 3
      2579720.89     13537394.14      2578496.97     13537883.71
      2577194.86     13538222.26
#Sta/Elev= 30
  3706.8   165.5  3774.4  162.29  3971.6  155.68    4144  152.52  4181.5  153.61
  4255.2  151.62    4426  149.57  4504.1  150.92  4617.9  149.15  4671.7  149.08
  4689.9  149.92  4718.9  149.19  4904.8  148.29  4940.8  148.67  4988.8   148.9
  5003.1  145.52  5003.5  145.02    5008  145.52    5013  147.37  5018.4  146.95
    5025  147.95  5068.4  149.56  5099.4  149.74  5141.8  147.96    5497  148.38
    5740  151.72  5887.2  154.69  6127.4  161.55  6241.6  165.36  6370.4  168.05
#Mann= 11 ,-1 , 0
  3706.8     .05       0  4181.5    .035       0  4255.2     .05       0
  4718.9      .1       0  4904.8    .035       0  4940.8      .1       0
  5003.1     .05       0    5008      .1       0  5141.8     .05       0
    5497     .07       0  6127.4     .05       0
Bank Sta=5003.1,5008
XS Rating Curve= 0 ,0
Exp/Cntr=0.3,0.1

Type RM Length L Ch R = 1 ,4840    ,305,305,305
BEGIN DESCRIPTION:
Mapping XS 1a26a763
END DESCRIPTION:
XS GIS Cut Line= 3
      2579061.43      13536949.8      2578178.41     13537633.65
      2577275.46     13538018.73
#Sta/Elev= 30
  3877.4  162.01    4007  160.08  4039.1  158.32  4077.6  156.21  4085.8  157.58
  4106.6  157.25  4127.4  155.19  4210.2  153.15  4366.8   149.2  4469.7  147.52
  4657.6  147.14  4712.3   147.6  4747.6   144.8  4762.1  146.31    4833  147.81
  4845.7  147.82  4890.7  148.29    4955  146.13  4988.4     147  5009.3  144.29
  5009.8  143.79  5015.5  144.29  5084.2  147.72  5192.4  149.53  5300.3   151.3
    5599  157.25  5758.3  162.13  5878.4  164.81  5879.6  164.78  5975.9  166.42
#Mann= 16 ,-1 , 0
  3877.4     .12       0  4039.1    .035       0  4210.2     .12       0
  4366.8     .07       0  4657.6      .1       0    4833    .035       0
  4845.7     .12       0  4988.4     .07       0  5009.3     .05       0
  5015.5     .07       0  5084.2     .05       0  5192.4     .12       0
  5300.3     .07       0  5758.3     .05       0  5878.4     .07       0
  5879.6     .05       0
Bank Sta=5009.3,5015.5
XS Rating Curve= 0 ,0
Exp/Cntr=0.3,0.1

Type RM Length L Ch R = 1 ,4535    ,477,477,477
BEGIN DESCRIPTION:
TRIB 10 TO SPRING CREEK 4.0
END DESCRIPTION:
XS GIS Cut Line= 3
        2578925.       13536875.        2578125.       13537375.
      2577524.96     13537575.01
#Sta/Elev= 30
  4056.2  163.43  4079.2  161.37    4137  160.01    4193  157.03  4374.6  150.74
  4462.5  149.29    4499  147.69    4546  147.46    4578  146.52  4666.5  146.95
  4681.8  145.98    4752  145.43  4775.5  146.25  4846.3  144.92    4907  146.71
  4928.3  147.46  4976.6  146.24  4991.9  144.95  4993.5  143.88    4994  143.38
  4999.7  143.88  5022.1  145.92  5062.8  148.17  5109.3  148.74  5231.3  151.63
    5336   154.1  5440.6  156.38  5451.7  156.92  5545.2  158.69  5632.1  161.07
#Mann= 14 ,-1 , 0
  4056.2    .035       0    4193     .12       0    4546     .07       0
  4681.8      .1       0    4907     .12       0  4993.5     .05       0
  4999.7     .12       0  5022.1     .07       0  5109.3     .12       0
  5231.3     .07       0    5336     .05       0  5440.6     .07       0
  5451.7     .05       0  5545.2     .07       0
Bank Sta=4993.5,4999.7
XS Rating Curve= 0 ,0
Exp/Cntr=0.3,0.1

Type RM Length L Ch R = 1 ,4058    ,416,416,416
BEGIN DESCRIPTION:
TRIB 10 TO SPRING CREEK 3.0
END DESCRIPTION:
XS GIS Cut Line= 3
      2578974.98     13536725.01        2578175.       13536975.
      2577524.96     13537375.03
#Sta/Elev= 30
  4161.9  164.43  4163.1  164.43  4183.4  165.08  4257.1  161.55  4280.8  161.81
  4345.7   157.5  4423.8  155.56  4497.1  151.77    4560  149.65  4591.4  150.11
  4623.8  149.12  4675.2  148.22    4681   147.3  4855.6  145.33  4926.7  144.92
  4968.6  145.88  4983.8   145.6  4989.6  143.85  4994.2  143.76  4994.7  143.26
  5000.6  143.76  5058.7  145.63  5117.5  145.34  5129.6  146.93  5181.7  149.63
  5197.1  148.02  5218.4   147.7  5345.6  150.33  5659.1  156.45  5763.3  159.02
#Mann= 9 ,-1 , 0
  4161.9     .12       0  4163.1    .035       0  4257.1     .12       0
  4623.8     .07       0  4855.6     .12       0  4994.2     .05       0
  5000.6     .12       0  5345.6     .07       0  5659.1     .05       0
Bank Sta=4994.2,5000.6
XS Rating Curve= 0 ,0
Exp/Cntr=0.3,0.1

Type RM Length L Ch R = 1 ,3642    ,1666,1666,1666
BEGIN DESCRIPTION:
TRIB 10 TO SPRING CREEK 2.0
END DESCRIPTION:
XS GIS Cut Line= 3
      2578724.97     13535825.03        2577975.       13536625.
        2577525.     13537324.99
#Sta/Elev= 30
  3898.1  162.96  3967.2  159.37  4004.3  158.81  4032.6  156.26  4075.1  155.59
  4244.6  148.94  4280.3  148.83    4379  145.19  4414.6  145.83  4472.8  144.76
    4486  144.48  4617.7  143.55  4715.6   143.2  4716.1   142.7  4722.1   143.2
  4749.4  144.23  4794.1  144.23  4845.9  144.82    4924   143.4  4959.2  144.95
  4987.6  143.39  5044.5  144.97  5059.7  144.09  5089.7  145.63  5210.9  146.77
  5444.1  152.23    5667  155.03  5701.2   155.8  5816.4  158.88  5826.8  158.66
#Mann= 12 ,-1 , 0
  3898.1     .07       0  3967.2     .12       0  4472.8     .05       0
    4486     .12       0  4617.7     .05       0  4715.6     .05       0
  4722.1     .05       0  4749.4      .1       0  4794.1     .12       0
    5667     .07       0  5701.2     .12       0  5816.4     .05       0
Bank Sta=4715.6,4722.1
XS Rating Curve= 0 ,0
Exp/Cntr=0.3,0.1

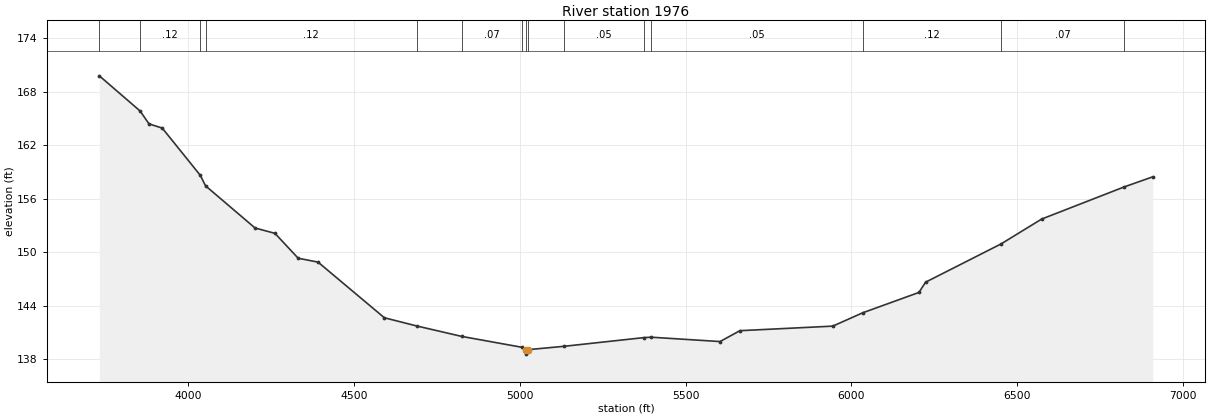
Type RM Length L Ch R = 1 ,1976    ,0,0,0
BEGIN DESCRIPTION:
TRIB 10 TO SPRING CREEK 1.0
END DESCRIPTION:
XS GIS Cut Line= 4
      2578714.71     13535242.93      2577561.89     13535249.88
      2577360.51     13535485.99      2577354.84     13537200.21
#Sta/Elev= 30
  3731.8  169.77  3854.9  165.82  3881.5  164.38  3921.5  163.91  4036.3  158.61
  4052.2  157.43  4201.5   152.7  4261.5   152.1  4331.5  149.31  4391.5  148.87
  4591.5  142.63  4689.1  141.71  4824.6  140.54  5007.5  139.31  5017.8  139.05
  5018.3  138.55  5024.6  139.05  5134.1  139.43  5373.7   140.4  5395.8  140.45
    5604  139.96    5664  141.18    5944  141.69  6034.6  143.19    6204  145.47
    6224  146.62  6451.5  150.91    6574   153.7  6823.2  157.31  6909.2  158.44
#Mann= 15 ,-1 , 0
  3731.8     .07       0  3854.9     .12       0  4036.3     .07       0
  4052.2     .12       0  4689.1     .05       0  4824.6     .07       0
  5007.5     .05       0  5017.8     .05       0  5024.6     .05       0
  5134.1     .05       0  5373.7      .1       0  5395.8     .05       0
  6034.6     .12       0  6451.5     .07       0  6823.2     .05       0
Bank Sta=5017.8,5024.6
XS Rating Curve= 0 ,0
Exp/Cntr=0.3,0.1

Chan Stop Cuts=-1
Use User Specified Reach Order=0
Composite Channel Slope=5