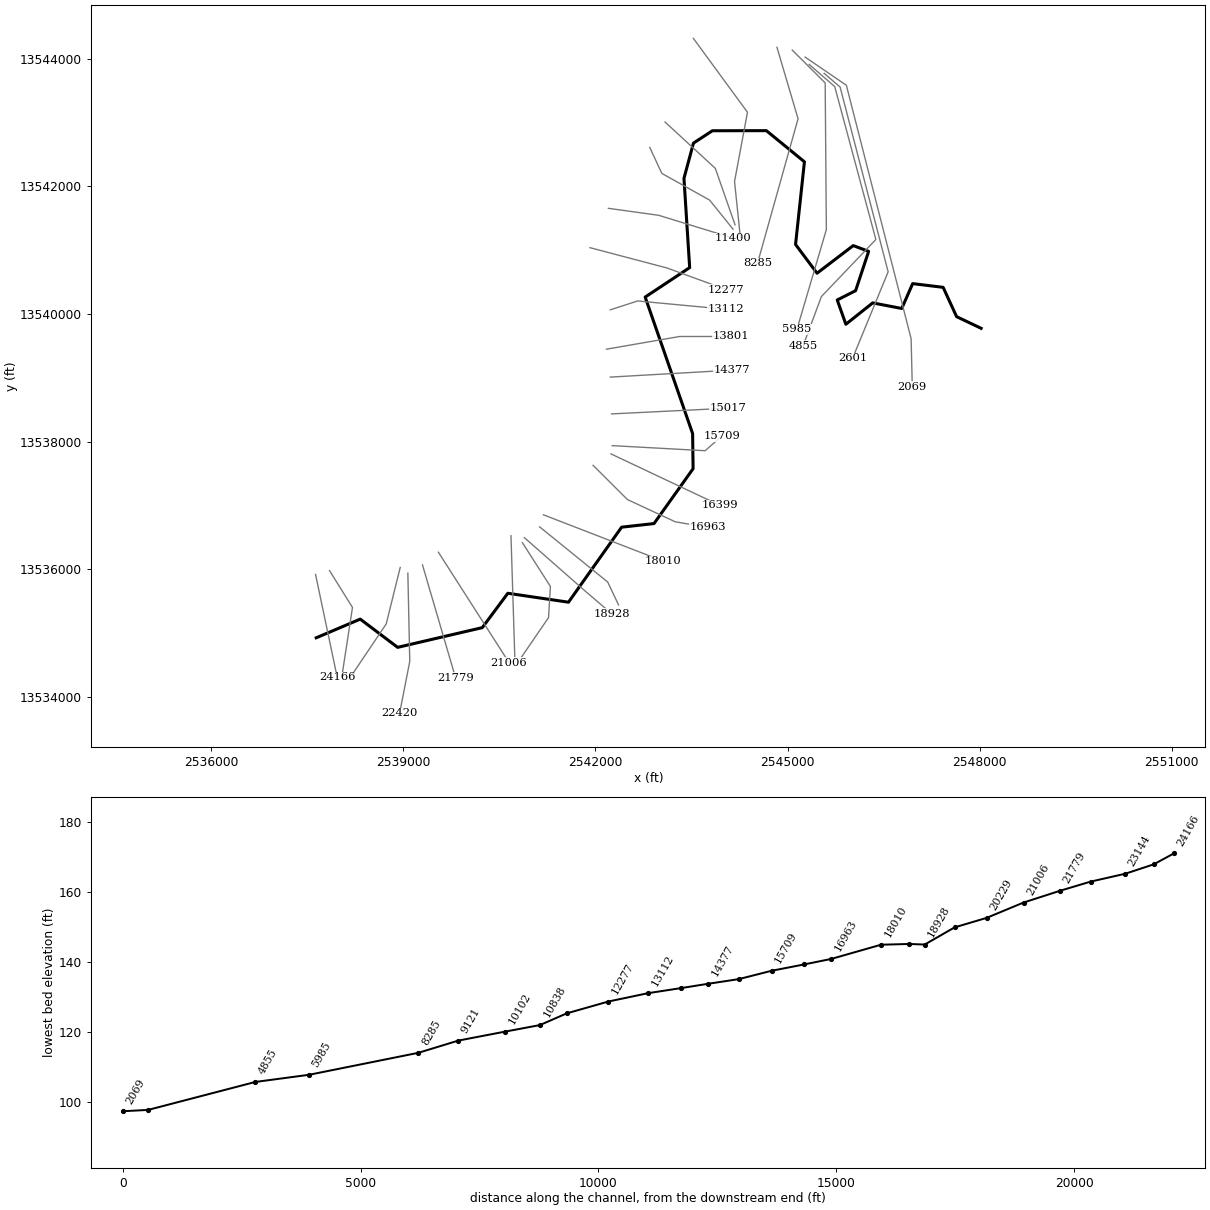
--- TRIB 11 TO GUADALUPE RIVER.prj (project) ---

Proj Title=TRIB 11 TO GUADALUPE RIVER Base Level Engineering
Current Plan=p01
Default Exp/Contr=0.3,0.1
English Units
Geom File=g01
Flow File=f01
Plan File=p01
Y Axis Title=Elevation
X Axis Title(PF)=Main Channel Distance
X Axis Title(XS)=Station
BEGIN DESCRIPTION:
TRIB 11 TO GUADALUPE RIVER
END DESCRIPTION:
DSS Export Rating Curves= 0
DSS Export Rating Curve Sorted= 0
DSS Export Volume Flow Curves= 0
DXF OffsetX= 0
DXF OffsetY= 0
DXF ScaleX= 1
DXF ScaleY= 10

--- TRIB 11 TO GUADALUPE RIVER.p01 (plan) ---

Plan Title=Multiple Run
Short Identifier=Multiple
Geom File=g01
Flow File=f01
Subcritical Flow
K Sum by GR= 0
Std Step Tol= 0.01
Critical Tol= 0.01
Num of Std Step Trials= 20
Max Error Tol= 0.3
Flow Tol Ratio= 0.001
Split Flow NTrial= 30
Split Flow Tol= 0.02
Split Flow Ratio= 0.02
Log Output Level= 0
Friction Slope Method= 1
Unsteady Friction Slope Method= 2
Unsteady Bridges Friction Slope Method= 1
Parabolic Critical Depth
Global Vel Dist=  1 , 1 , 1
Global Log Level= 0
CheckData=True
Encroach Param= -1, 0, 0, 0
BEGIN DESCRIPTION:
Multiple Run
END DESCRIPTION:

--- TRIB 11 TO GUADALUPE RIVER.f01 (steady flow) ---

Flow Title=Multiple
Number of Profiles=7
Profile Names=10-year,25-year,50-year,1pct_min,100-year,1pct_plu,500-year
River Rch & RM= TRIB 11 TO GUADA,Reach-1,24166
     935    1529    2073    1360    2714    5414    4597
River Rch & RM= TRIB 11 TO GUADA,Reach-1,21006
     998    1636    2221    1459    2911    5808    4944
River Rch & RM= TRIB 11 TO GUADA,Reach-1,18928
    1504    2507    3442    2281    4552    9083    7877
River Rch & RM= TRIB 11 TO GUADA,Reach-1,18010
    1784    2996    4132    2750    5486   10947    9571
River Rch & RM= TRIB 11 TO GUADA,Reach-1,15709
    1889    3173    4378    2913    5812   11596   10136
River Rch & RM= TRIB 11 TO GUADA,Reach-1,12277
    2045    3446    4765    3176    6337   12644   11094
River Rch & RM= TRIB 11 TO GUADA,Reach-1,10102
    2194    3708    5137    3430    6845   13657   12026
River Rch & RM= TRIB 11 TO GUADA,Reach-1,9121
    2279    3850    5332    3558    7099   14165   12458
River Rch & RM= TRIB 11 TO GUADA,Reach-1,2601
    2361    3997    5544    3705    7392   14749   13008
Boundary for River Rch & Prof#=TRIB 11 TO GUADA,Reach-1,1
Up Type=0
Dn Type=3
Dn Slope=0.005
Boundary for River Rch & Prof#=TRIB 11 TO GUADA,Reach-1,2
Up Type=0
Dn Type=3
Dn Slope=0.005
Boundary for River Rch & Prof#=TRIB 11 TO GUADA,Reach-1,3
Up Type=0
Dn Type=3
Dn Slope=0.005
Boundary for River Rch & Prof#=TRIB 11 TO GUADA,Reach-1,4
Up Type=0
Dn Type=3
Dn Slope=0.005
Boundary for River Rch & Prof#=TRIB 11 TO GUADA,Reach-1,5
Up Type=0
Dn Type=3
Dn Slope=0.005
Boundary for River Rch & Prof#=TRIB 11 TO GUADA,Reach-1,6
Up Type=0
Dn Type=3
Dn Slope=0.005
Boundary for River Rch & Prof#=TRIB 11 TO GUADA,Reach-1,7
Up Type=0
Dn Type=3
Dn Slope=0.005

--- TRIB 11 TO GUADALUPE RIVER.g01 (geometry) ---

Geom Title=Existing Conditions

River Reach=TRIB 11 TO GUADA,Reach-1
Reach XY= 30
      2537637.68     13534925.00      2538325.10     13535217.68
      2538909.79     13534775.23      2540231.76     13535084.12
      2540630.94     13535622.74      2541578.42     13535482.79
      2542408.25     13536658.55      2542914.49     13536715.19
      2543525.00     13537575.00      2543517.47     13538125.01
      2542776.20     13540264.50      2543471.46     13540726.46
      2543382.33     13542124.90      2543530.73     13542677.55
      2543826.58     13542871.17      2544669.52     13542872.74
      2545264.24     13542384.68      2545125.53     13541088.86
      2545461.26     13540638.38      2546026.56     13541071.26
      2546267.51     13540981.07      2546063.78     13540364.97
      2545776.62     13540218.99      2545911.64     13539838.40
      2546331.04     13540173.38      2546785.00     13540085.96
      2546954.79     13540475.37      2547431.19     13540417.19
      2547641.27     13539957.86      2548025.00     13539775.00

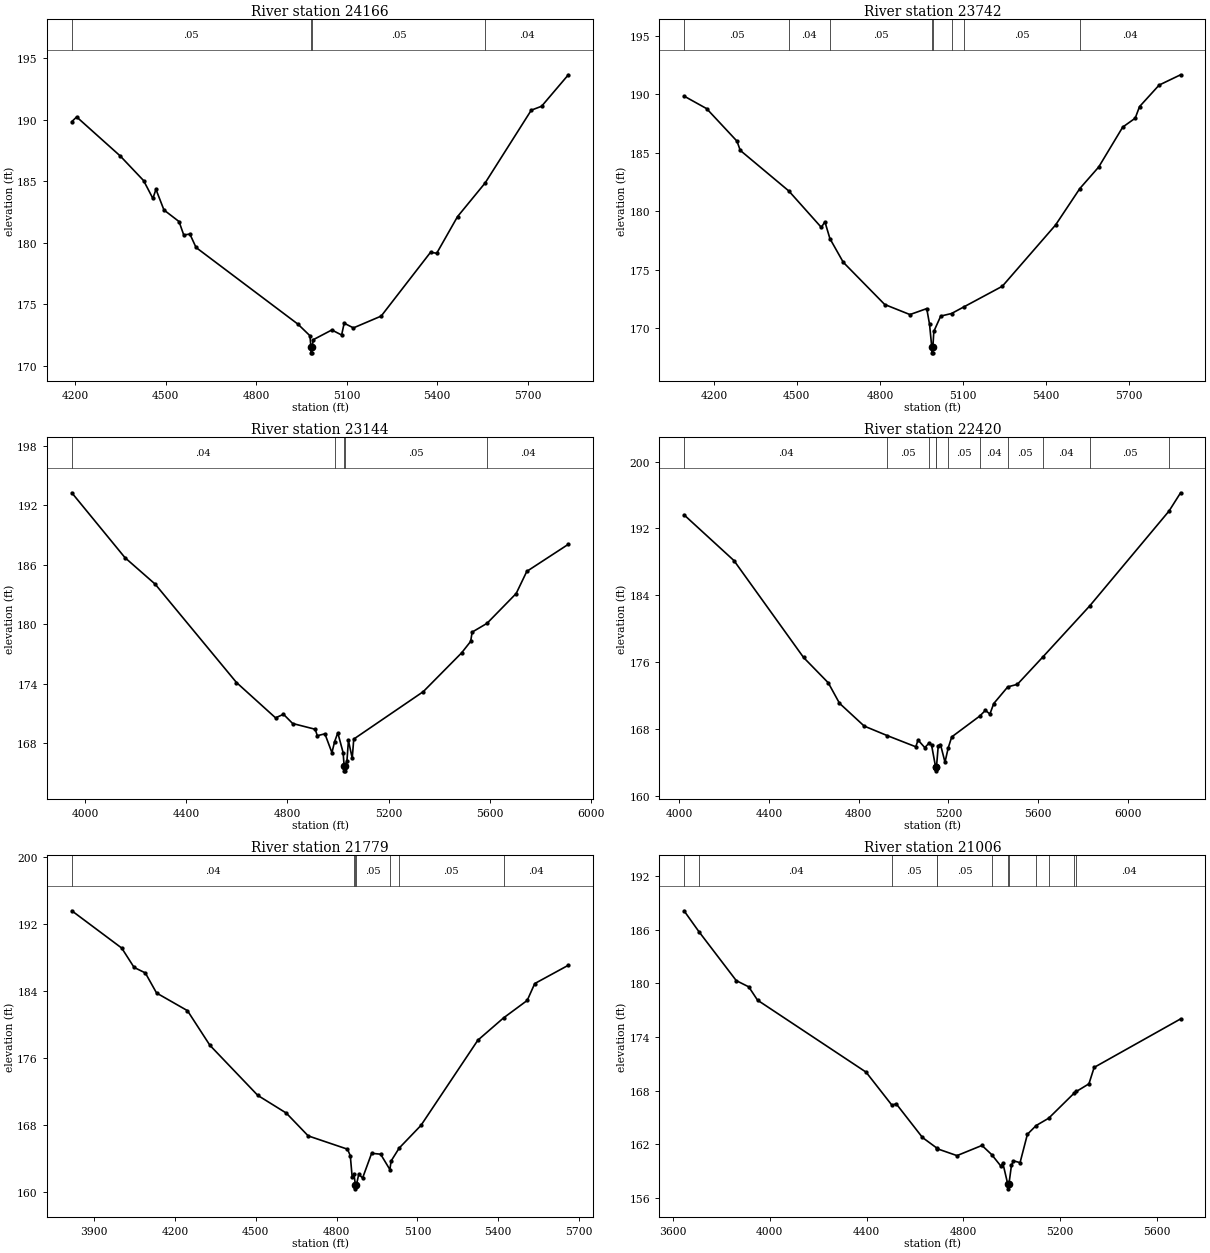
Type RM Length L Ch R = 1,24166,424,424,424
BEGIN DESCRIPTION:
LGII3213
END DESCRIPTION:
XS GIS Cut Line= 2
      2537627.12     13535917.77      2537964.91     13534308.33
#Sta/Elev= 30
  4189.5  189.84  4205.6  190.22  4350.1  187.04  4427.3  185.04  4458.0  183.59
  4468.2  184.33  4494.7  182.65  4544.6  181.71  4560.2  180.62  4580.6  180.69
  4601.0  179.60  4938.6  173.36  4978.2  172.42  4981.3  171.53  4981.6  171.03
  4985.1  171.03  4985.3  171.53  4989.3  172.10  5050.6  172.89  5083.1  172.48
  5091.5  173.44  5122.2  173.06  5214.1  174.02  5377.6  179.21  5398.0  179.13
  5466.9  182.11  5558.4  184.85  5711.2  190.77  5745.4  191.09  5834.0  193.65
#Mann=4,-1,0
  4189.5    0.05       0  4981.3    0.05       0  4985.3    0.05       0
  5558.4    0.04       0
Bank Sta=4981.3,4985.3
Exp/Cntr=0.3,0.1

Type RM Length L Ch R = 1,23742,598,598,598
BEGIN DESCRIPTION:
LGII3212
END DESCRIPTION:
XS GIS Cut Line= 3
      2537845.89     13535977.41      2538203.90     13535400.62
      2538035.09     13534298.43
#Sta/Elev= 30
  4092.4  189.84  4173.9  188.77  4283.6  185.99  4295.5  185.20  4471.0  181.73
  4588.4  178.62  4601.3  179.10  4619.4  177.66  4667.6  175.64  4817.4  172.03
  4908.5  171.17  4969.2  171.68  4979.3  170.35  4987.4  168.40  4987.6  167.90
  4991.1  167.90  4991.4  168.40  4994.8  169.73  5019.7  171.04  5058.7  171.26
  5102.9  171.82  5242.3  173.59  5434.5  178.82  5522.3  181.94  5590.5  183.78
  5677.3  187.19  5722.3  187.95  5738.0  188.94  5808.8  190.78  5886.3  191.66
#Mann=8,-1,0
  4092.4    0.05       0  4471.0    0.04       0  4619.4    0.05       0
  4987.4    0.05       0  4991.4    0.05       0  5058.7    0.12       0
  5102.9    0.05       0  5522.3    0.04       0
Bank Sta=4987.4,4991.4
Exp/Cntr=0.3,0.1

Type RM Length L Ch R = 1,23144,724,724,724
BEGIN DESCRIPTION:
LGII3211
END DESCRIPTION:
XS GIS Cut Line= 3
      2538949.72     13536027.14      2538730.94     13535142.08
      2538145.22     13534268.46
#Sta/Elev= 30
  3947.1  193.24  4157.4  186.70  4276.5  184.04  4598.3  174.12  4752.8  170.56
  4784.1  170.92  4820.4  169.99  4909.5  169.41  4917.9  168.76  4947.9  168.95
  4975.7  167.05  4986.3  168.16  4998.9  169.05  5020.0  167.05  5023.9  165.72
  5024.2  165.22  5027.7  165.22  5028.0  165.72  5035.0  166.20  5041.0  168.28
  5056.0  166.48  5062.0  168.42  5336.9  173.20  5488.2  177.10  5524.2  178.26
  5530.2  179.20  5588.8  180.08  5704.3  183.09  5746.3  185.32  5910.6  188.05
#Mann=5,-1,0
  3947.1    0.04       0  4986.3    0.05       0  5023.9    0.05       0
  5028.0    0.05       0  5588.8    0.04       0
Bank Sta=5023.9,5028
Exp/Cntr=0.3,0.1

Type RM Length L Ch R = 1,22420,641,641,641
BEGIN DESCRIPTION:
LGII3210
END DESCRIPTION:
XS GIS Cut Line= 3
      2539069.04     13535937.57      2539098.87     13534555.37
      2538939.88     13533740.56
#Sta/Elev= 30
  4022.2  193.63  4244.8  188.15  4554.9  176.55  4664.9  173.52  4714.9  171.07
  4825.0  168.34  4928.5  167.19  5055.0  165.86  5065.0  166.67  5095.0  165.76
  5114.0  166.30  5125.0  166.10  5142.9  163.48  5143.2  162.98  5147.2  163.48
  5155.0  165.97  5165.0  166.13  5185.0  164.02  5199.4  165.72  5215.0  167.04
  5340.0  169.54  5365.1  170.22  5385.1  169.78  5402.4  171.04  5464.7  173.03
  5507.7  173.34  5619.6  176.57  5830.4  182.74  6183.3  194.08  6234.9  196.27
#Mann=11,-1,0
  4022.2    0.04       0  4928.5    0.05       0  5114.0    0.04       0
  5142.9    0.05       0  5147.2    0.04       0  5199.4    0.05       0
  5340.0    0.04       0  5464.7    0.05       0  5619.6    0.04       0
  5830.4    0.05       0  6183.3    0.04       0
Bank Sta=5142.9,5147.2
Exp/Cntr=0.3,0.1

Type RM Length L Ch R = 1,21779,773,773,773
BEGIN DESCRIPTION:
LGII3209
END DESCRIPTION:
XS GIS Cut Line= 2
      2539297.76     13536066.86      2539814.40     13534298.38
#Sta/Elev= 30
  3817.5  193.62  4002.8  189.16  4048.6  186.85  4090.3  186.19  4132.0  183.79
  4246.6  181.68  4329.9  177.54  4507.6  171.55  4613.2  169.44  4694.6  166.71
  4840.4  165.12  4850.8  164.34  4857.8  161.77  4864.7  162.10  4869.5  160.88
  4869.8  160.38  4873.8  160.88  4882.1  162.12  4896.5  161.68  4930.0  164.63
  4963.4  164.52  4997.8  162.68  5002.1  163.70  5032.1  165.25  5112.9  167.96
  5324.1  178.15  5419.3  180.81  5507.2  182.90  5535.2  184.92  5659.9  187.11
#Mann=7,-1,0
  3817.5    0.04       0  4864.7    0.05       0  4869.5    0.04       0
  4873.8    0.05       0  4997.8    0.04       0  5032.1    0.05       0
  5419.3    0.04       0
Bank Sta=4869.5,4873.8
Exp/Cntr=0.3,0.1

Type RM Length L Ch R = 1,21006,777,777,777
BEGIN DESCRIPTION:
LGII3208
END DESCRIPTION:
XS GIS Cut Line= 2
      2539546.35     13536265.78      2540650.06     13534535.65
#Sta/Elev= 30
  3645.6  188.13  3706.9  185.80  3861.4  180.31  3913.1  179.61  3949.4  178.12
  4397.9  170.06  4505.0  166.35  4522.3  166.52  4631.0  162.74  4689.2  161.58
  4692.1  161.48  4773.7  160.71  4876.9  161.85  4916.9  160.83  4955.6  159.52
  4963.2  159.87  4983.8  157.49  4984.1  156.99  4988.2  157.49  4998.7  159.61
  5007.2  160.13  5034.3  159.92  5064.7  163.10  5100.9  164.08  5152.7  164.90
  5258.4  167.72  5267.5  167.90  5319.0  168.75  5340.6  170.59  5697.8  176.02
#Mann=12,-1,0
  3645.6    0.05       0  3706.9    0.04       0  4505.0    0.05       0
  4689.2    0.04       0  4692.1    0.05       0  4916.9    0.04       0
  4983.8    0.04       0  4988.2    0.04       0  5100.9    0.05       0
  5152.7    0.04       0  5258.4    0.05       0  5267.5    0.04       0
Bank Sta=4983.8,4988.2
Exp/Cntr=0.3,0.1

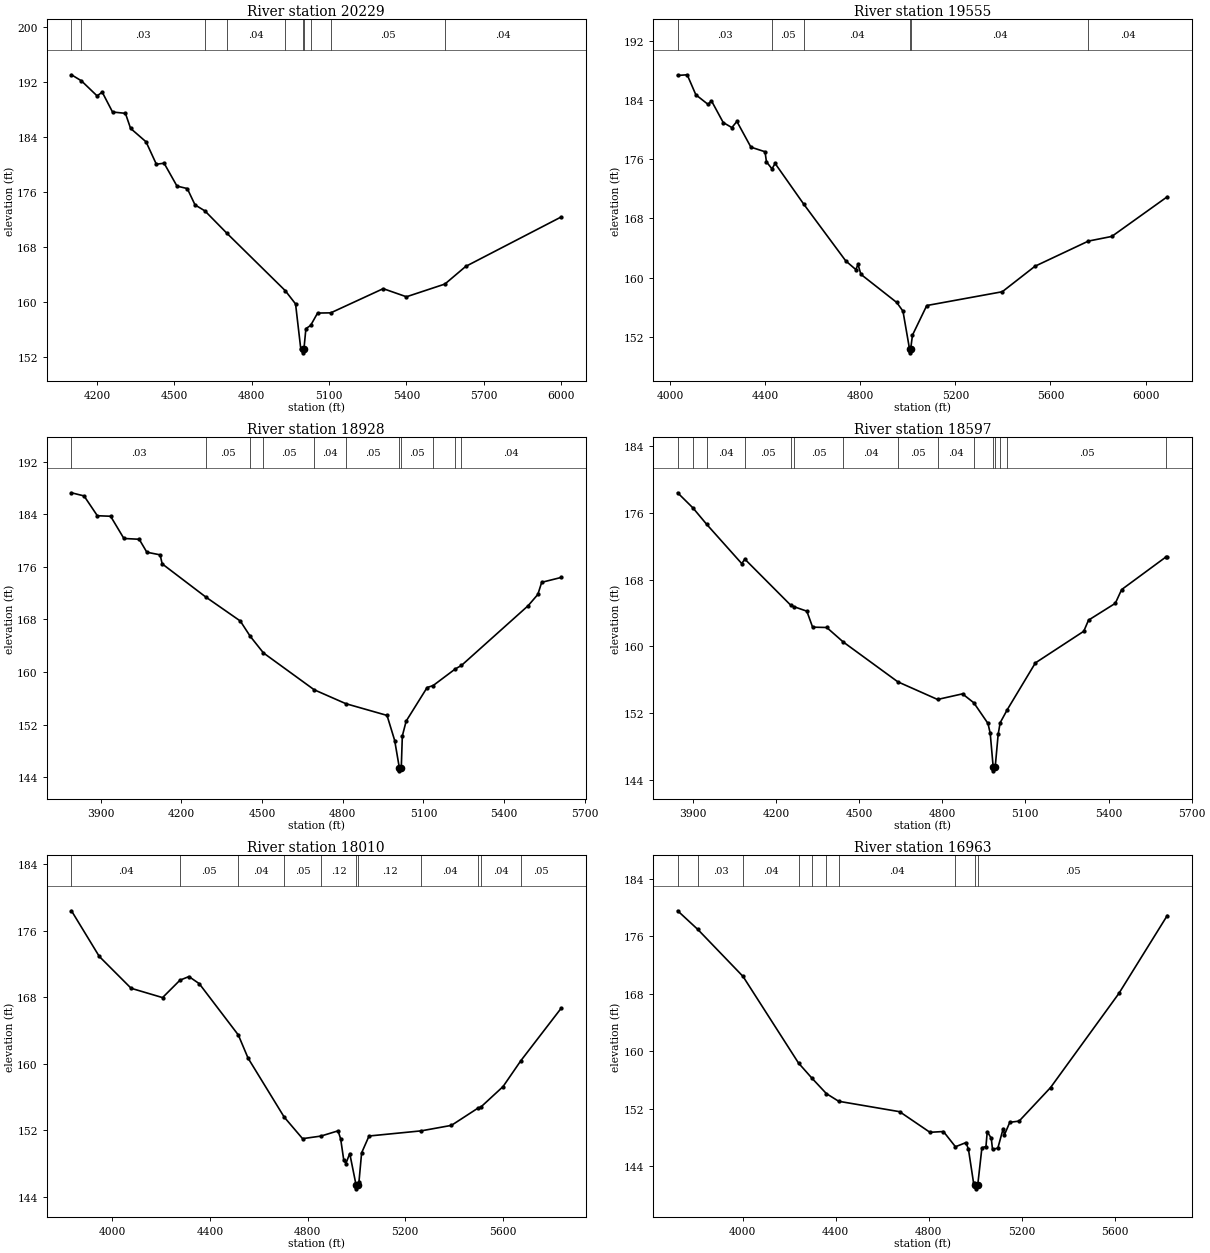
Type RM Length L Ch R = 1,20229,674,674,674
BEGIN DESCRIPTION:
LGII3207
END DESCRIPTION:
XS GIS Cut Line= 2
      2540680.00     13536524.32      2540739.66     13534624.96
#Sta/Elev= 30
  4100.4  193.07  4139.0  192.19  4199.8  190.00  4219.8  190.54  4259.8  187.65
  4309.8  187.46  4329.8  185.27  4389.9  183.31  4429.9  180.05  4459.9  180.20
  4509.9  176.87  4549.9  176.51  4580.0  174.13  4618.3  173.26  4703.5  170.01
  4930.1  161.65  4970.1  159.72  4990.2  153.22  4997.9  153.10  4998.2  152.60
  5002.5  153.10  5010.2  156.12  5028.6  156.59  5055.6  158.39  5106.7  158.42
  5310.3  161.94  5400.4  160.76  5549.6  162.61  5630.5  165.18  6000.7  172.37
#Mann=10,-1,0
  4100.4    0.04       0  4139.0    0.03       0  4618.3    0.05       0
  4703.5    0.04       0  4930.1    0.05       0  4997.9    0.05       0
  5002.5    0.05       0  5028.6    0.12       0  5106.7    0.05       0
  5549.6    0.04       0
Bank Sta=4997.9,5002.5
Exp/Cntr=0.3,0.1

Type RM Length L Ch R = 1,19555,627,627,627
BEGIN DESCRIPTION:
LGII3206
END DESCRIPTION:
XS GIS Cut Line= 4
      2540858.97     13536414.97      2541296.54     13535728.78
      2541266.70     13535241.52      2540839.56     13534615.70
#Sta/Elev= 30
  4031.7  187.29  4072.0  187.38  4108.4  184.68  4160.0  183.38  4174.0  183.87
  4223.5  180.94  4259.9  180.26  4281.0  181.09  4340.0  177.62  4399.3  177.00
  4405.4  175.64  4428.5  174.69  4441.8  175.42  4561.4  169.97  4738.9  162.28
  4781.2  161.11  4790.5  161.80  4802.6  160.47  4953.5  156.67  4979.6  155.50
  5007.3  150.38  5007.6  149.88  5011.9  150.38  5019.6  152.27  5079.7  156.26
  5397.4  158.12  5535.0  161.56  5759.5  164.95  5858.1  165.58  6091.4  170.93
#Mann=6,-1,0
  4031.7    0.03       0  4428.5    0.05       0  4561.4    0.04       0
  5007.3    0.04       0  5011.9    0.04       0  5759.5    0.04       0
Bank Sta=5007.3,5011.9
Exp/Cntr=0.3,0.1

Type RM Length L Ch R = 1,18928,331,331,331
BEGIN DESCRIPTION:
LGII3205
END DESCRIPTION:
XS GIS Cut Line= 3
      2540888.84     13536494.47      2541846.90     13535650.84
      2542259.59     13535297.10
#Sta/Elev= 30
  3791.5  187.27  3838.3  186.79  3887.7  183.78  3937.0  183.70  3986.4  180.32
  4043.3  180.20  4071.7  178.23  4121.1  177.83  4128.7  176.46  4290.7  171.42
  4419.0  167.77  4456.0  165.44  4505.2  162.91  4693.7  157.31  4811.7  155.19
  4964.5  153.41  4993.0  149.59  5010.1  145.48  5010.6  144.98  5017.5  145.48
  5021.4  150.28  5035.6  152.54  5113.5  157.65  5135.9  157.95  5218.7  160.49
  5241.2  161.01  5488.9  170.09  5525.1  171.81  5539.4  173.65  5611.6  174.39
#Mann=11,-1,0
  3791.5    0.03       0  4290.7    0.05       0  4456.0    0.04       0
  4505.2    0.05       0  4693.7    0.04       0  4811.7    0.05       0
  5010.1    0.05       0  5017.5    0.05       0  5135.9    0.04       0
  5218.7    0.05       0  5241.2    0.04       0
Bank Sta=5010.1,5017.5
Exp/Cntr=0.3,0.1

Type RM Length L Ch R = 1,18597,587,587,587
BEGIN DESCRIPTION:
LGII3204
END DESCRIPTION:
XS GIS Cut Line= 3
      2541127.51     13536663.52      2542191.51     13535798.39
      2542360.29     13535440.97
#Sta/Elev= 30
  3845.4  178.37  3900.7  176.56  3950.5  174.59  4076.7  169.91  4087.9  170.44
  4253.9  164.92  4265.7  164.75  4311.6  164.22  4332.4  162.31  4383.5  162.27
  4442.9  160.54  4639.8  155.78  4783.2  153.67  4873.2  154.34  4914.1  153.27
  4965.2  150.80  4973.2  149.62  4983.8  145.64  4984.3  145.14  4991.3  145.64
  5001.9  149.51  5009.1  150.89  5035.1  152.47  5136.2  158.04  5310.7  161.82
  5327.9  163.15  5424.5  165.16  5447.3  166.80  5606.8  170.69  5612.0  170.64
#Mann=15,-1,0
  3845.4    0.04       0  3900.7    0.03       0  3950.5    0.04       0
  4087.9    0.05       0  4253.9    0.04       0  4265.7    0.05       0
  4442.9    0.04       0  4639.8    0.05       0  4783.2    0.04       0
  4914.1    0.05       0  4983.8    0.05       0  4991.3    0.05       0
  5009.1    0.04       0  5035.1    0.05       0  5606.8    0.04       0
Bank Sta=4983.8,4991.3
Exp/Cntr=0.3,0.1

Type RM Length L Ch R = 1,18010,1047,1047,1047
BEGIN DESCRIPTION:
LGII3203
END DESCRIPTION:
XS GIS Cut Line= 2
      2541187.19     13536852.46      2543056.70     13536126.53
#Sta/Elev= 30
  3832.8  178.40  3946.6  172.91  4077.2  169.07  4205.9  167.95  4277.4  170.05
  4313.9  170.48  4356.1  169.63  4516.2  163.45  4556.2  160.66  4704.0  153.57
  4779.4  150.97  4854.4  151.28  4924.7  151.91  4935.4  150.94  4948.1  148.38
  4956.8  147.98  4972.6  149.18  4998.2  145.43  4998.7  144.93  5006.8  145.43
  5010.5  145.81  5021.2  149.26  5051.6  151.29  5265.5  151.91  5389.0  152.57
  5498.0  154.65  5510.1  154.79  5600.5  157.24  5673.5  160.36  5838.3  166.66
#Mann=11,-1,0
  3832.8    0.04       0  4277.4    0.05       0  4516.2    0.04       0
  4704.0    0.05       0  4854.4    0.12       0  4998.2    0.05       0
  5006.8    0.12       0  5265.5    0.04       0  5498.0    0.05       0
  5510.1    0.04       0  5673.5    0.05       0
Bank Sta=4998.2,5006.8
Exp/Cntr=0.3,0.1

Type RM Length L Ch R = 1,16963,564,564,564
BEGIN DESCRIPTION:
LGII3202
END DESCRIPTION:
XS GIS Cut Line= 4
      2541962.77     13537628.14      2542499.78     13537091.14
      2543245.59     13536743.09      2543761.35     13536653.82
#Sta/Elev= 30
  3720.7  179.58  3807.6  176.98  4002.0  170.44  4240.7  158.38  4297.4  156.31
  4360.4  154.13  4413.4  153.06  4675.5  151.61  4805.9  148.74  4863.9  148.85
  4915.6  146.73  4960.9  147.31  4971.5  146.38  4993.5  141.69  5001.8  141.37
  5002.3  140.87  5011.3  141.37  5029.4  146.59  5046.8  146.76  5052.3  148.83
  5069.6  147.91  5075.1  146.35  5098.0  146.55  5120.9  149.26  5126.4  148.40
  5149.2  150.13  5189.4  150.30  5324.6  154.97  5618.4  168.07  5826.6  178.92
#Mann=10,-1,0
  3720.7    0.04       0  3807.6    0.03       0  4002.0    0.04       0
  4240.7    0.05       0  4297.4    0.04       0  4360.4    0.05       0
  4413.4    0.04       0  4915.6    0.05       0  5001.8    0.05       0
  5011.3    0.05       0
Bank Sta=5001.8,5011.3
Exp/Cntr=0.3,0.1

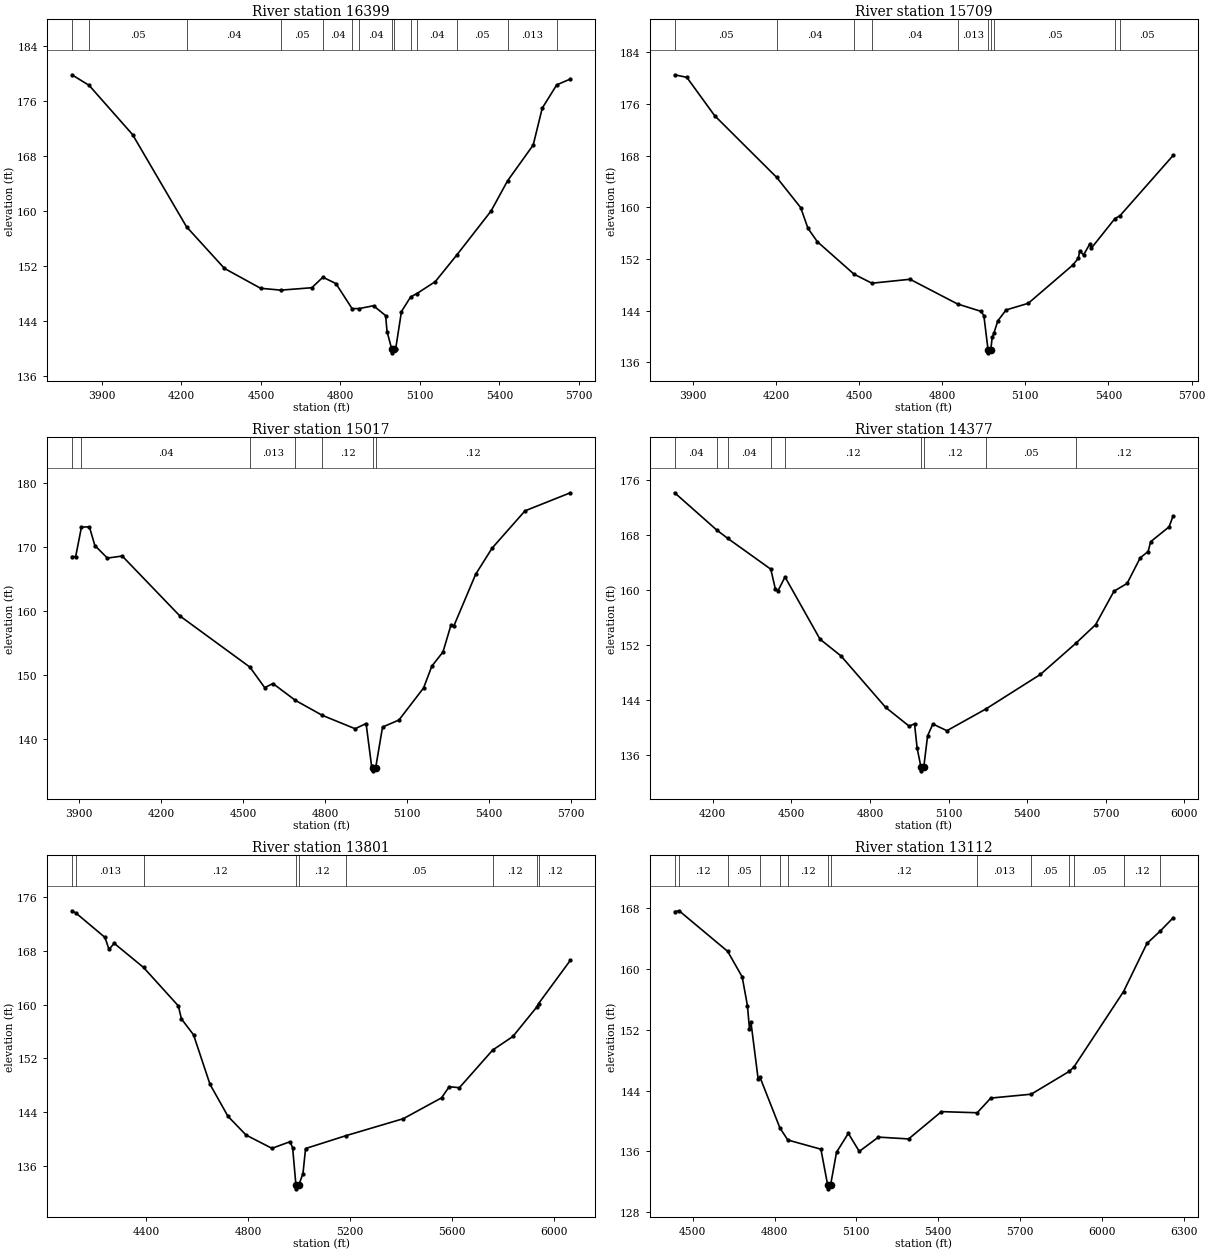
Type RM Length L Ch R = 1,16399,690,690,690
BEGIN DESCRIPTION:
LGII3201
END DESCRIPTION:
XS GIS Cut Line= 2
      2542241.27     13537807.10      2543940.84     13537002.04
#Sta/Elev= 30
  3786.7  179.80  3851.6  178.26  4015.6  171.09  4219.1  157.67  4362.3  151.60
  4498.8  148.71  4574.9  148.44  4691.8  148.79  4733.7  150.32  4782.8  149.40
  4844.0  145.74  4871.2  145.76  4924.8  146.17  4970.3  144.73  4975.8  142.39
  4993.8  139.81  4994.3  139.31  5003.3  139.81  5008.0  139.81  5030.1  145.32
  5064.5  147.44  5088.6  147.95  5157.8  149.68  5238.3  153.53  5368.0  159.95
  5430.3  164.35  5527.2  169.57  5561.3  174.94  5615.9  178.33  5667.3  179.18
#Mann=14,-1,0
  3786.7    0.04       0  3851.6    0.05       0  4219.1    0.04       0
  4574.9    0.05       0  4733.7    0.04       0  4844.0    0.12       0
  4871.2    0.04       0  4993.8    0.04       0  5003.3    0.04       0
  5064.5    0.05       0  5088.6    0.04       0  5238.3    0.05       0
  5430.3   0.013       0  5615.9    0.12       0
Bank Sta=4993.8,5003.3
Exp/Cntr=0.3,0.1

Type RM Length L Ch R = 1,15709,692,692,692
BEGIN DESCRIPTION:
LGII3200
END DESCRIPTION:
XS GIS Cut Line= 3
      2542261.17     13537936.39      2543712.97     13537856.84
      2543970.79     13538084.91
#Sta/Elev= 30
  3834.9  180.53  3878.8  180.13  3978.9  174.21  4203.0  164.64  4289.4  159.97
  4315.8  156.76  4349.5  154.69  4481.9  149.66  4546.3  148.26  4683.9  148.87
  4855.6  145.04  4940.4  143.90  4950.4  143.22  4965.4  137.98  4965.9  137.48
  4975.4  137.98  4980.4  139.87  4987.2  140.60  5000.5  142.42  5030.5  144.12
  5110.6  145.15  5270.9  151.06  5291.3  152.13  5296.0  153.27  5310.2  152.64
  5331.6  154.27  5338.6  153.71  5423.2  158.27  5441.6  158.71  5633.1  168.04
#Mann=10,-1,0
  3834.9    0.05       0  4203.0    0.04       0  4481.9    0.05       0
  4546.3    0.04       0  4855.6   0.013       0  4965.4    0.05       0
  4975.4   0.013       0  4987.2    0.05       0  5423.2    0.12       0
  5441.6    0.05       0
Bank Sta=4965.4,4975.4
Exp/Cntr=0.3,0.1

Type RM Length L Ch R = 1,15017,640,640,640
BEGIN DESCRIPTION:
LGII3199
END DESCRIPTION:
XS GIS Cut Line= 2
      2542251.20     13538433.60      2544070.51     13538523.07
#Sta/Elev= 30
  3874.7  168.52  3888.5  168.53  3909.6  173.12  3938.6  173.17  3958.6  170.25
  4004.3  168.29  4058.7  168.61  4269.0  159.27  4525.1  151.28  4579.3  148.07
  4609.4  148.71  4691.6  146.08  4789.9  143.75  4909.7  141.66  4949.8  142.47
  4969.8  135.85  4974.8  135.59  4975.3  135.09  4984.9  135.59  5009.9  141.92
  5069.9  143.02  5160.0  148.03  5190.1  151.43  5230.8  153.64  5260.2  157.87
  5270.2  157.67  5350.3  165.77  5410.3  169.84  5530.5  175.66  5696.2  178.48
#Mann=7,-1,0
  3874.7    0.05       0  3909.6    0.04       0  4525.1   0.013       0
  4691.6    0.04       0  4789.9    0.12       0  4974.8    0.05       0
  4984.9    0.12       0
Bank Sta=4974.8,4984.9
Exp/Cntr=0.3,0.1

Type RM Length L Ch R = 1,14377,576,576,576
BEGIN DESCRIPTION:
LGII3198
END DESCRIPTION:
XS GIS Cut Line= 2
      2542231.26     13539010.36      2544130.32     13539119.73
#Sta/Elev= 30
  4054.8  174.16  4216.2  168.72  4257.2  167.54  4421.7  163.06  4439.2  160.15
  4449.2  159.92  4475.9  161.93  4609.5  152.89  4689.6  150.46  4859.9  142.99
  4950.0  140.25  4970.1  140.61  4980.1  137.07  4994.9  134.27  4995.4  133.77
  5005.3  134.27  5020.1  138.87  5040.2  140.57  5093.7  139.60  5241.3  142.73
  5450.8  147.78  5585.0  152.27  5661.2  155.00  5731.3  159.86  5781.4  160.99
  5831.5  164.71  5861.5  165.63  5871.5  167.06  5941.7  169.21  5957.0  170.80
#Mann=9,-1,0
  4054.8    0.04       0  4216.2    0.05       0  4257.2    0.04       0
  4421.7   0.013       0  4475.9    0.12       0  4994.9    0.05       0
  5005.3    0.12       0  5241.3    0.05       0  5585.0    0.12       0
Bank Sta=4994.9,5005.3
Exp/Cntr=0.3,0.1

Type RM Length L Ch R = 1,13801,689,689,689
BEGIN DESCRIPTION:
LGII3197
END DESCRIPTION:
XS GIS Cut Line= 3
      2542171.58     13539447.90      2543315.20     13539646.79
      2544110.41     13539646.79
#Sta/Elev= 30
  4108.8  173.98  4125.4  173.62  4238.5  170.01  4254.4  168.22  4274.7  169.13
  4389.9  165.53  4526.5  159.80  4538.6  157.86  4586.1  155.49  4650.8  148.10
  4721.3  143.33  4792.3  140.54  4893.8  138.56  4964.9  139.55  4975.0  138.64
  4988.1  133.02  4988.6  132.52  4998.6  133.02  5015.6  134.80  5025.8  138.53
  5184.5  140.45  5409.4  142.98  5559.4  146.09  5589.4  147.75  5629.4  147.60
  5760.0  153.21  5839.4  155.24  5932.3  159.59  5940.1  160.14  6064.8  166.59
#Mann=9,-1,0
  4108.8    0.04       0  4125.4   0.013       0  4389.9    0.12       0
  4988.1    0.05       0  4998.6    0.12       0  5184.5    0.05       0
  5760.0    0.12       0  5932.3    0.03       0  5940.1    0.12       0
Bank Sta=4988.1,4998.6
Exp/Cntr=0.3,0.1

Type RM Length L Ch R = 1,13112,835,835,835
BEGIN DESCRIPTION:
LGII3196
END DESCRIPTION:
XS GIS Cut Line= 3
      2542231.33     13540064.46      2542658.89     13540203.66
      2544030.57     13540074.45
#Sta/Elev= 30
  4433.9  167.53  4450.1  167.63  4628.1  162.30  4681.4  158.94  4700.7  155.15
  4708.1  152.12  4713.3  153.04  4740.0  145.50  4746.1  145.80  4819.8  139.08
  4848.6  137.50  4970.0  136.29  4994.8  131.58  4995.3  131.08  5005.5  131.58
  5027.3  135.89  5070.5  138.37  5110.7  136.00  5181.0  137.88  5291.5  137.64
  5412.0  141.23  5543.0  141.08  5592.8  143.01  5741.0  143.52  5880.6  146.52
  5897.7  147.10  6079.6  157.01  6165.3  163.33  6213.6  164.95  6261.3  166.70
#Mann=14,-1,0
  4433.9    0.05       0  4450.1    0.12       0  4628.1    0.05       0
  4746.1    0.12       0  4819.8    0.05       0  4848.6    0.12       0
  4994.8    0.05       0  5005.5    0.12       0  5543.0   0.013       0
  5741.0    0.05       0  5880.6    0.04       0  5897.7    0.05       0
  6079.6    0.12       0  6213.6    0.05       0
Bank Sta=4994.8,5005.5
Exp/Cntr=0.3,0.1

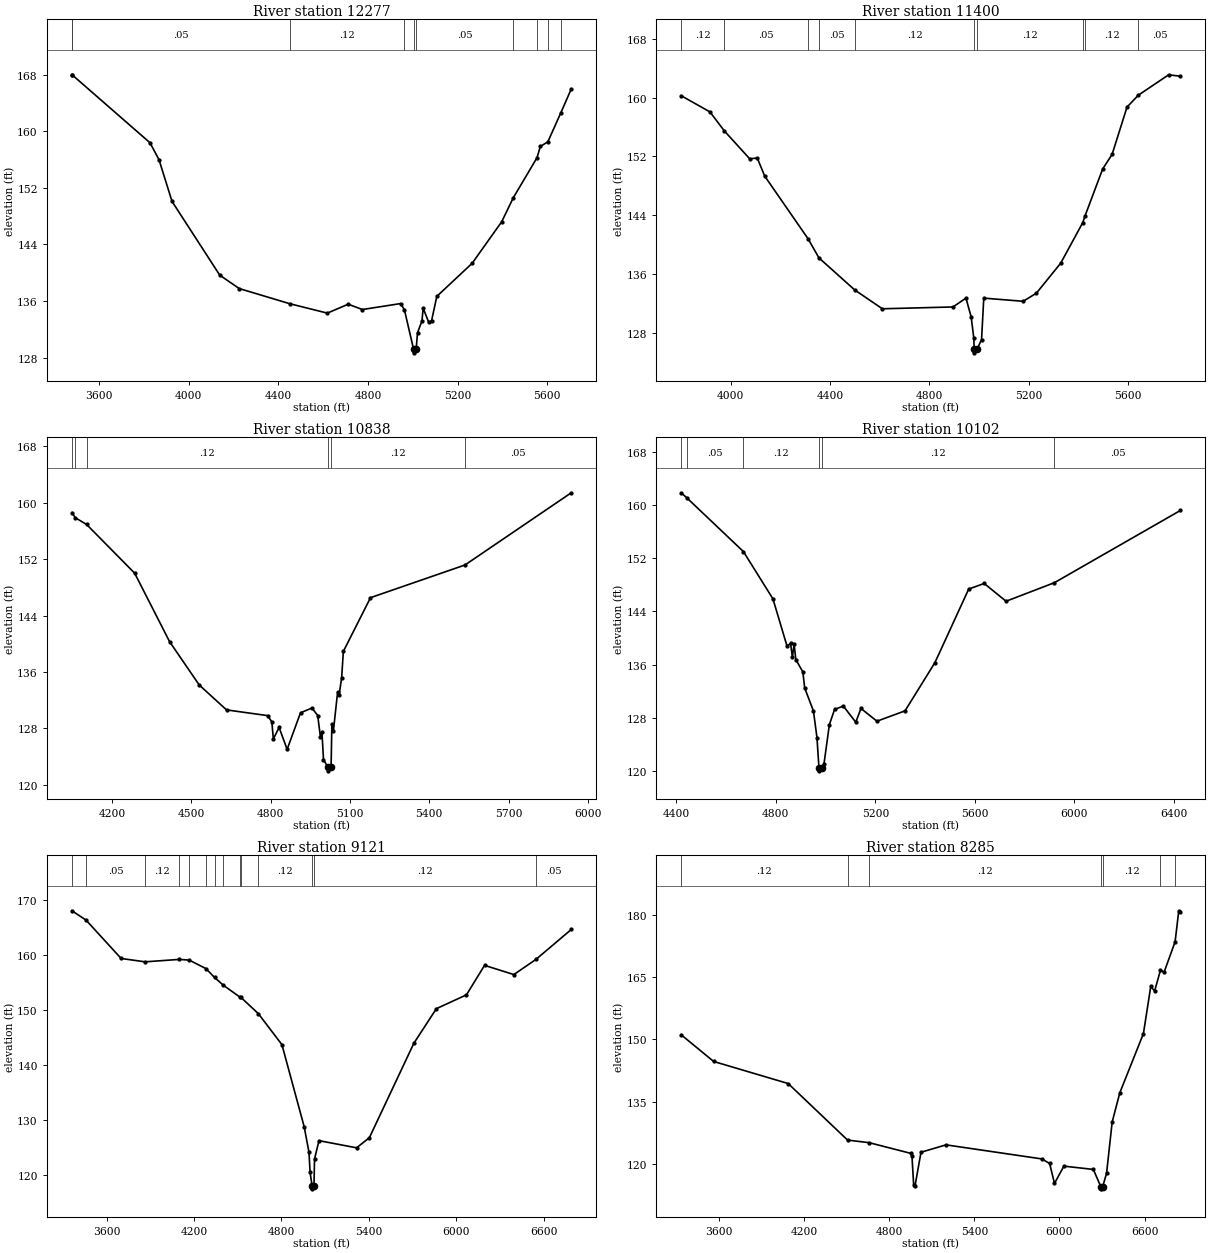
Type RM Length L Ch R = 1,12277,877,877,877
BEGIN DESCRIPTION:
LGII3195
END DESCRIPTION:
XS GIS Cut Line= 3
      2541913.12     13541038.96      2543116.32     13540720.76
      2544040.53     13540382.88
#Sta/Elev= 30
  3478.8  167.97  3479.3  167.97  3827.0  158.37  3867.3  155.98  3925.5  150.08
  4138.6  139.66  4225.5  137.77  4452.2  135.62  4618.6  134.30  4711.7  135.56
  4775.2  134.81  4945.6  135.65  4962.7  134.77  5003.6  129.19  5004.1  128.69
  5015.2  129.19  5021.1  131.53  5041.0  133.20  5046.3  135.00  5071.5  132.98
  5084.0  133.24  5107.4  136.67  5265.0  141.34  5396.7  147.20  5449.0  150.62
  5554.8  156.27  5569.3  157.84  5602.8  158.50  5660.6  162.58  5707.4  165.97
#Mann=10,-1,0
  3478.8   0.013       0  3479.3    0.05       0  4452.2    0.12       0
  4962.7    0.05       0  5003.6    0.05       0  5015.2    0.05       0
  5449.0   0.013       0  5554.8    0.05       0  5602.8    0.04       0
  5660.6    0.05       0
Bank Sta=5003.6,5015.2
Exp/Cntr=0.3,0.1

Type RM Length L Ch R = 1,11400,562,562,562
BEGIN DESCRIPTION:
LGII3194
END DESCRIPTION:
XS GIS Cut Line= 3
      2542201.49     13541655.51      2542987.05     13541546.13
      2544150.29     13541188.21
#Sta/Elev= 30
  3801.0  160.27  3917.1  158.06  3974.4  155.50  4077.2  151.68  4107.4  151.80
  4137.7  149.32  4311.9  140.82  4355.9  138.21  4499.9  133.85  4611.3  131.29
  4895.4  131.54  4947.7  132.74  4968.7  130.18  4979.1  127.34  4980.9  125.80
  4981.4  125.30  4992.5  125.80  5010.5  127.11  5019.4  132.74  5177.9  132.31
  5231.2  133.41  5329.3  137.50  5418.1  143.02  5426.2  143.84  5498.0  150.30
  5536.0  152.28  5596.1  158.72  5641.9  160.34  5763.8  163.11  5811.2  162.91
#Mann=10,-1,0
  3801.0    0.12       0  3974.4    0.05       0  4311.9    0.12       0
  4355.9    0.05       0  4499.9    0.12       0  4980.9    0.05       0
  4992.5    0.12       0  5418.1    0.05       0  5426.2    0.12       0
  5641.9    0.05       0
Bank Sta=4980.9,4992.5
Exp/Cntr=0.3,0.1

Type RM Length L Ch R = 1,10838,736,736,736
BEGIN DESCRIPTION:
LGII3193
END DESCRIPTION:
XS GIS Cut Line= 4
      2542847.82     13542610.18      2543036.77     13542202.44
      2543782.58     13541784.79      2544149.18     13541329.01
#Sta/Elev= 30
  4048.0  158.60  4061.0  157.88  4103.5  156.93  4285.2  150.02  4417.4  140.30
  4529.7  134.14  4632.9  130.61  4788.3  129.80  4804.2  128.92  4810.0  126.49
  4831.7  128.12  4862.1  125.01  4912.7  130.20  4956.1  130.88  4977.8  129.81
  4988.0  126.79  4993.8  127.48  4999.7  123.54  5016.8  122.46  5017.3  121.96
  5028.4  122.46  5031.4  128.63  5037.1  127.60  5053.1  133.14  5058.8  132.72
  5068.4  135.20  5074.8  138.91  5177.5  146.54  5535.0  151.18  5937.1  161.43
#Mann=6,-1,0
  4048.0    0.12       0  4061.0    0.05       0  4103.5    0.12       0
  5016.8    0.05       0  5028.4    0.12       0  5535.0    0.05       0
Bank Sta=5016.8,5028.4
Exp/Cntr=0.3,0.1

Type RM Length L Ch R = 1,10102,981,981,981
BEGIN DESCRIPTION:
LGII3192
END DESCRIPTION:
XS GIS Cut Line= 3
      2543086.48     13543007.92      2543872.08     13542282.00
      2544180.18     13541397.46
#Sta/Elev= 30
  4419.7  161.81  4441.4  161.09  4669.9  152.99  4788.6  145.89  4845.3  138.79
  4859.4  139.21  4866.8  137.11  4873.6  139.12  4880.6  136.78  4908.8  134.92
  4916.1  132.52  4951.3  129.07  4965.5  125.08  4973.4  120.58  4973.9  120.08
  4985.8  120.58  4993.8  121.14  5015.4  127.02  5036.3  129.30  5071.5  129.80
  5121.4  127.38  5142.4  129.44  5206.5  127.53  5319.3  129.08  5439.5  136.32
  5575.2  147.36  5637.4  148.20  5725.3  145.53  5919.7  148.32  6426.0  159.16
#Mann=6,-1,0
  4419.7    0.12       0  4441.4    0.05       0  4669.9    0.12       0
  4973.4    0.05       0  4985.8    0.12       0  5919.7    0.05       0
Bank Sta=4973.4,4985.8
Exp/Cntr=0.3,0.1

Type RM Length L Ch R = 1,9121,836,836,836
BEGIN DESCRIPTION:
LGII3191
END DESCRIPTION:
XS GIS Cut Line= 4
      2543528.75     13544319.43      2544374.67     13543160.90
      2544172.38     13542075.89      2544264.33     13541193.16
#Sta/Elev= 30
  3362.9  167.96  3459.5  166.27  3700.3  159.31  3864.4  158.70  4100.0  159.14
  4167.6  159.01  4282.6  157.47  4341.1  155.86  4402.2  154.44  4514.5  152.32
  4521.8  152.26  4641.4  149.31  4803.4  143.68  4956.0  128.80  4989.1  124.16
  4996.7  120.51  5010.7  118.02  5011.2  117.52  5023.3  118.02  5027.2  122.95
  5057.7  126.26  5315.5  124.96  5403.6  126.80  5708.7  143.93  5863.0  150.20
  6069.5  152.71  6193.6  158.06  6394.6  156.39  6545.9  159.13  6788.6  164.57
#Mann=14,-1,0
  3362.9    0.12       0  3459.5    0.05       0  3864.4    0.12       0
  4100.0    0.05       0  4167.6    0.12       0  4282.6    0.05       0
  4341.1    0.12       0  4402.2    0.05       0  4514.5    0.12       0
  4521.8    0.05       0  4641.4    0.12       0  5010.7    0.05       0
  5023.3    0.12       0  6545.9    0.05       0
Bank Sta=5010.7,5023.3
Exp/Cntr=0.3,0.1

Type RM Length L Ch R = 1,8285,2300,2300,2300
BEGIN DESCRIPTION:
Mapping XS 365a6a95
END DESCRIPTION:
XS GIS Cut Line= 3
      2544834.97     13544179.06      2545164.84     13543059.24
      2544531.15     13540793.58
#Sta/Elev= 30
  3332.7  151.11  3561.9  144.68  4087.5  139.37  4506.0  125.77  4658.8  125.14
  4951.0  122.58  4959.9  122.00  4971.8  115.08  4982.1  114.84  5023.7  122.84
  5200.2  124.62  5875.2  121.24  5930.5  120.14  5964.7  115.34  6030.9  119.50
  6238.6  118.71  6291.5  114.54  6292.0  114.04  6304.3  114.54  6332.0  117.80
  6371.4  130.12  6425.5  137.17  6591.6  151.38  6643.6  162.77  6670.4  161.60
  6711.9  166.65  6737.0  166.12  6815.0  173.47  6840.8  180.93  6852.7  180.59
#Mann=7,-1,0
  3332.7    0.12       0  4506.0    0.05       0  4658.8    0.12       0
  6291.5    0.05       0  6304.3    0.12       0  6711.9   0.013       0
  6815.0    0.05       0
Bank Sta=6291.5,6304.3
Exp/Cntr=0.3,0.1

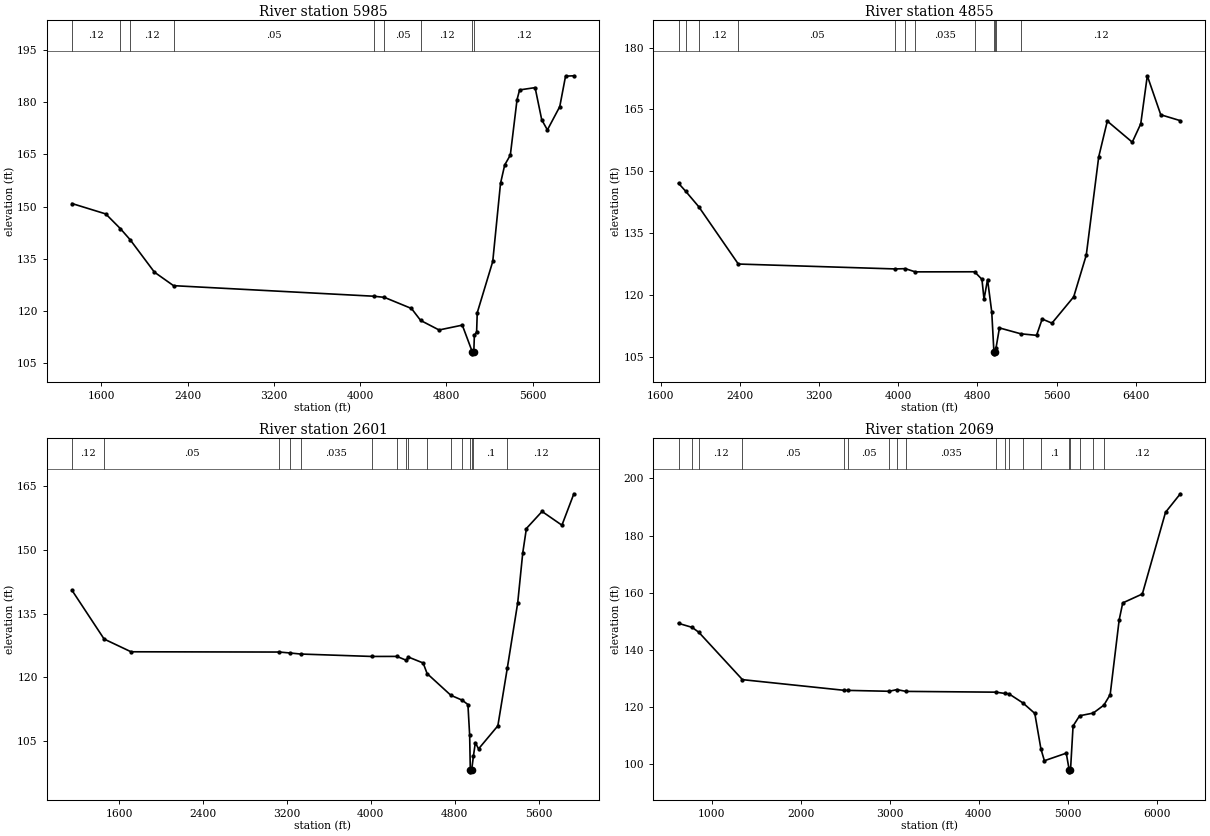
Type RM Length L Ch R = 1,5985,1130,1130,1130
BEGIN DESCRIPTION:
LGII3190
END DESCRIPTION:
XS GIS Cut Line= 4
      2545073.48     13544135.57      2545588.40     13543620.65
      2545606.79     13541321.91      2545147.24     13539759.41
#Sta/Elev= 30
  1327.5  150.89  1640.1  147.91  1774.7  143.72  1866.3  140.51  2091.4  131.20
  2269.0  127.32  4126.7  124.29  4225.3  123.96  4476.4  120.77  4561.5  117.34
  4732.4  114.60  4948.1  115.99  5041.7  108.25  5042.2  107.75  5054.8  108.25
  5060.1  113.02  5081.0  114.06  5086.8  119.55  5230.6  134.26  5302.6  156.66
  5341.5  161.96  5393.7  164.80  5456.2  180.76  5479.8  183.51  5623.6  184.17
  5685.1  174.94  5737.6  172.02  5852.3  178.71  5906.1  187.46  5983.2  187.57
#Mann=9,-1,0
  1327.5    0.12       0  1774.7    0.05       0  1866.3    0.12       0
  2269.0    0.05       0  4126.7   0.013       0  4225.3    0.05       0
  4561.5    0.12       0  5041.7    0.05       0  5054.8    0.12       0
Bank Sta=5041.7,5054.8
Exp/Cntr=0.3,0.1

Type RM Length L Ch R = 1,4855,2254,2254,2254
BEGIN DESCRIPTION:
Mapping XS 41fe3b90
END DESCRIPTION:
XS GIS Cut Line= 5
      2545338.48     13543909.92      2545737.76     13543562.72
      2546380.12     13541166.88      2545529.42     13540272.79
      2545242.96     13539500.20
#Sta/Elev= 30
  1780.9  147.08  1854.5  145.11  1985.0  141.40  2384.6  127.49  3969.6  126.30
  4070.9  126.37  4172.2  125.59  4771.0  125.61  4845.0  123.78  4866.1  118.96
  4901.7  123.73  4944.1  115.86  4965.9  106.20  4966.4  105.70  4979.0  106.20
  4987.0  107.08  5021.8  111.99  5237.6  110.56  5396.7  110.19  5453.4  114.15
  5552.2  113.15  5771.7  119.53  5898.7  129.65  6024.2  153.47  6111.1  162.17
  6363.2  157.06  6448.9  161.51  6515.1  173.17  6651.0  163.71  6848.6  162.28
#Mann=12,-1,0
  1780.9    0.12       0  1854.5    0.05       0  1985.0    0.12       0
  2384.6    0.05       0  3969.6   0.013       0  4070.9    0.05       0
  4172.2   0.035       0  4771.0    0.12       0  4965.9    0.05       0
  4979.0    0.12       0  4987.0    0.05       0  5237.6    0.12       0
Bank Sta=4965.9,4979
Exp/Cntr=0.3,0.1

Type RM Length L Ch R = 1,2601,532,532,532
BEGIN DESCRIPTION:
Mapping XS 4a719afe
END DESCRIPTION:
XS GIS Cut Line= 4
      2545571.96     13543771.05      2545821.96     13543555.77
      2546571.96     13540659.94      2546016.40     13539305.77
#Sta/Elev= 30
  1151.5  140.49  1457.3  129.02  1713.8  126.02  3128.1  125.96  3229.2  125.74
  3330.3  125.49  4009.2  124.92  4249.7  124.93  4339.7  124.00  4356.3  124.80
  4499.3  123.38  4537.1  120.88  4763.6  115.76  4871.4  114.61  4926.3  113.58
  4942.9  106.31  4949.0   98.21  4949.5   97.71  4962.3   98.21  4979.2  101.50
  4997.0  104.60  5027.6  103.12  5211.7  108.56  5302.5  122.27  5401.2  137.59
  5449.2  149.36  5483.9  155.09  5633.2  159.11  5822.7  155.87  5936.5  163.28
#Mann=16,-1,0
  1151.5    0.12       0  1457.3    0.05       0  3128.1   0.013       0
  3229.2    0.05       0  3330.3   0.035       0  4009.2    0.12       0
  4249.7    0.05       0  4339.7    0.12       0  4356.3    0.05       0
  4537.1    0.12       0  4763.6    0.05       0  4871.4    0.12       0
  4949.0    0.05       0  4962.3    0.12       0  4979.2     0.1       0
  5302.5    0.12       0
Bank Sta=4949,4962.3
Exp/Cntr=0.3,0.1

Type RM Length L Ch R = 1,2069,0,0,0
BEGIN DESCRIPTION:
LGII3189
END DESCRIPTION:
XS GIS Cut Line= 4
      2545275.75     13544025.24      2545919.42     13543583.87
      2546930.87     13539611.64      2546949.23     13538858.81
#Sta/Elev= 30
   629.1  149.29   781.9  147.88   856.6  146.17  1346.5  129.59  2487.3  125.86
  2531.1  125.83  2994.0  125.52  3080.7  126.11  3181.7  125.48  4191.7  125.21
  4292.7  124.76  4337.1  124.64  4494.7  121.44  4628.0  117.78  4696.7  105.37
  4735.7  101.22  4981.1  103.86  5015.2   97.83  5015.7   97.33  5028.7   97.83
  5057.7  113.38  5131.1  116.95  5283.8  117.89  5403.6  120.67  5474.1  124.35
  5575.2  150.51  5615.2  156.44  5835.3  159.57  6095.4  188.14  6261.6  194.63
#Mann=19,-1,0
   629.1    0.12       0   781.9    0.05       0   856.6    0.12       0
  1346.5    0.05       0  2487.3    0.12       0  2531.1    0.05       0
  2994.0   0.013       0  3080.7    0.05       0  3181.7   0.035       0
  4191.7    0.12       0  4292.7    0.05       0  4337.1    0.12       0
  4494.7    0.05       0  4696.7     0.1       0  5015.2    0.05       0
  5028.7     0.1       0  5131.1    0.12       0  5283.8     0.1       0
  5403.6    0.12       0
Bank Sta=5015.2,5028.7
Exp/Cntr=0.3,0.1

Chan Stop Cuts=-1