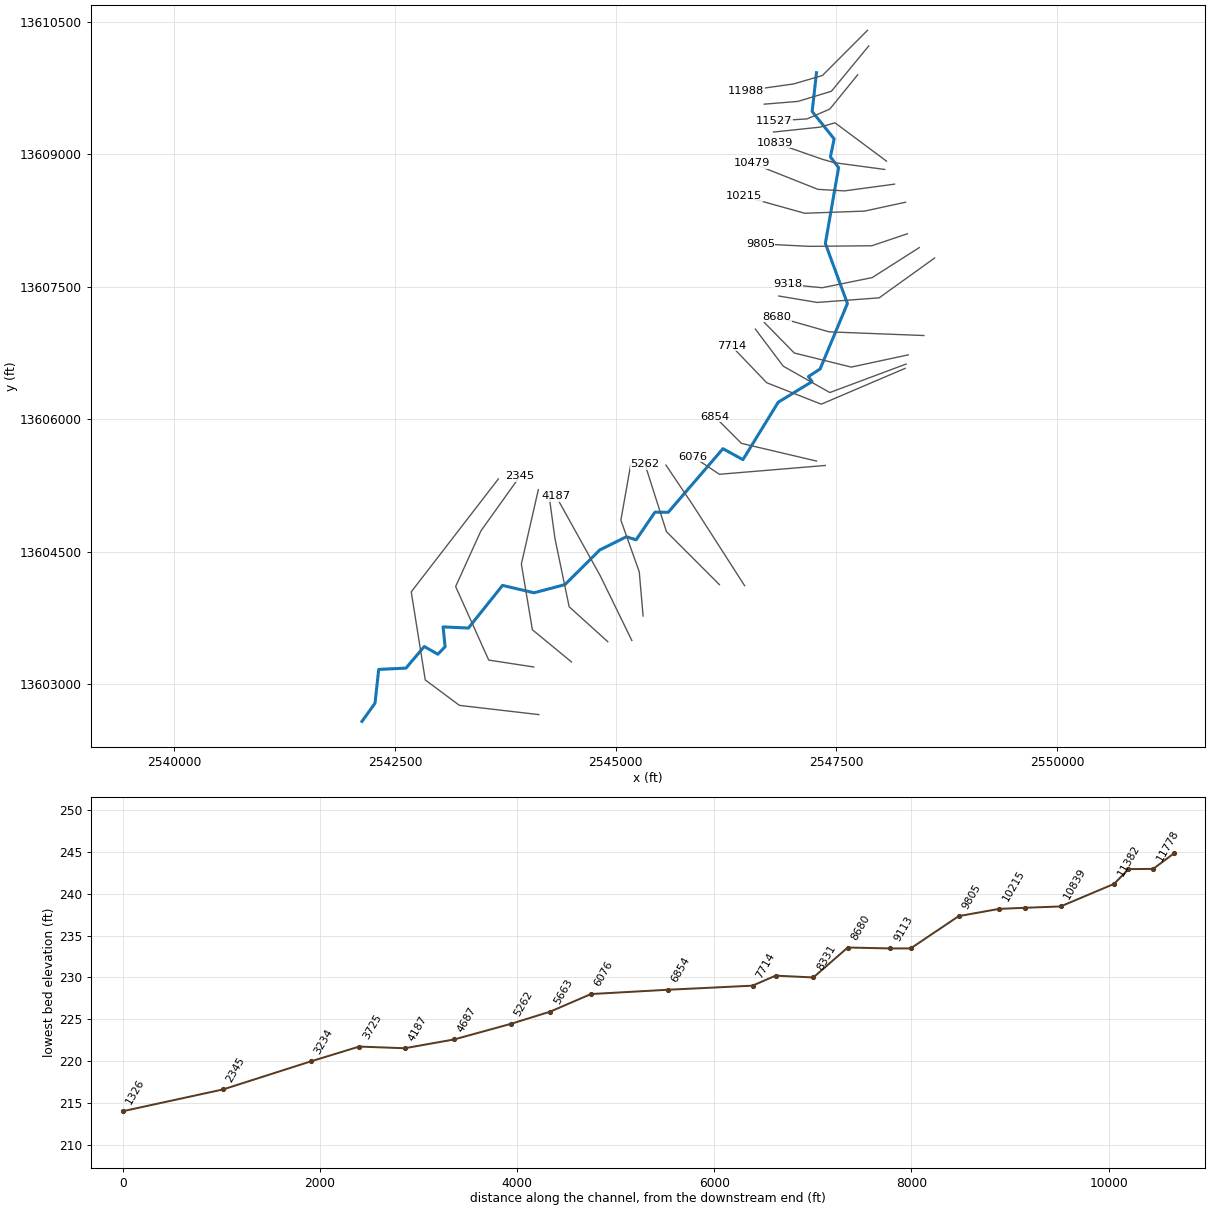
--- TRIB 11 TO IRISH CREEK.prj (project) ---

Proj Title=TRIB 11 TO IRISH CREEK Base Level Engineering
Current Plan=p01
Default Exp/Contr=0.3,0.1
English Units
Geom File=g01
Flow File=f01
Plan File=p01
BEGIN DESCRIPTION:
TRIB 11 TO IRISH CREEK
END DESCRIPTION:

--- TRIB 11 TO IRISH CREEK.p01 (plan) ---

Plan Title=Multiple Run
Short Identifier=Multiple
Geom File=g01
Flow File=f01
Subcritical Flow
K Sum by GR= 0
Std Step Tol= 0.01
Critical Tol= 0.01
Num of Std Step Trials= 20
Max Error Tol= 0.3
Flow Tol Ratio= 0.001
Split Flow NTrial= 30
Split Flow Tol= 0.02
Split Flow Ratio= 0.02
Log Output Level= 0
Friction Slope Method= 1
Unsteady Friction Slope Method= 2
Unsteady Bridges Friction Slope Method= 1
Parabolic Critical Depth
Global Vel Dist=  1 , 1 , 1
Global Log Level= 0
CheckData=True
Encroach Param= -1, 0, 0, 0
BEGIN DESCRIPTION:
Multiple Run
END DESCRIPTION:

--- TRIB 11 TO IRISH CREEK.f01 (steady flow) ---

Flow Title=Multiple
Number of Profiles=7
Profile Names=10-year,25-year,50-year,1pct_min,100-year,1pct_plu,500-year
River Rch & RM= TRIB 11 TO IRISH,Reach-1,11988
     508     803    1067     688    1373    2739    2245
River Rch & RM= TRIB 11 TO IRISH,Reach-1,10839
     965    1581    2148    1413    2819    5625    4804
River Rch & RM= TRIB 11 TO IRISH,Reach-1,7949
    1306    2165    2962    1960    3911    7803    6746
River Rch & RM= TRIB 11 TO IRISH,Reach-1,3725
    1645    2764    3815    2544    5076   10127    8897
Boundary for River Rch & Prof#=TRIB 11 TO IRISH,Reach-1,1
Up Type=0
Dn Type=3
Dn Slope=0.005
Boundary for River Rch & Prof#=TRIB 11 TO IRISH,Reach-1,2
Up Type=0
Dn Type=3
Dn Slope=0.005
Boundary for River Rch & Prof#=TRIB 11 TO IRISH,Reach-1,3
Up Type=0
Dn Type=3
Dn Slope=0.005
Boundary for River Rch & Prof#=TRIB 11 TO IRISH,Reach-1,4
Up Type=0
Dn Type=3
Dn Slope=0.005
Boundary for River Rch & Prof#=TRIB 11 TO IRISH,Reach-1,5
Up Type=0
Dn Type=3
Dn Slope=0.005
Boundary for River Rch & Prof#=TRIB 11 TO IRISH,Reach-1,6
Up Type=0
Dn Type=3
Dn Slope=0.005
Boundary for River Rch & Prof#=TRIB 11 TO IRISH,Reach-1,7
Up Type=0
Dn Type=3
Dn Slope=0.005

--- TRIB 11 TO IRISH CREEK.g01 (geometry) ---

Geom Title=Existing Conditions

River Reach=TRIB 11 TO IRISH,Reach-1
Reach XY= 30
      2547275.00     13609925.00      2547226.10     13609485.55
      2547475.00     13609175.00      2547432.80     13608971.59
      2547525.49     13608850.04      2547375.52     13607990.22
      2547625.53     13607309.81      2547315.97     13606567.99
      2547183.62     13606482.04      2547225.00     13606425.00
      2546841.64     13606191.71      2546441.85     13605540.97
      2546215.32     13605664.83      2545595.03     13604944.30
      2545444.63     13604945.68      2545231.33     13604632.38
      2545121.60     13604667.17      2544818.84     13604517.12
      2544425.00     13604125.00      2544075.10     13604032.33
      2543718.07     13604115.78      2543331.52     13603632.67
      2543044.27     13603645.68      2543067.02     13603421.64
      2542985.05     13603335.96      2542831.04     13603423.42
      2542623.45     13603178.66      2542314.94     13603164.39
      2542272.74     13602780.94      2542125.00     13602575.00

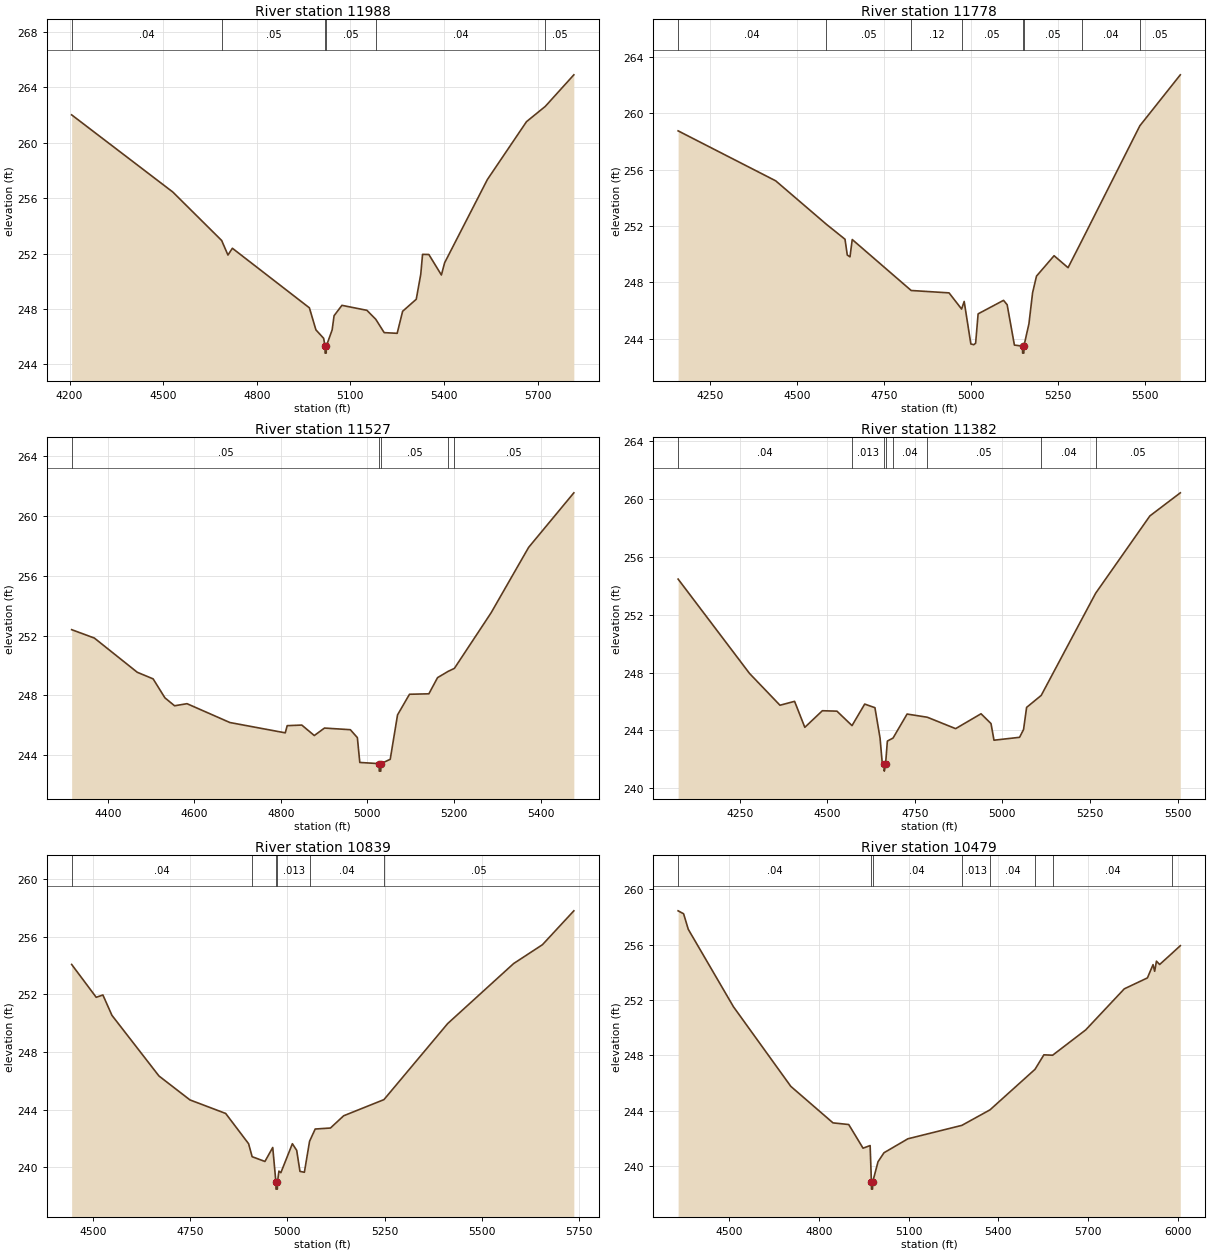
Type RM Length L Ch R = 1,11988,210,210,210
BEGIN DESCRIPTION:
Mapping XS f2b784a0
END DESCRIPTION:
XS GIS Cut Line= 4
      2547853.25     13610405.43      2547342.72     13609893.58
      2547016.43     13609797.77      2546474.79     13609721.38
#Sta/Elev= 30
  4206.5  262.02  4530.8  256.45  4687.5  252.95  4707.6  251.90  4721.8  252.39
  4968.7  248.09  4989.6  246.50  5014.4  245.89  5018.9  245.32  5019.1  244.82
  5022.6  244.82  5022.9  245.32  5041.7  246.50  5047.8  247.52  5073.0  248.27
  5153.1  247.91  5181.6  247.26  5208.5  246.30  5250.1  246.25  5267.6  247.84
  5311.3  248.71  5325.8  250.52  5331.5  251.95  5351.7  251.94  5391.9  250.46
  5402.2  251.34  5539.3  257.35  5664.8  261.53  5724.9  262.63  5816.5  264.91
#Mann=6,-1,0
  4206.5    0.04       0  4687.5    0.05       0  5018.9    0.05       0
  5022.9    0.05       0  5181.6    0.04       0  5724.9    0.05       0
Bank Sta=5018.9,5022.9
Exp/Cntr=0.3,0.1

Type RM Length L Ch R = 1,11778,251,251,251
BEGIN DESCRIPTION:
Mapping XS 38e6cdde
END DESCRIPTION:
XS GIS Cut Line= 4
      2547867.13     13610228.33      2547443.51     13609714.43
      2547065.04     13609599.85      2546683.15     13609568.61
#Sta/Elev= 30
  4158.4  258.76  4439.1  255.21  4585.0  252.12  4638.5  251.06  4645.0  249.94
  4652.8  249.81  4659.3  251.04  4828.8  247.42  4937.8  247.25  4973.9  246.10
  4981.3  246.64  5000.5  243.62  5009.0  243.57  5014.2  243.67  5021.4  245.76
  5094.5  246.72  5104.9  246.41  5125.8  243.54  5149.1  243.47  5149.4  242.97
  5152.9  242.97  5153.1  243.47  5167.6  245.06  5178.1  247.26  5189.3  248.44
  5239.9  249.89  5280.1  249.04  5319.0  250.92  5486.6  259.12  5603.0  262.74
#Mann=8,-1,0
  4158.4    0.04       0  4585.0    0.05       0  4828.8    0.12       0
  4973.9    0.05       0  5149.1    0.05       0  5153.1    0.05       0
  5319.0    0.04       0  5486.6    0.05       0
Bank Sta=5149.1,5153.1
Exp/Cntr=0.3,0.1

Type RM Length L Ch R = 1,11527,145,145,145
BEGIN DESCRIPTION:
Mapping XS 78507b2e
END DESCRIPTION:
XS GIS Cut Line= 4
      2547742.09     13609901.90      2547426.15     13609513.05
      2547169.21     13609401.93      2546790.75     13609377.63
#Sta/Elev= 30
  4316.7  252.40  4369.1  251.84  4468.3  249.55  4504.9  249.11  4532.2  247.84
  4554.5  247.31  4583.2  247.45  4682.3  246.19  4810.2  245.50  4814.7  245.98
  4848.4  246.02  4877.3  245.32  4900.8  245.82  4960.6  245.71  4976.8  245.18
  4982.4  243.52  5027.2  243.44  5027.4  242.94  5030.9  242.94  5031.2  243.44
  5052.7  243.73  5069.6  246.70  5097.2  248.08  5142.0  248.11  5162.0  249.19
  5186.4  249.61  5200.9  249.81  5285.6  253.52  5372.4  257.90  5476.9  261.55
#Mann=5,-1,0
  4316.7    0.05       0  5027.2    0.05       0  5031.2    0.05       0
  5186.4    0.04       0  5200.9    0.05       0
Bank Sta=5027.2,5031.2
Exp/Cntr=0.3,0.1

Type RM Length L Ch R = 1,11382,543,543,543
BEGIN DESCRIPTION:
Mapping XS 779a5a99
END DESCRIPTION:
XS GIS Cut Line= 4
      2548068.51     13608922.77      2547485.07     13609357.18
      2547315.04     13609308.18      2546788.59     13609252.77
#Sta/Elev= 30
  4074.1  254.47  4278.0  247.94  4364.9  245.74  4406.6  246.01  4435.8  244.21
  4485.9  245.36  4527.5  245.33  4570.6  244.33  4606.8  245.82  4636.0  245.57
  4650.6  243.47  4656.9  241.73  4662.4  241.68  4662.7  241.18  4666.4  241.68
  4671.5  243.26  4687.7  243.47  4727.8  245.13  4785.5  244.91  4866.4  244.12
  4938.9  245.15  4967.4  244.47  4975.9  243.32  5048.9  243.52  5060.3  244.06
  5069.0  245.59  5110.7  246.42  5266.1  253.49  5420.9  258.84  5507.8  260.44
#Mann=8,-1,0
  4074.1    0.04       0  4570.6   0.013       0  4662.4    0.05       0
  4666.4   0.013       0  4687.7    0.04       0  4785.5    0.05       0
  5110.7    0.04       0  5266.1    0.05       0
Bank Sta=4662.4,4666.4
Exp/Cntr=0.3,0.1

Type RM Length L Ch R = 1,10839,360,360,360
BEGIN DESCRIPTION:
Mapping XS 0ead9839
END DESCRIPTION:
XS GIS Cut Line= 4
      2548047.64     13608829.02      2547478.23     13608905.41
      2547342.82     13608943.60      2546798.84     13609134.17
#Sta/Elev= 30
  4445.2  254.07  4508.4  251.79  4525.6  251.95  4548.8  250.54  4669.8  246.33
  4749.5  244.67  4841.4  243.73  4900.3  241.63  4909.4  240.73  4942.3  240.40
  4962.4  241.37  4970.5  238.98  4970.8  238.48  4974.3  238.48  4974.6  238.98
  4978.3  239.73  4983.3  239.62  5012.9  241.63  5024.0  241.17  5032.4  239.71
  5043.8  239.65  5057.1  241.80  5071.6  242.65  5110.8  242.72  5144.8  243.57
  5248.4  244.69  5412.4  249.97  5581.9  254.13  5656.1  255.44  5736.8  257.79
#Mann=6,-1,0
  4445.2    0.04       0  4909.4   0.013       0  4970.5    0.03       0
  4974.6   0.013       0  5057.1    0.04       0  5248.4    0.05       0
Bank Sta=4970.5,4974.6
Exp/Cntr=0.3,0.1

Type RM Length L Ch R = 1,10479,264,264,264
BEGIN DESCRIPTION:
Mapping XS 553c1e1e
END DESCRIPTION:
XS GIS Cut Line= 4
      2548158.77     13608662.35      2547592.82     13608585.96
      2547290.73     13608603.32      2546540.76     13608901.92
#Sta/Elev= 30
  4328.3  258.44  4346.6  258.23  4362.4  257.10  4513.7  251.50  4705.5  245.75
  4846.7  243.11  4899.4  242.99  4947.3  241.28  4971.0  241.47  4975.3  238.82
  4975.5  238.32  4979.1  238.32  4979.4  238.82  4997.4  240.30  5017.4  240.95
  5097.5  241.96  5278.1  242.93  5372.1  244.05  5522.8  246.98  5552.6  248.03
  5581.8  248.00  5692.5  249.83  5821.7  252.80  5899.1  253.59  5918.0  254.55
  5923.4  254.07  5929.3  254.80  5940.1  254.56  5982.0  255.38  6009.2  255.92
#Mann=8,-1,0
  4328.3    0.04       0  4975.3    0.04       0  4979.4    0.04       0
  5278.1   0.013       0  5372.1    0.04       0  5522.8    0.05       0
  5581.8    0.04       0  5982.0    0.05       0
Bank Sta=4975.3,4979.4
Exp/Cntr=0.3,0.1

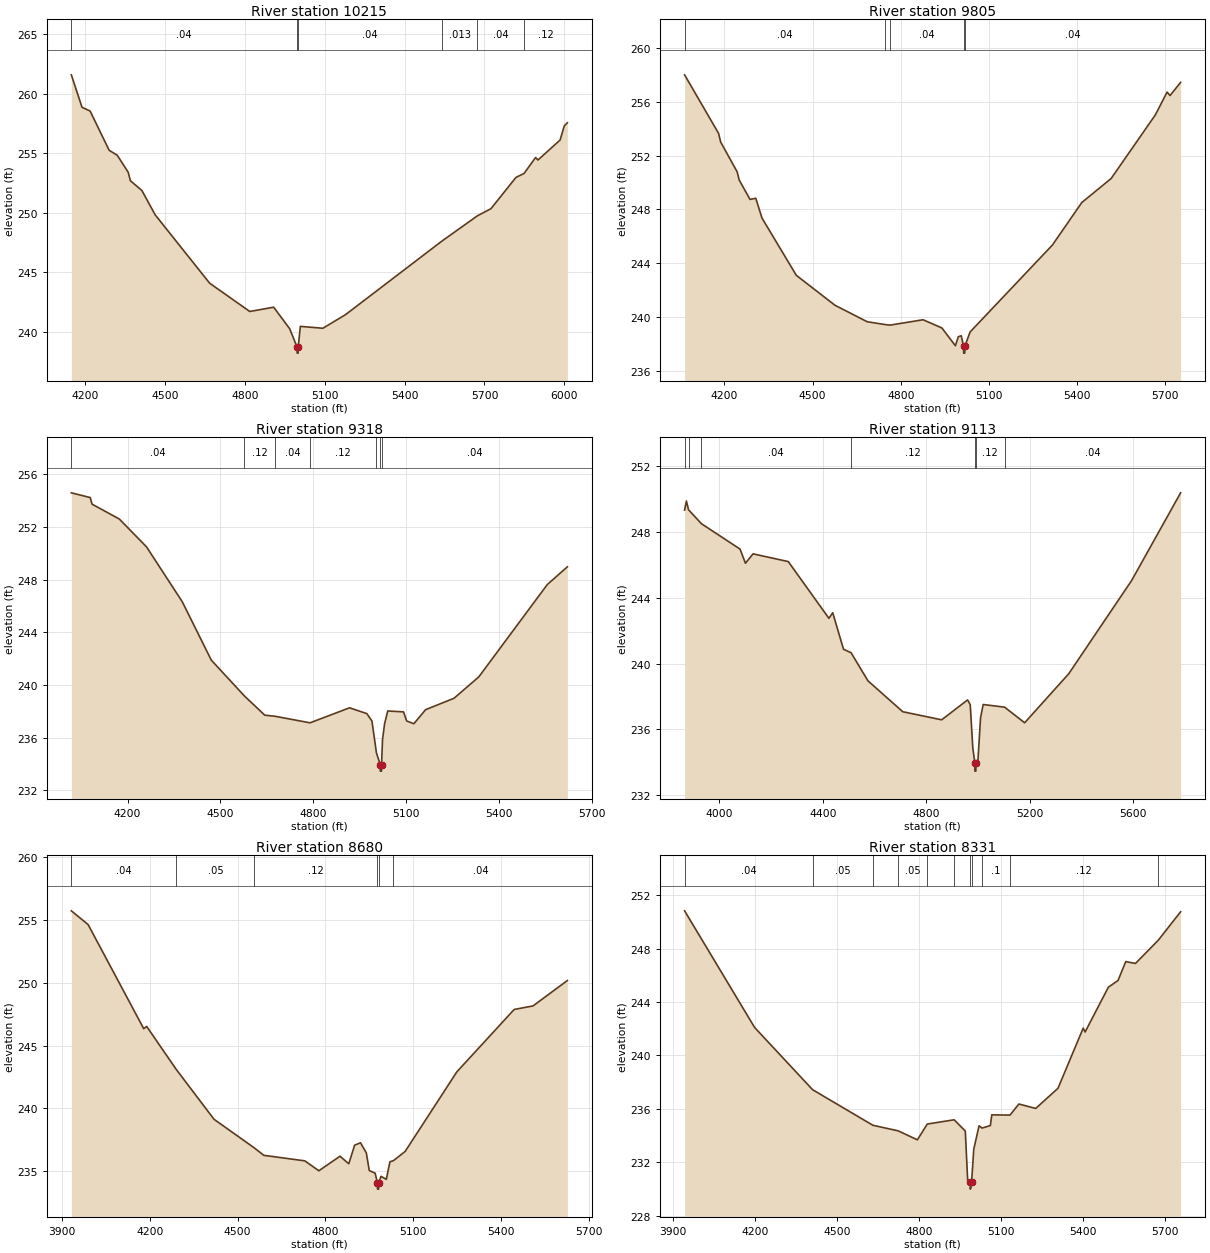
Type RM Length L Ch R = 1,10215,410,410,410
BEGIN DESCRIPTION:
Mapping XS 23bb7c4d
END DESCRIPTION:
XS GIS Cut Line= 4
      2548283.78     13608457.49      2547818.51     13608356.80
      2547141.43     13608332.49      2546458.70     13608523.10
#Sta/Elev= 30
  4148.8  261.58  4188.9  258.85  4219.2  258.54  4290.8  255.24  4321.2  254.82
  4362.4  253.39  4370.4  252.68  4413.6  251.86  4463.7  249.81  4668.4  244.06
  4818.9  241.69  4908.5  242.05  4968.6  240.24  4996.5  238.69  4996.8  238.19
  5000.4  238.19  5000.7  238.69  5008.6  240.44  5093.3  240.28  5178.7  241.43
  5539.8  247.60  5673.5  249.73  5724.3  250.33  5818.3  252.96  5848.6  253.29
  5891.9  254.63  5900.8  254.42  5983.9  256.10  5999.6  257.29  6011.2  257.55
#Mann=6,-1,0
  4148.8    0.04       0  4996.5    0.04       0  5000.7    0.04       0
  5539.8   0.013       0  5673.5    0.04       0  5848.6    0.12       0
Bank Sta=4996.5,5000.7
Exp/Cntr=0.3,0.1

Type RM Length L Ch R = 1,9805,487,487,487
BEGIN DESCRIPTION:
Mapping XS f20e60c3
END DESCRIPTION:
XS GIS Cut Line= 4
      2548304.63     13608099.85      2547901.85     13607964.43
      2547196.98     13607957.49      2546639.01     13607985.22
#Sta/Elev= 30
  4064.2  258.00  4179.9  253.65  4187.2  253.00  4243.2  250.79  4250.2  250.18
  4287.0  248.74  4306.5  248.83  4327.6  247.36  4444.6  243.10  4576.0  240.88
  4686.0  239.65  4748.0  239.44  4763.5  239.40  4876.0  239.80  4940.1  239.19
  4986.0  237.87  4996.0  238.54  5006.0  238.61  5013.9  237.82  5014.2  237.32
  5017.9  237.32  5018.1  237.82  5036.0  238.89  5316.2  245.35  5416.3  248.51
  5516.4  250.30  5666.6  255.02  5706.7  256.72  5716.7  256.46  5752.7  257.44
#Mann=5,-1,0
  4064.2    0.04       0  4748.0    0.12       0  4763.5    0.04       0
  5013.9    0.04       0  5018.1    0.04       0
Bank Sta=5013.9,5018.1
Exp/Cntr=0.3,0.1

Type RM Length L Ch R = 1,9318,205,205,205
BEGIN DESCRIPTION:
Mapping XS cc8d3181
END DESCRIPTION:
XS GIS Cut Line= 4
      2548440.06     13607943.62      2547905.32     13607603.32
      2547339.35     13607488.74      2546950.41     13607526.94
#Sta/Elev= 30
  4018.4  254.60  4079.4  254.24  4085.3  253.74  4173.4  252.61  4261.4  250.49
  4376.6  246.33  4470.5  241.89  4577.4  239.17  4643.2  237.71  4675.7  237.63
  4789.4  237.13  4916.9  238.27  4972.7  237.83  4989.3  237.27  5003.9  234.84
  5016.1  233.96  5016.4  233.46  5020.1  233.46  5020.4  233.96  5023.4  235.84
  5030.1  237.05  5040.3  238.03  5091.3  237.96  5101.5  237.27  5124.8  237.06
  5162.7  238.13  5254.2  238.99  5334.5  240.62  5555.6  247.63  5620.5  248.98
#Mann=7,-1,0
  4018.4    0.04       0  4577.4    0.12       0  4675.7    0.04       0
  4789.4    0.12       0  5003.9    0.04       0  5016.1    0.05       0
  5020.4    0.04       0
Bank Sta=5016.1,5020.4
Exp/Cntr=0.3,0.1

Type RM Length L Ch R = 1,9113,433,433,433
BEGIN DESCRIPTION:
Mapping XS dac0d721
END DESCRIPTION:
XS GIS Cut Line= 4
      2548613.63     13607825.53      2547985.18     13607374.16
      2547283.79     13607322.07      2546848.17     13607394.68
#Sta/Elev= 30
  3865.5  249.33  3872.5  249.88  3880.7  249.35  3930.9  248.50  4080.0  246.96
  4100.9  246.10  4130.3  246.67  4266.6  246.20  4423.8  242.75  4438.5  243.09
  4480.3  240.87  4509.5  240.66  4574.8  238.95  4709.6  237.07  4860.0  236.58
  4960.3  237.79  4970.4  237.50  4980.4  234.87  4988.2  233.96  4988.5  233.46
  4992.2  233.46  4992.5  233.96  5000.4  234.16  5010.4  236.71  5020.5  237.51
  5103.3  237.35  5180.9  236.40  5351.5  239.38  5594.8  245.05  5784.2  250.38
#Mann=7,-1,0
  3865.5    0.12       0  3880.7    0.05       0  3930.9    0.04       0
  4509.5    0.12       0  4988.2    0.05       0  4992.5    0.12       0
  5103.3    0.04       0
Bank Sta=4988.2,4992.5
Exp/Cntr=0.3,0.1

Type RM Length L Ch R = 1,8680,349,349,349
BEGIN DESCRIPTION:
Mapping XS a15862f8
END DESCRIPTION:
XS GIS Cut Line= 3
      2548492.16     13606947.07      2547419.21     13606988.74
      2546822.03     13607158.87
#Sta/Elev= 30
  3931.9  255.72  3989.1  254.63  4179.2  246.34  4189.3  246.52  4290.6  243.09
  4419.4  239.13  4557.1  236.85  4589.6  236.26  4729.7  235.82  4777.6  235.03
  4849.7  236.19  4879.8  235.59  4899.8  237.07  4919.8  237.26  4939.8  236.45
  4949.8  235.05  4969.8  234.84  4977.7  234.07  4978.0  233.57  4981.7  233.57
  4982.0  234.07  4989.9  234.59  5008.0  234.35  5020.4  235.75  5032.0  235.83
  5072.4  236.57  5249.2  242.91  5444.9  247.87  5509.1  248.15  5626.6  250.17
#Mann=6,-1,0
  3931.9    0.04       0  4290.6    0.05       0  4557.1    0.12       0
  4977.7    0.05       0  4982.0    0.12       0  5032.0    0.04       0
Bank Sta=4977.7,4982
Exp/Cntr=0.3,0.1

Type RM Length L Ch R = 1,8331,382,382,382
BEGIN DESCRIPTION:
Mapping XS 57bb133c
END DESCRIPTION:
XS GIS Cut Line= 4
      2548315.06     13606728.33      2547669.21     13606589.43
      2547023.37     13606749.16      2546683.07     13607096.40
#Sta/Elev= 30
  3944.0  250.82  4199.8  242.09  4411.8  237.43  4631.9  234.77  4724.6  234.35
  4794.4  233.68  4830.6  234.86  4928.7  235.18  4969.5  234.34  4978.2  230.63
  4987.8  230.49  4988.1  229.99  4992.4  230.49  5000.4  232.97  5019.7  234.73
  5030.7  234.56  5061.1  234.75  5066.3  235.55  5132.8  235.53  5165.2  236.36
  5226.8  236.03  5308.2  237.54  5400.2  242.04  5407.2  241.75  5492.1  245.10
  5527.5  245.61  5555.8  247.02  5591.1  246.88  5674.5  248.62  5756.1  250.75
#Mann=11,-1,0
  3944.0    0.04       0  4411.8    0.05       0  4631.9    0.12       0
  4724.6    0.05       0  4830.6     0.1       0  4928.7    0.12       0
  4987.8    0.05       0  4992.4    0.12       0  5030.7     0.1       0
  5132.8    0.12       0  5674.5    0.04       0
Bank Sta=4987.8,4992.4
Exp/Cntr=0.3,0.1

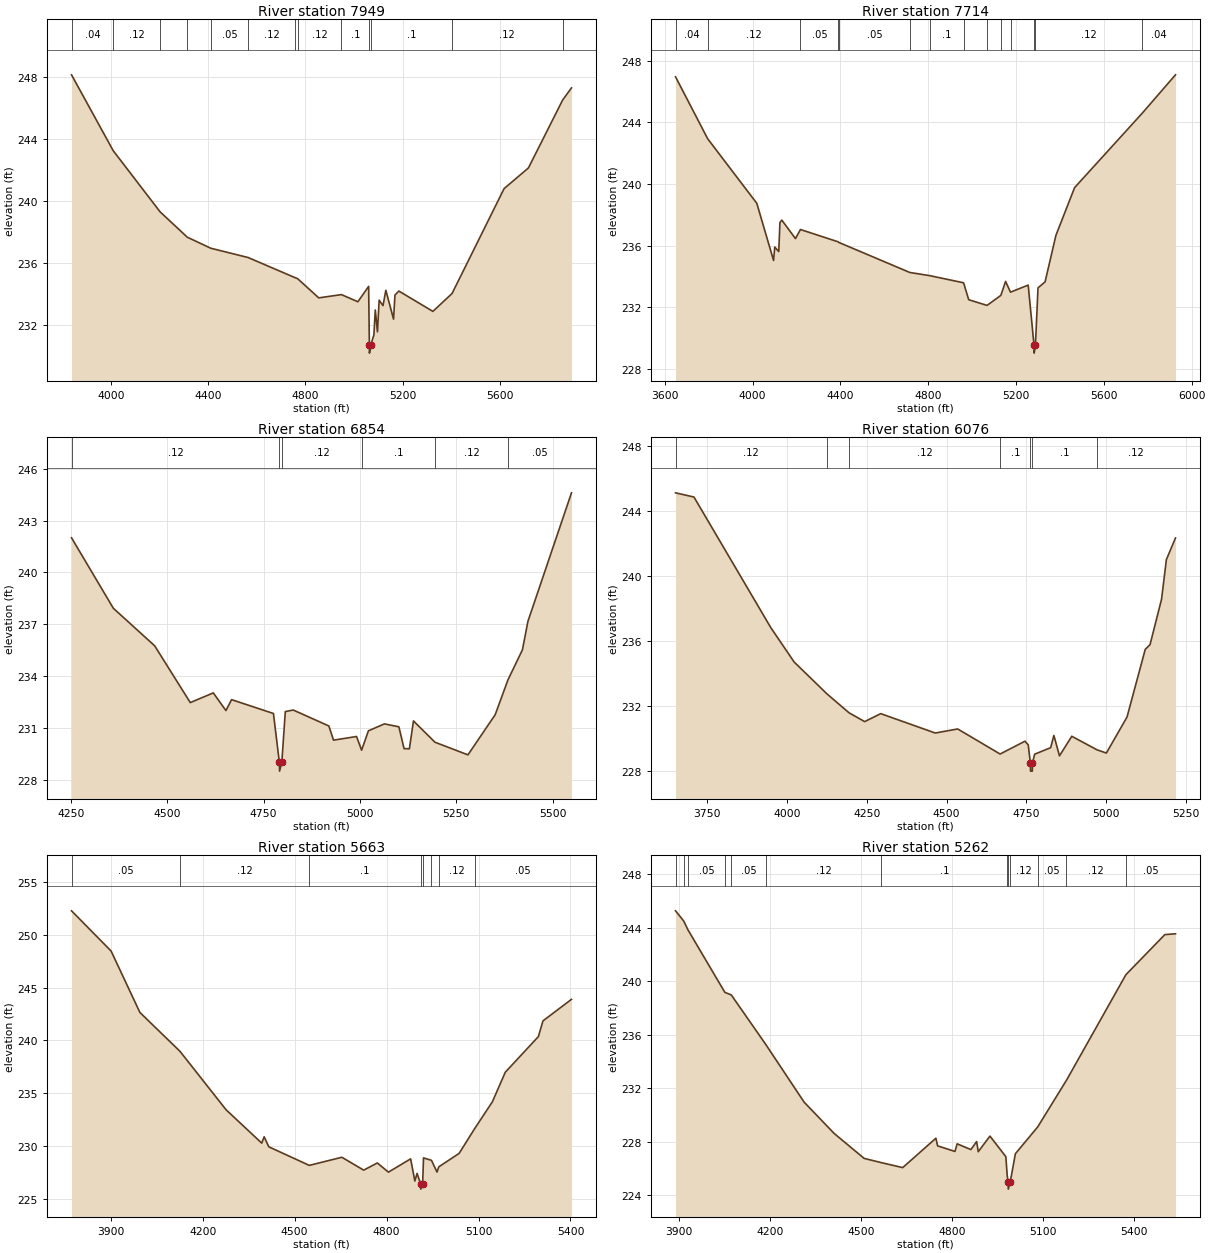
Type RM Length L Ch R = 1,7949,235,235,235
BEGIN DESCRIPTION:
Mapping XS cd12fd38
END DESCRIPTION:
XS GIS Cut Line= 4
      2548290.77     13606624.17      2547426.15     13606301.24
      2546898.37     13606599.85      2546582.43     13607019.95
#Sta/Elev= 30
  3838.8  248.14  4010.2  243.25  4203.0  239.31  4314.6  237.68  4410.8  236.97
  4564.5  236.37  4756.5  235.08  4767.9  235.01  4855.0  233.77  4948.2  233.98
  5015.8  233.52  5060.0  234.51  5063.0  230.71  5063.4  230.21  5068.4  230.71
  5081.6  231.38  5087.3  232.99  5096.3  231.58  5103.2  233.62  5119.1  233.27
  5130.7  234.26  5162.4  232.40  5168.2  233.95  5184.1  234.21  5324.1  232.90
  5402.9  234.05  5616.8  240.81  5716.8  242.14  5857.6  246.52  5893.8  247.30
#Mann=13,-1,0
  3838.8    0.04       0  4010.2    0.12       0  4203.0    0.05       0
  4314.6    0.12       0  4410.8    0.05       0  4564.5    0.12       0
  4756.5    0.05       0  4767.9    0.12       0  4948.2     0.1       0
  5063.0    0.05       0  5068.4     0.1       0  5402.9    0.12       0
  5857.6    0.04       0
Bank Sta=5063,5068.4
Exp/Cntr=0.3,0.1

Type RM Length L Ch R = 1,7714,860,860,860
BEGIN DESCRIPTION:
Mapping XS dd65f4cb
END DESCRIPTION:
XS GIS Cut Line= 4
      2548280.31     13606575.54      2547328.93     13606169.30
      2546710.87     13606412.35      2546310.26     13606830.23
#Sta/Elev= 30
  3648.9  246.96  3795.2  242.94  4019.2  238.74  4095.5  235.03  4100.9  235.90
  4119.1  235.61  4124.5  237.50  4133.1  237.65  4195.3  236.45  4218.0  237.04
  4389.9  236.24  4393.0  236.20  4716.1  234.25  4808.0  234.04  4961.0  233.58
  4984.5  232.48  5067.9  232.11  5130.8  232.76  5152.4  233.67  5174.8  232.97
  5255.4  233.43  5282.1  229.51  5282.6  229.01  5288.3  229.51  5300.1  233.25
  5332.3  233.64  5381.7  236.66  5466.7  239.76  5775.1  244.60  5926.4  247.09
#Mann=14,-1,0
  3648.9    0.04       0  3795.2    0.12       0  4218.0    0.05       0
  4389.9    0.12       0  4393.0    0.05       0  4716.1    0.12       0
  4808.0     0.1       0  4961.0    0.05       0  5067.9    0.12       0
  5130.8     0.1       0  5174.8    0.12       0  5282.1    0.05       0
  5288.3    0.12       0  5775.1    0.04       0
Bank Sta=5282.1,5288.3
Exp/Cntr=0.3,0.1

Type RM Length L Ch R = 1,6854,778,778,778
BEGIN DESCRIPTION:
TRIB 11 TO IRISH CREEK 7.0
END DESCRIPTION:
XS GIS Cut Line= 3
      2547275.03     13605524.99      2546425.00     13605725.00
      2546125.01     13606024.99
#Sta/Elev= 30
  4251.5  242.00  4360.0  237.93  4467.3  235.76  4559.7  232.48  4619.4  233.04
  4652.2  232.02  4666.9  232.65  4775.5  231.85  4790.9  229.02  4791.4  228.52
  4797.2  229.02  4806.3  231.96  4826.8  232.05  4919.3  231.13  4931.5  230.31
  4991.2  230.52  5004.3  229.73  5022.0  230.85  5063.7  231.25  5101.0  231.08
  5114.5  229.82  5128.3  229.81  5138.9  231.42  5194.7  230.19  5280.3  229.46
  5351.0  231.78  5384.1  233.79  5421.7  235.53  5435.9  237.17  5549.0  244.60
#Mann=6,-1,0
  4251.5    0.12       0  4790.9    0.05       0  4797.2    0.12       0
  5004.3     0.1       0  5194.7    0.12       0  5384.1    0.05       0
Bank Sta=4790.9,4797.2
Exp/Cntr=0.3,0.1

Type RM Length L Ch R = 1,6076,413,413,413
BEGIN DESCRIPTION:
TRIB 11 TO IRISH CREEK 6.0
END DESCRIPTION:
XS GIS Cut Line= 3
      2547374.99     13605475.00      2546175.00     13605375.00
      2545875.00     13605575.00
#Sta/Elev= 30
  3651.8  245.10  3709.5  244.84  3950.3  236.81  4023.1  234.71  4125.9  232.75
  4195.0  231.59  4243.8  231.05  4294.0  231.54  4464.6  230.35  4534.8  230.60
  4667.6  229.06  4745.6  229.85  4755.6  229.62  4762.4  228.51  4762.9  228.01
  4768.4  228.01  4768.9  228.51  4775.7  229.05  4825.8  229.45  4835.9  230.20
  4853.4  228.95  4892.0  230.15  4970.7  229.32  5000.2  229.12  5064.8  231.33
  5121.9  235.49  5136.9  235.78  5172.9  238.57  5188.0  241.00  5216.5  242.33
#Mann=7,-1,0
  3651.8    0.12       0  4125.9    0.05       0  4195.0    0.12       0
  4667.6     0.1       0  4762.4    0.05       0  4768.9     0.1       0
  4970.7    0.12       0
Bank Sta=4762.4,4768.9
Exp/Cntr=0.3,0.1

Type RM Length L Ch R = 1,5663,401,401,401
BEGIN DESCRIPTION:
TRIB 11 TO IRISH CREEK 5.0
END DESCRIPTION:
XS GIS Cut Line= 3
      2546460.63     13604112.66      2545875.00     13605025.00
      2545569.36     13605479.10
#Sta/Elev= 30
  3771.8  252.29  3900.9  248.48  3994.8  242.66  4125.8  238.97  4276.2  233.43
  4392.5  230.27  4400.4  230.87  4415.6  229.92  4547.7  228.16  4653.9  228.93
  4725.2  227.71  4769.7  228.39  4806.0  227.52  4878.4  228.78  4892.1  226.68
  4899.4  227.40  4911.1  226.41  4911.6  225.91  4917.6  226.41  4920.4  228.87
  4946.4  228.64  4964.4  227.53  4970.2  228.02  5036.7  229.30  5086.8  231.62
  5145.2  234.19  5187.3  236.99  5295.3  240.37  5310.3  241.86  5403.3  243.90
#Mann=8,-1,0
  3771.8    0.05       0  4125.8    0.12       0  4547.7     0.1       0
  4911.1    0.05       0  4917.6     0.1       0  4946.4    0.05       0
  4970.2    0.12       0  5086.8    0.05       0
Bank Sta=4911.1,4917.6
Exp/Cntr=0.3,0.1

Type RM Length L Ch R = 1,5262,575,575,575
BEGIN DESCRIPTION:
TRIB 11 TO IRISH CREEK 4.0
END DESCRIPTION:
XS GIS Cut Line= 3
      2546175.03     13604124.97      2545575.00     13604725.00
      2545332.20     13605488.45
#Sta/Elev= 30
  3888.7  245.27  3915.9  244.50  3929.6  243.85  4051.4  239.17  4072.8  238.97
  4187.0  235.25  4313.0  230.95  4412.0  228.61  4511.0  226.74  4568.3  226.42
  4638.3  226.05  4747.8  228.25  4753.4  227.68  4810.7  227.26  4817.9  227.83
  4863.2  227.40  4882.3  228.00  4887.6  227.24  4926.2  228.41  4978.6  226.87
  4983.1  225.47  4986.2  224.94  4986.7  224.44  4992.8  224.94  5010.1  227.09
  5083.9  229.10  5178.7  232.59  5374.8  240.49  5503.3  243.49  5538.4  243.55
#Mann=13,-1,0
  3888.7    0.05       0  3915.9    0.12       0  3929.6    0.05       0
  4051.4    0.12       0  4072.8    0.05       0  4187.0    0.12       0
  4568.3     0.1       0  4983.1    0.12       0  4986.2    0.05       0
  4992.8    0.12       0  5083.9    0.05       0  5178.7    0.12       0
  5374.8    0.05       0
Bank Sta=4986.2,4992.8
Exp/Cntr=0.3,0.1

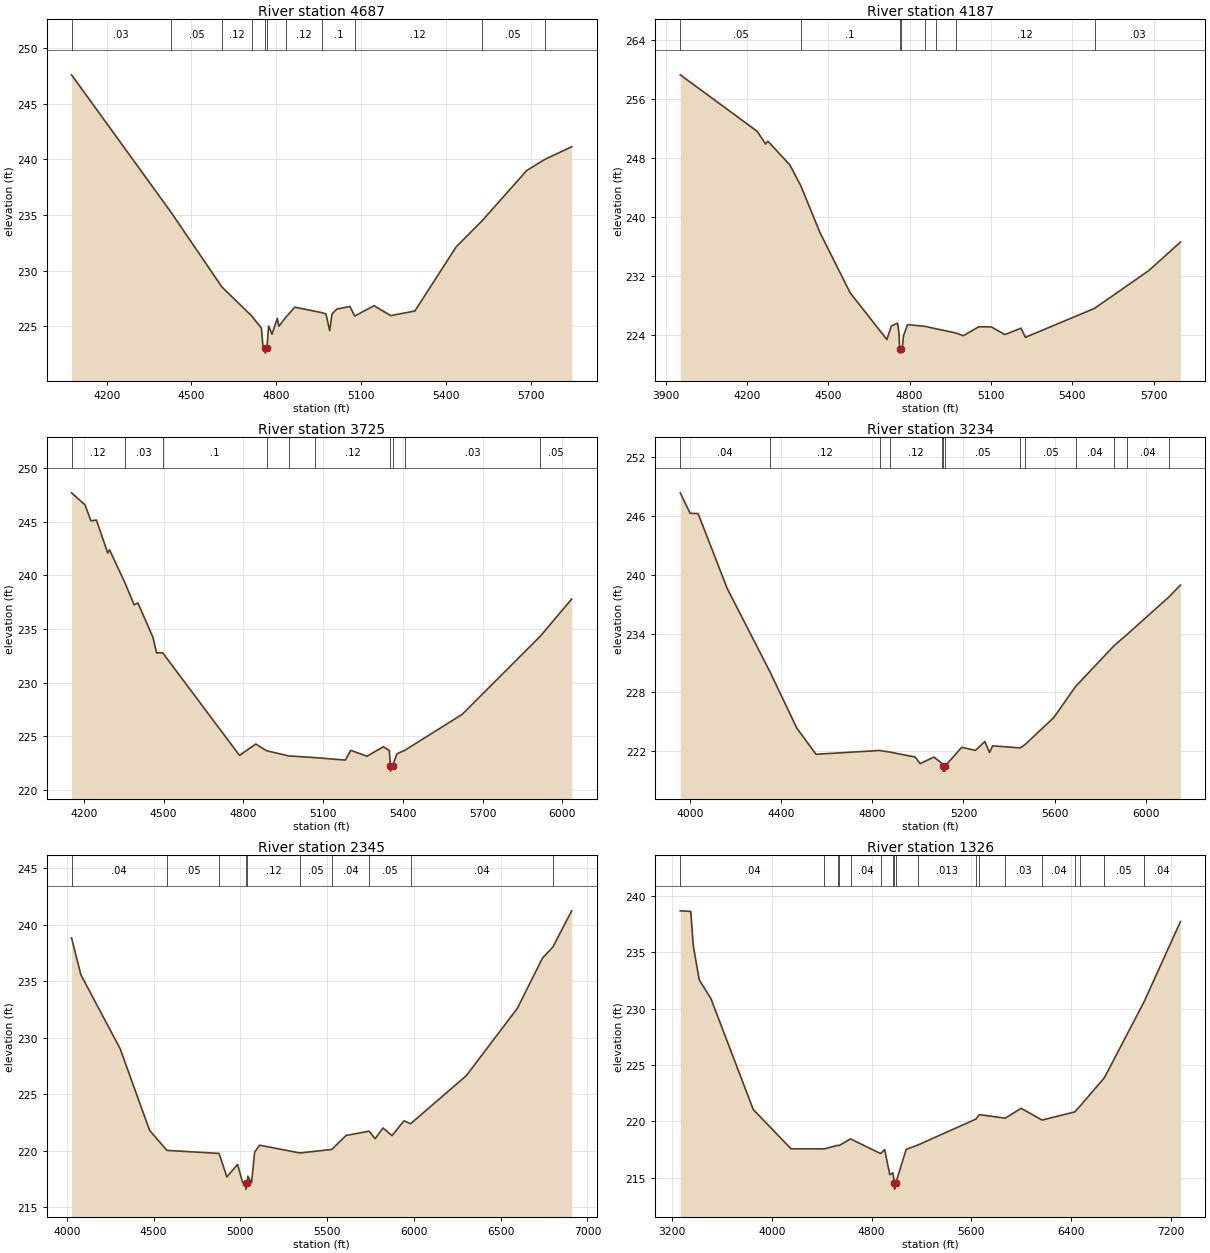
Type RM Length L Ch R = 1,4687,500,500,500
BEGIN DESCRIPTION:
Mapping XS b4fab1f2
END DESCRIPTION:
XS GIS Cut Line= 4
      2545310.48     13603769.71      2545267.08     13604268.87
      2545058.74     13604854.81      2545171.34     13605491.41
#Sta/Elev= 30
  4075.8  247.58  4427.1  235.26  4607.8  228.52  4713.2  225.92  4747.5  224.83
  4753.2  223.13  4760.5  223.08  4761.0  222.58  4767.1  223.08  4773.1  225.02
  4785.0  224.28  4803.9  225.71  4809.2  224.99  4833.8  225.80  4865.6  226.71
  4962.1  226.21  4976.0  226.10  4989.0  224.60  4997.3  226.10  5014.5  226.54
  5060.9  226.77  5077.4  225.91  5145.9  226.84  5205.0  225.95  5290.3  226.36
  5436.6  232.13  5527.2  234.44  5686.4  238.99  5749.3  239.97  5845.2  241.12
#Mann=11,-1,0
  4075.8    0.03       0  4427.1    0.05       0  4607.8    0.12       0
  4713.2     0.1       0  4760.5    0.05       0  4767.1     0.1       0
  4833.8    0.12       0  4962.1     0.1       0  5077.4    0.12       0
  5527.2    0.05       0  5749.3    0.12       0
Bank Sta=4760.5,4767.1
Exp/Cntr=0.3,0.1

Type RM Length L Ch R = 1,4187,462,462,462
BEGIN DESCRIPTION:
TRIB 11 TO IRISH CREEK 2.0
END DESCRIPTION:
XS GIS Cut Line= 3
      2545182.87     13603491.96      2544825.00     13604225.00
      2544325.00     13605125.01
#Sta/Elev= 30
  3953.9  259.23  4237.5  251.59  4268.9  249.85  4277.0  250.25  4357.9  247.04
  4398.5  244.22  4469.2  237.87  4580.9  229.69  4716.1  223.38  4733.1  225.22
  4755.6  225.58  4761.1  224.19  4763.5  222.03  4764.0  221.53  4770.1  222.03
  4772.5  222.03  4777.6  223.89  4792.5  225.39  4858.6  225.15  4895.6  224.84
  4969.6  224.27  4998.4  223.89  5055.6  225.10  5101.4  225.08  5151.7  224.04
  5211.2  224.91  5227.2  223.67  5482.3  227.59  5682.5  232.71  5799.2  236.57
#Mann=8,-1,0
  3953.9    0.05       0  4398.5     0.1       0  4763.5    0.05       0
  4770.1     0.1       0  4858.6    0.12       0  4895.6     0.1       0
  4969.6    0.12       0  5482.3    0.03       0
Bank Sta=4763.5,4770.1
Exp/Cntr=0.3,0.1

Type RM Length L Ch R = 1,3725,491,491,491
BEGIN DESCRIPTION:
Mapping XS c58a10a9
END DESCRIPTION:
XS GIS Cut Line= 4
      2544910.33     13603478.05      2544472.81     13603873.91
      2544311.35     13604649.95      2544243.64     13605144.75
#Sta/Elev= 30
  4153.5  247.71  4204.5  246.58  4226.2  245.10  4247.1  245.17  4289.7  242.09
  4296.4  242.39  4353.9  239.34  4389.0  237.26  4403.2  237.43  4459.3  234.26
  4473.5  232.77  4496.3  232.78  4785.5  223.20  4846.8  224.26  4887.8  223.63
  4970.1  223.15  5070.2  222.99  5183.9  222.76  5204.3  223.67  5265.6  223.12
  5326.9  224.01  5349.4  223.65  5353.2  222.23  5353.7  221.73  5361.7  222.23
  5377.9  223.35  5406.7  223.66  5623.5  227.03  5918.0  234.34  6035.6  237.80
#Mann=10,-1,0
  4153.5    0.12       0  4353.9    0.03       0  4496.3     0.1       0
  4887.8    0.03       0  4970.1     0.1       0  5070.2    0.12       0
  5353.2    0.05       0  5361.7    0.12       0  5406.7    0.03       0
  5918.0    0.05       0
Bank Sta=5353.2,5361.7
Exp/Cntr=0.3,0.1

Type RM Length L Ch R = 1,3234,889,889,889
BEGIN DESCRIPTION:
Mapping XS 53d40466
END DESCRIPTION:
XS GIS Cut Line= 4
      2544498.87     13603248.89      2544056.14     13603613.49
      2543931.14     13604358.28      2544123.62     13605201.03
#Sta/Elev= 30
  3958.5  248.37  4001.7  246.28  4036.8  246.25  4164.5  238.60  4349.9  230.19
  4469.4  224.36  4553.9  221.68  4832.3  222.07  4876.9  221.91  4988.4  221.40
  5010.1  220.73  5071.0  221.39  5104.5  220.77  5110.5  220.46  5111.0  219.96
  5118.5  219.96  5119.0  220.46  5192.7  222.39  5253.5  222.08  5294.1  222.99
  5314.7  221.86  5328.5  222.54  5450.2  222.33  5471.1  222.69  5596.6  225.43
  5691.7  228.59  5861.0  232.77  5917.3  233.90  6101.4  237.74  6151.7  238.95
#Mann=13,-1,0
  3958.5    0.04       0  4349.9    0.12       0  4832.3     0.1       0
  4876.9    0.12       0  5104.5    0.05       0  5110.5    0.05       0
  5119.0    0.05       0  5450.2    0.12       0  5471.1    0.05       0
  5691.7    0.04       0  5861.0    0.05       0  5917.3    0.04       0
  6101.4    0.05       0
Bank Sta=5110.5,5119
Exp/Cntr=0.3,0.1

Type RM Length L Ch R = 1,2345,1019,1019,1019
BEGIN DESCRIPTION:
Mapping XS a363f637
END DESCRIPTION:
XS GIS Cut Line= 5
      2544071.77     13603191.62      2543561.35     13603269.74
      2543186.35     13604103.07      2543472.81     13604733.28
      2543914.40     13605351.52
#Sta/Elev= 30
  4027.1  238.84  4081.0  235.58  4307.1  229.04  4476.6  221.82  4576.4  220.04
  4876.9  219.77  4922.1  217.69  4983.9  218.80  5012.5  217.21  5031.2  217.11
  5031.7  216.61  5040.2  217.11  5042.7  217.75  5064.6  217.18  5082.0  219.87
  5110.6  220.50  5342.7  219.81  5526.4  220.12  5609.4  221.36  5742.0  221.74
  5776.4  221.07  5821.9  222.02  5874.1  221.35  5942.7  222.65  5981.3  222.40
  6302.4  226.66  6596.1  232.61  6741.1  237.06  6801.1  238.04  6909.3  241.24
#Mann=10,-1,0
  4027.1    0.04       0  4576.4    0.05       0  4876.9    0.12       0
  5031.2    0.05       0  5040.2    0.12       0  5342.7    0.05       0
  5526.4    0.04       0  5742.0    0.05       0  5981.3    0.04       0
  6801.1    0.05       0
Bank Sta=5031.2,5040.2
Exp/Cntr=0.3,0.1

Type RM Length L Ch R = 1,1326,0,0,0
BEGIN DESCRIPTION:
Mapping XS a363f637aa
END DESCRIPTION:
XS GIS Cut Line= 5
      2544128.78     13602652.19      2543229.85     13602756.49
      2542842.46     13603044.54      2542683.54     13604042.80
      2543670.91     13605322.91
#Sta/Elev= 30
  3264.0  238.66  3348.3  238.61  3368.5  235.57  3416.1  232.55  3509.9  230.89
  3849.5  221.06  4153.7  217.57  4421.4  217.57  4527.2  217.88  4539.2  217.86
  4630.9  218.45  4872.0  217.15  4905.3  217.50  4945.8  215.28  4971.3  215.45
  4983.8  214.50  4984.3  214.00  4993.0  214.50  5077.5  217.52  5170.0  217.90
  5638.2  220.21  5664.6  220.60  5873.0  220.29  6000.3  221.16  6169.1  220.12
  6430.9  220.84  6475.4  221.38  6669.4  223.88  6987.6  230.60  7279.2  237.70
#Mann=18,-1,0
  3264.0    0.04       0  4421.4   0.013       0  4527.2    0.05       0
  4539.2   0.013       0  4630.9    0.04       0  4872.0   0.013       0
  4971.3    0.05       0  4983.8    0.05       0  4993.0    0.05       0
  5170.0   0.013       0  5638.2    0.03       0  5664.6   0.013       0
  5873.0    0.03       0  6169.1    0.04       0  6430.9    0.05       0
  6475.4    0.04       0  6669.4    0.05       0  6987.6    0.04       0
Bank Sta=4983.8,4993
Exp/Cntr=0.3,0.1

Chan Stop Cuts=-1