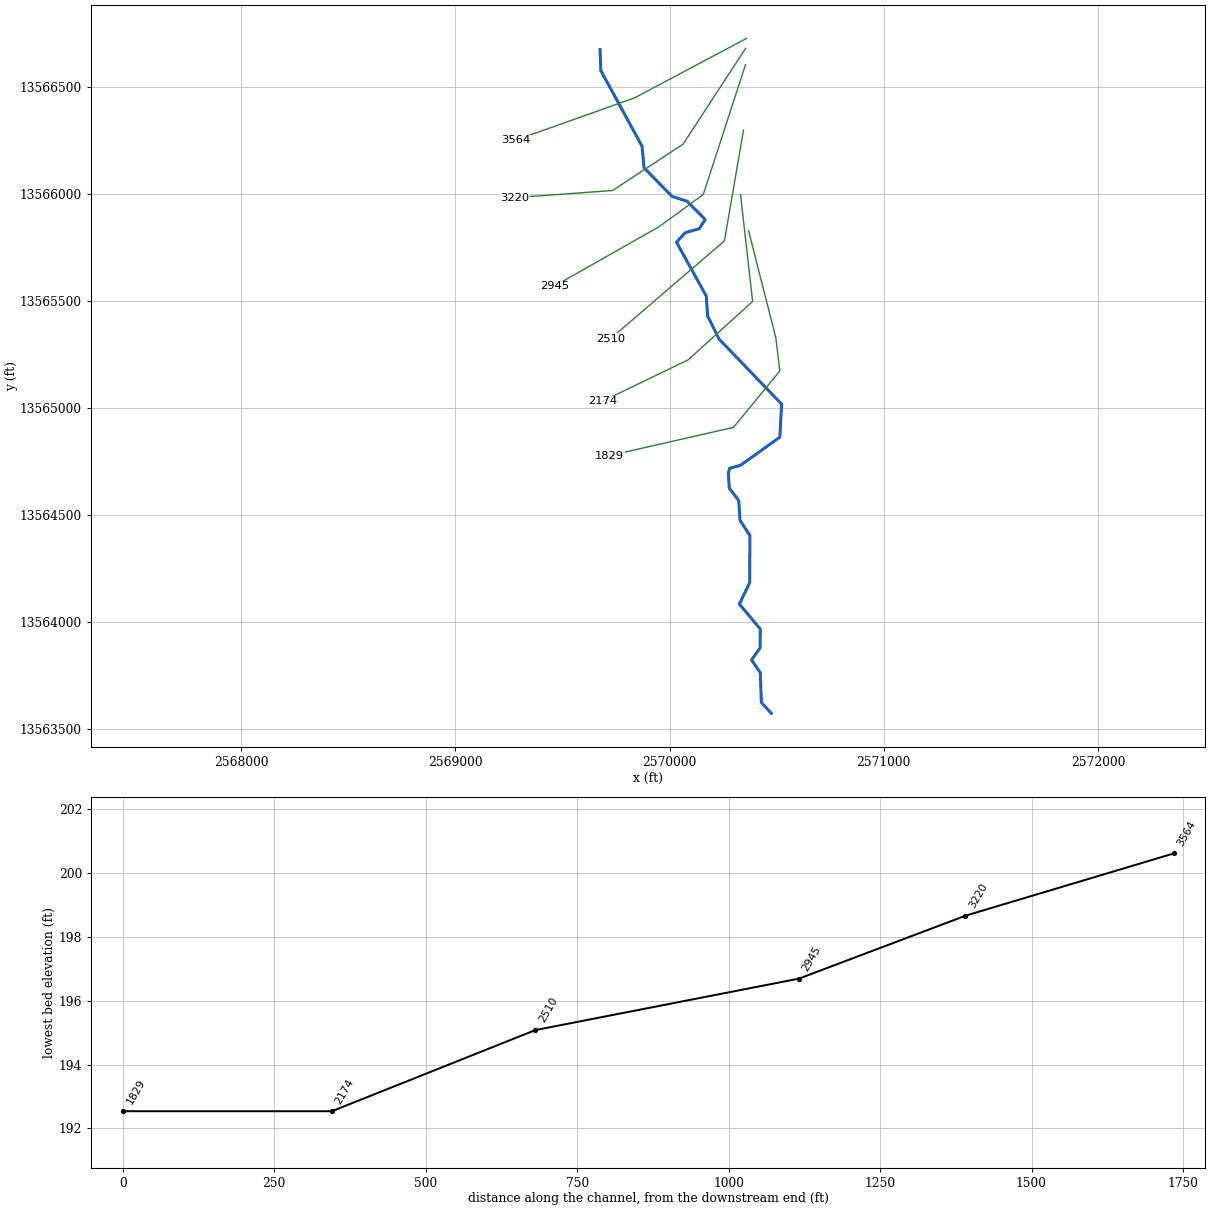
--- TRIB 11 TO PRICE CREEK.prj (project) ---

Proj Title=TRIB 11 TO PRICE CREEK Base Level Engineering
Current Plan=p01
Default Exp/Contr=0.3,0.1
English Units
Geom File=g01
Flow File=f01
Plan File=p01
BEGIN DESCRIPTION:
TRIB 11 TO PRICE CREEK
END DESCRIPTION:

--- TRIB 11 TO PRICE CREEK.p01 (plan) ---

Plan Title=Multiple Run
Short Identifier=Multiple
Geom File=g01
Flow File=f01
Subcritical Flow
K Sum by GR= 0
Std Step Tol= 0.01
Critical Tol= 0.01
Num of Std Step Trials= 20
Max Error Tol= 0.3
Flow Tol Ratio= 0.001
Split Flow NTrial= 30
Split Flow Tol= 0.02
Split Flow Ratio= 0.02
Log Output Level= 0
Friction Slope Method= 1
Unsteady Friction Slope Method= 2
Unsteady Bridges Friction Slope Method= 1
Parabolic Critical Depth
Global Vel Dist=  1 , 1 , 1
Global Log Level= 0
CheckData=True
Encroach Param= -1, 0, 0, 0
BEGIN DESCRIPTION:
Multiple Run
END DESCRIPTION:

--- TRIB 11 TO PRICE CREEK.f01 (steady flow) ---

Flow Title=Multiple
Number of Profiles=7
Profile Names=10-year,25-year,50-year,1pct_min,100-year,1pct_plu,500-year
River Rch & RM= TRIB 11 TO PRICE,Reach-1,3564
     284     429     551     344     687    1370    1052
Boundary for River Rch & Prof#=TRIB 11 TO PRICE,Reach-1,1
Up Type=0
Dn Type=3
Dn Slope=0.005
Boundary for River Rch & Prof#=TRIB 11 TO PRICE,Reach-1,2
Up Type=0
Dn Type=3
Dn Slope=0.005
Boundary for River Rch & Prof#=TRIB 11 TO PRICE,Reach-1,3
Up Type=0
Dn Type=3
Dn Slope=0.005
Boundary for River Rch & Prof#=TRIB 11 TO PRICE,Reach-1,4
Up Type=0
Dn Type=3
Dn Slope=0.005
Boundary for River Rch & Prof#=TRIB 11 TO PRICE,Reach-1,5
Up Type=0
Dn Type=3
Dn Slope=0.005
Boundary for River Rch & Prof#=TRIB 11 TO PRICE,Reach-1,6
Up Type=0
Dn Type=3
Dn Slope=0.005
Boundary for River Rch & Prof#=TRIB 11 TO PRICE,Reach-1,7
Up Type=0
Dn Type=3
Dn Slope=0.005

--- TRIB 11 TO PRICE CREEK.g01 (geometry) ---

Geom Title=Existing Conditions

River Reach=TRIB 11 TO PRICE,Reach-1
Reach XY= 30
      2569675.00     13566675.00      2569678.63     13566576.50
      2569871.17     13566223.41      2569880.52     13566122.57
      2570011.79     13565988.63      2570081.09     13565966.84
      2570166.12     13565881.53      2570139.03     13565838.63
      2570072.20     13565819.15      2570032.20     13565775.30
      2570171.17     13565523.42      2570177.33     13565430.97
      2570230.83     13565322.70      2570522.95     13565019.14
      2570514.66     13564864.88      2570330.69     13564733.32
      2570280.11     13564719.53      2570274.22     13564695.34
      2570278.67     13564626.67      2570322.64     13564569.03
      2570328.86     13564476.60      2570374.93     13564404.97
      2570373.76     13564185.50      2570325.60     13564085.62
      2570423.02     13563969.10      2570422.64     13563880.90
      2570382.56     13563825.00      2570423.61     13563764.56
      2570428.30     13563626.37      2570475.00     13563575.00

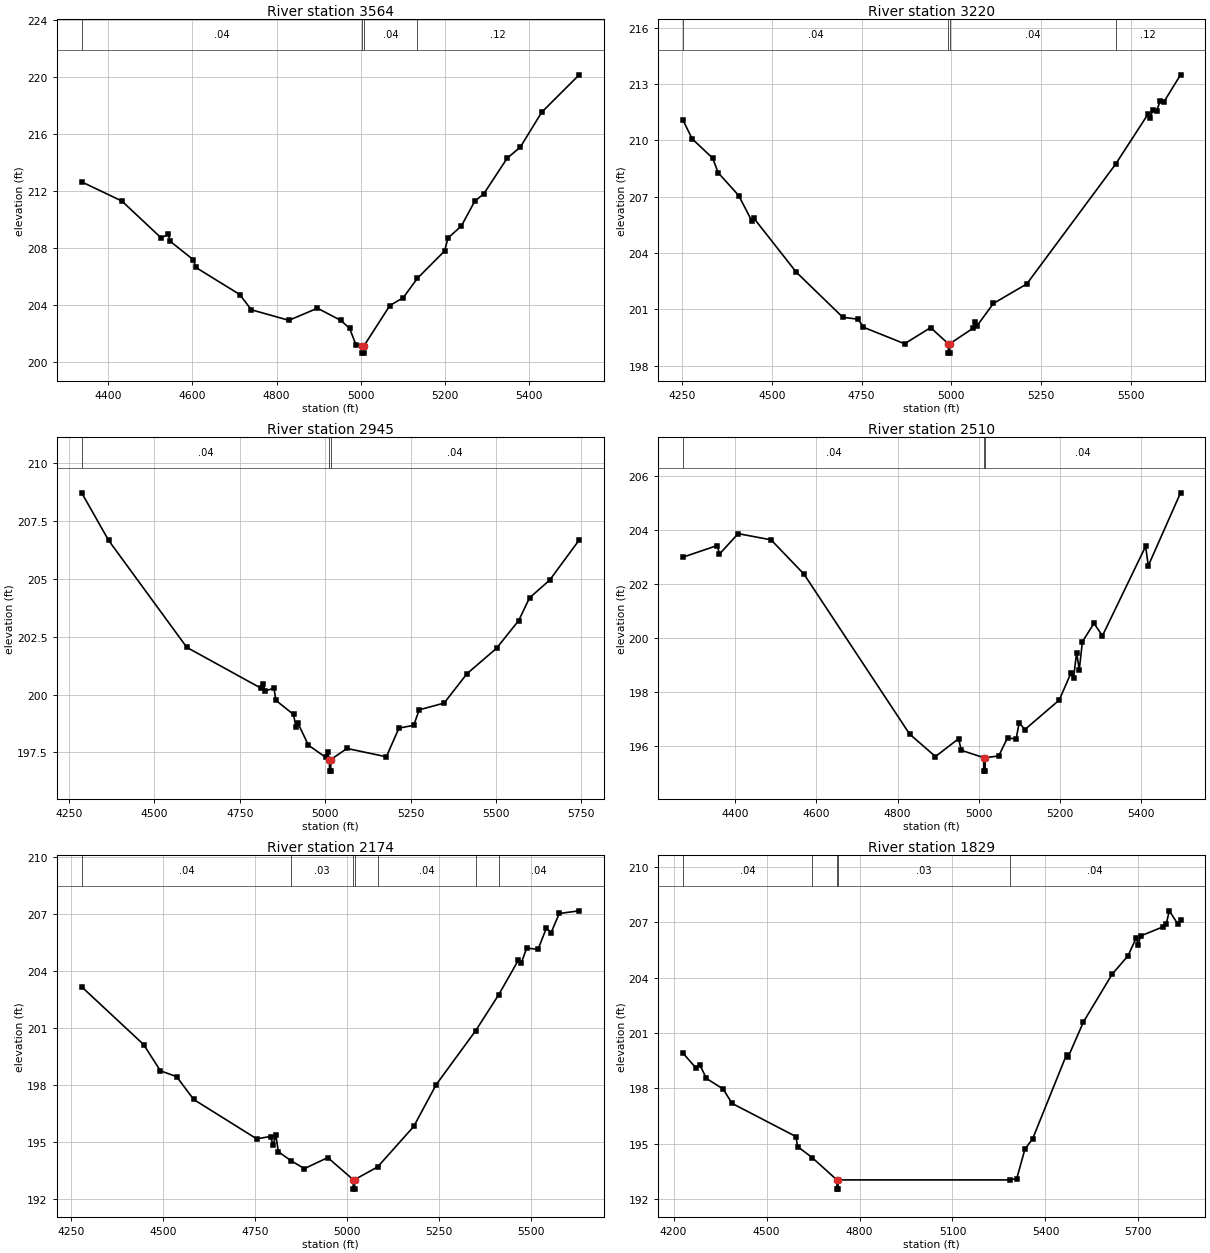
Type RM Length L Ch R = 1,3564,344,344,344
BEGIN DESCRIPTION:
LGII3185
END DESCRIPTION:
XS GIS Cut Line= 3
      2570359.34     13566727.24      2569836.86     13566449.52
      2569281.50     13566251.85
#Sta/Elev= 30
  4337.0  212.62  4432.3  211.28  4525.8  208.69  4542.1  208.94  4547.8  208.44
  4602.4  207.15  4608.1  206.62  4712.3  204.72  4739.9  203.65  4828.9  202.91
  4896.8  203.76  4951.9  202.91  4973.1  202.35  4988.0  201.21  5003.0  201.11
  5003.2  200.61  5006.7  200.61  5007.0  201.11  5068.7  203.95  5100.5  204.50
  5134.2  205.86  5198.5  207.77  5206.7  208.68  5238.5  209.53  5270.3  211.27
  5291.6  211.78  5347.4  214.29  5378.2  215.05  5429.3  217.51  5518.2  220.13
#Mann=4,-1,0
  4337.0    0.04       0  5003.0    0.04       0  5007.0    0.04       0
  5134.2    0.12       0
Bank Sta=5003,5007
Exp/Cntr=0.3,0.1

Type RM Length L Ch R = 1,3220,275,275,275
BEGIN DESCRIPTION:
LGII3184
END DESCRIPTION:
XS GIS Cut Line= 4
      2570354.59     13566680.12      2570062.79     13566233.01
      2569733.31     13566016.50      2569278.35     13565983.67
#Sta/Elev= 30
  4253.2  211.08  4278.6  210.09  4335.9  209.05  4351.0  208.28  4408.3  207.06
  4444.5  205.71  4450.5  205.85  4568.2  202.98  4697.9  200.57  4740.1  200.47
  4755.2  200.04  4869.8  199.16  4942.1  200.02  4991.4  199.16  4991.6  198.66
  4995.1  198.66  4995.4  199.16  5059.7  199.98  5065.7  200.33  5071.7  200.13
  5116.9  201.31  5209.7  202.35  5456.6  208.73  5547.6  211.42  5552.6  211.18
  5560.6  211.62  5570.7  211.56  5580.7  212.10  5590.7  212.04  5637.5  213.50
#Mann=4,-1,0
  4253.2    0.04       0  4991.4    0.04       0  4995.4    0.04       0
  5456.6    0.12       0
Bank Sta=4991.4,4995.4
Exp/Cntr=0.3,0.1

Type RM Length L Ch R = 1,2945,435,435,435
BEGIN DESCRIPTION:
LGII3183
END DESCRIPTION:
XS GIS Cut Line= 4
      2570354.60     13566604.83      2570156.92     13565997.67
      2569949.82     13565847.05      2569460.92     13565569.70
#Sta/Elev= 30
  4286.9  208.72  4366.0  206.66  4594.7  202.04  4812.6  200.27  4818.2  200.47
  4823.5  200.16  4850.1  200.27  4855.4  199.75  4907.2  199.14  4914.0  198.61
  4919.2  198.79  4950.9  197.81  5001.1  197.29  5007.3  197.50  5012.4  197.19
  5012.6  196.69  5016.1  196.69  5016.4  197.19  5063.8  197.67  5178.9  197.31
  5215.9  198.55  5259.2  198.67  5275.1  199.34  5348.0  199.63  5415.0  200.90
  5501.5  202.00  5566.5  203.20  5598.2  204.18  5657.3  204.95  5743.6  206.68
#Mann=3,-1,0
  4286.9    0.04       0  5012.4    0.04       0  5016.4    0.04       0
Bank Sta=5012.4,5016.4
Exp/Cntr=0.3,0.1

Type RM Length L Ch R = 1,2510,336,336,336
BEGIN DESCRIPTION:
LGII3182
END DESCRIPTION:
XS GIS Cut Line= 3
      2570345.19     13566298.87      2570255.76     13565781.16
      2569723.92     13565324.62
#Sta/Elev= 30
  4271.1  203.00  4355.7  203.43  4360.8  203.11  4407.0  203.87  4488.1  203.64
  4569.3  202.37  4829.7  196.45  4893.3  195.62  4950.4  196.28  4957.0  195.85
  5012.1  195.58  5012.3  195.08  5015.8  195.08  5016.1  195.58  5049.2  195.64
  5071.1  196.32  5092.0  196.26  5099.7  196.87  5113.8  196.62  5198.4  197.71
  5227.0  198.70  5233.6  198.51  5241.2  199.46  5247.8  198.84  5255.5  199.87
  5284.0  200.55  5304.9  200.09  5411.3  203.40  5417.9  202.68  5497.4  205.38
#Mann=3,-1,0
  4271.1    0.04       0  5012.1    0.04       0  5016.1    0.04       0
Bank Sta=5012.1,5016.1
Exp/Cntr=0.3,0.1

Type RM Length L Ch R = 1,2174,345,345,345
BEGIN DESCRIPTION:
LGII3181
END DESCRIPTION:
XS GIS Cut Line= 4
      2570331.07     13565997.71      2570387.55     13565498.75
      2570086.32     13565225.76      2569686.21     13565032.76
#Sta/Elev= 30
  4278.2  203.19  4446.7  200.15  4492.3  198.77  4536.5  198.46  4582.8  197.26
  4753.9  195.19  4792.0  195.31  4798.7  194.84  4806.2  195.39  4812.9  194.51
  4848.7  194.02  4883.9  193.62  4947.4  194.20  5016.4  193.04  5016.6  192.54
  5020.1  192.54  5020.4  193.04  5083.0  193.71  5181.2  195.84  5242.2  198.04
  5349.2  200.87  5411.8  202.76  5465.9  204.60  5473.9  204.45  5488.1  205.23
  5519.1  205.16  5541.7  206.27  5554.7  206.04  5576.9  207.05  5631.1  207.19
#Mann=7,-1,0
  4278.2    0.04       0  4848.7    0.03       0  5016.4    0.03       0
  5020.4    0.03       0  5083.0    0.04       0  5349.2    0.05       0
  5411.8    0.04       0
Bank Sta=5016.4,5020.4
Exp/Cntr=0.3,0.1

Type RM Length L Ch R = 1,1829,0,0,0
BEGIN DESCRIPTION:
LGII3180
END DESCRIPTION:
XS GIS Cut Line= 5
      2570368.73     13565828.21      2570495.81     13565329.31
      2570514.64     13565173.98      2570298.12     13564910.40
      2569719.63     13564778.71
#Sta/Elev= 30
  4230.3  199.91  4272.8  199.10  4285.2  199.26  4305.8  198.54  4359.8  197.97
  4388.4  197.19  4594.8  195.39  4600.0  194.85  4647.8  194.24  4726.9  193.04
  4727.2  192.54  4730.7  192.54  4730.9  193.04  5284.0  193.04  5307.4  193.11
  5333.8  194.71  5358.7  195.27  5468.1  199.83  5473.2  199.70  5522.8  201.61
  5615.1  204.19  5666.4  205.19  5693.5  206.18  5698.7  205.79  5707.4  206.27
  5779.2  206.76  5789.9  206.92  5799.7  207.63  5827.8  206.90  5836.0  207.12
#Mann=5,-1,0
  4230.3    0.04       0  4647.8    0.03       0  4726.9    0.03       0
  4730.9    0.03       0  5284.0    0.04       0
Bank Sta=4726.9,4730.9
Exp/Cntr=0.3,0.1

Chan Stop Cuts=-1