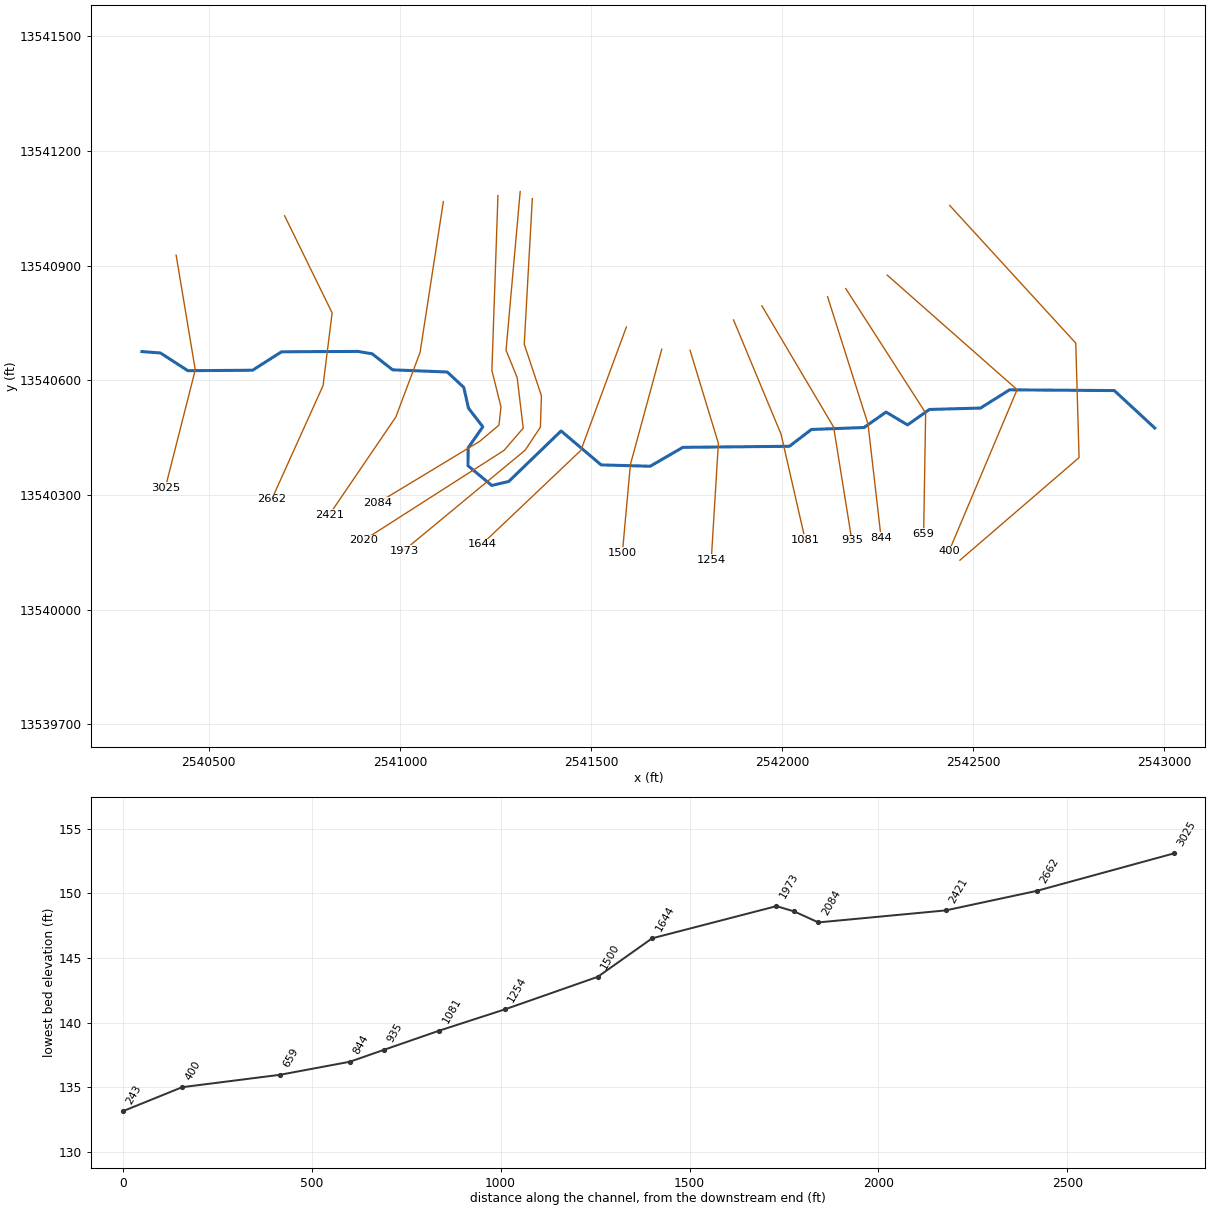
--- TRIB 11_1 TO GUADALUPE RIVER.prj (project) ---

Proj Title=TRIB 11_1 TO GUADALUPE RIVER Base Level Engineering
Current Plan=p01
Default Exp/Contr=0.3,0.1
English Units
Geom File=g01
Flow File=f01
Plan File=p01
Y Axis Title=Elevation
X Axis Title(PF)=Main Channel Distance
X Axis Title(XS)=Station
BEGIN DESCRIPTION:
TRIB 11_1 TO GUADALUPE RIVER
END DESCRIPTION:
DSS Export Rating Curves= 0
DSS Export Rating Curve Sorted= 0
DSS Export Volume Flow Curves= 0
DXF OffsetX= 0
DXF OffsetY= 0
DXF ScaleX= 1
DXF ScaleY= 10

--- TRIB 11_1 TO GUADALUPE RIVER.p01 (plan) ---

Plan Title=Multiple Run
Short Identifier=Multiple
Geom File=g01
Flow File=f01
Subcritical Flow
K Sum by GR= 0
Std Step Tol= 0.01
Critical Tol= 0.01
Num of Std Step Trials= 20
Max Error Tol= 0.3
Flow Tol Ratio= 0.001
Split Flow NTrial= 30
Split Flow Tol= 0.02
Split Flow Ratio= 0.02
Log Output Level= 0
Friction Slope Method= 1
Unsteady Friction Slope Method= 2
Unsteady Bridges Friction Slope Method= 1
Parabolic Critical Depth
Global Vel Dist=  1 , 1 , 1
Global Log Level= 0
CheckData=True
Encroach Param= -1, 0, 0, 0
BEGIN DESCRIPTION:
Multiple Run
END DESCRIPTION:

--- TRIB 11_1 TO GUADALUPE RIVER.f01 (steady flow) ---

Flow Title=Multiple
Number of Profiles=7
Profile Names=10-year,25-year,50-year,1pct_min,100-year,1pct_plu,500-year
River Rch & RM= TRIB 11_1 TO GUA,Reach-1,3025
     484     765    1013     652    1300    2595    2114
Boundary for River Rch & Prof#=TRIB 11_1 TO GUA,Reach-1,1
Up Type=0
Dn Type=3
Dn Slope=0.005
Boundary for River Rch & Prof#=TRIB 11_1 TO GUA,Reach-1,2
Up Type=0
Dn Type=3
Dn Slope=0.005
Boundary for River Rch & Prof#=TRIB 11_1 TO GUA,Reach-1,3
Up Type=0
Dn Type=3
Dn Slope=0.005
Boundary for River Rch & Prof#=TRIB 11_1 TO GUA,Reach-1,4
Up Type=0
Dn Type=3
Dn Slope=0.005
Boundary for River Rch & Prof#=TRIB 11_1 TO GUA,Reach-1,5
Up Type=0
Dn Type=3
Dn Slope=0.005
Boundary for River Rch & Prof#=TRIB 11_1 TO GUA,Reach-1,6
Up Type=0
Dn Type=3
Dn Slope=0.005
Boundary for River Rch & Prof#=TRIB 11_1 TO GUA,Reach-1,7
Up Type=0
Dn Type=3
Dn Slope=0.005

--- TRIB 11_1 TO GUADALUPE RIVER.g01 (geometry) ---

Geom Title=Existing Conditions

River Reach=TRIB 11_1 TO GUA,Reach-1
Reach XY= 30
      2540325.00     13540675.00      2540373.49     13540671.35
      2540445.01     13540625.02      2540614.49     13540626.22
      2540690.22     13540674.48      2540890.18     13540675.43
      2540927.33     13540669.25      2540980.94     13540627.27
      2541123.75     13540621.55      2541167.02     13540581.38
      2541179.47     13540526.68      2541216.93     13540478.31
      2541178.56     13540423.31      2541178.07     13540376.37
      2541240.21     13540324.84      2541284.66     13540335.17
      2541421.66     13540467.40      2541526.47     13540378.55
      2541654.96     13540375.05      2541740.22     13540424.48
      2542019.06     13540427.26      2542076.57     13540471.21
      2542214.56     13540476.39      2542271.78     13540516.72
      2542328.22     13540483.28      2542385.44     13540523.61
      2542519.06     13540527.27      2542595.03     13540574.93
      2542869.16     13540572.98      2542975.00     13540475.00

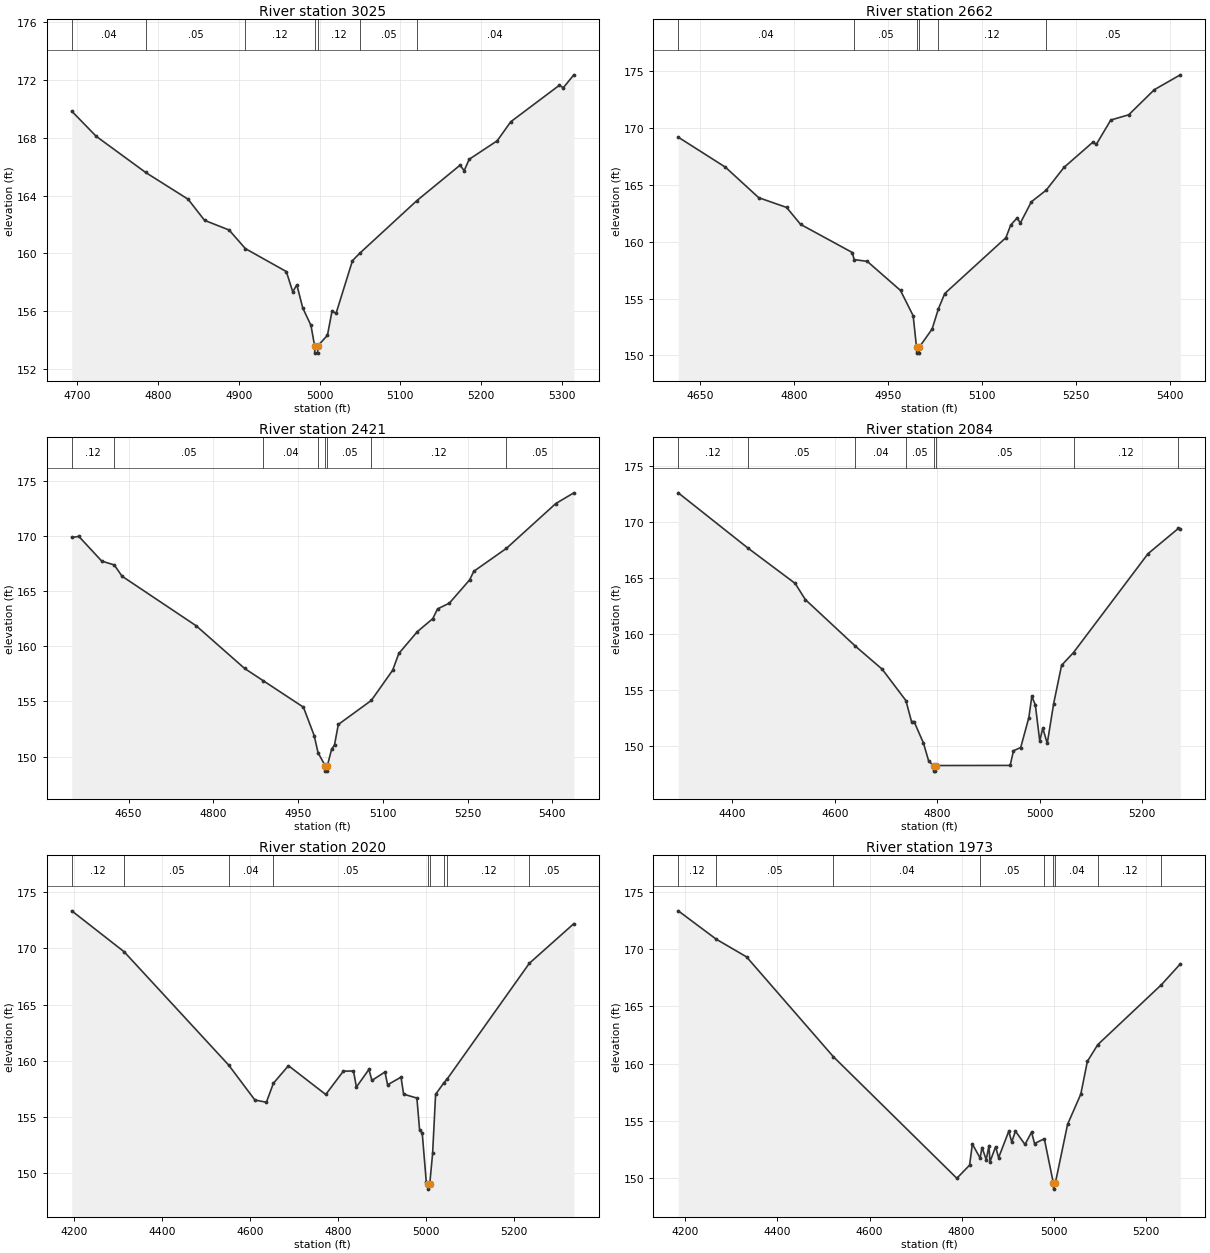
Type RM Length L Ch R = 1,3025,363,363,363
BEGIN DESCRIPTION:
TRIB 11_1 TO GUADALUPE RIVER 6.0
END DESCRIPTION:
XS GIS Cut Line= 3
      2540414.55     13540927.12      2540464.54     13540627.15
      2540386.31     13540319.35
#Sta/Elev= 30
  4693.2  169.85  4723.5  168.11  4784.6  165.61  4837.3  163.75  4857.6  162.29
  4888.0  161.62  4908.2  160.33  4958.9  158.74  4966.8  157.34  4971.9  157.82
  4979.2  156.22  4989.4  155.01  4993.9  153.59  4994.1  153.09  4997.6  153.09
  4997.9  153.59  5009.8  154.33  5015.4  155.98  5020.5  155.85  5040.8  159.50
  5050.0  160.02  5120.4  163.65  5174.0  166.11  5179.1  165.73  5185.3  166.52
  5220.0  167.80  5236.8  169.12  5296.8  171.64  5301.9  171.48  5314.9  172.37
#Mann=7,-1,0
  4693.2    0.04       0  4784.6    0.05       0  4908.2    0.12       0
  4993.9    0.05       0  4997.9    0.12       0  5050.0    0.05       0
  5120.4    0.04       0
Bank Sta=4993.9,4997.9
Exp/Cntr=0.3,0.1

Type RM Length L Ch R = 1,2662,241,241,241
BEGIN DESCRIPTION:
Mapping XS 38a9e123
END DESCRIPTION:
XS GIS Cut Line= 4
      2540698.29     13541030.28      2540822.63     13540776.30
      2540798.82     13540585.83      2540664.61     13540288.45
#Sta/Elev= 30
  4615.2  169.21  4690.4  166.57  4743.6  163.88  4788.1  163.02  4810.4  161.53
  4892.9  159.05  4895.8  158.43  4916.8  158.27  4969.8  155.71  4990.0  153.48
  4995.4  150.69  4995.7  150.19  4999.2  150.19  4999.4  150.69  5020.2  152.31
  5030.2  154.08  5040.4  155.44  5138.0  160.36  5145.7  161.48  5155.6  162.08
  5161.1  161.66  5178.6  163.52  5202.2  164.54  5230.5  166.54  5276.7  168.77
  5282.2  168.58  5305.3  170.72  5333.9  171.18  5374.7  173.39  5416.2  174.70
#Mann=6,-1,0
  4615.2    0.04       0  4895.8    0.05       0  4995.4    0.05       0
  4999.4    0.05       0  5030.2    0.12       0  5202.2    0.05       0
Bank Sta=4995.4,4999.4
Exp/Cntr=0.3,0.1

Type RM Length L Ch R = 1,2421,337,337,337
BEGIN DESCRIPTION:
Mapping XS ffbe8ac8
END DESCRIPTION:
XS GIS Cut Line= 4
      2541113.64     13541067.35      2541052.79     13540673.13
      2540989.29     13540503.82      2540815.64     13540248.60
#Sta/Elev= 30
  4549.5  169.87  4562.0  169.97  4602.5  167.73  4624.7  167.38  4638.4  166.36
  4769.7  161.86  4855.4  157.99  4888.6  156.87  4959.4  154.48  4978.4  151.91
  4985.3  150.35  4997.8  149.18  4998.0  148.68  5001.5  148.68  5001.8  149.18
  5009.2  150.65  5014.5  151.08  5021.1  152.91  5079.5  155.09  5117.3  157.83
  5128.2  159.35  5160.8  161.32  5188.3  162.51  5196.7  163.39  5217.7  163.92
  5253.6  166.03  5260.8  166.80  5318.5  168.88  5406.0  172.95  5437.9  173.92
#Mann=8,-1,0
  4549.5    0.12       0  4624.7    0.05       0  4888.6    0.04       0
  4985.3    0.05       0  4997.8    0.05       0  5001.8    0.05       0
  5079.5    0.12       0  5318.5    0.05       0
Bank Sta=4997.8,5001.8
Exp/Cntr=0.3,0.1

Type RM Length L Ch R = 1,2084,64,64,64
BEGIN DESCRIPTION:
Mapping XS 7dddcd1d
END DESCRIPTION:
XS GIS Cut Line= 6
      2541256.48     13541083.14      2541240.61     13540625.51
      2541264.42     13540530.27      2541259.13     13540482.65
      2541208.87     13540440.32      2540942.57     13540279.49
#Sta/Elev= 30
  4294.2  172.62  4430.2  167.69  4522.5  164.53  4542.5  163.08  4640.2  158.92
  4692.6  156.86  4738.9  154.06  4749.9  152.18  4754.9  152.18  4773.2  150.26
  4783.6  148.63  4792.9  148.25  4793.2  147.75  4796.7  147.75  4796.9  148.25
  4942.6  148.26  4949.1  149.57  4963.2  149.86  4979.1  152.53  4984.9  154.43
  4991.8  153.67  5000.4  150.44  5006.3  151.59  5015.1  150.23  5027.6  153.79
  5043.1  157.21  5066.4  158.35  5211.9  167.18  5271.2  169.44  5275.0  169.41
#Mann=8,-1,0
  4294.2    0.12       0  4430.2    0.05       0  4640.2    0.04       0
  4738.9    0.05       0  4792.9    0.05       0  4796.9    0.05       0
  5066.4    0.12       0  5271.2    0.05       0
Bank Sta=4792.9,4796.9
Exp/Cntr=0.3,0.1

Type RM Length L Ch R = 1,2020,47,47,47
BEGIN DESCRIPTION:
Mapping XS ee7f69fc
END DESCRIPTION:
XS GIS Cut Line= 6
      2541314.68     13541093.74      2541277.65     13540678.42
      2541306.75     13540606.99      2541322.62     13540474.72
      2541272.36     13540416.52      2540904.63     13540181.07
#Sta/Elev= 30
  4194.6  173.33  4313.7  169.69  4551.3  159.62  4610.8  156.52  4636.9  156.32
  4652.9  158.01  4687.1  159.57  4771.8  157.01  4811.8  159.08  4834.9  159.10
  4841.5  157.67  4870.0  159.24  4876.7  158.26  4906.5  159.01  4912.4  157.87
  4942.9  158.55  4948.8  157.04  4979.0  156.69  4985.1  153.87  4991.1  153.59
  5000.4  149.19  5004.3  149.10  5004.5  148.60  5008.3  149.10  5014.7  151.77
  5021.5  157.02  5040.0  158.03  5048.4  158.42  5234.6  168.67  5335.7  172.19
#Mann=9,-1,0
  4194.6    0.12       0  4313.7    0.05       0  4551.3    0.04       0
  4652.9    0.05       0  5004.3    0.05       0  5008.3    0.05       0
  5040.0    0.04       0  5048.4    0.12       0  5234.6    0.05       0
Bank Sta=5004.3,5008.3
Exp/Cntr=0.3,0.1

Type RM Length L Ch R = 1,1973,329,329,329
BEGIN DESCRIPTION:
Mapping XS b78650d5
END DESCRIPTION:
XS GIS Cut Line= 6
      2541346.43     13541075.24      2541325.27     13540694.29
      2541370.24     13540559.37      2541367.60     13540477.36
      2541327.67     13540417.07      2541010.43     13540154.59
#Sta/Elev= 30
  4184.5  173.37  4267.3  170.88  4332.9  169.34  4521.5  160.60  4789.7  149.96
  4817.4  151.11  4823.4  152.96  4840.2  151.73  4844.4  152.65  4853.5  151.59
  4859.5  152.82  4861.6  151.40  4873.9  152.72  4880.4  151.76  4902.5  154.08
  4909.0  153.13  4916.9  154.09  4937.7  152.92  4952.0  154.00  4958.5  153.00
  4979.7  153.42  4999.5  149.51  4999.8  149.01  5003.5  149.51  5030.2  154.68
  5058.9  157.32  5073.2  160.19  5095.9  161.66  5234.0  166.90  5275.1  168.72
#Mann=9,-1,0
  4184.5    0.12       0  4267.3    0.05       0  4521.5    0.04       0
  4840.2    0.05       0  4979.7    0.04       0  4999.5    0.04       0
  5003.5    0.04       0  5095.9    0.12       0  5234.0    0.05       0
Bank Sta=4999.5,5003.5
Exp/Cntr=0.3,0.1

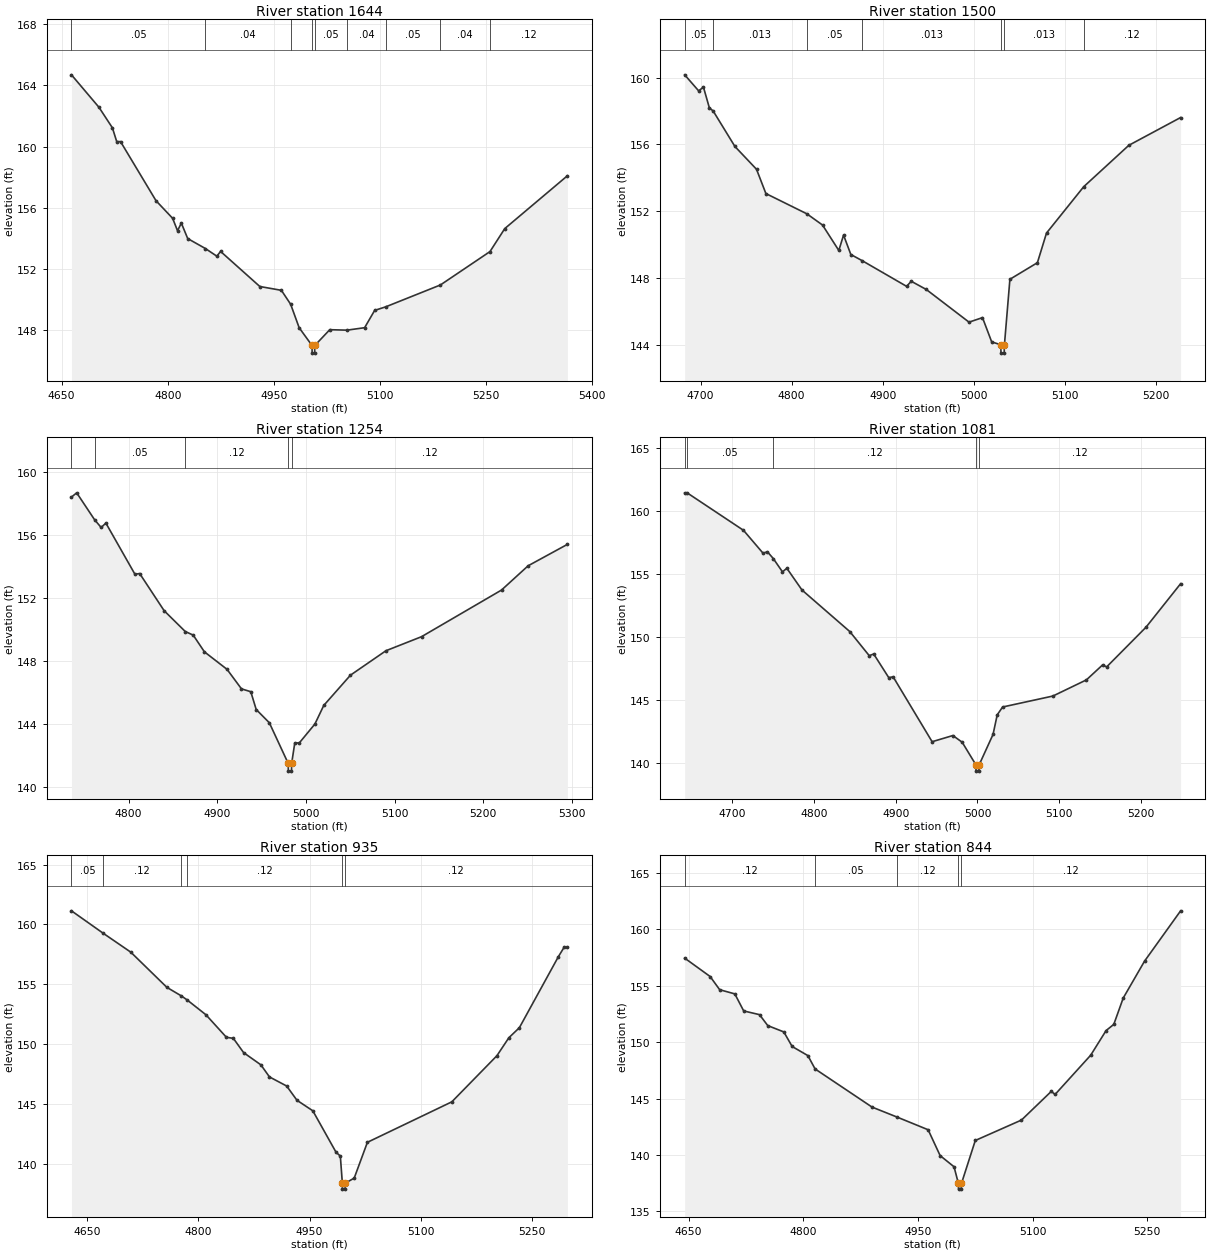
Type RM Length L Ch R = 1,1644,144,144,144
BEGIN DESCRIPTION:
Mapping XS 9d958c91
END DESCRIPTION:
XS GIS Cut Line= 3
      2541592.47     13540739.28      2541473.41     13540416.52
      2541214.18     13540170.51
#Sta/Elev= 30
  4663.9  164.69  4702.8  162.57  4721.8  161.23  4727.9  160.33  4733.3  160.33
  4783.5  156.47  4807.0  155.32  4813.9  154.51  4819.3  155.01  4828.3  154.00
  4853.3  153.35  4869.5  152.85  4874.8  153.16  4930.3  150.87  4960.8  150.62
  4973.9  149.71  4985.9  148.18  5004.1  147.02  5004.3  146.52  5007.8  146.52
  5008.1  147.02  5029.2  148.05  5053.6  148.02  5078.5  148.18  5092.7  149.31
  5108.2  149.54  5185.7  150.97  5255.8  153.15  5276.7  154.65  5365.3  158.10
#Mann=9,-1,0
  4663.9    0.05       0  4853.3    0.04       0  4973.9    0.05       0
  5004.1    0.05       0  5008.1    0.05       0  5053.6    0.04       0
  5108.2    0.05       0  5185.7    0.04       0  5255.8    0.12       0
Bank Sta=5004.1,5008.1
Exp/Cntr=0.3,0.1

Type RM Length L Ch R = 1,1500,246,246,246
BEGIN DESCRIPTION:
Mapping XS 6abb7aac
END DESCRIPTION:
XS GIS Cut Line= 3
      2541685.06     13540681.11      2541603.04     13540379.48
      2541582.03     13540148.31
#Sta/Elev= 30
  4682.5  160.16  4697.9  159.20  4703.1  159.43  4709.6  158.19  4713.8  158.00
  4737.7  155.88  4761.4  154.52  4771.7  153.07  4816.7  151.86  4833.9  151.19
  4851.8  149.67  4857.0  150.59  4865.0  149.43  4877.5  149.06  4926.2  147.53
  4931.4  147.83  4947.9  147.34  4994.8  145.39  5009.6  145.66  5019.7  144.21
  5029.7  144.04  5029.9  143.54  5033.4  143.54  5033.7  144.04  5039.7  147.95
  5069.9  148.94  5079.9  150.71  5120.8  153.48  5170.3  155.95  5227.2  157.61
#Mann=7,-1,0
  4682.5    0.05       0  4713.8   0.013       0  4816.7    0.05       0
  4877.5   0.013       0  5029.7    0.03       0  5033.7   0.013       0
  5120.8    0.12       0
Bank Sta=5029.7,5033.7
Exp/Cntr=0.3,0.1

Type RM Length L Ch R = 1,1254,173,173,173
BEGIN DESCRIPTION:
Mapping XS 6002b17e
END DESCRIPTION:
XS GIS Cut Line= 3
      2541759.12     13540678.43      2541833.20     13540435.03
      2541814.68     13540130.82
#Sta/Elev= 30
  4735.6  158.41  4741.5  158.68  4761.7  156.97  4769.1  156.48  4774.4  156.76
  4807.2  153.51  4812.5  153.56  4840.1  151.20  4863.9  149.88  4872.9  149.65
  4885.5  148.59  4911.0  147.48  4927.3  146.24  4937.8  146.06  4943.9  144.93
  4958.7  144.09  4979.9  141.52  4980.2  141.02  4983.7  141.02  4983.9  141.52
  4987.4  142.81  4992.5  142.81  5010.1  144.01  5020.1  145.19  5050.2  147.11
  5090.2  148.66  5130.3  149.55  5220.5  152.51  5250.5  154.05  5294.8  155.41
#Mann=5,-1,0
  4735.6   0.013       0  4761.7    0.05       0  4863.9    0.12       0
  4979.9    0.05       0  4983.9    0.12       0
Bank Sta=4979.9,4983.9
Exp/Cntr=0.3,0.1

Type RM Length L Ch R = 1,1081,146,146,146
BEGIN DESCRIPTION:
Mapping XS 3608c4dc
END DESCRIPTION:
XS GIS Cut Line= 3
      2541872.88     13540757.77      2541997.21     13540458.84
      2542060.35     13540182.62
#Sta/Elev= 30
  4641.6  161.43  4644.6  161.43  4713.6  158.46  4737.5  156.65  4742.9  156.76
  4750.1  156.22  4761.3  155.17  4766.7  155.45  4785.2  153.73  4843.7  150.44
  4867.5  148.53  4873.0  148.66  4891.4  146.79  4896.8  146.85  4944.5  141.71
  4969.9  142.20  4981.3  141.67  4998.1  139.88  4998.3  139.38  5001.8  139.38
  5002.1  139.88  5019.1  142.29  5024.2  143.84  5030.8  144.46  5092.4  145.33
  5133.4  146.61  5153.1  147.79  5158.2  147.64  5206.3  150.78  5248.7  154.23
#Mann=5,-1,0
  4641.6   0.013       0  4644.6    0.05       0  4750.1    0.12       0
  4998.1    0.05       0  5002.1    0.12       0
Bank Sta=4998.1,5002.1
Exp/Cntr=0.3,0.1

Type RM Length L Ch R = 1,935,91,91,91
BEGIN DESCRIPTION:
Mapping XS 4d01ff2f
END DESCRIPTION:
XS GIS Cut Line= 3
      2541946.93     13540794.85      2542134.78     13540477.36
      2542182.40     13540181.07
#Sta/Elev= 30
  4628.9  161.14  4672.1  159.25  4708.9  157.69  4757.6  154.75  4777.0  154.04
  4784.7  153.71  4810.3  152.46  4837.9  150.58  4847.3  150.49  4861.1  149.30
  4884.4  148.28  4896.0  147.27  4919.2  146.51  4933.1  145.32  4954.5  144.44
  4985.8  140.98  4991.6  140.66  4994.3  138.40  4994.5  137.90  4998.0  137.90
  4998.3  138.40  5010.3  138.82  5028.1  141.81  5142.0  145.19  5202.8  149.04
  5218.9  150.54  5233.1  151.38  5285.8  157.32  5293.4  158.09  5297.9  158.09
#Mann=6,-1,0
  4628.9    0.05       0  4672.1    0.12       0  4777.0    0.05       0
  4784.7    0.12       0  4994.3    0.05       0  4998.3    0.12       0
Bank Sta=4994.3,4998.3
Exp/Cntr=0.3,0.1

Type RM Length L Ch R = 1,844,185,185,185
BEGIN DESCRIPTION:
Mapping XS 4ebcce54
END DESCRIPTION:
XS GIS Cut Line= 3
      2542118.91     13540818.61      2542224.72     13540485.30
      2542258.91     13540188.16
#Sta/Elev= 30
  4644.9  157.44  4678.2  155.81  4690.7  154.64  4710.5  154.27  4722.1  152.76
  4742.8  152.43  4753.6  151.46  4774.6  150.90  4785.5  149.61  4806.1  148.80
  4815.5  147.62  4890.0  144.24  4923.3  143.34  4963.4  142.23  4979.1  139.94
  4997.3  138.95  5003.0  137.47  5003.2  136.97  5006.7  136.97  5007.0  137.47
  5025.1  141.28  5085.5  143.09  5124.5  145.63  5129.5  145.36  5176.1  148.84
  5196.2  151.02  5206.3  151.57  5218.6  153.90  5246.5  157.17  5293.7  161.63
#Mann=5,-1,0
  4644.9    0.12       0  4815.5    0.05       0  4923.3    0.12       0
  5003.0    0.05       0  5007.0    0.12       0
Bank Sta=5003,5007
Exp/Cntr=0.3,0.1

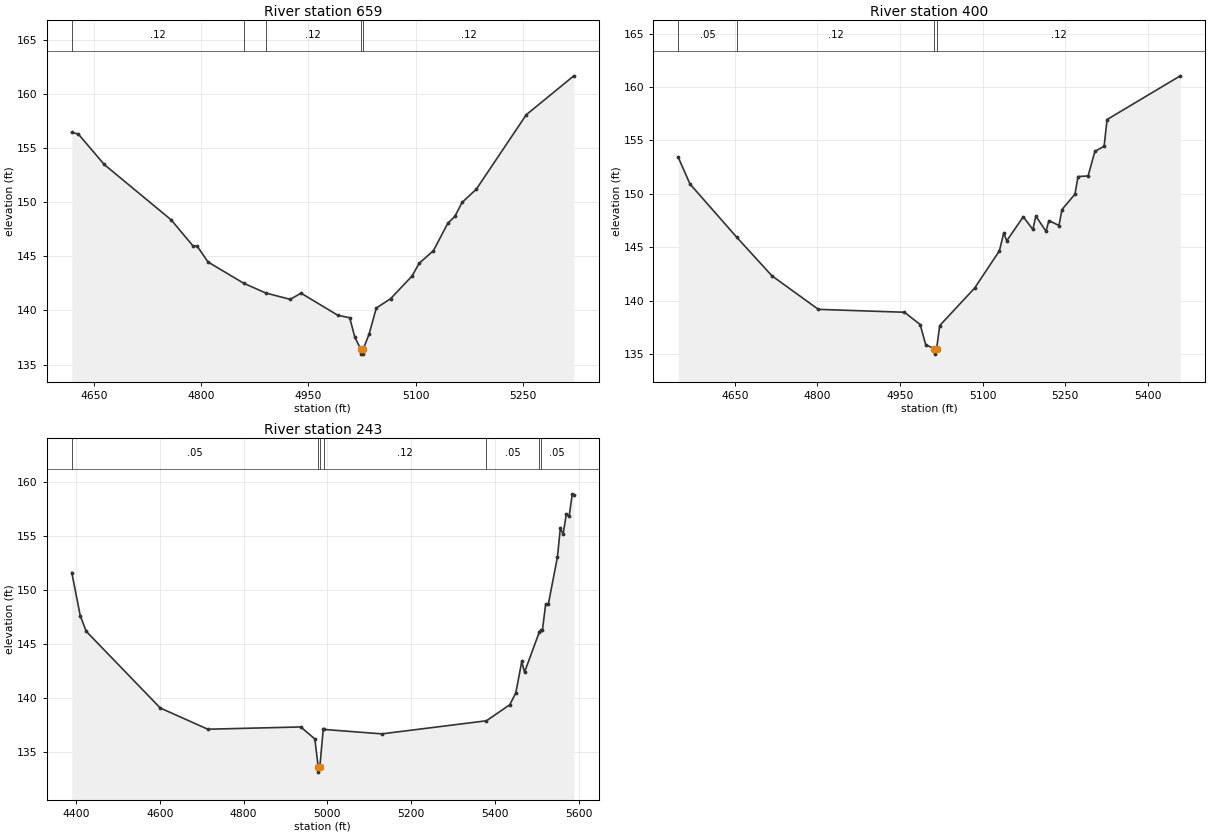
Type RM Length L Ch R = 1,659,259,259,259
BEGIN DESCRIPTION:
Mapping XS 85cde202
END DESCRIPTION:
XS GIS Cut Line= 3
      2542166.50     13540839.82      2542375.52     13540514.40
      2542370.25     13540198.51
#Sta/Elev= 30
  4618.7  156.44  4627.8  156.30  4664.1  153.48  4757.9  148.36  4788.3  145.96
  4794.2  145.94  4809.4  144.47  4859.3  142.51  4890.1  141.61  4924.4  141.02
  4939.6  141.59  4991.1  139.55  5007.7  139.32  5014.9  137.52  5022.9  136.46
  5023.1  135.96  5026.6  135.96  5026.9  136.46  5034.9  137.82  5044.9  140.22
  5064.9  141.08  5094.9  143.17  5104.9  144.35  5124.9  145.52  5144.9  148.04
  5154.9  148.69  5164.9  149.97  5184.9  151.20  5254.9  158.08  5321.4  161.67
#Mann=5,-1,0
  4618.7    0.12       0  4859.3    0.05       0  4890.1    0.12       0
  5022.9    0.05       0  5026.9    0.12       0
Bank Sta=5022.9,5026.9
Exp/Cntr=0.3,0.1

Type RM Length L Ch R = 1,400,157,157,157
BEGIN DESCRIPTION:
TRIB 11_1 TO GUADALUPE RIVER 1.0
END DESCRIPTION:
XS GIS Cut Line= 3
      2542274.99     13540875.00      2542614.81     13540575.45
      2542436.38     13540152.01
#Sta/Elev= 30
  4547.0  153.43  4568.3  150.93  4653.0  145.96  4717.3  142.33  4801.7  139.19
  4958.2  138.92  4986.7  137.77  4996.8  135.88  5012.6  135.50  5012.8  135.00
  5016.6  135.50  5022.2  137.67  5085.8  141.19  5130.7  144.67  5138.6  146.34
  5144.1  145.61  5174.1  147.86  5191.5  146.67  5197.0  147.92  5215.3  146.50
  5220.7  147.50  5239.0  147.04  5244.4  148.53  5268.1  149.98  5273.6  151.62
  5291.9  151.68  5304.3  153.98  5321.0  154.46  5326.4  156.96  5459.5  161.05
#Mann=4,-1,0
  4547.0    0.05       0  4653.0    0.12       0  5012.6    0.05       0
  5016.6    0.12       0
Bank Sta=5012.6,5016.6
Exp/Cntr=0.3,0.1

Type RM Length L Ch R = 1,243,0,0,0
BEGIN DESCRIPTION:
LGII3252
END DESCRIPTION:
XS GIS Cut Line= 4
      2542438.43     13541057.34      2542768.26     13540697.12
      2542776.94     13540397.64      2542465.28     13540129.27
#Sta/Elev= 30
  4389.5  151.61  4409.8  147.61  4424.0  146.17  4601.0  139.07  4714.5  137.11
  4936.5  137.32  4970.1  136.21  4978.1  133.64  4978.3  133.14  4982.1  133.64
  4990.1  137.11  4992.0  137.09  5130.1  136.68  5379.9  137.89  5435.9  139.38
  5450.2  140.48  5464.4  143.38  5471.0  142.39  5506.6  146.13  5509.5  146.26
  5513.8  146.29  5521.5  148.68  5528.1  148.73  5549.6  153.04  5556.6  155.73
  5563.2  155.15  5570.9  157.03  5577.5  156.80  5585.1  158.89  5588.8  158.76
#Mann=7,-1,0
  4389.5    0.05       0  4978.1    0.05       0  4982.1    0.05       0
  4992.0    0.12       0  5379.9    0.05       0  5506.6    0.12       0
  5509.5    0.05       0
Bank Sta=4978.1,4982.1
Exp/Cntr=0.3,0.1

Chan Stop Cuts=-1