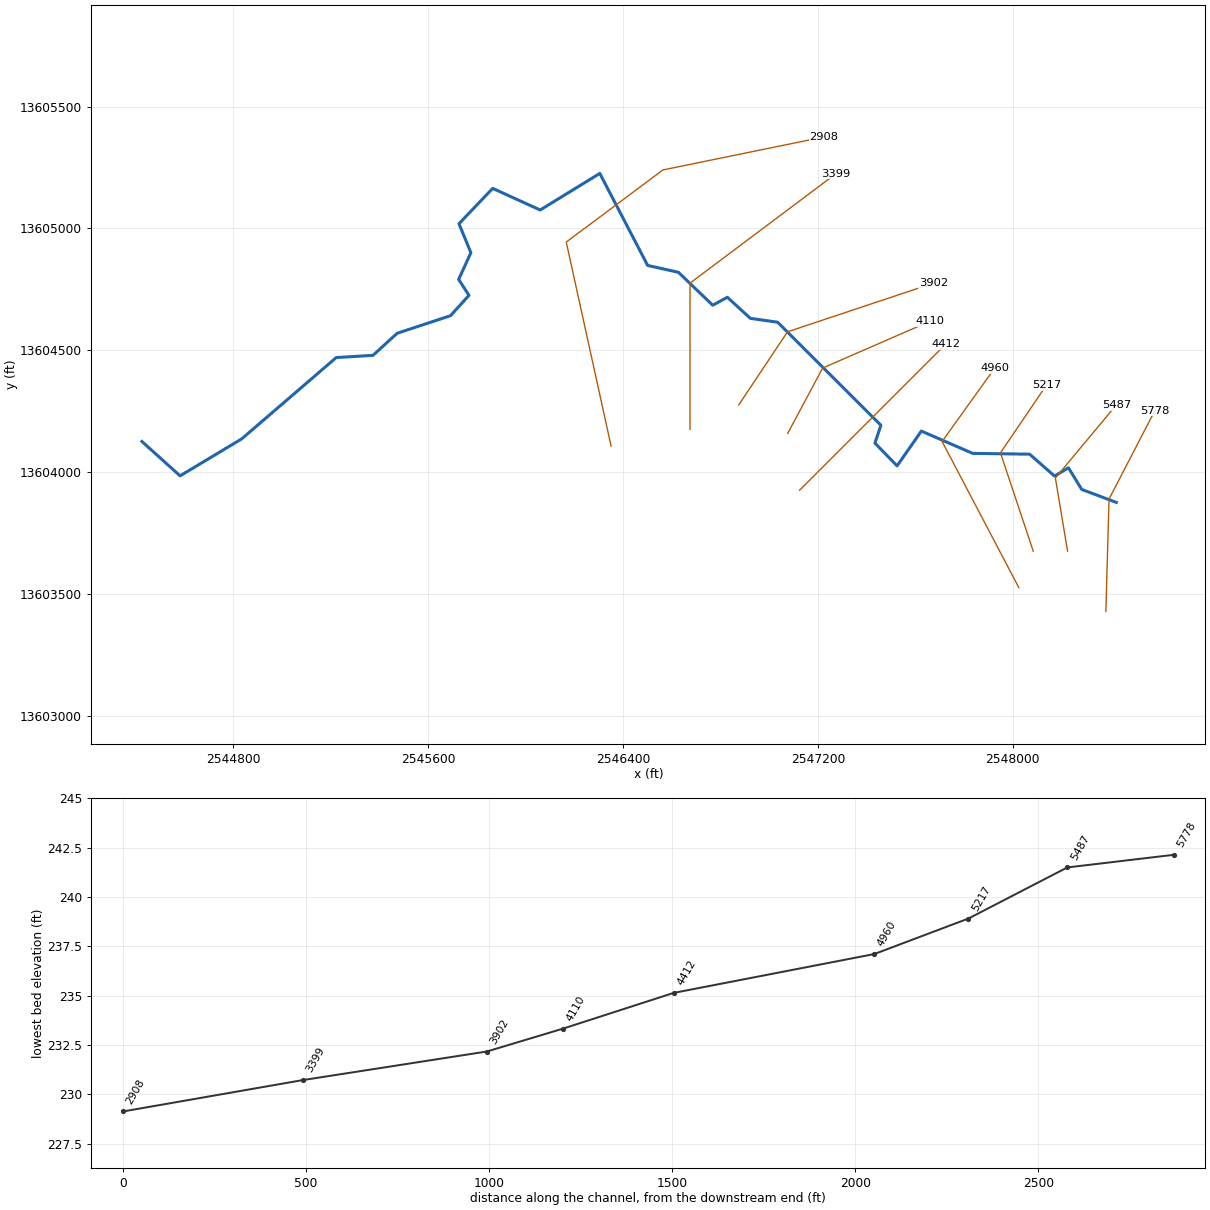
--- TRIB 11_1 TO IRISH CREEK.prj (project) ---

Proj Title=TRIB 11_1 TO IRISH CREEK Base Level Engineering
Current Plan=p01
Default Exp/Contr=0.3,0.1
English Units
Geom File=g01
Flow File=f01
Plan File=p01
BEGIN DESCRIPTION:
TRIB 11_1 TO IRISH CREEK
END DESCRIPTION:

--- TRIB 11_1 TO IRISH CREEK.p01 (plan) ---

Plan Title=Multiple Run
Short Identifier=Multiple
Geom File=g01
Flow File=f01
Subcritical Flow
K Sum by GR= 0
Std Step Tol= 0.01
Critical Tol= 0.01
Num of Std Step Trials= 20
Max Error Tol= 0.3
Flow Tol Ratio= 0.001
Split Flow NTrial= 30
Split Flow Tol= 0.02
Split Flow Ratio= 0.02
Log Output Level= 0
Friction Slope Method= 1
Unsteady Friction Slope Method= 2
Unsteady Bridges Friction Slope Method= 1
Parabolic Critical Depth
Global Vel Dist=  1 , 1 , 1
Global Log Level= 0
CheckData=True
Encroach Param= -1, 0, 0, 0
BEGIN DESCRIPTION:
Multiple Run
END DESCRIPTION:

--- TRIB 11_1 TO IRISH CREEK.f01 (steady flow) ---

Flow Title=Multiple
Number of Profiles=7
Profile Names=10-year,25-year,50-year,1pct_min,100-year,1pct_plu,500-year
River Rch & RM= TRIB 11_1 TO IRI,Reach-1,5778
     402     627     823     526    1049    2093    1681
River Rch & RM= TRIB 11_1 TO IRI,Reach-1,4412
     585     931    1241     802    1600    3193    2631
Boundary for River Rch & Prof#=TRIB 11_1 TO IRI,Reach-1,1
Up Type=0
Dn Type=3
Dn Slope=0.005
Boundary for River Rch & Prof#=TRIB 11_1 TO IRI,Reach-1,2
Up Type=0
Dn Type=3
Dn Slope=0.005
Boundary for River Rch & Prof#=TRIB 11_1 TO IRI,Reach-1,3
Up Type=0
Dn Type=3
Dn Slope=0.005
Boundary for River Rch & Prof#=TRIB 11_1 TO IRI,Reach-1,4
Up Type=0
Dn Type=3
Dn Slope=0.005
Boundary for River Rch & Prof#=TRIB 11_1 TO IRI,Reach-1,5
Up Type=0
Dn Type=3
Dn Slope=0.005
Boundary for River Rch & Prof#=TRIB 11_1 TO IRI,Reach-1,6
Up Type=0
Dn Type=3
Dn Slope=0.005
Boundary for River Rch & Prof#=TRIB 11_1 TO IRI,Reach-1,7
Up Type=0
Dn Type=3
Dn Slope=0.005

--- TRIB 11_1 TO IRISH CREEK.g01 (geometry) ---

Geom Title=Existing Conditions

River Reach=TRIB 11_1 TO IRI,Reach-1
Reach XY= 30
      2548425.00     13603875.00      2548283.31     13603928.17
      2548228.56     13604017.06      2548171.68     13603983.02
      2548069.15     13604072.93      2547835.50     13604076.22
      2547624.69     13604167.79      2547525.00     13604025.00
      2547434.17     13604118.33      2547458.61     13604191.67
      2547034.79     13604614.48      2546922.57     13604630.55
      2546828.33     13604716.98      2546768.33     13604684.30
      2546627.42     13604819.47      2546501.10     13604847.72
      2546304.67     13605225.32      2546059.78     13605075.24
      2545865.00     13605164.04      2545726.62     13605018.97
      2545775.38     13604900.00      2545725.24     13604790.34
      2545767.66     13604724.90      2545691.82     13604641.46
      2545472.71     13604569.15      2545373.53     13604478.55
      2545222.56     13604469.52      2544834.68     13604135.76
      2544581.66     13603983.97      2544425.00     13604125.00

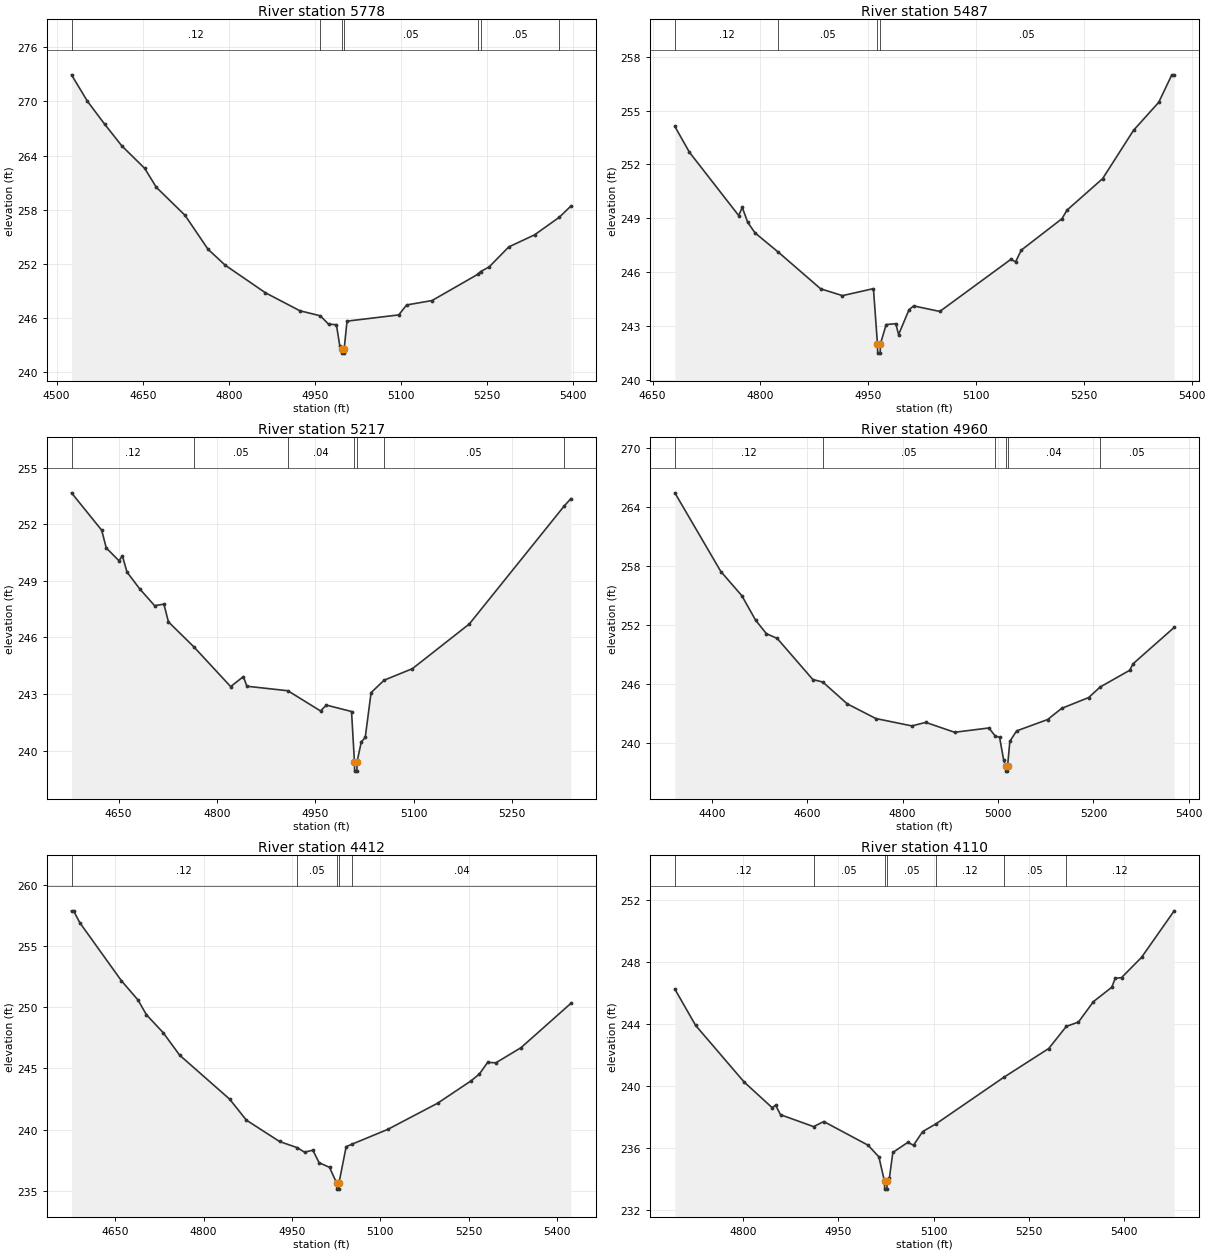
Type RM Length L Ch R = 1,5778,291,291,291
BEGIN DESCRIPTION:
TRIB 11_1 TO IRISH CREEK 7.0
END DESCRIPTION:
XS GIS Cut Line= 3
      2548382.23     13603427.43      2548395.22     13603888.51
      2548583.00     13604251.12
#Sta/Elev= 30
  4525.9  272.94  4553.5  270.03  4583.5  267.49  4613.5  265.08  4653.5  262.58
  4673.5  260.50  4723.5  257.40  4763.6  253.64  4793.6  251.87  4863.6  248.82
  4923.6  246.83  4959.2  246.27  4973.6  245.34  4987.2  245.29  4993.2  242.91
  4996.8  242.64  4997.1  242.14  5000.6  242.14  5000.8  242.64  5005.7  245.68
  5095.8  246.37  5109.5  247.47  5153.8  247.96  5233.1  250.85  5238.4  251.17
  5253.2  251.68  5287.3  253.89  5332.3  255.23  5375.4  257.18  5395.5  258.41
#Mann=7,-1,0
  4525.9    0.12       0  4959.2    0.05       0  4996.8    0.05       0
  5000.8    0.05       0  5233.1    0.04       0  5238.4    0.05       0
  5375.4    0.04       0
Bank Sta=4996.8,5000.8
Exp/Cntr=0.3,0.1

Type RM Length L Ch R = 1,5487,270,270,270
BEGIN DESCRIPTION:
TRIB 11_1 TO IRISH CREEK 6.0
END DESCRIPTION:
XS GIS Cut Line= 3
      2548225.01     13603674.96      2548175.00     13603975.00
      2548425.00     13604275.00
#Sta/Elev= 30
  4681.0  254.12  4701.3  252.68  4769.8  249.16  4774.8  249.61  4782.4  248.78
  4792.6  248.19  4825.0  247.12  4883.8  245.08  4914.2  244.70  4957.3  245.09
  4962.9  242.00  4963.2  241.50  4966.7  241.50  4966.9  242.00  4975.0  243.09
  4988.4  243.14  4992.3  242.53  5006.7  243.91  5013.2  244.13  5049.6  243.82
  5148.5  246.72  5155.1  246.58  5162.9  247.23  5219.5  248.98  5226.6  249.46
  5276.1  251.21  5319.1  253.90  5354.2  255.46  5372.4  256.99  5375.7  256.99
#Mann=4,-1,0
  4681.0    0.12       0  4825.0    0.05       0  4962.9    0.05       0
  4966.9    0.05       0
Bank Sta=4962.9,4966.9
Exp/Cntr=0.3,0.1

Type RM Length L Ch R = 1,5217,257,257,257
BEGIN DESCRIPTION:
Mapping XS 24761f34
END DESCRIPTION:
XS GIS Cut Line= 3
      2548084.02     13603674.76      2547949.45     13604078.45
      2548138.26     13604356.23
#Sta/Elev= 30
  4578.1  253.66  4624.1  251.68  4631.1  250.74  4650.5  250.06  4655.7  250.32
  4662.7  249.46  4682.1  248.57  4704.8  247.68  4719.0  247.76  4725.9  246.82
  4764.3  245.51  4820.8  243.39  4840.2  243.92  4845.5  243.41  4908.0  243.17
  4957.8  242.10  4966.7  242.41  5005.1  242.07  5009.5  239.41  5009.8  238.91
  5013.3  238.91  5013.5  239.41  5020.0  240.46  5026.0  240.70  5034.9  243.07
  5054.8  243.73  5097.9  244.34  5184.7  246.71  5329.3  252.96  5339.5  253.35
#Mann=7,-1,0
  4578.1    0.12       0  4764.3    0.05       0  4908.0    0.04       0
  5009.5    0.04       0  5013.5    0.04       0  5054.8    0.05       0
  5329.3    0.04       0
Bank Sta=5009.5,5013.5
Exp/Cntr=0.3,0.1

Type RM Length L Ch R = 1,4960,548,548,548
BEGIN DESCRIPTION:
TRIB 11_1 TO IRISH CREEK 5.0
END DESCRIPTION:
XS GIS Cut Line= 3
      2548024.99     13603525.02      2547709.91     13604124.91
      2547924.99     13604424.99
#Sta/Elev= 30
  4322.4  265.48  4418.8  257.46  4462.9  254.99  4491.8  252.49  4514.4  251.12
  4537.0  250.64  4611.6  246.45  4632.6  246.19  4683.8  243.97  4743.8  242.47
  4819.4  241.72  4848.4  242.08  4908.9  241.07  4980.7  241.51  4994.2  240.68
  5003.2  240.55  5011.8  238.22  5015.9  237.61  5016.2  237.11  5019.7  237.11
  5019.9  237.61  5024.7  240.15  5038.8  241.21  5103.9  242.37  5133.4  243.51
  5189.9  244.61  5214.2  245.69  5275.9  247.39  5283.1  248.06  5369.2  251.76
#Mann=6,-1,0
  4322.4    0.12       0  4632.6    0.05       0  4994.2    0.04       0
  5015.9    0.04       0  5019.9    0.04       0  5214.2    0.05       0
Bank Sta=5015.9,5019.9
Exp/Cntr=0.3,0.1

Type RM Length L Ch R = 1,4412,302,302,302
BEGIN DESCRIPTION:
TRIB 11_1 TO IRISH CREEK 4.0
END DESCRIPTION:
XS GIS Cut Line= 3
      2547125.01     13603925.01      2547425.00     13604225.00
      2547724.99     13604524.99
#Sta/Elev= 30
  4575.4  257.87  4578.9  257.87  4589.5  256.90  4660.2  252.16  4688.5  250.58
  4702.7  249.38  4731.0  247.93  4759.2  246.08  4844.1  242.49  4872.4  240.78
  4928.9  239.03  4958.7  238.53  4971.4  238.16  4985.5  238.32  4996.1  237.30
  5013.8  236.92  5025.9  235.64  5026.2  235.14  5029.7  235.14  5029.9  235.64
  5042.1  238.61  5052.5  238.82  5112.8  240.02  5197.6  242.16  5254.2  243.98
  5268.4  244.54  5282.5  245.49  5296.6  245.46  5339.1  246.69  5423.9  250.31
#Mann=5,-1,0
  4575.4    0.12       0  4958.7    0.05       0  5025.9    0.05       0
  5029.9    0.05       0  5052.5    0.04       0
Bank Sta=5025.9,5029.9
Exp/Cntr=0.3,0.1

Type RM Length L Ch R = 1,4110,208,208,208
BEGIN DESCRIPTION:
Mapping XS c91b2204
END DESCRIPTION:
XS GIS Cut Line= 3
      2547076.20     13604158.34      2547219.42     13604426.54
      2547661.05     13604618.78
#Sta/Elev= 30
  4692.7  246.26  4725.3  243.92  4801.8  240.25  4845.7  238.60  4851.3  238.75
  4859.0  238.14  4911.1  237.37  4927.0  237.70  4996.7  236.17  5013.7  235.42
  5022.6  233.83  5022.9  233.33  5026.4  233.33  5026.6  233.83  5030.3  234.05
  5035.7  235.70  5059.2  236.35  5068.3  236.17  5082.6  237.05  5104.0  237.56
  5210.0  240.55  5281.0  242.42  5308.7  243.85  5327.8  244.13  5351.3  245.45
  5380.2  246.38  5385.6  246.96  5395.5  247.00  5427.0  248.31  5478.4  251.32
#Mann=7,-1,0
  4692.7    0.12       0  4911.1    0.05       0  5022.6    0.05       0
  5026.6    0.05       0  5104.0    0.12       0  5210.0    0.05       0
  5308.7    0.12       0
Bank Sta=5022.6,5026.6
Exp/Cntr=0.3,0.1

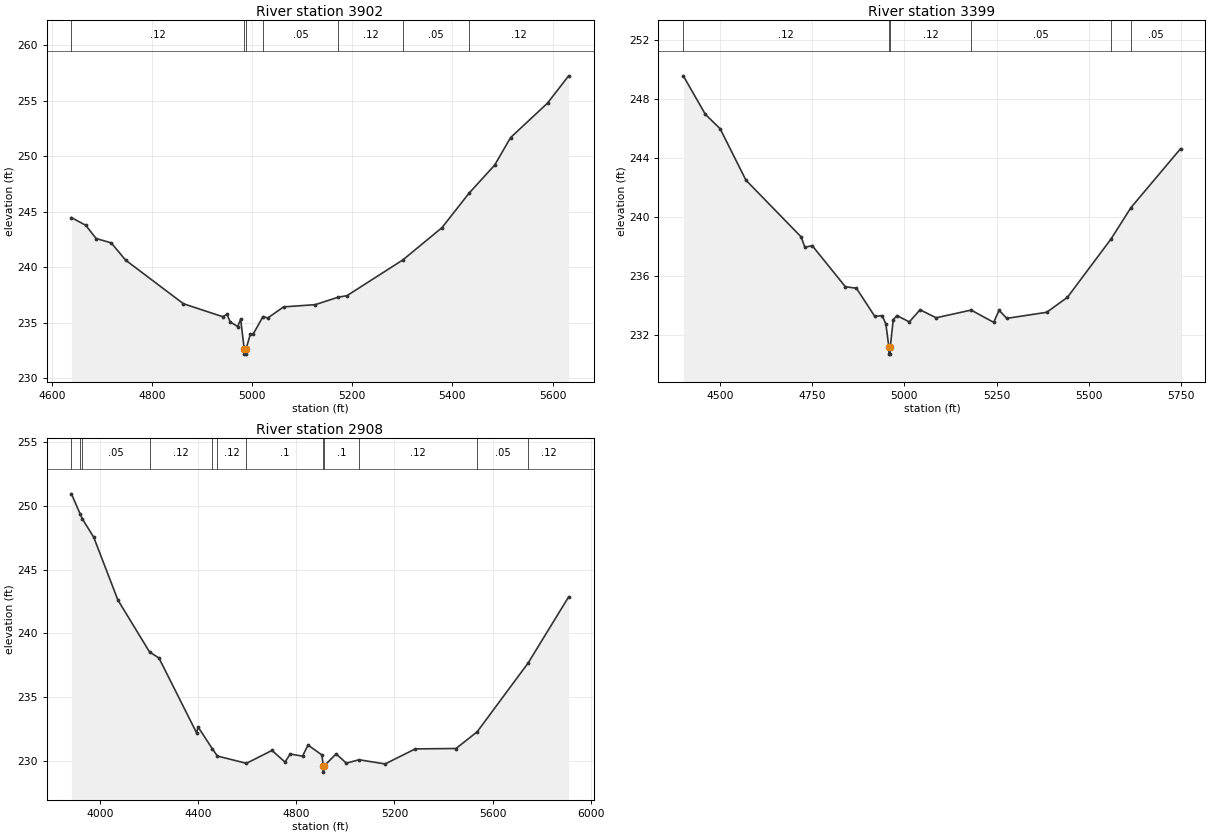
Type RM Length L Ch R = 1,3902,503,503,503
BEGIN DESCRIPTION:
TRIB 11_1 TO IRISH CREEK 3.0
END DESCRIPTION:
XS GIS Cut Line= 3
      2546875.02     13604275.03      2547075.00     13604575.00
      2547675.02     13604775.01
#Sta/Elev= 30
  4639.2  244.48  4667.7  243.79  4688.7  242.59  4718.8  242.20  4747.3  240.65
  4863.0  236.71  4941.1  235.55  4950.1  235.75  4956.2  235.08  4971.2  234.66
  4977.2  235.32  4984.2  232.67  4984.4  232.17  4987.9  232.17  4988.2  232.67
  4996.7  233.99  5002.4  233.99  5021.8  235.56  5031.3  235.43  5063.0  236.43
  5126.2  236.63  5171.7  237.30  5189.5  237.44  5301.0  240.66  5379.2  243.57
  5433.1  246.67  5484.6  249.22  5516.2  251.69  5590.0  254.80  5632.2  257.26
#Mann=7,-1,0
  4639.2    0.12       0  4984.2    0.05       0  4988.2    0.12       0
  5021.8    0.05       0  5171.7    0.12       0  5301.0    0.05       0
  5433.1    0.12       0
Bank Sta=4984.2,4988.2
Exp/Cntr=0.3,0.1

Type RM Length L Ch R = 1,3399,491,491,491
BEGIN DESCRIPTION:
TRIB 11_1 TO IRISH CREEK 2.0
END DESCRIPTION:
XS GIS Cut Line= 3
      2546675.00     13604174.97      2546675.00     13604775.00
      2547274.97     13605224.98
#Sta/Elev= 30
  4399.7  249.55  4459.7  246.94  4499.7  245.97  4569.7  242.49  4719.7  238.65
  4729.7  237.95  4749.7  238.06  4839.7  235.28  4869.7  235.18  4919.7  233.27
  4939.7  233.33  4949.7  232.75  4957.7  231.22  4958.0  230.72  4961.5  230.72
  4961.7  231.22  4969.7  233.06  4979.7  233.33  5013.3  232.90  5042.4  233.72
  5086.2  233.18  5181.1  233.70  5242.4  232.87  5257.0  233.69  5277.9  233.14
  5386.2  233.55  5442.4  234.56  5560.9  238.51  5615.2  240.64  5749.7  244.62
#Mann=6,-1,0
  4399.7    0.12       0  4957.7    0.05       0  4961.7    0.12       0
  5181.1    0.05       0  5560.9    0.12       0  5615.2    0.05       0
Bank Sta=4957.7,4961.7
Exp/Cntr=0.3,0.1

Type RM Length L Ch R = 1,2908,0,0,0
BEGIN DESCRIPTION:
TRIB 11_1 TO IRISH CREEK 1.0
END DESCRIPTION:
XS GIS Cut Line= 4
      2546351.01     13604106.28      2546166.92     13604943.71
      2546563.97     13605239.69      2547225.01     13605375.00
#Sta/Elev= 30
  3882.9  250.93  3919.4  249.32  3927.1  248.98  3973.7  247.54  4072.5  242.61
  4201.7  238.54  4239.9  238.07  4393.5  232.20  4399.3  232.67  4457.2  230.97
  4478.2  230.39  4596.6  229.82  4700.7  230.83  4753.7  229.92  4775.3  230.55
  4825.2  230.38  4847.6  231.25  4903.9  230.48  4910.2  229.63  4910.5  229.13
  4914.2  229.63  4962.3  230.56  5004.0  229.83  5055.8  230.10  5162.0  229.77
  5284.8  230.95  5451.0  230.98  5537.4  232.29  5745.5  237.69  5910.3  242.86
#Mann=12,-1,0
  3882.9    0.05       0  3919.4    0.12       0  3927.1    0.05       0
  4201.7    0.12       0  4457.2    0.05       0  4478.2    0.12       0
  4596.6     0.1       0  4910.2    0.05       0  4914.2     0.1       0
  5055.8    0.12       0  5537.4    0.05       0  5745.5    0.12       0
Bank Sta=4910.2,4914.2
Exp/Cntr=0.3,0.1

Chan Stop Cuts=-1