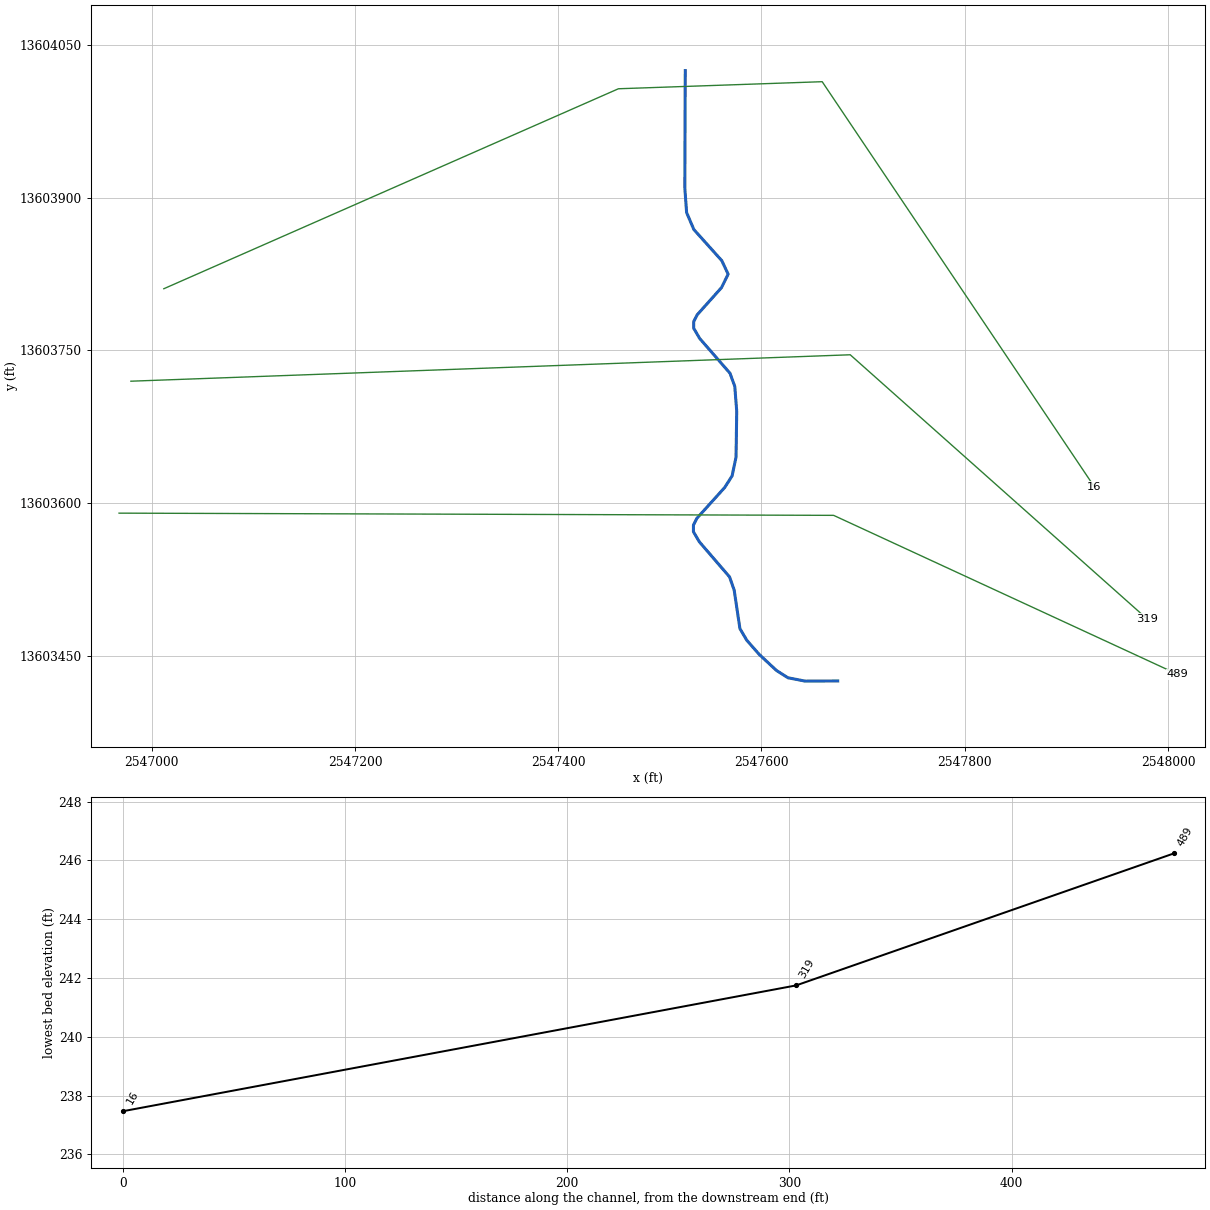
--- TRIB 11_1_1 TO IRISH CREEK.prj (project) ---

Proj Title=TRIB 11_1_1 TO IRISH CREEK Base Level Engineering
Current Plan=p01
Default Exp/Contr=0.3,0.1
English Units
Geom File=g01
Flow File=f01
Plan File=p01
BEGIN DESCRIPTION:
TRIB 11_1_1 TO IRISH CREEK
END DESCRIPTION:

--- TRIB 11_1_1 TO IRISH CREEK.p01 (plan) ---

Plan Title=Multiple Run
Short Identifier=Multiple
Geom File=g01
Flow File=f01
Subcritical Flow
K Sum by GR= 0
Std Step Tol= 0.01
Critical Tol= 0.01
Num of Std Step Trials= 20
Max Error Tol= 0.3
Flow Tol Ratio= 0.001
Split Flow NTrial= 30
Split Flow Tol= 0.02
Split Flow Ratio= 0.02
Log Output Level= 0
Friction Slope Method= 1
Unsteady Friction Slope Method= 2
Unsteady Bridges Friction Slope Method= 1
Parabolic Critical Depth
Global Vel Dist=  1 , 1 , 1
Global Log Level= 0
CheckData=True
Encroach Param= -1, 0, 0, 0
BEGIN DESCRIPTION:
Multiple Run
END DESCRIPTION:

--- TRIB 11_1_1 TO IRISH CREEK.f01 (steady flow) ---

Flow Title=Multiple
Number of Profiles=7
Profile Names=10-year,25-year,50-year,1pct_min,100-year,1pct_plu,500-year
River Rch & RM= TRIB 11_1_1 TO I,Reach-1,489
     189     281     359     223     445     889     676
River Rch & RM= TRIB 11_1_1 TO I,Reach-1,16
     585     931    1241     802    1600    3193    2631
Boundary for River Rch & Prof#=TRIB 11_1_1 TO I,Reach-1,1
Up Type=0
Dn Type=3
Dn Slope=0.005
Boundary for River Rch & Prof#=TRIB 11_1_1 TO I,Reach-1,2
Up Type=0
Dn Type=3
Dn Slope=0.005
Boundary for River Rch & Prof#=TRIB 11_1_1 TO I,Reach-1,3
Up Type=0
Dn Type=3
Dn Slope=0.005
Boundary for River Rch & Prof#=TRIB 11_1_1 TO I,Reach-1,4
Up Type=0
Dn Type=3
Dn Slope=0.005
Boundary for River Rch & Prof#=TRIB 11_1_1 TO I,Reach-1,5
Up Type=0
Dn Type=3
Dn Slope=0.005
Boundary for River Rch & Prof#=TRIB 11_1_1 TO I,Reach-1,6
Up Type=0
Dn Type=3
Dn Slope=0.005
Boundary for River Rch & Prof#=TRIB 11_1_1 TO I,Reach-1,7
Up Type=0
Dn Type=3
Dn Slope=0.005

--- TRIB 11_1_1 TO IRISH CREEK.g01 (geometry) ---

Geom Title=Existing Conditions

River Reach=TRIB 11_1_1 TO I,Reach-1
Reach XY= 30
      2547675.00     13603425.00      2547642.94     13603424.85
      2547626.03     13603428.14      2547614.74     13603435.32
      2547597.71     13603451.15      2547585.53     13603465.03
      2547578.79     13603476.46      2547573.13     13603514.34
      2547568.59     13603527.27      2547538.88     13603561.76
      2547533.04     13603571.68      2547533.06     13603578.29
      2547536.46     13603584.90      2547563.83     13603615.22
      2547571.06     13603626.50      2547574.98     13603645.06
      2547575.64     13603690.08      2547573.73     13603714.52
      2547569.06     13603727.43      2547539.07     13603761.84
      2547533.28     13603771.78      2547533.35     13603778.41
      2547536.83     13603785.05      2547560.66     13603811.63
      2547567.21     13603824.90      2547560.94     13603838.16
      2547533.43     13603868.80      2547526.33     13603885.41
      2547524.55     13603909.76      2547525.00     13604025.00

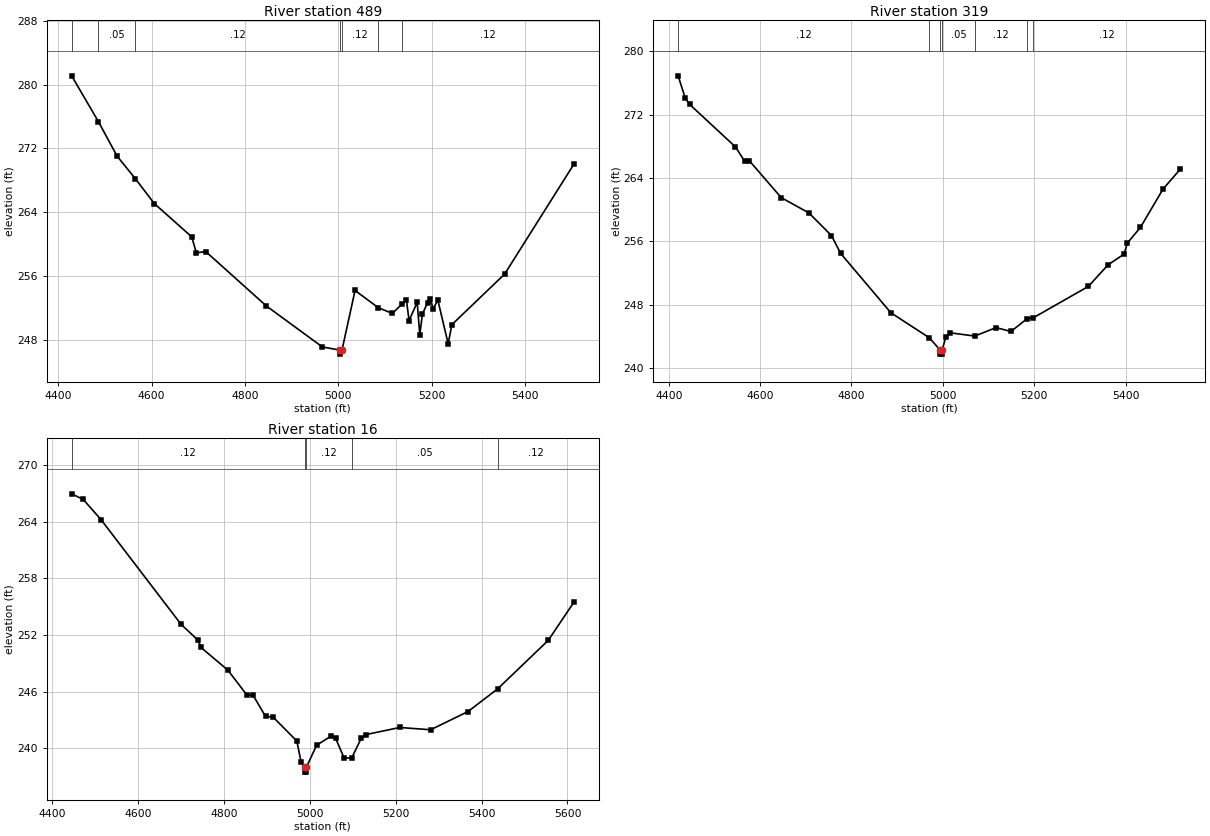
Type RM Length L Ch R = 1,489,170,170,170
BEGIN DESCRIPTION:
LGII4225
END DESCRIPTION:
XS GIS Cut Line= 3
      2546967.84     13603589.96      2547671.00     13603587.79
      2548009.52     13603431.55
#Sta/Elev= 30
  4428.9  281.09  4486.4  275.34  4526.1  271.05  4565.6  268.19  4606.1  265.09
  4686.1  260.93  4696.1  258.92  4716.1  259.09  4846.1  252.27  4966.1  247.14
  5004.1  246.74  5004.3  246.24  5008.1  246.74  5036.1  254.21  5085.6  252.07
  5116.1  251.33  5135.9  252.47  5146.3  252.97  5151.8  250.45  5169.3  252.72
  5174.8  248.66  5180.5  251.26  5191.5  252.69  5197.7  253.16  5203.2  251.92
  5213.6  252.99  5235.6  247.54  5243.6  249.93  5356.7  256.27  5504.9  270.02
#Mann=7,-1,0
  4428.9    0.12       0  4486.4    0.05       0  4565.6    0.12       0
  5004.1    0.05       0  5008.1    0.12       0  5085.6    0.05       0
  5135.9    0.12       0
Bank Sta=5004.1,5008.1
Exp/Cntr=0.3,0.1

Type RM Length L Ch R = 1,319,303,303,303
BEGIN DESCRIPTION:
LGII4224
END DESCRIPTION:
XS GIS Cut Line= 3
      2546979.49     13603719.66      2547687.34     13603745.64
      2547979.56     13603485.89
#Sta/Elev= 30
  4420.6  276.89  4436.1  274.10  4446.1  273.27  4546.2  267.91  4566.2  266.12
  4576.2  266.19  4646.3  261.51  4706.9  259.58  4756.3  256.72  4776.3  254.47
  4886.4  246.97  4970.1  243.83  4994.5  242.25  4994.7  241.75  4998.2  241.75
  4998.5  242.25  5006.5  243.87  5016.5  244.44  5070.0  244.03  5116.6  245.10
  5149.2  244.61  5184.4  246.22  5197.8  246.33  5318.9  250.31  5361.6  253.02
  5396.7  254.37  5404.2  255.79  5432.6  257.75  5482.0  262.58  5519.9  265.11
#Mann=7,-1,0
  4420.6    0.12       0  4970.1    0.05       0  4994.5    0.05       0
  4998.5    0.05       0  5070.0    0.12       0  5184.4    0.05       0
  5197.8    0.12       0
Bank Sta=4994.5,4998.5
Exp/Cntr=0.3,0.1

Type RM Length L Ch R = 1,16,0,0,0
BEGIN DESCRIPTION:
LGII4223
END DESCRIPTION:
XS GIS Cut Line= 4
      2547011.89     13603810.56      2547459.22     13604007.13
      2547659.74     13604014.07      2547927.64     13603615.73
#Sta/Elev= 30
  4445.6  266.96  4472.7  266.36  4513.9  264.23  4700.2  253.14  4740.5  251.42
  4745.9  250.71  4809.5  248.27  4853.1  245.67  4868.2  245.60  4897.0  243.38
  4914.9  243.29  4970.0  240.76  4980.0  238.50  4988.0  237.97  4988.3  237.47
  4991.8  237.47  4992.0  237.97  5016.1  240.33  5050.1  241.30  5060.1  241.06
  5080.1  238.96  5097.8  238.98  5120.1  241.08  5130.0  241.44  5209.5  242.20
  5281.5  241.96  5368.5  243.89  5437.4  246.29  5555.5  251.44  5614.9  255.47
#Mann=5,-1,0
  4445.6    0.12       0  4988.0    0.05       0  4992.0    0.12       0
  5097.8    0.05       0  5437.4    0.12       0
Bank Sta=4988,4992
Exp/Cntr=0.3,0.1

Chan Stop Cuts=-1