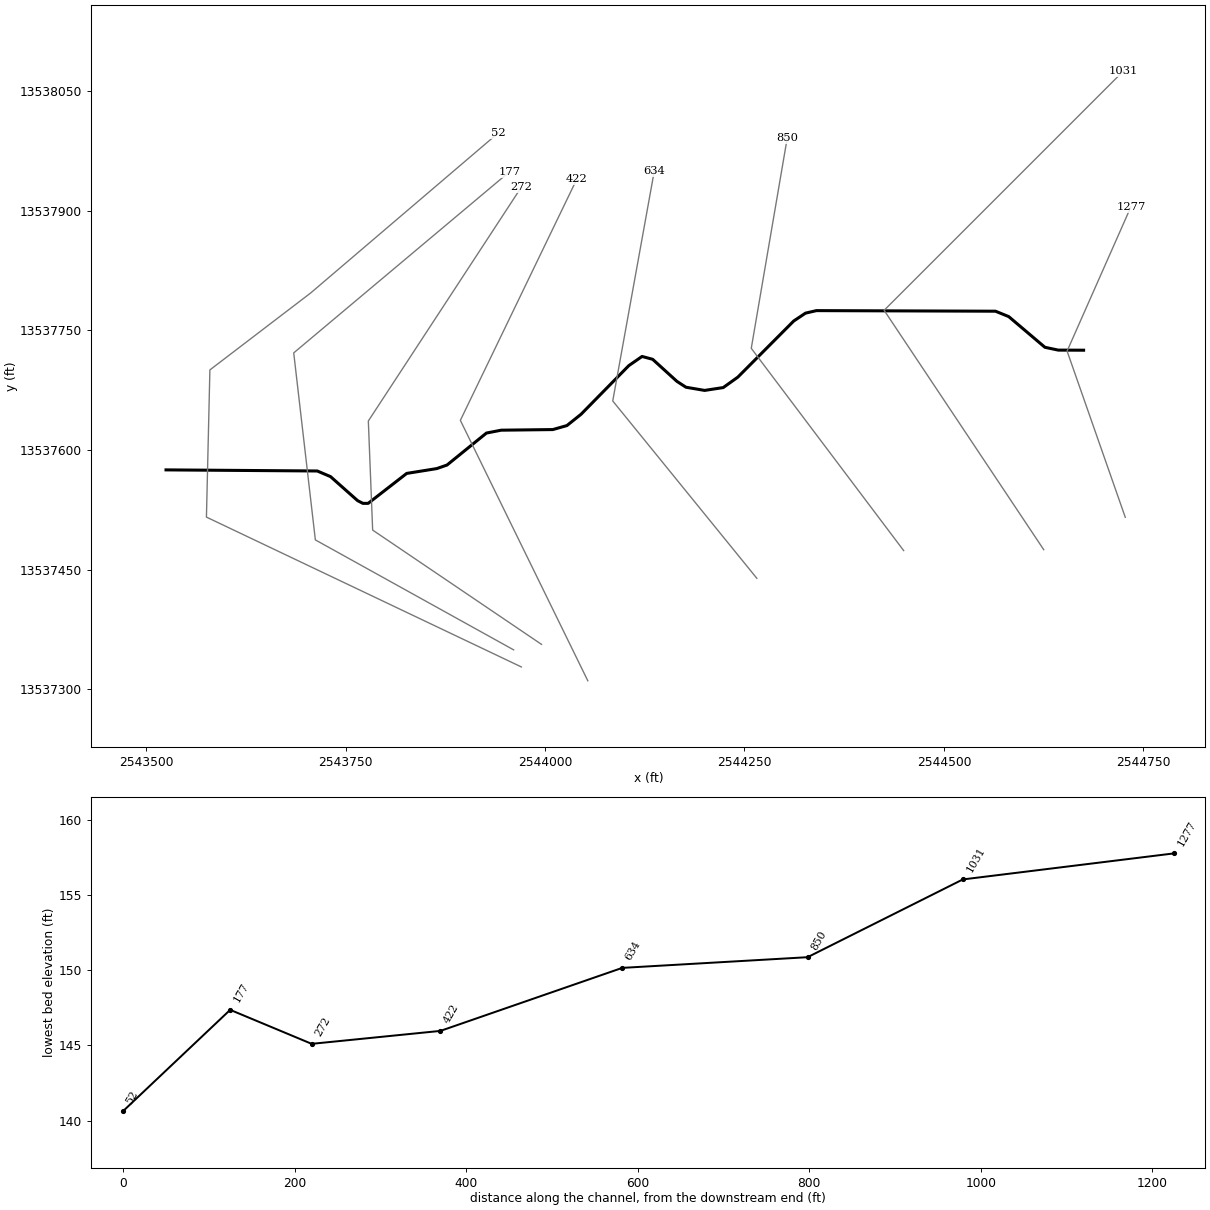
--- TRIB 11_2 TO GUADALUPE RIVER.prj (project) ---

Proj Title=TRIB 11_2 TO GUADALUPE RIVER Base Level Engineering
Current Plan=p01
Default Exp/Contr=0.3,0.1
English Units
Geom File=g01
Flow File=f01
Plan File=p01
Y Axis Title=Elevation
X Axis Title(PF)=Main Channel Distance
X Axis Title(XS)=Station
BEGIN DESCRIPTION:
TRIB 11_2 TO GUADALUPE RIVER
END DESCRIPTION:
DSS Export Rating Curves= 0
DSS Export Rating Curve Sorted= 0
DSS Export Volume Flow Curves= 0
DXF OffsetX= 0
DXF OffsetY= 0
DXF ScaleX= 1
DXF ScaleY= 10

--- TRIB 11_2 TO GUADALUPE RIVER.p01 (plan) ---

Plan Title=Multiple Run
Short Identifier=Multiple
Geom File=g01
Flow File=f01
Subcritical Flow
K Sum by GR= 0
Std Step Tol= 0.01
Critical Tol= 0.01
Num of Std Step Trials= 20
Max Error Tol= 0.3
Flow Tol Ratio= 0.001
Split Flow NTrial= 30
Split Flow Tol= 0.02
Split Flow Ratio= 0.02
Log Output Level= 0
Friction Slope Method= 1
Unsteady Friction Slope Method= 2
Unsteady Bridges Friction Slope Method= 1
Parabolic Critical Depth
Global Vel Dist=  1 , 1 , 1
Global Log Level= 0
CheckData=True
Encroach Param= -1, 0, 0, 0
BEGIN DESCRIPTION:
Multiple Run
END DESCRIPTION:

--- TRIB 11_2 TO GUADALUPE RIVER.f01 (steady flow) ---

Flow Title=Multiple
Number of Profiles=7
Profile Names=10-year,25-year,50-year,1pct_min,100-year,1pct_plu,500-year
River Rch & RM= TRIB 11_2 TO GUA,Reach-1,1277
     305     469     611     387     773    1542    1219
Boundary for River Rch & Prof#=TRIB 11_2 TO GUA,Reach-1,1
Up Type=0
Dn Type=3
Dn Slope=0.005
Boundary for River Rch & Prof#=TRIB 11_2 TO GUA,Reach-1,2
Up Type=0
Dn Type=3
Dn Slope=0.005
Boundary for River Rch & Prof#=TRIB 11_2 TO GUA,Reach-1,3
Up Type=0
Dn Type=3
Dn Slope=0.005
Boundary for River Rch & Prof#=TRIB 11_2 TO GUA,Reach-1,4
Up Type=0
Dn Type=3
Dn Slope=0.005
Boundary for River Rch & Prof#=TRIB 11_2 TO GUA,Reach-1,5
Up Type=0
Dn Type=3
Dn Slope=0.005
Boundary for River Rch & Prof#=TRIB 11_2 TO GUA,Reach-1,6
Up Type=0
Dn Type=3
Dn Slope=0.005
Boundary for River Rch & Prof#=TRIB 11_2 TO GUA,Reach-1,7
Up Type=0
Dn Type=3
Dn Slope=0.005

--- TRIB 11_2 TO GUADALUPE RIVER.g01 (geometry) ---

Geom Title=Existing Conditions
Program Version=4.10

River Reach=TRIB 11_2 TO GUA,Reach-1
Reach XY= 30
        2544675.       13537725.       2544643.2     13537725.12
      2544626.51     13537728.65      2544581.16     13537767.11
      2544564.54     13537773.88      2544340.16     13537774.61
      2544326.47     13537771.45      2544311.69      13537761.6
      2544241.66     13537691.26      2544223.35     13537678.17
        2544200.      13537674.6      2544176.65     13537678.59
      2544165.32     13537685.93      2544134.87     13537713.61
       2544121.6     13537717.16      2544104.99     13537705.66
      2544045.15     13537644.71      2544027.43     13537630.55
      2544009.78     13537625.53       2543945.1     13537624.76
      2543926.59     13537621.17      2543877.17     13537581.09
      2543864.29     13537576.62      2543826.64     13537570.58
      2543778.32     13537533.04      2543771.71     13537533.06
       2543765.1     13537536.46      2543731.19     13537566.55
      2543714.57     13537573.62        2543525.       13537575.

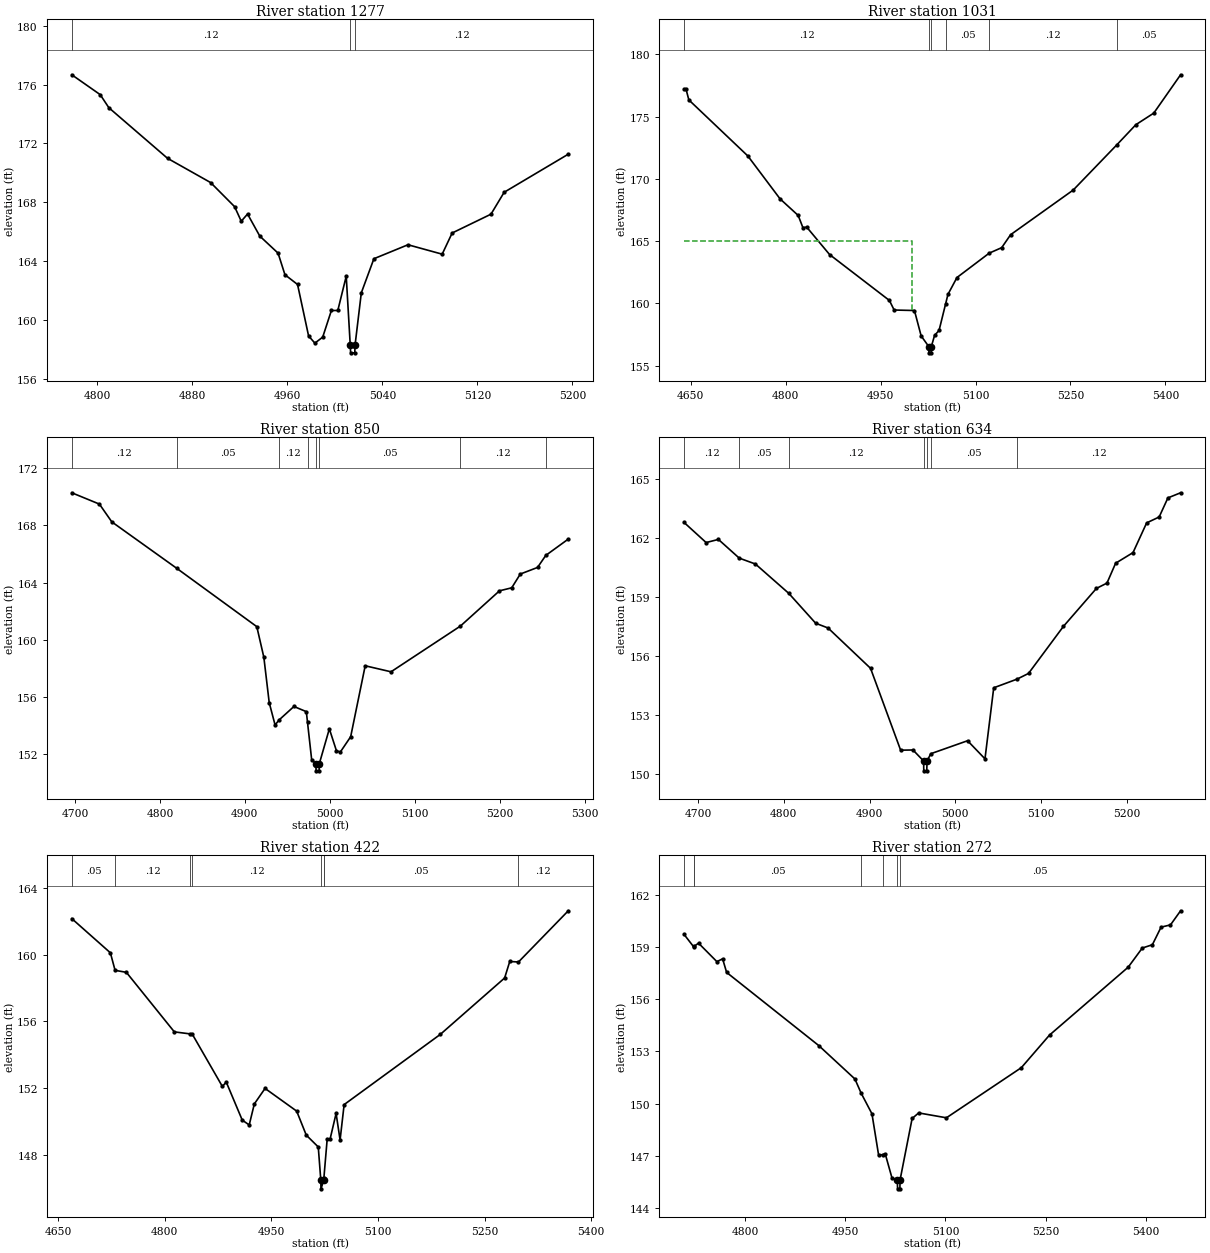
Type RM Length L Ch R = 1 ,1277    ,246,246,246
BEGIN DESCRIPTION:
Mapping XS c600070f
END DESCRIPTION:
XS GIS Cut Line= 3
      2544727.22     13537515.58      2544654.31     13537723.89
      2544734.16     13537904.42
#Sta/Elev= 30
  4778.5  176.67  4802.4  175.32  4809.7  174.43  4859.1  170.99  4895.4  169.34
  4915.6   167.7  4921.2  166.71  4926.5   167.2  4936.8   165.7  4952.2  164.54
    4958  163.07  4968.6  162.41  4977.9  158.91  4983.2  158.42  4989.8  158.83
  4997.1  160.64  5002.5  160.64  5009.6  162.97    5013  158.26  5013.3  157.76
  5016.8  157.76    5017  158.26  5022.3  161.84  5032.9  164.16  5061.6  165.11
  5090.4  164.47  5098.8  165.91  5131.5  167.19  5142.6  168.68  5196.6  171.27
#Mann= 3 ,-1 , 0
  4778.5     .12       0    5013     .05       0    5017     .12       0
Bank Sta=5013,5017
XS Rating Curve= 0 ,0
Exp/Cntr=0.3,0.1

Type RM Length L Ch R = 1 ,1031    ,181,181,181
BEGIN DESCRIPTION:
TRIB 11_2 TO GUADALUPE RIVER 2.0
END DESCRIPTION:
XS GIS Cut Line= 3
        2544625.       13537475.        2544425.       13537775.
      2544724.99     13538074.99
#Sta/Elev= 30
  4639.3  177.22  4642.3  177.22  4646.8  176.35    4740  171.85    4791   168.4
  4819.6  167.07  4827.1  166.09  4833.1  166.13  4869.2  163.93  4963.8  160.24
  4971.3  159.47  5003.4  159.43    5014  157.39  5026.1  156.53  5026.4  156.03
  5029.9  156.03  5030.1  156.53  5035.2  157.43  5042.3  157.83  5052.6  159.95
  5056.4  160.73  5070.6  162.08  5121.6  164.04  5141.3  164.48  5155.4  165.52
  5254.4  169.11  5323.1  172.73  5353.4  174.36  5381.7  175.29  5424.1  178.37
#Mann= 6 ,-1 , 0
  4639.3     .12       0  5026.1     .05       0  5030.1     .12       0
  5052.6     .05       0  5121.6     .12       0  5323.1     .05       0
#XS Ineff= 2 , 0
       0    4999     165               0
Permanent Ineff=
       F       F
Bank Sta=5026.1,5030.1
XS Rating Curve= 0 ,0
Exp/Cntr=0.3,0.1

Type RM Length L Ch R = 1 ,850     ,216,216,216
BEGIN DESCRIPTION:
Mapping XS fc4d9c29
END DESCRIPTION:
XS GIS Cut Line= 3
      2544449.46     13537473.88      2544258.48     13537727.36
      2544303.52     13537990.66
#Sta/Elev= 30
  4696.3  170.26  4728.8  169.47  4743.4  168.23  4819.6     165  4914.1  160.92
  4922.4  158.78  4928.7  155.62  4935.6  154.06  4940.5  154.42  4957.8  155.35
  4972.4  154.99  4973.8  154.24  4978.7  151.63  4983.7  151.36  4983.9  150.86
  4987.4  150.86  4987.7  151.36  4999.5  153.79  5007.8  152.27  5012.4  152.17
  5024.6  153.24  5041.7  158.19  5072.1  157.77  5153.8  160.96  5199.8  163.42
  5214.2  163.63  5224.3  164.59  5244.6  165.05  5254.3  165.89  5280.8  167.03
#Mann= 8 ,-1 , 0
  4696.3     .12       0  4819.6     .05       0  4940.5     .12       0
  4973.8     .05       0  4983.7     .05       0  4987.7     .05       0
  5153.8     .12       0  5254.3     .05       0
Bank Sta=4983.7,4987.7
XS Rating Curve= 0 ,0
Exp/Cntr=0.3,0.1

Type RM Length L Ch R = 1 ,634     ,212,212,212
BEGIN DESCRIPTION:
Mapping XS fb9322b1
END DESCRIPTION:
XS GIS Cut Line= 3
      2544265.44     13537439.15      2544084.87     13537661.39
      2544136.95     13537949.57
#Sta/Elev= 30
  4683.7  162.77  4709.4  161.75  4723.7  161.91    4748  160.96  4766.9  160.66
  4805.8  159.17  4837.2  157.65  4851.6  157.41  4901.2  155.36  4936.3   151.2
  4950.7  151.21  4963.1  150.65  4963.3  150.15  4966.8  150.15  4967.1  150.65
  4971.5  151.02  5014.4  151.68  5034.7  150.76  5044.9  154.37  5072.1  154.81
  5085.5   155.1  5126.2  157.49  5164.7  159.42    5177  159.69  5187.1   160.7
  5207.4  161.24  5223.3  162.75  5237.9  163.05  5248.1  164.02  5262.9  164.28
#Mann= 7 ,-1 , 0
  4683.7     .12       0    4748     .05       0  4805.8     .12       0
  4963.1     .05       0  4967.1     .12       0  4971.5     .05       0
  5072.1     .12       0
Bank Sta=4963.1,4967.1
XS Rating Curve= 0 ,0
Exp/Cntr=0.3,0.1

Type RM Length L Ch R = 1 ,422     ,150,150,150
BEGIN DESCRIPTION:
Mapping XS 0234c8af
END DESCRIPTION:
XS GIS Cut Line= 3
      2544053.61     13537310.71      2543893.89     13537637.08
      2544039.73     13537939.17
#Sta/Elev= 30
  4669.1  162.16  4723.4  160.11    4730  159.06  4745.9  158.94  4813.4  155.37
  4835.5  155.25  4838.7  155.23    4881   152.1  4886.5  152.36    4909  150.08
  4918.8  149.79    4926  151.05  4941.1  151.98  4985.6  150.62  4999.1  149.18
    5016  148.47  5019.6  146.46  5019.8  145.96  5023.6  146.46  5023.9  146.61
  5028.5  148.92  5032.5  148.92  5041.1  150.48  5046.7  148.89  5052.4  151.01
  5187.8  155.22  5278.3   158.6  5285.5  159.59  5297.8  159.56  5367.9  162.63
#Mann= 8 ,-1 , 0
  4669.1     .05       0    4730     .12       0  4835.5     .05       0
  4838.7     .12       0  5019.6     .05       0  5023.6     .12       0
  5023.9     .05       0  5297.8     .12       0
Bank Sta=5019.6,5023.6
XS Rating Curve= 0 ,0
Exp/Cntr=0.3,0.1

Type RM Length L Ch R = 1 ,272     ,95,95,95
BEGIN DESCRIPTION:
Mapping XS 05bb2f3b
END DESCRIPTION:
XS GIS Cut Line= 4
      2543995.59     13537356.31      2543783.97     13537499.56
      2543778.55     13537636.28      2543970.38     13537929.42
#Sta/Elev= 30
    4709  159.71  4723.1  159.01    4724  159.03  4730.6  159.21    4758  158.15
  4766.6  158.31  4772.6  157.53  4910.4  153.33  4964.5  151.41  4973.9  150.59
    4990  149.41    5000  147.03  5006.5  147.07    5010  147.09    5020  145.72
    5028   145.6  5028.3   145.1  5031.8   145.1    5032   145.6  5050.1  149.14
  5059.9  149.46  5101.4  149.18  5213.5  152.06  5255.6  153.93  5373.3  157.83
  5394.4  158.93  5409.5  159.12  5422.5  160.13  5436.6  160.26  5451.7  161.07
#Mann= 7 ,-1 , 0
    4709     .05       0  4723.1     .12       0    4724     .05       0
  4973.9     .12       0  5006.5     .05       0    5028     .05       0
    5032     .05       0
Bank Sta=5028,5032
XS Rating Curve= 0 ,0
Exp/Cntr=0.3,0.1

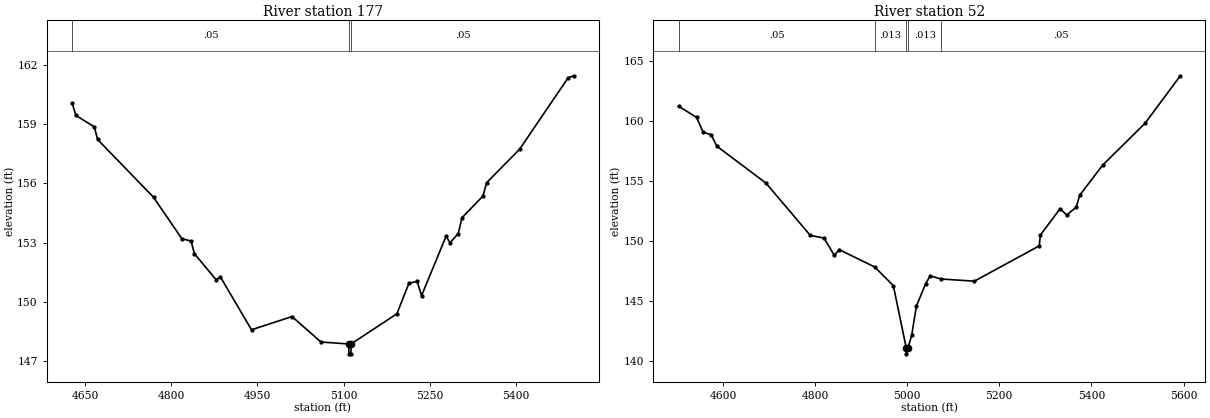
Type RM Length L Ch R = 1 ,177     ,125,125,125
BEGIN DESCRIPTION:
Mapping XS 2dc96fb7
END DESCRIPTION:
XS GIS Cut Line= 4
      2543960.66     13537349.44      2543712.16     13537487.25
      2543685.04     13537721.63      2543955.19     13537948.38
#Sta/Elev= 30
  4627.5  160.08  4634.2  159.45  4666.2  158.87  4671.9  158.23  4769.2   155.3
  4818.4   153.2  4834.5  153.08  4840.2  152.44    4878  151.12  4885.5  151.26
  4939.6  148.58  5010.1  149.25  5060.4  147.96  5108.7  147.86    5109  147.36
  5112.5  147.36  5112.7  147.86  5192.5  149.39  5213.3  150.93  5227.6  151.04
  5235.4  150.31  5278.1  153.33  5284.8  152.99  5299.2  153.46  5305.7  154.26
  5342.1  155.36  5348.6  156.04  5405.8  157.73  5490.4  161.36  5500.3  161.46
#Mann= 3 ,-1 , 0
  4627.5     .05       0  5108.7     .05       0  5112.7     .05       0
Bank Sta=5108.7,5112.7
XS Rating Curve= 0 ,0
Exp/Cntr=0.3,0.1

Type RM Length L Ch R = 1 ,52      ,0,0,0
BEGIN DESCRIPTION:
Mapping XS 97b0214a
END DESCRIPTION:
XS GIS Cut Line= 5
      2543970.32     13537328.04      2543575.64     13537515.83
      2543579.98      13537700.3      2543706.39     13537796.81
      2543941.23     13537997.11
#Sta/Elev= 30
  4503.7  161.24  4542.8  160.31  4557.1  159.07  4574.3  158.87  4587.1   157.9
  4693.4  154.84  4789.8  150.48  4819.7  150.26  4841.8  148.82  4852.4   149.3
  4929.6  147.85    4970   146.3    4998  141.12  4998.2  140.62    5002  141.12
    5010   142.2    5020  144.59    5040  146.45    5050  147.11  5073.6  146.85
  5145.9  146.67  5286.7  149.61  5289.2  150.51    5332   152.7  5346.3  152.18
  5367.1  152.83  5374.5  153.82  5424.2  156.32  5516.5  159.82    5593  163.77
#Mann= 5 ,-1 , 0
  4503.7     .05       0  4929.6    .013       0    4998     .03       0
    5002    .013       0  5073.6     .05       0
Bank Sta=4998,5002
XS Rating Curve= 0 ,0
Exp/Cntr=0.3,0.1

Chan Stop Cuts=-1
Use User Specified Reach Order=0
Composite Channel Slope=5