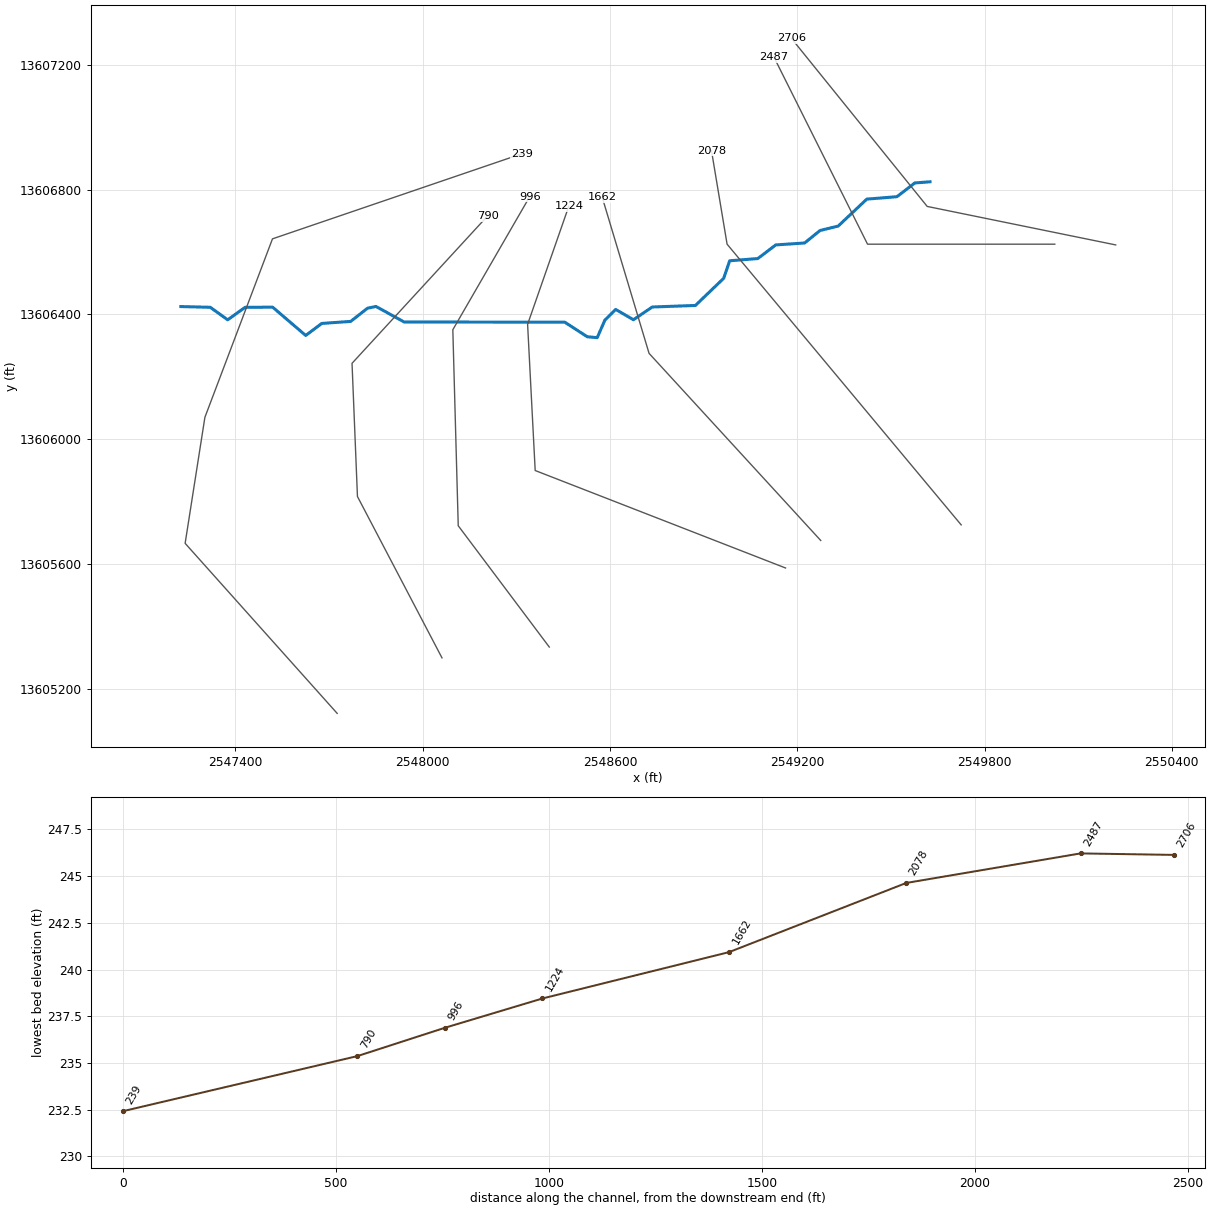
--- TRIB 11_2 TO IRISH CREEK.prj (project) ---

Proj Title=TRIB 11_2 TO IRISH CREEK Base Level Engineering
Current Plan=p01
Default Exp/Contr=0.3,0.1
English Units
Geom File=g01
Flow File=f01
Plan File=p01
Y Axis Title=Elevation
X Axis Title(PF)=Main Channel Distance
X Axis Title(XS)=Station
BEGIN DESCRIPTION:
TRIB 11_2 TO IRISH CREEK
END DESCRIPTION:
DSS Export Rating Curves= 0
DSS Export Rating Curve Sorted= 0
DSS Export Volume Flow Curves= 0
DXF OffsetX= 0
DXF OffsetY= 0
DXF ScaleX= 1
DXF ScaleY= 10

--- TRIB 11_2 TO IRISH CREEK.p01 (plan) ---

Plan Title=Multiple Run
Short Identifier=Multiple
Geom File=g01
Flow File=f01
Subcritical Flow
K Sum by GR= 0
Std Step Tol= 0.01
Critical Tol= 0.01
Num of Std Step Trials= 20
Max Error Tol= 0.3
Flow Tol Ratio= 0.001
Split Flow NTrial= 30
Split Flow Tol= 0.02
Split Flow Ratio= 0.02
Log Output Level= 0
Friction Slope Method= 1
Unsteady Friction Slope Method= 2
Unsteady Bridges Friction Slope Method= 1
Parabolic Critical Depth
Global Vel Dist=  1 , 1 , 1
Global Log Level= 0
CheckData=True
Encroach Param= -1, 0, 0, 0
BEGIN DESCRIPTION:
Multiple Run
END DESCRIPTION:

--- TRIB 11_2 TO IRISH CREEK.f01 (steady flow) ---

Flow Title=Multiple
Number of Profiles=7
Profile Names=10-year,25-year,50-year,1pct_min,100-year,1pct_plu,500-year
River Rch & RM= TRIB 11_2 TO IRI,Reach-1,2706
     392     608     796     507    1011    2018    1609
Boundary for River Rch & Prof#=TRIB 11_2 TO IRI,Reach-1,1
Up Type=0
Dn Type=3
Dn Slope=0.005
Boundary for River Rch & Prof#=TRIB 11_2 TO IRI,Reach-1,2
Up Type=0
Dn Type=3
Dn Slope=0.005
Boundary for River Rch & Prof#=TRIB 11_2 TO IRI,Reach-1,3
Up Type=0
Dn Type=3
Dn Slope=0.005
Boundary for River Rch & Prof#=TRIB 11_2 TO IRI,Reach-1,4
Up Type=0
Dn Type=3
Dn Slope=0.005
Boundary for River Rch & Prof#=TRIB 11_2 TO IRI,Reach-1,5
Up Type=0
Dn Type=3
Dn Slope=0.005
Boundary for River Rch & Prof#=TRIB 11_2 TO IRI,Reach-1,6
Up Type=0
Dn Type=3
Dn Slope=0.005
Boundary for River Rch & Prof#=TRIB 11_2 TO IRI,Reach-1,7
Up Type=0
Dn Type=3
Dn Slope=0.005

--- TRIB 11_2 TO IRISH CREEK.g01 (geometry) ---

Geom Title=Existing Conditions

River Reach=TRIB 11_2 TO IRI,Reach-1
Reach XY= 30
      2549625.00     13606825.00      2549576.51     13606821.36
      2549519.08     13606777.23      2549422.58     13606769.47
      2549331.05     13606683.16      2549272.83     13606668.86
      2549223.42     13606628.83      2549130.97     13606622.65
      2549073.33     13606578.89      2548983.34     13606571.84
      2548964.11     13606515.60      2548873.54     13606428.54
      2548735.44     13606423.61      2548674.89     13606382.81
      2548618.07     13606415.77      2548583.28     13606381.27
      2548558.99     13606325.26      2548527.11     13606328.20
      2548454.99     13606374.91      2547940.21     13606375.54
      2547850.00     13606425.40      2547822.82     13606419.63
      2547769.03     13606377.38      2547676.50     13606370.90
      2547624.90     13606332.33      2547519.11     13606423.01
      2547430.90     13606422.64      2547374.99     13606382.52
      2547319.23     13606422.66      2547225.00     13606425.00

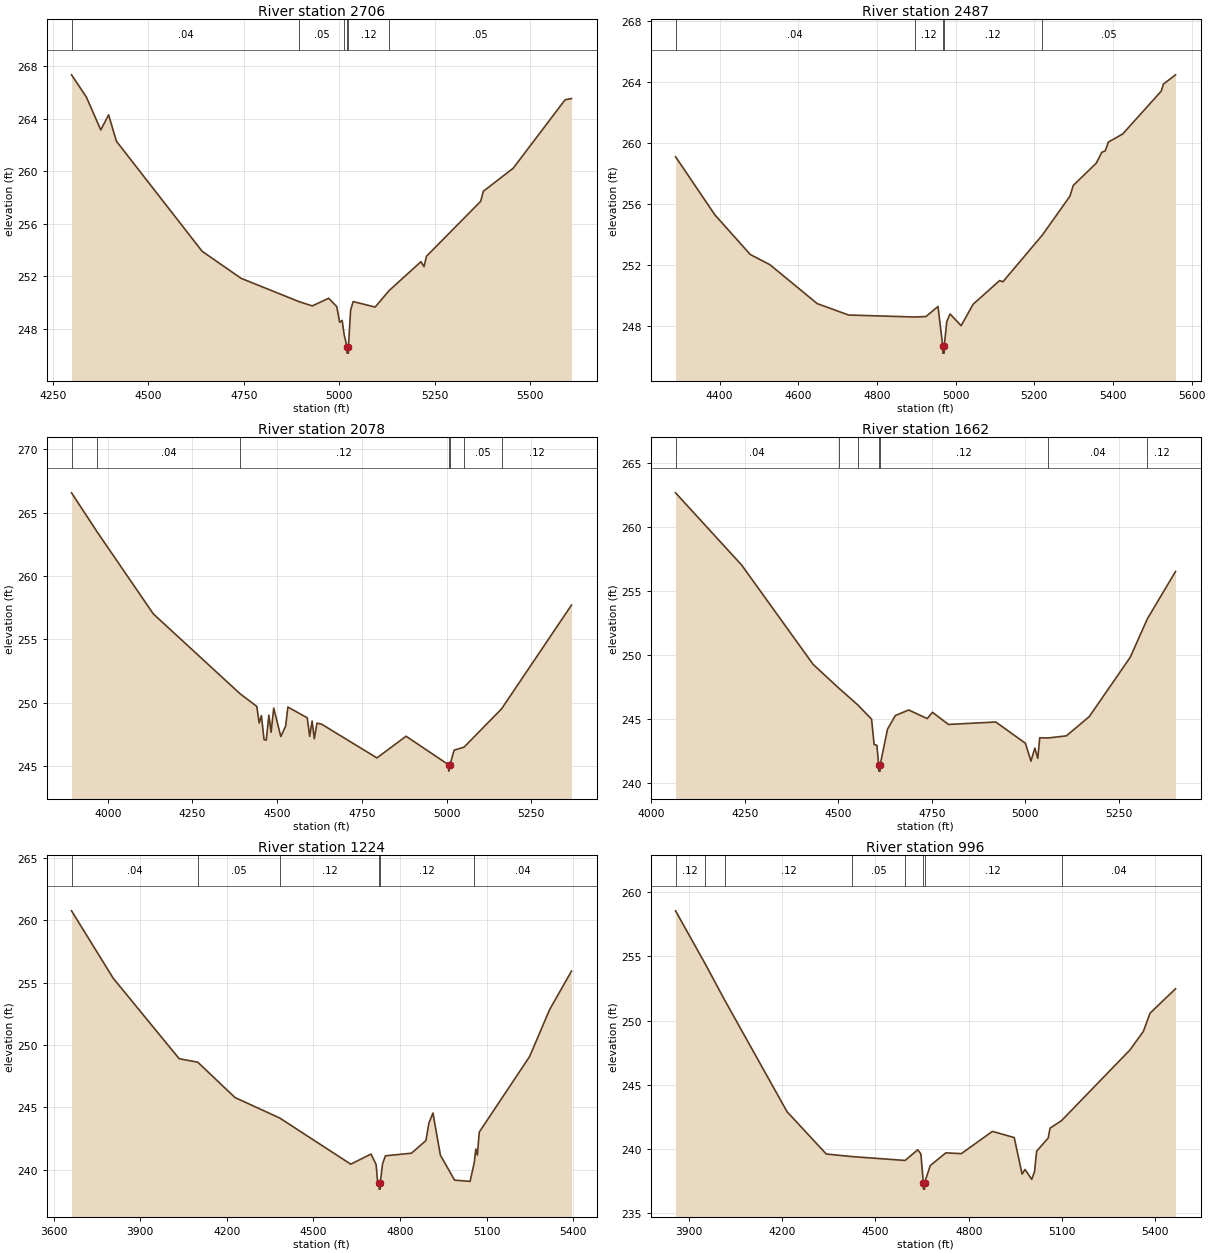
Type RM Length L Ch R = 1,2706,219,219,219
BEGIN DESCRIPTION:
TRIB 11_2 TO IRISH CREEK 8.0
END DESCRIPTION:
XS GIS Cut Line= 3
      2550220.09     13606622.64      2549616.16     13606746.03
      2549181.06     13607285.02
#Sta/Elev= 30
  4299.0  267.34  4337.8  265.65  4375.6  263.14  4396.1  264.29  4416.5  262.28
  4641.0  253.89  4743.1  251.83  4895.1  250.05  4929.3  249.73  4972.4  250.31
  4993.3  249.68  5001.2  248.48  5007.6  248.62  5012.7  247.56  5020.0  246.63
  5020.3  246.13  5023.8  246.13  5024.0  246.63  5029.8  249.42  5036.4  250.06
  5094.0  249.64  5130.3  250.89  5213.9  253.10  5221.9  252.72  5228.3  253.51
  5370.3  257.70  5377.1  258.46  5455.4  260.22  5591.3  265.44  5608.1  265.53
#Mann=6,-1,0
  4299.0    0.04       0  4895.1    0.05       0  5012.7    0.12       0
  5020.0    0.05       0  5024.0    0.12       0  5130.3    0.05       0
Bank Sta=5020,5024
Exp/Cntr=0.3,0.1

Type RM Length L Ch R = 1,2487,409,409,409
BEGIN DESCRIPTION:
TRIB 11_2 TO IRISH CREEK 7.0
END DESCRIPTION:
XS GIS Cut Line= 3
      2550024.97     13606625.00      2549425.00     13606625.00
      2549125.00     13607225.01
#Sta/Elev= 30
  4288.2  259.10  4388.2  255.28  4478.2  252.68  4528.2  252.01  4648.2  249.46
  4728.2  248.71  4896.2  248.58  4924.5  248.61  4955.3  249.27  4967.2  246.71
  4967.5  246.21  4971.0  246.21  4971.2  246.71  4977.6  248.28  4986.0  248.78
  5014.0  248.01  5044.7  249.42  5111.8  250.97  5120.2  250.89  5220.6  253.96
  5290.7  256.51  5299.0  257.21  5357.7  258.68  5371.7  259.39  5380.1  259.47
  5388.5  260.06  5424.8  260.59  5522.7  263.40  5528.2  263.86  5559.0  264.47
#Mann=5,-1,0
  4288.2    0.04       0  4896.2    0.12       0  4967.2    0.05       0
  4971.2    0.12       0  5220.6    0.05       0
Bank Sta=4967.2,4971.2
Exp/Cntr=0.3,0.1

Type RM Length L Ch R = 1,2078,416,416,416
BEGIN DESCRIPTION:
TRIB 11_2 TO IRISH CREEK 6.0
END DESCRIPTION:
XS GIS Cut Line= 3
      2549725.00     13605724.99      2548975.00     13606625.00
      2548925.00     13606925.02
#Sta/Elev= 30
  3893.2  266.55  3969.4  263.45  4134.7  257.01  4390.9  250.72  4439.9  249.73
  4447.1  248.42  4453.6  249.01  4461.4  247.12  4467.9  247.07  4475.7  249.04
  4482.2  247.69  4490.0  249.60  4510.9  247.35  4525.2  248.18  4531.7  249.68
  4589.0  248.83  4596.1  247.37  4603.3  248.58  4609.8  247.18  4617.6  248.41
  4631.9  248.32  4794.6  245.67  4880.6  247.38  5006.1  245.13  5006.4  244.63
  5010.1  245.13  5022.4  246.28  5051.8  246.52  5162.6  249.54  5368.9  257.71
#Mann=7,-1,0
  3893.2    0.05       0  3969.4    0.04       0  4390.9    0.12       0
  5006.1    0.05       0  5010.1    0.12       0  5051.8    0.05       0
  5162.6    0.12       0
Bank Sta=5006.1,5010.1
Exp/Cntr=0.3,0.1

Type RM Length L Ch R = 1,1662,438,438,438
BEGIN DESCRIPTION:
TRIB 11_2 TO IRISH CREEK 5.0
END DESCRIPTION:
XS GIS Cut Line= 3
      2549275.02     13605674.98      2548725.00     13606275.00
      2548575.00     13606775.02
#Sta/Elev= 30
  4065.1  262.69  4241.8  257.04  4432.9  249.27  4501.7  247.41  4551.6  246.12
  4588.9  244.99  4595.7  243.01  4603.1  242.95  4607.9  241.43  4608.2  240.93
  4611.7  240.93  4611.9  241.43  4631.5  244.21  4652.5  245.28  4688.2  245.71
  4737.6  245.04  4751.7  245.53  4794.3  244.58  4920.8  244.77  5000.0  243.11
  5014.8  241.71  5025.2  242.73  5033.1  241.93  5038.3  243.54  5060.2  243.52
  5109.6  243.69  5170.5  245.19  5280.1  249.83  5325.9  252.84  5401.1  256.54
#Mann=7,-1,0
  4065.1    0.04       0  4501.7    0.05       0  4551.6    0.12       0
  4607.9    0.05       0  4611.9    0.12       0  5060.2    0.04       0
  5325.9    0.12       0
Bank Sta=4607.9,4611.9
Exp/Cntr=0.3,0.1

Type RM Length L Ch R = 1,1224,228,228,228
BEGIN DESCRIPTION:
Mapping XS 16c619d6
END DESCRIPTION:
XS GIS Cut Line= 4
      2549162.28     13605586.79      2548360.18     13605899.29
      2548335.88     13606368.04      2548467.81     13606746.50
#Sta/Elev= 30
  3662.4  260.75  3806.7  255.35  4035.1  248.90  4099.5  248.62  4228.3  245.79
  4383.1  244.15  4629.1  240.45  4699.2  241.26  4717.0  240.42  4722.0  239.08
  4727.2  238.95  4727.5  238.45  4731.0  238.45  4731.2  238.95  4739.2  240.48
  4749.2  241.12  4839.4  241.33  4889.4  242.34  4899.4  243.72  4913.7  244.55
  4939.5  241.17  4988.6  239.17  5042.3  239.07  5056.8  240.59  5062.1  241.66
  5067.4  241.18  5074.1  243.02  5248.5  249.08  5317.7  252.84  5393.4  255.92
#Mann=6,-1,0
  3662.4    0.04       0  4099.5    0.05       0  4383.1    0.12       0
  4727.2    0.05       0  4731.2    0.12       0  5056.8    0.04       0
Bank Sta=4727.2,4731.2
Exp/Cntr=0.3,0.1

Type RM Length L Ch R = 1,996,206,206,206
BEGIN DESCRIPTION:
Mapping XS 4cc72bcb
END DESCRIPTION:
XS GIS Cut Line= 4
      2548405.34     13605333.30      2548113.65     13605722.21
      2548096.29     13606350.68      2548342.83     13606777.78
#Sta/Elev= 30
  3857.1  258.53  3952.4  254.41  4015.3  251.58  4215.7  242.91  4341.9  239.62
  4424.7  239.42  4595.3  239.12  4636.1  239.95  4646.1  239.63  4654.1  237.39
  4654.4  236.89  4657.9  236.89  4658.1  237.39  4676.2  238.72  4726.2  239.71
  4776.2  239.65  4876.2  241.38  4946.3  240.90  4971.6  238.06  4981.0  238.42
  5002.6  237.65  5011.6  238.24  5018.4  239.84  5055.7  240.87  5061.5  241.63
  5098.6  242.22  5318.5  247.71  5361.6  249.15  5383.1  250.57  5465.1  252.47
#Mann=8,-1,0
  3857.1    0.12       0  3952.4    0.04       0  4015.3    0.12       0
  4424.7    0.05       0  4595.3    0.12       0  4654.1    0.05       0
  4658.1    0.12       0  5098.6    0.04       0
Bank Sta=4654.1,4658.1
Exp/Cntr=0.3,0.1

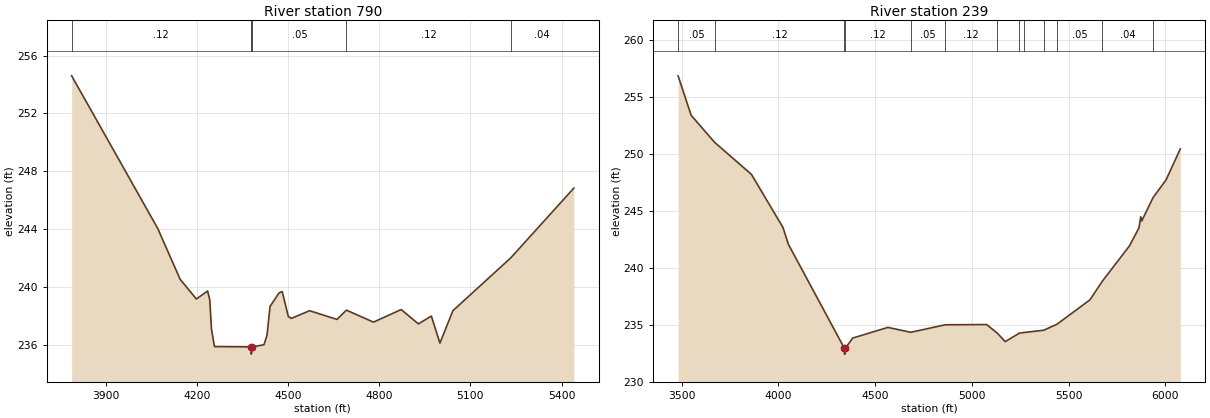
Type RM Length L Ch R = 1,790,551,551,551
BEGIN DESCRIPTION:
Mapping XS c41905ef
END DESCRIPTION:
XS GIS Cut Line= 4
      2548061.56     13605298.62      2547790.74     13605815.96
      2547773.38     13606243.04      2548207.44     13606715.30
#Sta/Elev= 30
  3787.6  254.60  4071.3  244.04  4144.7  240.54  4198.1  239.18  4235.0  239.73
  4242.2  239.12  4247.8  237.10  4257.6  235.89  4377.2  235.87  4378.6  235.87
  4378.8  235.37  4382.6  235.87  4420.6  236.02  4430.6  236.68  4440.6  238.67
  4470.7  239.61  4480.7  239.69  4500.7  237.97  4510.7  237.84  4570.7  238.37
  4660.8  237.77  4692.1  238.41  4780.9  237.58  4872.1  238.45  4928.8  237.46
  4971.4  238.00  4999.7  236.13  5042.3  238.37  5232.8  242.02  5440.4  246.84
#Mann=6,-1,0
  3787.6    0.12       0  4377.2    0.05       0  4378.6    0.05       0
  4382.6    0.05       0  4692.1    0.12       0  5232.8    0.04       0
Bank Sta=4378.6,4382.6
Exp/Cntr=0.3,0.1

Type RM Length L Ch R = 1,239,0,0,0
BEGIN DESCRIPTION:
TRIB 11_2 TO IRISH CREEK 4.0
END DESCRIPTION:
XS GIS Cut Line= 5
      2547725.75     13605120.62      2547238.65     13605665.82
      2547301.98     13606069.93      2547518.49     13606642.12
      2548317.28     13606914.87
#Sta/Elev= 30
  3481.5  256.89  3548.9  253.42  3670.9  251.03  3860.8  248.22  4023.8  243.55
  4051.4  242.08  4341.4  232.92  4341.6  232.42  4345.1  232.42  4345.4  232.92
  4383.8  233.83  4566.0  234.77  4683.9  234.34  4862.6  235.00  5076.1  235.02
  5130.7  234.28  5172.4  233.52  5245.2  234.26  5268.6  234.32  5371.5  234.52
  5439.2  235.04  5610.1  237.19  5674.8  238.84  5815.5  241.96  5863.8  243.52
  5872.9  244.50  5878.2  244.13  5936.2  246.17  6003.5  247.73  6077.5  250.46
#Mann=13,-1,0
  3481.5    0.05       0  3670.9    0.12       0  4341.4    0.05       0
  4345.4    0.12       0  4683.9    0.05       0  4862.6    0.12       0
  5130.7    0.05       0  5245.2    0.12       0  5268.6    0.05       0
  5371.5    0.12       0  5439.2    0.05       0  5674.8    0.04       0
  5936.2    0.05       0
Bank Sta=4341.4,4345.4
Exp/Cntr=0.3,0.1

Chan Stop Cuts=-1