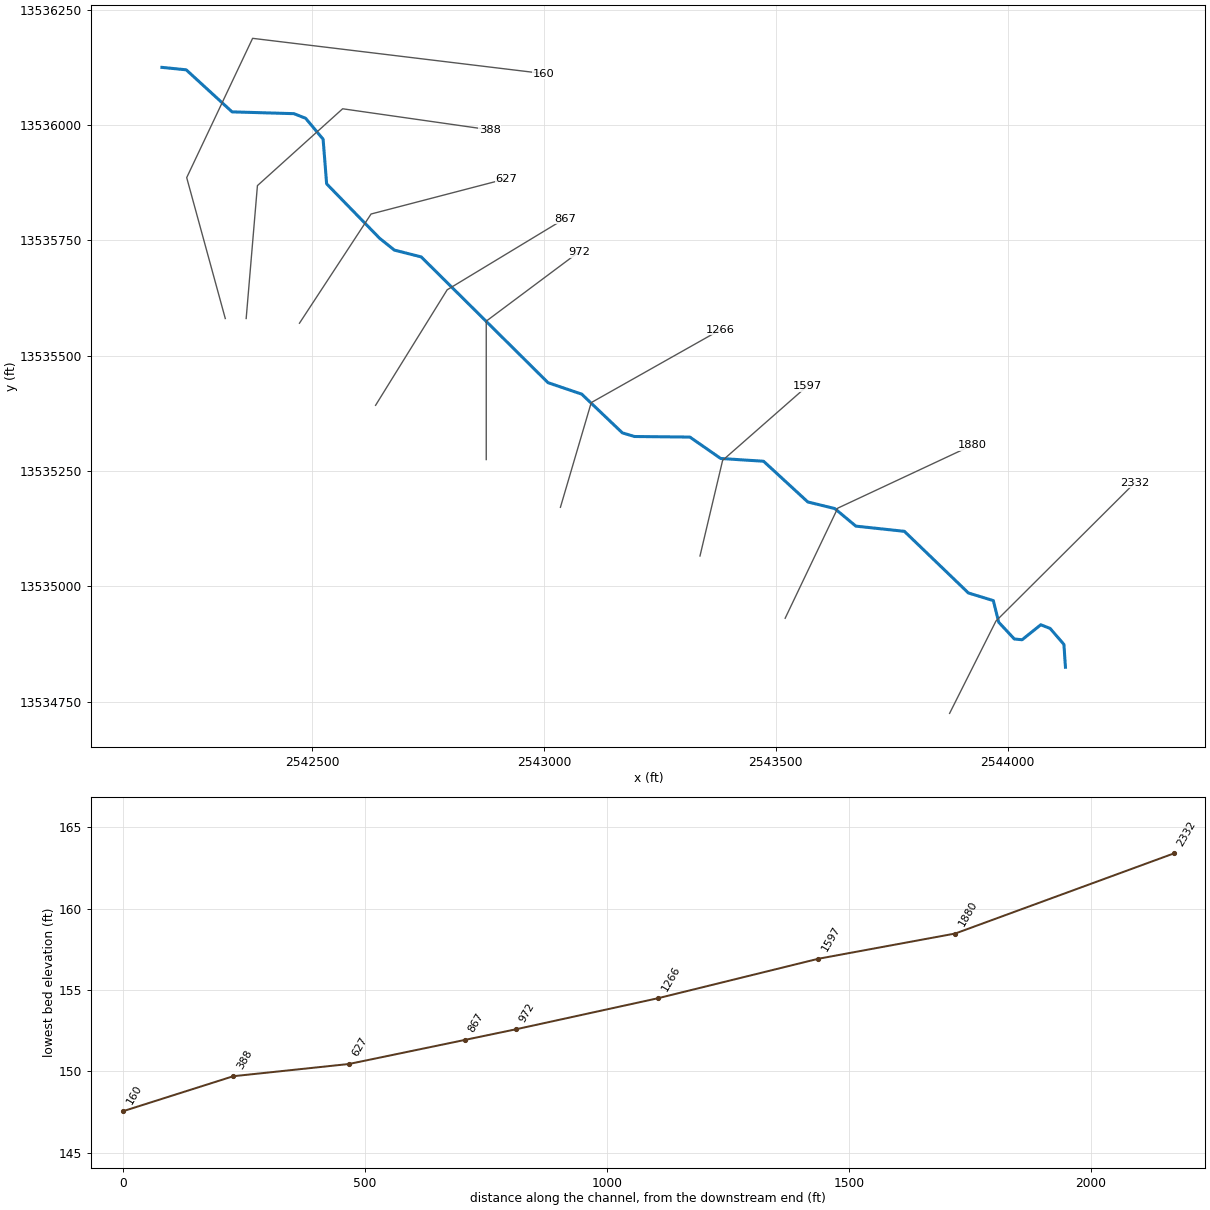
--- TRIB 11_3 TO GUADALUPE RIVER.prj (project) ---

Proj Title=TRIB 11_3 TO GUADALUPE RIVER Base Level Engineering
Current Plan=p01
Default Exp/Contr=0.3,0.1
English Units
Geom File=g01
Flow File=f01
Plan File=p01
Y Axis Title=Elevation
X Axis Title(PF)=Main Channel Distance
X Axis Title(XS)=Station
BEGIN DESCRIPTION:
TRIB 11_3 TO GUADALUPE RIVER
END DESCRIPTION:
DSS Export Rating Curves= 0
DSS Export Rating Curve Sorted= 0
DSS Export Volume Flow Curves= 0
DXF OffsetX= 0
DXF OffsetY= 0
DXF ScaleX= 1
DXF ScaleY= 10

--- TRIB 11_3 TO GUADALUPE RIVER.p01 (plan) ---

Plan Title=Multiple Run
Short Identifier=Multiple
Geom File=g01
Flow File=f01
Subcritical Flow
K Sum by GR= 0
Std Step Tol= 0.01
Critical Tol= 0.01
Num of Std Step Trials= 20
Max Error Tol= 0.3
Flow Tol Ratio= 0.001
Split Flow NTrial= 30
Split Flow Tol= 0.02
Split Flow Ratio= 0.02
Log Output Level= 0
Friction Slope Method= 1
Unsteady Friction Slope Method= 2
Unsteady Bridges Friction Slope Method= 1
Parabolic Critical Depth
Global Vel Dist=  1 , 1 , 1
Global Log Level= 0
CheckData=True
Encroach Param= -1, 0, 0, 0
BEGIN DESCRIPTION:
Multiple Run
END DESCRIPTION:

--- TRIB 11_3 TO GUADALUPE RIVER.f01 (steady flow) ---

Flow Title=Multiple
Number of Profiles=7
Profile Names=10-year,25-year,50-year,1pct_min,100-year,1pct_plu,500-year
River Rch & RM= TRIB 11_3 TO GUA,Reach-1,2332
     439     687     904     577    1152    2298    1846
Boundary for River Rch & Prof#=TRIB 11_3 TO GUA,Reach-1,1
Up Type=0
Dn Type=3
Dn Slope=0.005
Boundary for River Rch & Prof#=TRIB 11_3 TO GUA,Reach-1,2
Up Type=0
Dn Type=3
Dn Slope=0.005
Boundary for River Rch & Prof#=TRIB 11_3 TO GUA,Reach-1,3
Up Type=0
Dn Type=3
Dn Slope=0.005
Boundary for River Rch & Prof#=TRIB 11_3 TO GUA,Reach-1,4
Up Type=0
Dn Type=3
Dn Slope=0.005
Boundary for River Rch & Prof#=TRIB 11_3 TO GUA,Reach-1,5
Up Type=0
Dn Type=3
Dn Slope=0.005
Boundary for River Rch & Prof#=TRIB 11_3 TO GUA,Reach-1,6
Up Type=0
Dn Type=3
Dn Slope=0.005
Boundary for River Rch & Prof#=TRIB 11_3 TO GUA,Reach-1,7
Up Type=0
Dn Type=3
Dn Slope=0.005

--- TRIB 11_3 TO GUADALUPE RIVER.g01 (geometry) ---

Geom Title=Existing Conditions

River Reach=TRIB 11_3 TO GUA,Reach-1
Reach XY= 30
      2544125.00     13534825.00      2544121.73     13534874.36
      2544091.96     13534909.06      2544071.79     13534916.99
      2544031.53     13534884.54      2544014.71     13534886.15
      2543980.99     13534922.50      2543969.38     13534969.32
      2543915.58     13534985.89      2543777.43     13535119.48
      2543672.68     13535130.77      2543627.17     13535168.86
      2543568.95     13535183.16      2543473.50     13535271.38
      2543380.98     13535277.36      2543314.49     13535323.77
      2543194.99     13535324.98      2543168.82     13535332.83
      2543081.04     13535416.82      2543008.33     13535441.65
      2542734.68     13535714.22      2542676.65     13535728.98
      2542644.84     13535754.61      2542530.53     13535872.58
      2542522.93     13535969.31      2542485.17     13536014.67
      2542459.98     13536024.66      2542326.47     13536028.54
      2542227.51     13536119.67      2542175.00     13536125.00

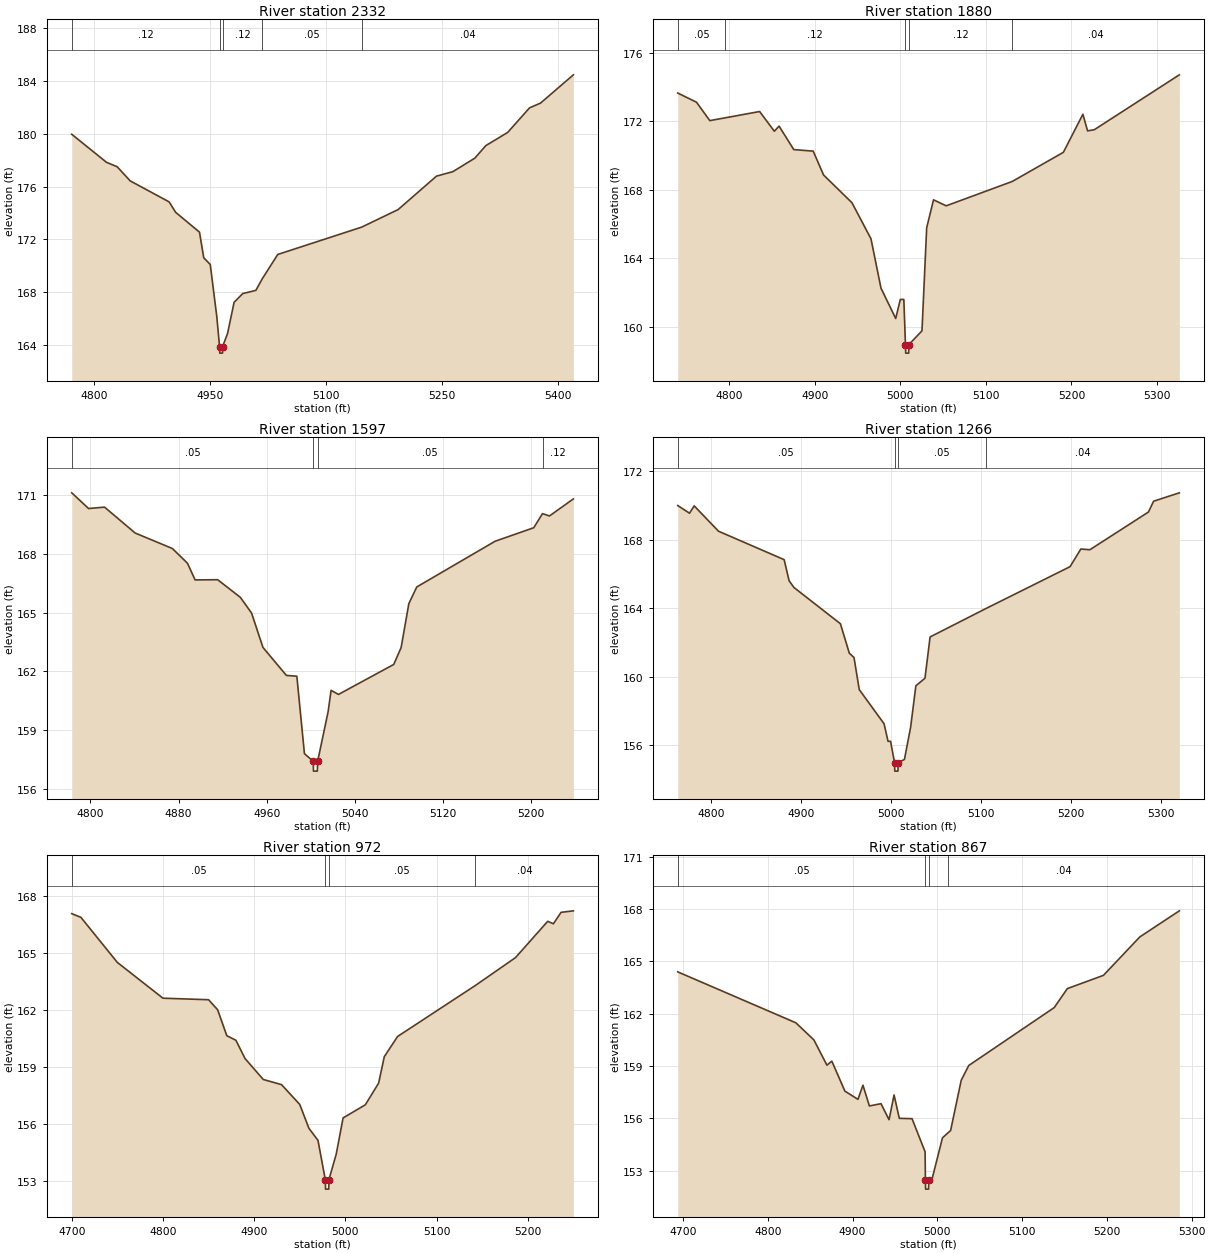
Type RM Length L Ch R = 1,2332,452,452,452
BEGIN DESCRIPTION:
TRIB 11_3 TO GUADALUPE RIVER 5.0
END DESCRIPTION:
XS GIS Cut Line= 3
      2543874.98     13534724.96      2543975.00     13534925.00
      2544274.99     13535224.99
#Sta/Elev= 30
  4771.4  179.96  4816.2  177.84  4830.1  177.50  4846.9  176.43  4897.2  174.84
  4905.6  174.05  4936.4  172.55  4941.9  170.61  4950.3  170.10  4958.7  166.18
  4962.3  163.89  4962.6  163.39  4966.1  163.39  4966.3  163.89  4972.7  164.89
  4981.1  167.24  4992.3  167.90  5009.2  168.14  5017.5  169.02  5037.5  170.86
  5145.9  172.93  5193.0  174.26  5242.5  176.79  5263.7  177.13  5292.0  178.15
  5306.2  179.10  5334.5  180.10  5362.7  181.96  5376.9  182.32  5419.3  184.46
#Mann=5,-1,0
  4771.4    0.12       0  4962.3    0.05       0  4966.3    0.12       0
  5017.5    0.05       0  5145.9    0.04       0
Bank Sta=4962.3,4966.3
Exp/Cntr=0.3,0.1

Type RM Length L Ch R = 1,1880,283,283,283
BEGIN DESCRIPTION:
Mapping XS ceb9bd5e
END DESCRIPTION:
XS GIS Cut Line= 3
      2543520.10     13534931.10      2543633.51     13535169.67
      2543924.90     13535306.56
#Sta/Elev= 30
  4740.0  173.64  4762.0  173.10  4777.5  172.03  4795.2  172.19  4835.7  172.56
  4852.9  171.41  4858.4  171.71  4875.6  170.34  4898.3  170.25  4910.4  168.86
  4943.6  167.24  4965.8  165.14  4977.5  162.26  4994.7  160.49  5000.1  161.60
  5004.2  161.60  5006.1  158.97  5006.4  158.47  5009.9  158.47  5010.1  158.97
  5025.4  159.77  5030.9  165.78  5038.9  167.41  5053.7  167.06  5130.8  168.48
  5190.6  170.18  5213.4  172.40  5218.9  171.43  5226.8  171.50  5326.1  174.70
#Mann=5,-1,0
  4740.0    0.05       0  4795.2    0.12       0  5006.1    0.05       0
  5010.1    0.12       0  5130.8    0.04       0
Bank Sta=5006.1,5010.1
Exp/Cntr=0.3,0.1

Type RM Length L Ch R = 1,1597,331,331,331
BEGIN DESCRIPTION:
Mapping XS da5c8ec8
END DESCRIPTION:
XS GIS Cut Line= 3
      2543336.27     13535066.01      2543385.16     13535273.31
      2543567.06     13535433.70
#Sta/Elev= 30
  4783.0  171.11  4798.3  170.31  4812.8  170.38  4840.6  169.06  4874.4  168.27
  4888.1  167.52  4895.0  166.67  4915.5  166.68  4936.1  165.78  4946.3  164.98
  4956.6  163.23  4977.9  161.80  4987.4  161.76  4994.3  157.81  5002.3  157.42
  5002.5  156.92  5006.0  156.92  5006.3  157.42  5015.8  159.95  5018.5  161.04
  5025.2  160.83  5075.4  162.36  5082.1  163.22  5089.1  165.46  5096.3  166.31
  5167.4  168.64  5202.5  169.33  5210.5  170.05  5216.8  169.93  5238.5  170.80
#Mann=4,-1,0
  4783.0    0.05       0  5002.3    0.05       0  5006.3    0.05       0
  5210.5    0.12       0
Bank Sta=5002.3,5006.3
Exp/Cntr=0.3,0.1

Type RM Length L Ch R = 1,1266,294,294,294
BEGIN DESCRIPTION:
Mapping XS 9b51475e
END DESCRIPTION:
XS GIS Cut Line= 3
      2543035.10     13535171.58      2543101.60     13535398.47
      2543380.62     13535556.51
#Sta/Elev= 30
  4763.3  170.00  4776.4  169.55  4781.6  169.98  4808.6  168.50  4881.5  166.84
  4887.0  165.61  4892.3  165.22  4944.0  163.10  4953.9  161.38  4959.1  161.13
  4964.9  159.26  4992.5  157.26  4996.9  156.24  4999.7  156.24  5004.1  155.00
  5004.4  154.50  5007.9  154.50  5008.1  155.00  5015.1  155.18  5022.0  157.07
  5027.8  159.48  5037.9  159.92  5043.6  162.33  5105.7  163.99  5199.0  166.43
  5211.0  167.46  5221.1  167.42  5286.1  169.62  5291.8  170.25  5320.4  170.74
#Mann=4,-1,0
  4763.3    0.05       0  5004.1    0.05       0  5008.1    0.05       0
  5105.7    0.04       0
Bank Sta=5004.1,5008.1
Exp/Cntr=0.3,0.1

Type RM Length L Ch R = 1,972,105,105,105
BEGIN DESCRIPTION:
TRIB 11_3 TO GUADALUPE RIVER 2.0
END DESCRIPTION:
XS GIS Cut Line= 3
      2542875.00     13535274.99      2542875.00     13535575.00
      2543074.99     13535724.99
#Sta/Elev= 30
  4700.0  167.06  4710.0  166.87  4750.0  164.50  4800.0  162.62  4850.0  162.54
  4860.0  162.01  4870.0  160.65  4880.0  160.41  4890.0  159.45  4910.0  158.35
  4930.0  158.08  4950.0  157.04  4960.0  155.79  4970.0  155.15  4978.0  153.09
  4978.3  152.59  4981.8  152.59  4982.0  153.09  4990.0  154.43  4997.5  156.33
  5021.9  157.02  5036.5  158.16  5042.7  159.55  5057.3  160.61  5142.6  163.29
  5186.5  164.75  5221.9  166.66  5228.1  166.53  5236.5  167.13  5250.0  167.21
#Mann=4,-1,0
  4700.0    0.05       0  4978.0    0.05       0  4982.0    0.05       0
  5142.6    0.04       0
Bank Sta=4978,4982
Exp/Cntr=0.3,0.1

Type RM Length L Ch R = 1,867,240,240,240
BEGIN DESCRIPTION:
Mapping XS 1960c935
END DESCRIPTION:
XS GIS Cut Line= 3
      2542636.16     13535392.57      2542790.67     13535642.91
      2543044.92     13535797.42
#Sta/Elev= 30
  4693.8  164.40  4833.1  161.48  4854.4  160.50  4869.8  159.05  4875.6  159.28
  4891.0  157.56  4906.4  157.09  4912.3  157.90  4919.9  156.71  4933.6  156.84
  4943.1  155.92  4949.0  157.34  4955.2  156.00  4970.2  155.98  4985.6  154.08
  4986.0  152.44  4986.2  151.94  4989.7  151.94  4990.0  152.44  4993.4  152.44
  5006.1  154.88  5012.4  155.16  5015.7  155.30  5028.2  158.18  5037.1  159.03
  5137.9  162.35  5153.4  163.44  5196.0  164.20  5238.8  166.40  5285.5  167.90
#Mann=4,-1,0
  4693.8    0.05       0  4986.0    0.05       0  4990.0    0.05       0
  5012.4    0.04       0
Bank Sta=4986,4990
Exp/Cntr=0.3,0.1

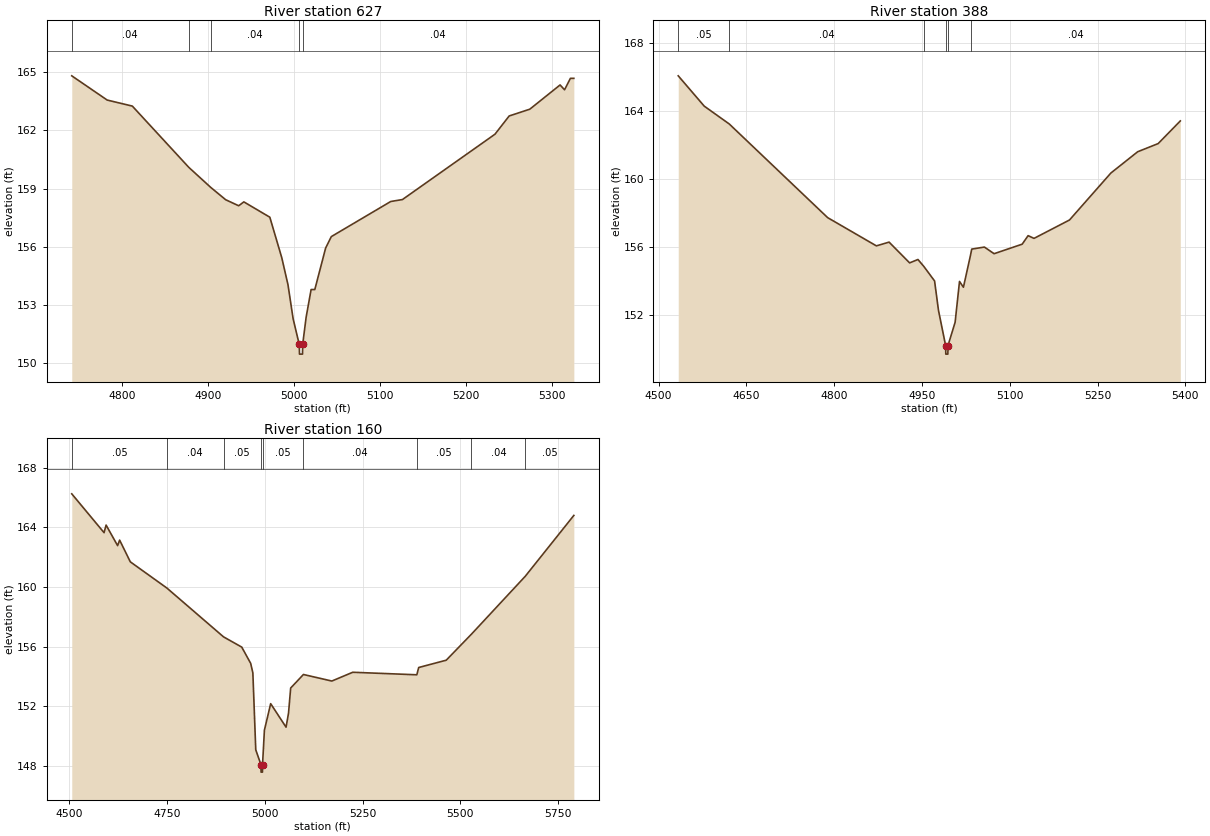
Type RM Length L Ch R = 1,627,239,239,239
BEGIN DESCRIPTION:
Mapping XS 2a2d35db
END DESCRIPTION:
XS GIS Cut Line= 3
      2542471.90     13535570.53      2542626.40     13535807.18
      2542917.77     13535883.44
#Sta/Elev= 30
  4741.8  164.81  4783.0  163.56  4812.2  163.25  4877.9  160.09  4903.3  159.06
  4920.8  158.42  4935.9  158.11  4941.9  158.31  4972.1  157.52  4986.0  155.43
  4993.2  154.04  4999.2  152.28  5006.3  150.96  5006.6  150.46  5010.1  150.46
  5010.3  150.96  5014.3  152.36  5020.1  153.79  5024.4  153.79  5037.0  155.93
  5043.6  156.52  5112.7  158.33  5126.3  158.43  5233.9  161.80  5250.4  162.74
  5274.4  163.09  5309.6  164.34  5314.8  164.09  5321.6  164.68  5325.6  164.68
#Mann=5,-1,0
  4741.8    0.04       0  4877.9    0.05       0  4903.3    0.04       0
  5006.3    0.04       0  5010.3    0.04       0
Bank Sta=5006.3,5010.3
Exp/Cntr=0.3,0.1

Type RM Length L Ch R = 1,388,228,228,228
BEGIN DESCRIPTION:
TRIB 11_3 TO GUADALUPE RIVER 1.0
END DESCRIPTION:
XS GIS Cut Line= 4
      2542356.89     13535580.72      2542381.18     13535868.71
      2542565.06     13536035.25      2542882.40     13535989.70
#Sta/Elev= 30
  4533.7  166.06  4578.1  164.28  4620.9  163.23  4788.9  157.73  4872.2  156.07
  4893.9  156.29  4929.0  155.07  4943.2  155.27  4953.3  154.86  4971.6  154.01
  4978.3  152.28  4990.5  150.21  4990.8  149.71  4994.3  149.71  4994.5  150.21
  5006.7  151.58  5014.2  153.98  5020.9  153.64  5033.0  155.52  5035.1  155.88
  5056.7  156.00  5073.3  155.61  5121.3  156.17  5131.4  156.67  5141.5  156.51
  5202.1  157.59  5272.8  160.35  5318.6  161.60  5353.6  162.08  5391.4  163.41
#Mann=6,-1,0
  4533.7    0.05       0  4620.9    0.04       0  4953.3    0.05       0
  4990.5    0.05       0  4994.5    0.05       0  5033.0    0.04       0
Bank Sta=4990.5,4994.5
Exp/Cntr=0.3,0.1

Type RM Length L Ch R = 1,160,0,0,0
BEGIN DESCRIPTION:
LGII3231
END DESCRIPTION:
XS GIS Cut Line= 4
      2542311.80     13535580.70      2542228.52     13535886.06
      2542370.77     13536187.91      2542998.74     13536111.58
#Sta/Elev= 30
  4507.0  166.26  4589.5  163.65  4594.7  164.16  4624.1  162.78  4629.3  163.15
  4656.6  161.69  4750.0  159.93  4894.7  156.65  4941.3  155.96  4964.1  154.87
  4969.7  154.23  4977.1  149.06  4990.4  148.06  4990.7  147.56  4994.2  147.56
  4994.4  148.06  4999.2  150.38  5015.2  152.16  5054.5  150.58  5060.8  151.52
  5066.3  153.21  5098.9  154.12  5171.5  153.68  5224.9  154.27  5388.6  154.10
  5393.4  154.59  5463.7  155.08  5528.2  156.83  5665.7  160.72  5789.8  164.81
#Mann=9,-1,0
  4507.0    0.05       0  4750.0    0.04       0  4894.7    0.05       0
  4990.4    0.05       0  4994.4    0.05       0  5098.9    0.04       0
  5388.6    0.05       0  5528.2    0.04       0  5665.7    0.05       0
Bank Sta=4990.4,4994.4
Exp/Cntr=0.3,0.1

Chan Stop Cuts=-1