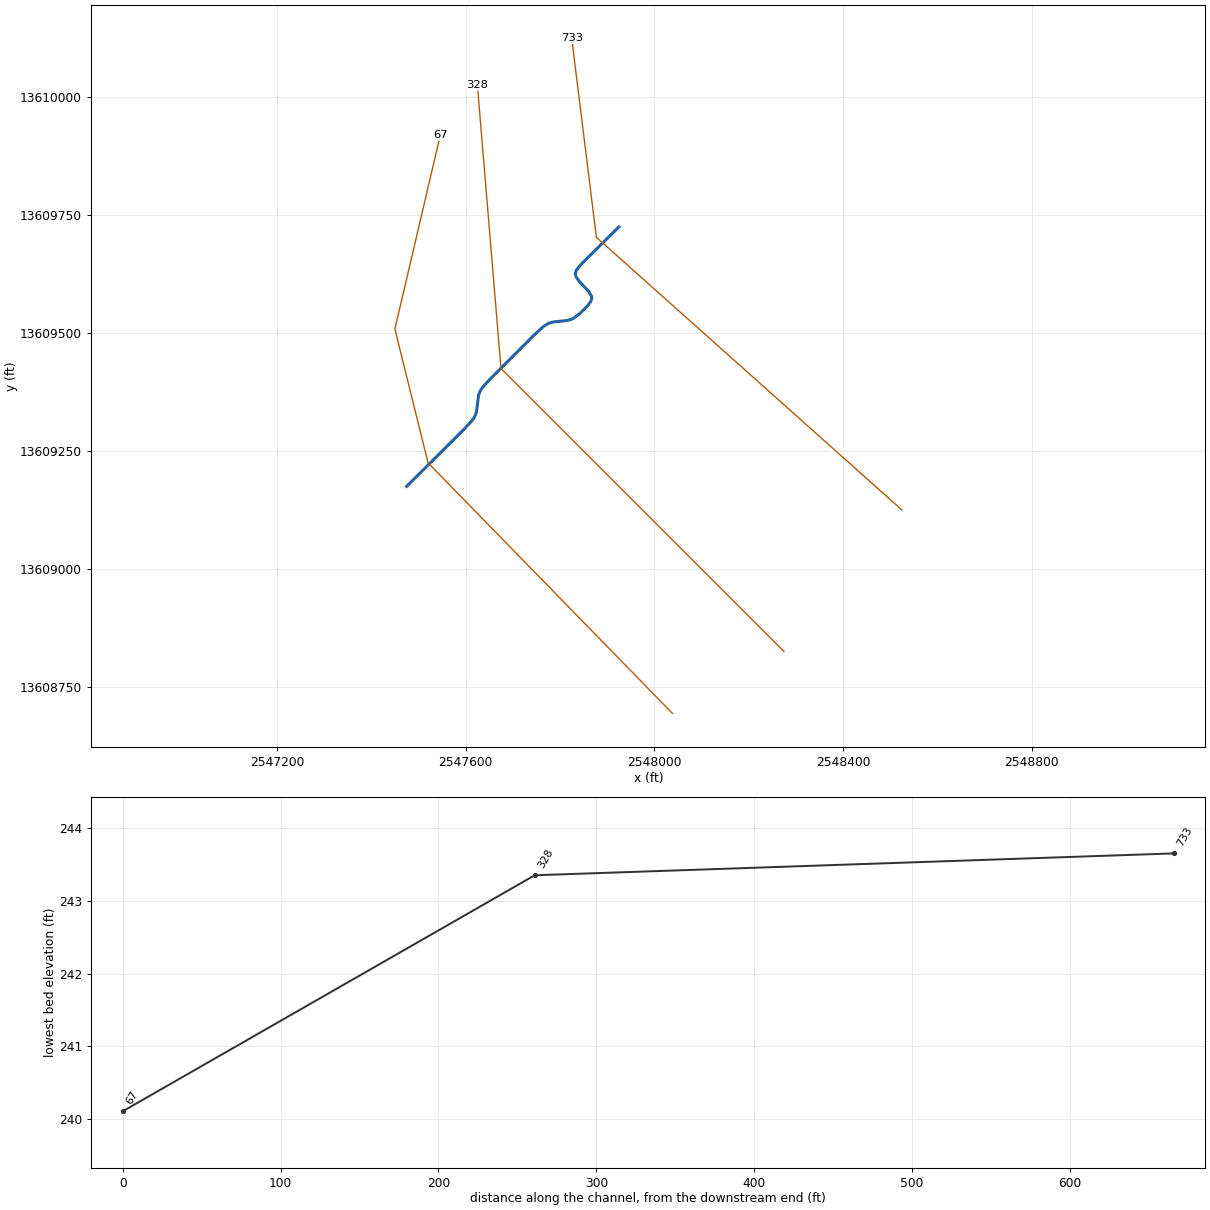
--- TRIB 11_3 TO IRISH CREEK.prj (project) ---

Proj Title=TRIB 11_3 TO IRISH CREEK Base Level Engineering
Current Plan=p01
Default Exp/Contr=0.3,0.1
English Units
Geom File=g01
Flow File=f01
Plan File=p01
Y Axis Title=Elevation
X Axis Title(PF)=Main Channel Distance
X Axis Title(XS)=Station
BEGIN DESCRIPTION:
TRIB 11_3 TO IRISH CREEK
END DESCRIPTION:
DSS Export Rating Curves= 0
DSS Export Rating Curve Sorted= 0
DSS Export Volume Flow Curves= 0
DXF OffsetX= 0
DXF OffsetY= 0
DXF ScaleX= 1
DXF ScaleY= 10

--- TRIB 11_3 TO IRISH CREEK.p01 (plan) ---

Plan Title=Multiple Run
Short Identifier=Multiple
Geom File=g01
Flow File=f01
Subcritical Flow
K Sum by GR= 0
Std Step Tol= 0.01
Critical Tol= 0.01
Num of Std Step Trials= 20
Max Error Tol= 0.3
Flow Tol Ratio= 0.001
Split Flow NTrial= 30
Split Flow Tol= 0.02
Split Flow Ratio= 0.02
Log Output Level= 0
Friction Slope Method= 1
Unsteady Friction Slope Method= 2
Unsteady Bridges Friction Slope Method= 1
Parabolic Critical Depth
Global Vel Dist=  1 , 1 , 1
Global Log Level= 0
CheckData=True
Encroach Param= -1, 0, 0, 0
BEGIN DESCRIPTION:
Multiple Run
END DESCRIPTION:

--- TRIB 11_3 TO IRISH CREEK.f01 (steady flow) ---

Flow Title=Multiple
Number of Profiles=7
Profile Names=10-year,25-year,50-year,1pct_min,100-year,1pct_plu,500-year
River Rch & RM= TRIB 11_3 TO IRI,Reach-1,733
     495     781    1034     665    1327    2648    2160
Boundary for River Rch & Prof#=TRIB 11_3 TO IRI,Reach-1,1
Up Type=0
Dn Type=3
Dn Slope=0.005
Boundary for River Rch & Prof#=TRIB 11_3 TO IRI,Reach-1,2
Up Type=0
Dn Type=3
Dn Slope=0.005
Boundary for River Rch & Prof#=TRIB 11_3 TO IRI,Reach-1,3
Up Type=0
Dn Type=3
Dn Slope=0.005
Boundary for River Rch & Prof#=TRIB 11_3 TO IRI,Reach-1,4
Up Type=0
Dn Type=3
Dn Slope=0.005
Boundary for River Rch & Prof#=TRIB 11_3 TO IRI,Reach-1,5
Up Type=0
Dn Type=3
Dn Slope=0.005
Boundary for River Rch & Prof#=TRIB 11_3 TO IRI,Reach-1,6
Up Type=0
Dn Type=3
Dn Slope=0.005
Boundary for River Rch & Prof#=TRIB 11_3 TO IRI,Reach-1,7
Up Type=0
Dn Type=3
Dn Slope=0.005

--- TRIB 11_3 TO IRISH CREEK.g01 (geometry) ---

Geom Title=Existing Conditions

River Reach=TRIB 11_3 TO IRI,Reach-1
Reach XY= 30
      2547925.00     13609725.00      2547847.31     13609648.33
      2547838.48     13609638.33      2547834.18     13609631.66
      2547832.49     13609624.99      2547834.59     13609618.32
      2547842.15     13609608.30      2547860.81     13609588.22
      2547866.93     13609578.15      2547867.54     13609574.79
      2547865.82     13609568.05      2547858.77     13609557.96
      2547842.53     13609541.65      2547827.83     13609530.86
      2547823.82     13609528.98      2547814.69     13609526.55
      2547785.74     13609523.45      2547776.71     13609521.02
      2547765.35     13609514.22      2547744.85     13609495.39
      2547651.30     13609401.82      2547635.78     13609384.68
      2547630.86     13609377.29      2547627.53     13609368.95
      2547623.45     13609335.64      2547621.03     13609326.65
      2547616.84     13609318.95      2547611.37     13609311.79
      2547595.39     13609294.84      2547475.00     13609175.00

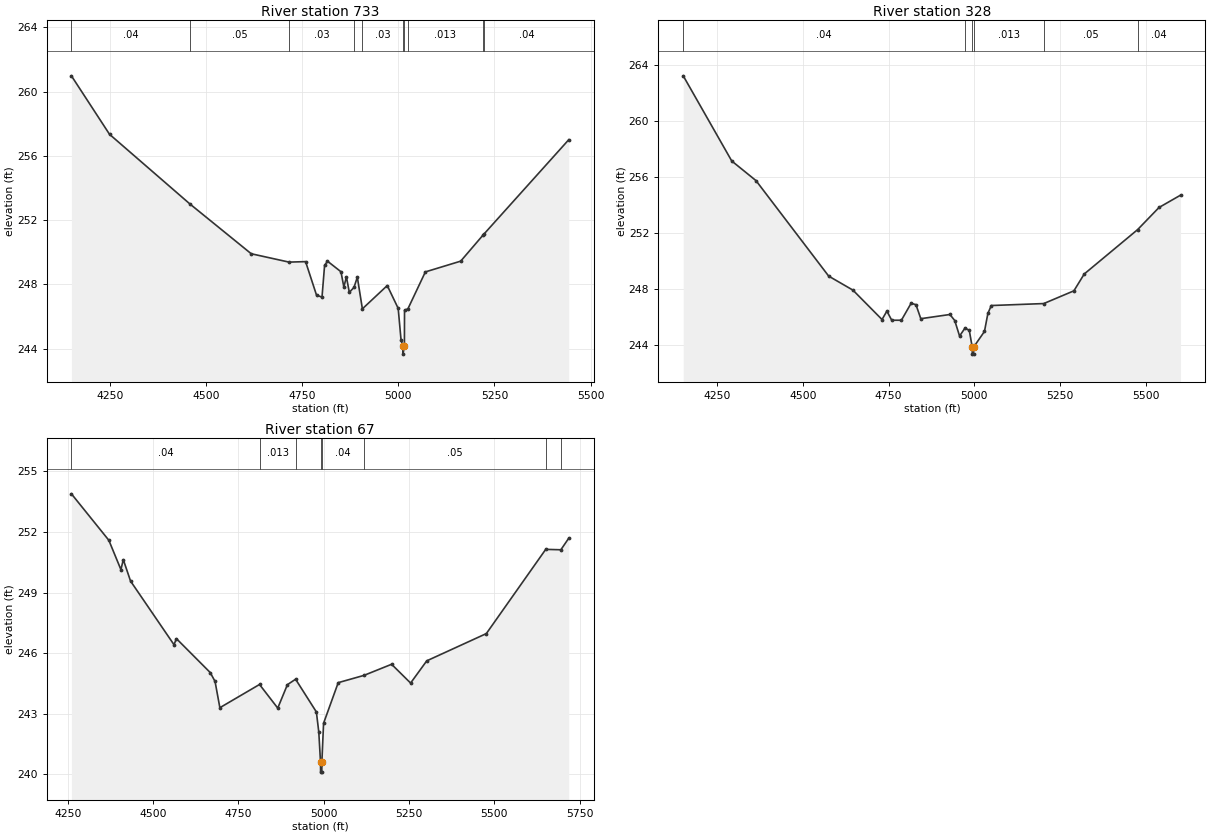
Type RM Length L Ch R = 1,733,405,405,405
BEGIN DESCRIPTION:
TRIB 11_3 TO IRISH CREEK 2.0
END DESCRIPTION:
XS GIS Cut Line= 3
      2548524.99     13609125.01      2547877.29     13609702.99
      2547825.00     13610124.98
#Sta/Elev= 30
  4149.9  260.98  4249.0  257.34  4458.6  252.99  4617.6  249.90  4715.8  249.38
  4758.9  249.41  4787.4  247.32  4801.6  247.20  4808.3  249.17  4815.8  249.44
  4850.9  248.78  4858.4  247.83  4865.1  248.46  4872.6  247.50  4884.7  247.80
  4893.5  248.44  4906.6  246.47  4971.3  247.92  4999.7  246.50  5007.2  244.52
  5011.9  244.15  5012.2  243.65  5015.9  244.15  5016.2  246.38  5025.0  246.47
  5070.4  248.77  5162.3  249.44  5220.3  251.06  5222.9  251.13  5443.2  257.00
#Mann=10,-1,0
  4149.9    0.04       0  4458.6    0.05       0  4715.8    0.03       0
  4884.7    0.05       0  4906.6    0.03       0  5011.9    0.03       0
  5015.9    0.03       0  5025.0   0.013       0  5220.3    0.05       0
  5222.9    0.04       0
Bank Sta=5011.9,5015.9
Exp/Cntr=0.3,0.1

Type RM Length L Ch R = 1,328,261,261,261
BEGIN DESCRIPTION:
TRIB 11_3 TO IRISH CREEK 1.0
END DESCRIPTION:
XS GIS Cut Line= 3
      2548275.03     13608824.97      2547675.00     13609425.00
      2547625.00     13610025.05
#Sta/Elev= 30
  4151.1  263.22  4292.6  257.14  4363.3  255.74  4575.4  248.92  4646.1  247.92
  4731.0  245.82  4745.1  246.42  4759.3  245.77  4787.5  245.77  4815.8  246.98
  4830.0  246.88  4844.1  245.88  4929.0  246.18  4943.1  245.75  4957.2  244.64
  4973.0  245.21  4985.5  245.05  4994.1  243.85  4994.4  243.35  4997.9  243.35
  4998.1  243.85  5029.8  244.97  5039.8  246.26  5049.8  246.82  5202.7  246.96
  5290.7  247.87  5320.8  249.07  5476.6  252.24  5539.0  253.82  5601.8  254.70
#Mann=6,-1,0
  4151.1    0.04       0  4973.0   0.013       0  4994.1    0.03       0
  4998.1   0.013       0  5202.7    0.05       0  5476.6    0.04       0
Bank Sta=4994.1,4998.1
Exp/Cntr=0.3,0.1

Type RM Length L Ch R = 1,67,0,0,0
BEGIN DESCRIPTION:
TRIB 11_3 TO IRISH CREEK 0.5
END DESCRIPTION:
XS GIS Cut Line= 4
      2548038.55     13608693.48      2547520.31     13609224.74
      2547450.00     13609508.59      2547546.36     13609920.06
#Sta/Elev= 30
  4261.0  253.89  4370.7  251.59  4406.0  250.14  4413.1  250.63  4434.3  249.57
  4561.6  246.42  4568.7  246.72  4667.8  245.04  4681.9  244.60  4696.0  243.30
  4812.2  244.45  4865.6  243.28  4893.9  244.44  4917.9  244.71  4978.8  243.09
  4985.9  242.09  4990.9  240.61  4991.2  240.11  4994.7  240.11  4994.9  240.61
  4999.9  242.53  5042.8  244.54  5118.2  244.90  5199.2  245.45  5254.9  244.52
  5302.2  245.62  5476.8  246.97  5650.8  251.14  5695.2  251.12  5718.2  251.69
#Mann=8,-1,0
  4261.0    0.04       0  4812.2   0.013       0  4917.9    0.04       0
  4990.9    0.04       0  4994.9    0.04       0  5118.2    0.05       0
  5650.8    0.12       0  5695.2    0.04       0
Bank Sta=4990.9,4994.9
Exp/Cntr=0.3,0.1

Chan Stop Cuts=-1