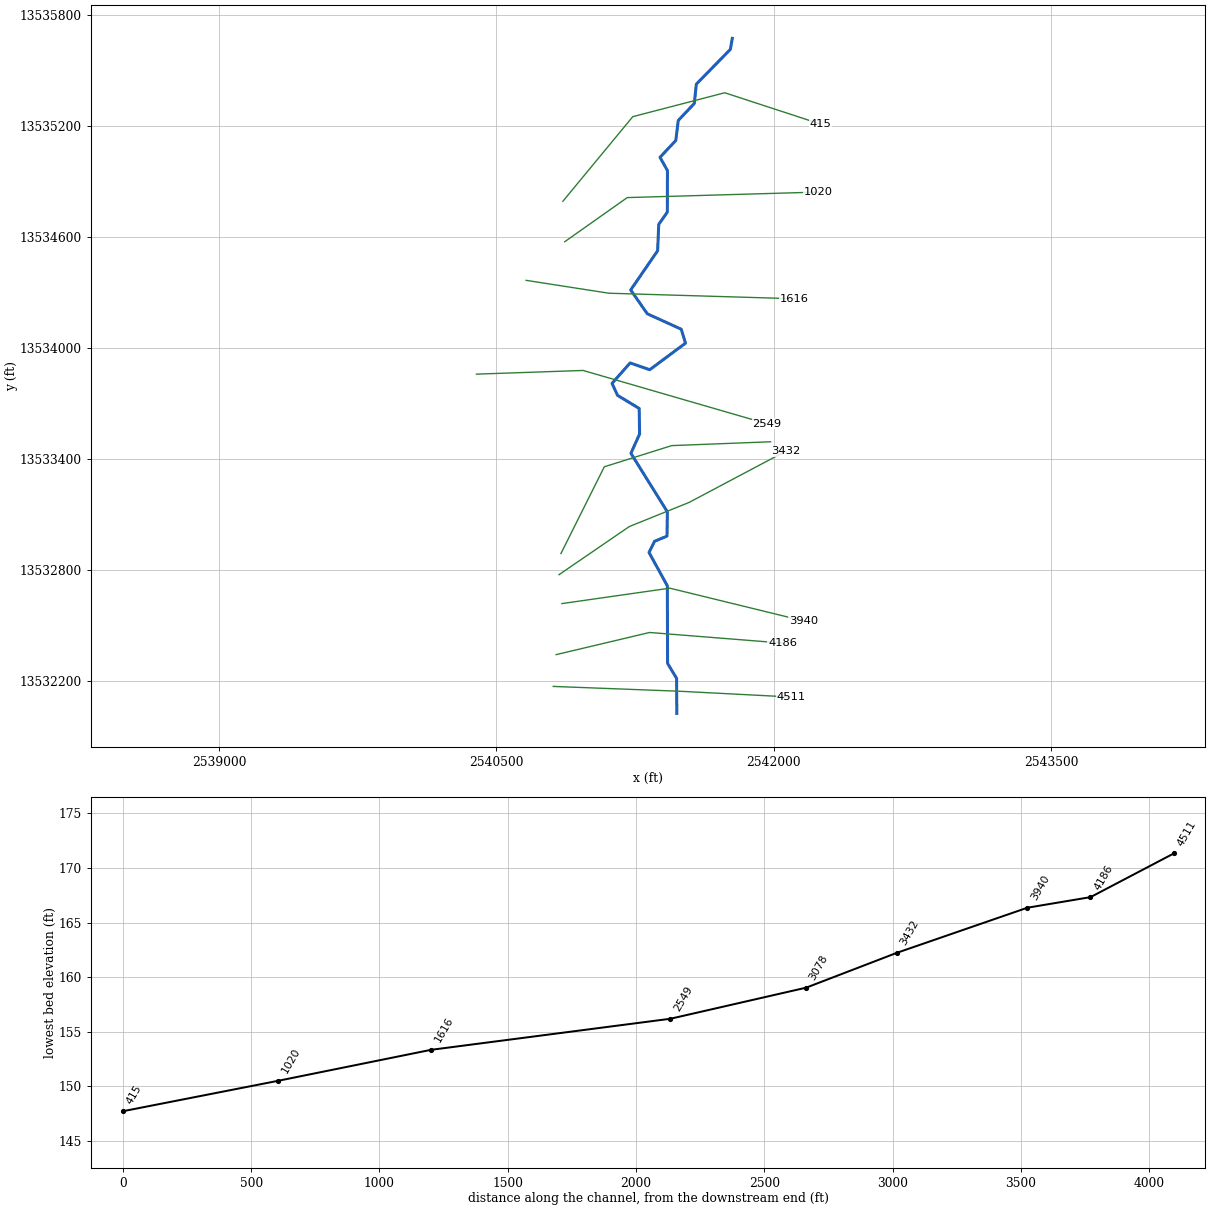
--- TRIB 11_4 TO GUADALUPE RIVER.prj (project) ---

Proj Title=TRIB 11_4 TO GUADALUPE RIVER Base Level Engineering
Current Plan=p01
Default Exp/Contr=0.3,0.1
English Units
Geom File=g01
Flow File=f01
Plan File=p01
Y Axis Title=Elevation
X Axis Title(PF)=Main Channel Distance
X Axis Title(XS)=Station
BEGIN DESCRIPTION:
TRIB 11_4 TO GUADALUPE RIVER
END DESCRIPTION:
DSS Export Rating Curves= 0
DSS Export Rating Curve Sorted= 0
DSS Export Volume Flow Curves= 0
DXF OffsetX= 0
DXF OffsetY= 0
DXF ScaleX= 1
DXF ScaleY= 10

--- TRIB 11_4 TO GUADALUPE RIVER.p01 (plan) ---

Plan Title=Multiple Run
Short Identifier=Multiple
Geom File=g01
Flow File=f01
Subcritical Flow
K Sum by GR= 0
Std Step Tol= 0.01
Critical Tol= 0.01
Num of Std Step Trials= 20
Max Error Tol= 0.3
Flow Tol Ratio= 0.001
Split Flow NTrial= 30
Split Flow Tol= 0.02
Split Flow Ratio= 0.02
Log Output Level= 0
Friction Slope Method= 1
Unsteady Friction Slope Method= 2
Unsteady Bridges Friction Slope Method= 1
Parabolic Critical Depth
Global Vel Dist=  1 , 1 , 1
Global Log Level= 0
CheckData=True
Encroach Param= -1, 0, 0, 0
BEGIN DESCRIPTION:
Multiple Run
END DESCRIPTION:

--- TRIB 11_4 TO GUADALUPE RIVER.f01 (steady flow) ---

Flow Title=Multiple
Number of Profiles=7
Profile Names=10-year,25-year,50-year,1pct_min,100-year,1pct_plu,500-year
River Rch & RM= TRIB 11_4 TO GUA,Reach-1,4511
     676    1079    1440     930    1856    3703    3045
River Rch & RM= TRIB 11_4 TO GUA,Reach-1,3432
     858    1387    1865    1213    2421    4831    4033
Boundary for River Rch & Prof#=TRIB 11_4 TO GUA,Reach-1,1
Up Type=0
Dn Type=3
Dn Slope=0.005
Boundary for River Rch & Prof#=TRIB 11_4 TO GUA,Reach-1,2
Up Type=0
Dn Type=3
Dn Slope=0.005
Boundary for River Rch & Prof#=TRIB 11_4 TO GUA,Reach-1,3
Up Type=0
Dn Type=3
Dn Slope=0.005
Boundary for River Rch & Prof#=TRIB 11_4 TO GUA,Reach-1,4
Up Type=0
Dn Type=3
Dn Slope=0.005
Boundary for River Rch & Prof#=TRIB 11_4 TO GUA,Reach-1,5
Up Type=0
Dn Type=3
Dn Slope=0.005
Boundary for River Rch & Prof#=TRIB 11_4 TO GUA,Reach-1,6
Up Type=0
Dn Type=3
Dn Slope=0.005
Boundary for River Rch & Prof#=TRIB 11_4 TO GUA,Reach-1,7
Up Type=0
Dn Type=3
Dn Slope=0.005

--- TRIB 11_4 TO GUADALUPE RIVER.g01 (geometry) ---

Geom Title=Existing Conditions

River Reach=TRIB 11_4 TO GUA,Reach-1
Reach XY= 30
      2541475.00     13532025.00      2541473.79     13532214.50
      2541425.07     13532295.03      2541423.80     13532714.50
      2541324.61     13532895.27      2541354.50     13532955.29
      2541421.91     13532983.31      2541423.96     13533114.55
      2541226.80     13533431.11      2541273.77     13533535.50
      2541271.56     13533673.75      2541154.32     13533744.64
      2541124.86     13533809.59      2541222.69     13533919.89
      2541328.31     13533883.07      2541521.92     13534026.66
      2541499.10     13534102.14      2541315.29     13534185.76
      2541225.55     13534314.35      2541371.24     13534526.56
      2541377.27     13534669.06      2541423.78     13534735.50
      2541424.34     13534959.84      2541384.15     13535031.73
      2541469.45     13535122.57      2541482.88     13535231.16
      2541569.46     13535322.58      2541580.52     13535427.43
      2541764.48     13535615.21      2541775.00     13535675.00

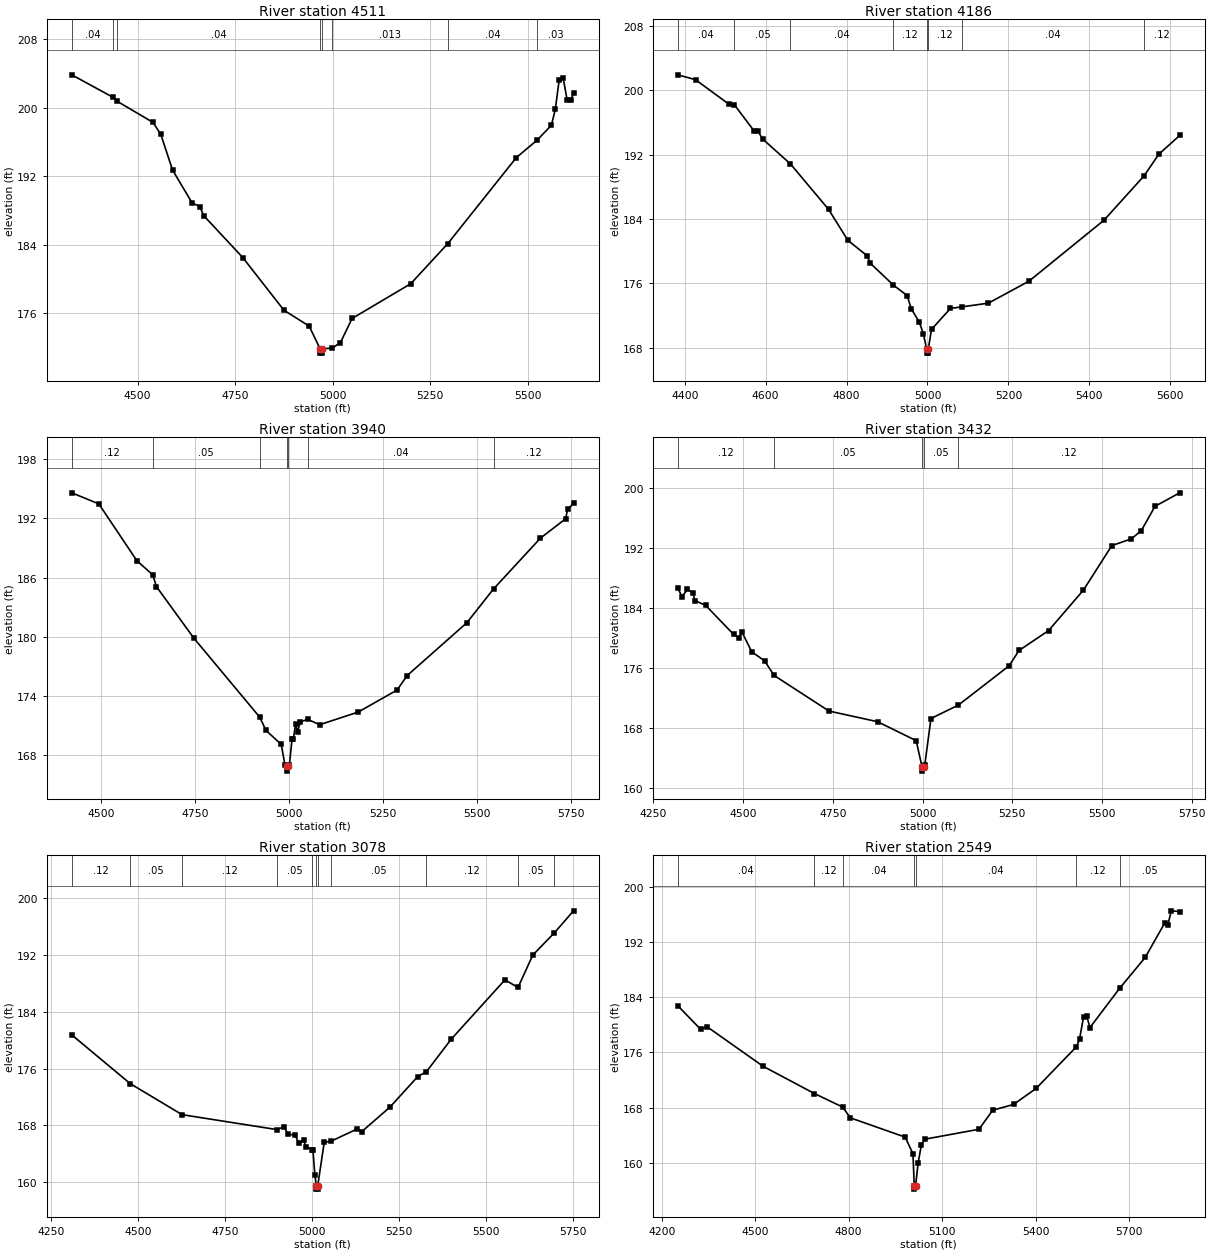
Type RM Length L Ch R = 1,4511,325,325,325
BEGIN DESCRIPTION:
LGII3222
END DESCRIPTION:
XS GIS Cut Line= 3
      2540806.92     13532170.75      2541489.17     13532144.71
      2542091.62     13532113.55
#Sta/Elev= 30
  4331.2  203.82  4437.6  201.18  4447.3  200.74  4539.4  198.27  4559.4  196.87
  4589.5  192.71  4639.5  188.88  4659.5  188.44  4669.5  187.38  4769.6  182.49
  4874.9  176.35  4939.7  174.49  4967.7  171.84  4968.0  171.34  4971.5  171.34
  4971.7  171.84  4999.2  171.93  5019.8  172.58  5049.8  175.39  5200.0  179.44
  5294.9  184.12  5470.4  194.15  5524.7  196.23  5560.5  197.94  5570.5  199.80
  5580.5  203.26  5590.5  203.48  5600.6  200.93  5610.6  200.90  5617.2  201.71
#Mann=8,-1,0
  4331.2    0.04       0  4437.6    0.05       0  4447.3    0.04       0
  4967.7    0.03       0  4971.7    0.04       0  4999.2   0.013       0
  5294.9    0.04       0  5524.7    0.03       0
Bank Sta=4967.7,4971.7
Exp/Cntr=0.3,0.1

Type RM Length L Ch R = 1,4186,246,246,246
BEGIN DESCRIPTION:
LGII3221
END DESCRIPTION:
XS GIS Cut Line= 3
      2540822.51     13532342.63      2541327.71     13532462.42
      2542046.42     13532405.13
#Sta/Elev= 30
  4383.2  201.92  4426.9  201.31  4509.1  198.28  4522.5  198.22  4570.8  194.99
  4581.0  194.92  4592.5  193.95  4661.3  190.85  4755.7  185.19  4803.6  181.33
  4851.0  179.43  4858.5  178.51  4914.9  175.83  4949.9  174.47  4959.9  172.85
  4979.9  171.18  4990.0  169.72  4998.0  167.83  4998.3  167.33  5001.8  167.33
  5002.0  167.83  5010.0  170.28  5056.9  172.89  5086.5  173.09  5150.5  173.54
  5250.8  176.27  5436.3  183.85  5535.3  189.36  5571.8  192.05  5623.4  194.38
#Mann=8,-1,0
  4383.2    0.04       0  4522.5    0.05       0  4661.3    0.04       0
  4914.9    0.12       0  4998.0    0.05       0  5002.0    0.12       0
  5086.5    0.04       0  5535.3    0.12       0
Bank Sta=4998,5002
Exp/Cntr=0.3,0.1

Type RM Length L Ch R = 1,3940,508,508,508
BEGIN DESCRIPTION:
LGII3220
END DESCRIPTION:
XS GIS Cut Line= 3
      2540853.70     13532618.66      2541437.08     13532702.00
      2542160.55     13532525.04
#Sta/Elev= 30
  4422.7  194.59  4494.7  193.47  4595.7  187.71  4638.1  186.27  4647.8  185.08
  4747.3  179.85  4922.3  171.84  4939.2  170.49  4979.6  169.07  4989.7  166.96
  4994.3  166.86  4994.6  166.36  4998.3  166.86  5001.4  167.03  5008.4  169.59
  5012.0  169.59  5017.7  171.15  5022.9  170.35  5030.4  171.36  5050.0  171.61
  5081.9  171.07  5184.2  172.35  5287.8  174.59  5314.3  176.05  5473.1  181.41
  5544.1  184.84  5668.7  189.99  5735.8  191.96  5740.9  192.91  5756.8  193.51
#Mann=7,-1,0
  4422.7    0.12       0  4638.1    0.05       0  4922.3    0.12       0
  4994.3    0.05       0  4998.3    0.12       0  5050.0    0.04       0
  5544.1    0.12       0
Bank Sta=4994.3,4998.3
Exp/Cntr=0.3,0.1

Type RM Length L Ch R = 1,3432,354,354,354
BEGIN DESCRIPTION:
LGII3219
END DESCRIPTION:
XS GIS Cut Line= 4
      2540838.17     13532774.94      2541218.33     13533035.33
      2541541.25     13533165.54      2542062.05     13533441.57
#Sta/Elev= 30
  4318.3  186.56  4329.9  185.47  4344.9  186.43  4359.8  185.98  4365.8  184.95
  4395.6  184.31  4473.5  180.44  4488.4  179.98  4496.3  180.80  4524.2  178.12
  4560.1  176.91  4586.2  174.98  4739.5  170.23  4874.9  168.81  4982.3  166.29
  4999.0  162.73  4999.3  162.23  5003.0  162.73  5006.4  163.05  5023.5  169.24
  5100.1  171.03  5241.3  176.26  5269.0  178.30  5351.3  180.95  5448.4  186.34
  5527.6  192.27  5581.9  193.17  5609.6  194.25  5647.9  197.50  5716.7  199.30
#Mann=5,-1,0
  4318.3    0.12       0  4586.2    0.05       0  4999.0    0.05       0
  5003.0    0.05       0  5100.1    0.12       0
Bank Sta=4999,5003
Exp/Cntr=0.3,0.1

Type RM Length L Ch R = 1,3078,529,529,529
BEGIN DESCRIPTION:
LGII3218
END DESCRIPTION:
XS GIS Cut Line= 4
      2540848.54     13532889.49      2541082.92     13533358.25
      2541447.50     13533472.83      2541981.94     13533493.59
#Sta/Elev= 30
  4309.3  180.74  4477.2  173.88  4626.2  169.51  4898.3  167.41  4919.4  167.83
  4929.9  166.74  4950.9  166.65  4961.4  165.46  4974.9  165.88  4982.3  165.02
  5000.5  164.60  5002.0  164.56  5007.3  161.07  5011.8  159.53  5012.0  159.03
  5015.5  159.03  5015.8  159.53  5034.4  165.62  5053.7  165.77  5129.1  167.50
  5142.1  167.12  5223.1  170.57  5303.1  174.88  5327.7  175.54  5399.2  180.14
  5553.3  188.48  5591.0  187.42  5633.4  191.97  5695.6  195.12  5750.4  198.20
#Mann=11,-1,0
  4309.3    0.12       0  4477.2    0.05       0  4626.2    0.12       0
  4898.3    0.05       0  5000.5    0.12       0  5011.8    0.05       0
  5015.8    0.12       0  5053.7    0.05       0  5327.7    0.12       0
  5591.0    0.05       0  5695.6    0.12       0
Bank Sta=5011.8,5015.8
Exp/Cntr=0.3,0.1

Type RM Length L Ch R = 1,2549,933,933,933
BEGIN DESCRIPTION:
LGII3217
END DESCRIPTION:
XS GIS Cut Line= 3
      2540391.59     13533859.28      2540968.38     13533879.17
      2541961.43     13533591.18
#Sta/Elev= 30
  4251.7  182.77  4325.2  179.34  4345.2  179.74  4525.3  174.00  4689.8  170.05
  4780.8  168.08  4805.4  166.52  4981.5  163.72  5006.4  161.32  5010.6  156.68
  5010.9  156.18  5014.9  156.68  5023.1  160.00  5033.6  162.62  5045.2  163.43
  5218.3  164.86  5262.6  167.63  5329.4  168.46  5401.7  170.78  5530.9  176.82
  5541.2  177.93  5554.2  181.17  5564.6  181.23  5574.8  179.62  5670.3  185.33
  5752.0  189.78  5814.5  194.76  5824.9  194.53  5835.8  196.55  5862.8  196.44
#Mann=7,-1,0
  4251.7    0.04       0  4689.8    0.12       0  4780.8    0.04       0
  5010.6    0.04       0  5014.9    0.04       0  5530.9    0.12       0
  5670.3    0.05       0
Bank Sta=5010.6,5014.9
Exp/Cntr=0.3,0.1

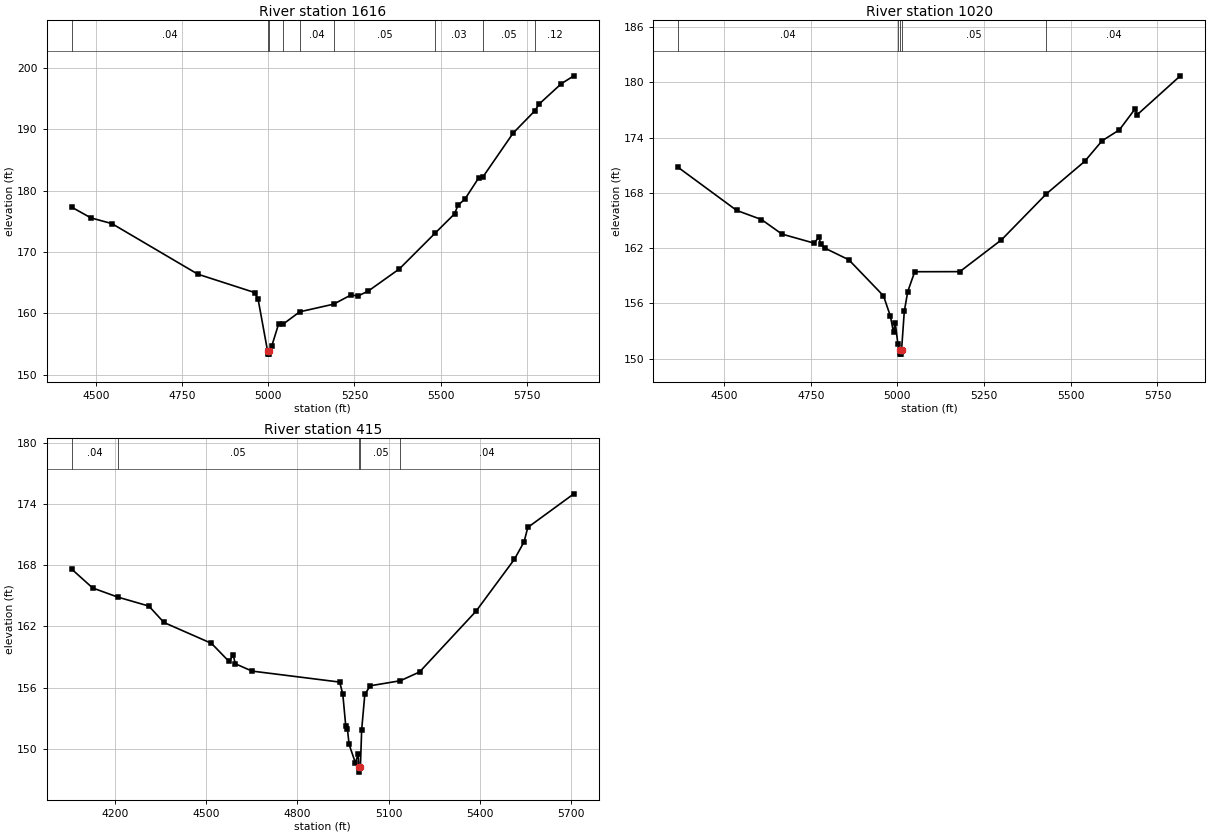
Type RM Length L Ch R = 1,1616,596,596,596
BEGIN DESCRIPTION:
LGII3216
END DESCRIPTION:
XS GIS Cut Line= 3
      2540660.10     13534366.43      2541107.60     13534296.82
      2542110.97     13534267.02
#Sta/Elev= 30
  4430.0  177.29  4485.6  175.55  4546.3  174.62  4795.7  166.37  4960.3  163.38
  4970.3  162.38  4998.1  153.83  4998.4  153.33  5002.2  153.33  5002.5  153.83
  5010.3  154.66  5030.4  158.30  5043.1  158.22  5091.3  160.23  5189.8  161.48
  5240.4  162.99  5260.5  162.81  5290.5  163.63  5380.5  167.23  5485.2  173.12
  5540.6  176.21  5550.6  177.62  5570.6  178.61  5610.6  182.07  5622.9  182.23
  5710.7  189.39  5773.8  193.03  5786.0  194.12  5850.7  197.45  5886.7  198.72
#Mann=9,-1,0
  4430.0    0.04       0  4998.1    0.04       0  5002.5    0.04       0
  5043.1    0.05       0  5091.3    0.04       0  5189.8    0.05       0
  5485.2    0.03       0  5622.9    0.05       0  5773.8    0.12       0
Bank Sta=4998.1,5002.5
Exp/Cntr=0.3,0.1

Type RM Length L Ch R = 1,1020,605,605,605
BEGIN DESCRIPTION:
LGII3215
END DESCRIPTION:
XS GIS Cut Line= 3
      2540868.95     13534575.27      2541207.04     13534813.92
      2542240.58     13534843.73
#Sta/Elev= 30
  4368.0  170.77  4536.5  166.10  4608.0  165.11  4667.0  163.53  4759.3  162.55
  4774.1  163.20  4778.4  162.41  4789.8  162.02  4859.8  160.74  4959.9  156.82
  4979.9  154.60  4988.8  152.84  4993.8  153.85  5001.6  151.55  5007.7  150.99
  5008.0  150.49  5011.8  150.49  5012.1  150.99  5019.9  155.15  5029.9  157.29
  5049.9  159.44  5180.0  159.45  5300.0  162.90  5429.9  167.91  5540.1  171.43
  5590.1  173.66  5640.1  174.85  5685.8  177.15  5690.8  176.47  5815.8  180.72
#Mann=5,-1,0
  4368.0    0.04       0  5001.6    0.05       0  5007.7    0.04       0
  5012.1    0.05       0  5429.9    0.04       0
Bank Sta=5007.7,5012.1
Exp/Cntr=0.3,0.1

Type RM Length L Ch R = 1,415,0,0,0
BEGIN DESCRIPTION:
LGII3214
END DESCRIPTION:
XS GIS Cut Line= 4
      2540859.00     13534794.03      2541236.87     13535251.46
      2541734.08     13535380.74      2542250.62     13535211.87
#Sta/Elev= 30
  4058.0  167.62  4126.5  165.78  4208.5  164.89  4311.5  164.00  4361.0  162.39
  4517.3  160.34  4574.7  158.57  4589.0  159.18  4595.5  158.34  4650.4  157.62
  4938.7  156.54  4949.0  155.35  4958.8  152.19  4964.0  151.98  4969.7  150.42
  4990.4  148.61  4999.3  149.45  5002.3  148.20  5002.6  147.70  5006.8  148.20
  5011.0  151.85  5021.4  155.36  5039.9  156.18  5138.0  156.67  5201.2  157.53
  5387.0  163.50  5513.2  168.60  5544.8  170.30  5557.1  171.72  5708.5  175.02
#Mann=5,-1,0
  4058.0    0.04       0  4208.5    0.05       0  5002.3    0.05       0
  5006.8    0.05       0  5138.0    0.04       0
Bank Sta=5002.3,5006.8
Exp/Cntr=0.3,0.1

Chan Stop Cuts=-1