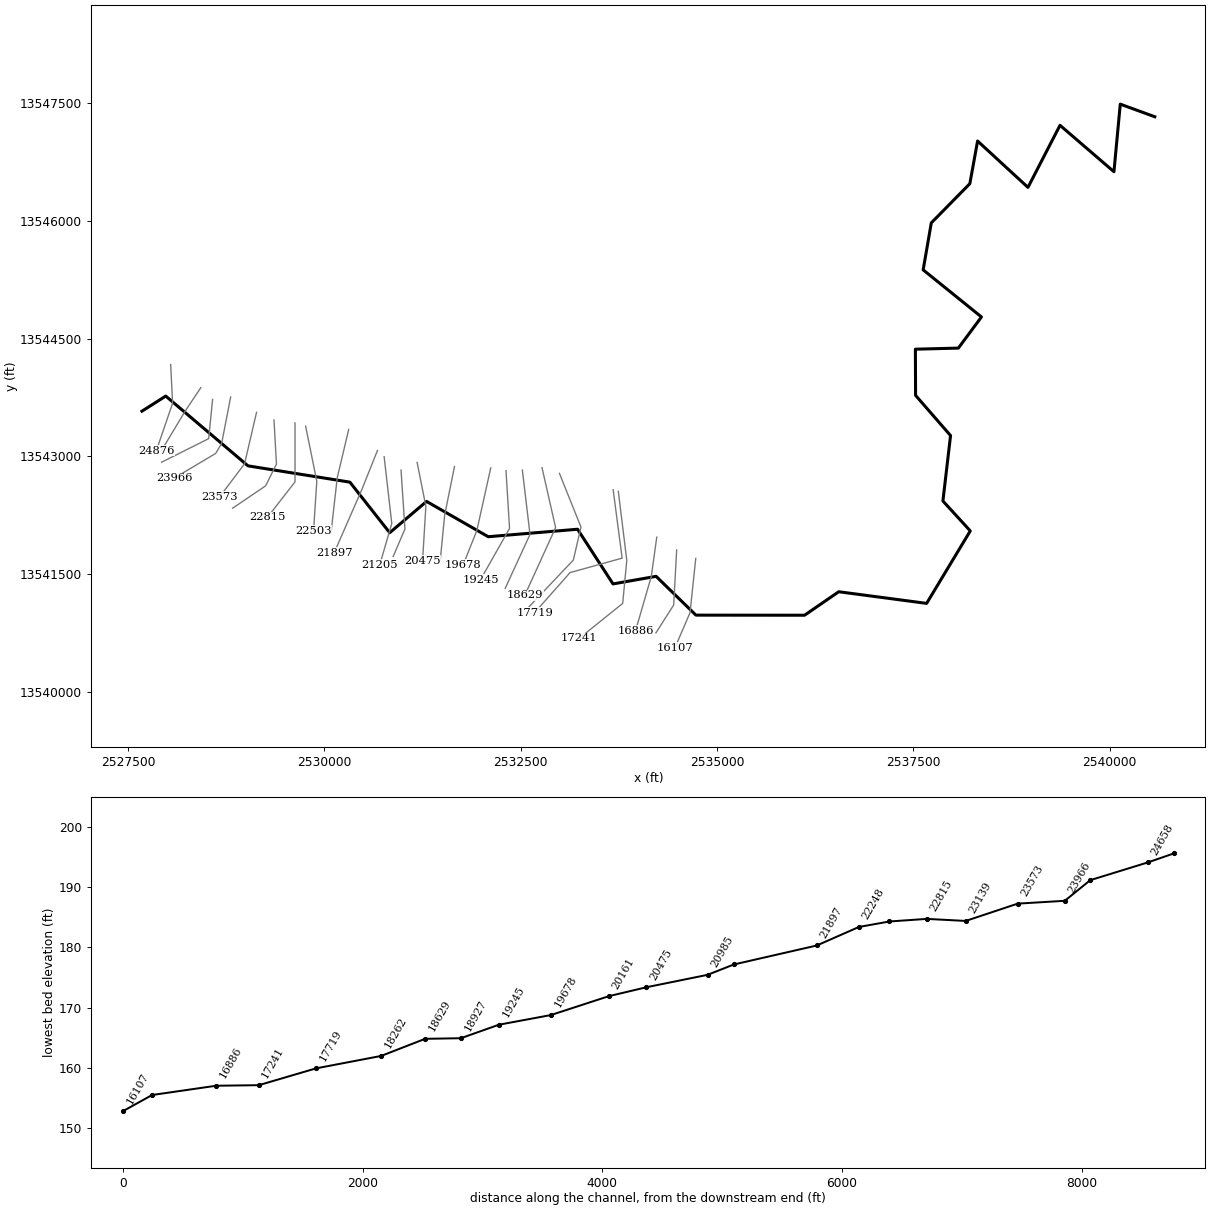
--- TRIB 12 TO GUADALUPE RIVER.prj (project) ---

Proj Title=TRIB 12 TO GUADALUPE RIVER Base Level Engineering
Current Plan=p01
Default Exp/Contr=0.3,0.1
English Units
Geom File=g01
Flow File=f01
Plan File=p01
Y Axis Title=Elevation
X Axis Title(PF)=Main Channel Distance
X Axis Title(XS)=Station
BEGIN DESCRIPTION:
TRIB 12 TO GUADALUPE RIVER
END DESCRIPTION:
DSS Export Rating Curves= 0
DSS Export Rating Curve Sorted= 0
DSS Export Volume Flow Curves= 0
DXF OffsetX= 0
DXF OffsetY= 0
DXF ScaleX= 1
DXF ScaleY= 10

--- TRIB 12 TO GUADALUPE RIVER.p01 (plan) ---

Plan Title=Multiple Run
Program Version=4.10
Short Identifier=Multiple
Geom File=g01
Flow File=f01
Subcritical Flow
K Sum by GR= 0
Std Step Tol= 0.01
Critical Tol= 0.01
Num of Std Step Trials= 20
Max Error Tol= 0.3
Flow Tol Ratio= 0.001
Split Flow NTrial= 30
Split Flow Tol= 0.02
Split Flow Ratio= 0.02
Log Output Level= 0
Friction Slope Method= 1
Unsteady Friction Slope Method= 2
Unsteady Bridges Friction Slope Method= 1
Parabolic Critical Depth
Global Vel Dist= 1 , 1 , 1
Global Log Level= 0
CheckData=True
Encroach Param=-1 ,0,0, 0
BEGIN DESCRIPTION:
Multiple Run
END DESCRIPTION:
Computation Interval=1HOUR
Output Interval=1HOUR
Run HTab= 0
Run UNet= 0
Run PostProcess= 0
Run WQNet= 0
UNET Theta= 1
UNET Theta Warmup= 1
UNET ZTol= 0.02
UNET ZSATol= 0.05
UNET MxIter= 20
UNET MaxInSteps= 0
UNET DtIC= 0
UNET DtMin= 0
UNET MaxCRTS= 20
UNET WFStab= 2
UNET SFStab= 1
UNET WFX= 1
UNET SFX= 1
UNET DSS MLevel= 4
UNET DZMax Abort= 100
UNET Convert EG Bridges= 0
UNET Use Existing IB Tables=-1
UNET Froude Reduction=False
UNET Froude Limit= 1
UNET Froude Power= 10
UNET Time Slicing=0,0, 5
UNET Junction Losses=0
Instantaneous Interval=1HOUR
Write IC File= 0
Write IC File at Sim End=0
Echo Input=False
Echo Parameters=False
Echo Output=False
Write Detailed= 0
WQ AD Non Conservative
WQ ULTIMATE=-1
WQ Max Comp Step=1HOUR
WQ Output Interval=15MIN
WQ Output Selected Increments= 0
WQ Output face flow=0
WQ Output face velocity=0
WQ Output face area=0
WQ Output face dispersion=0
WQ Output cell volume=0
WQ Output cell surface area=0
WQ Output cell continuity=0
WQ Output cumulative cell continuity=0
WQ Output face conc=0
WQ Output face dconc_dx=0
WQ Output face courant=0
WQ Output face peclet=0
WQ Output face adv mass=0
WQ Output face disp mass=0
WQ Output cell mass=0
WQ Output cell source sink temp=0
WQ Output cell source sink nsm=0
WQ Output MaxMinRange=-1
WQ Daily Max Min Mean=-1
WQ Daily Range=0
WQ Daily Time=0
WQ Create Restart=0
WQ Fixed Restart=0
WQ System Summary=0
WQ Use Fixed Temperature=0
Sorting and Armoring Iterations= 10
XS Update Threshold= 0.02
Hydraulics Update Threshold= 0.02
Energy Slope Method= 1
Volume Change Method= 0
XS Weighting Method= 0
Number of US Weighted Cross Sections= 1
Number of DS Weighted Cross Sections= 1
Upstream XS Weight=0.25
Main XS Weight=0.5
Downstream XS Weight=0.25
Number of DS XS's Weighted with US Boundary= 1
Upstream Boundary Weight= 1
Weight of XSs Associated with US Boundary= 0
Number of US XS's Weighted with DS Boundary= 1
Downstream Boundary Weight= 0.5
Weight of XSs Associated with DS Boundary= 0.5
Sediment Output Level= 4
Mass or Volume Output= 0
Output Increment Type= 1
Profile and TS Output Increment= 10
XS Output Flag= 0
XS Output Increment= 10
Disregard all LS=0
Disregard all Conn=0
Disregard all Breaches=0
Disregard all Pumps=0

--- TRIB 12 TO GUADALUPE RIVER.f01 (steady flow) ---

Flow Title=Multiple
Number of Profiles=7
Profile Names=10-year,25-year,50-year,1pct_min,100-year,1pct_plu,500-year
River Rch & RM= TRIB 12 TO GUADA,Reach-1,24876
    1027    1701    2327    1540    3072    6129    5297
River Rch & RM= TRIB 12 TO GUADA,Reach-1,22503
    1280    2142    2950    1964    3919    7820    6843
River Rch & RM= TRIB 12 TO GUADA,Reach-1,21205
    1432    2404    3318    2211    4412    8802    7721
River Rch & RM= TRIB 12 TO GUADA,Reach-1,17241
    1726    2921    4051    2712    5412   10798    9560
River Rch & RM= TRIB 12 TO GUADA,Reach-1,13554
    2116    3608    5030    3381    6746   13460   12016
River Rch & RM= TRIB 12 TO GUADA,Reach-1,7969
    2133    3636    5067    3405    6794   13555   12092
River Rch & RM= TRIB 12 TO GUADA,Reach-1,6362
    2455    4204    5876    3957    7896   15755   14122
Boundary for River Rch & Prof#=TRIB 12 TO GUADA,Reach-1,1
Up Type=0
Dn Type=3
Dn Slope=0.005
Boundary for River Rch & Prof#=TRIB 12 TO GUADA,Reach-1,2
Up Type=0
Dn Type=3
Dn Slope=0.005
Boundary for River Rch & Prof#=TRIB 12 TO GUADA,Reach-1,3
Up Type=0
Dn Type=3
Dn Slope=0.005
Boundary for River Rch & Prof#=TRIB 12 TO GUADA,Reach-1,4
Up Type=0
Dn Type=3
Dn Slope=0.005
Boundary for River Rch & Prof#=TRIB 12 TO GUADA,Reach-1,5
Up Type=0
Dn Type=3
Dn Slope=0.005
Boundary for River Rch & Prof#=TRIB 12 TO GUADA,Reach-1,6
Up Type=0
Dn Type=3
Dn Slope=0.005
Boundary for River Rch & Prof#=TRIB 12 TO GUADA,Reach-1,7
Up Type=0
Dn Type=3
Dn Slope=0.005

--- TRIB 12 TO GUADALUPE RIVER.g01 (geometry) ---

Geom Title=Existing Conditions
Program Version=4.10

River Reach=TRIB 12 TO GUADA,Reach-1
Reach XY= 30
        2527675.       13543575.      2527978.35     13543767.41
       2529026.5     13542878.46      2530323.45     13542671.25
      2530830.67     13542026.97      2531299.99     13542425.59
      2532085.55      13541976.1      2533223.42     13542071.33
        2533675.       13541375.      2534223.75     13541471.55
      2534730.94     13540977.27       2536114.5      13540976.2
      2536549.89     13541275.32      2537669.16     13541127.05
       2538225.3     13542050.12      2537876.58     13542431.05
       2537973.9     13543264.45      2537528.53     13543776.45
      2537526.05     13544364.57       2538073.5     13544378.46
       2538367.5       13544775.        2537625.       13545375.
      2537728.75     13545973.45      2538219.55     13546472.53
      2538318.27     13547015.89      2538959.84     13546425.36
      2539368.06     13547216.17      2540055.06     13546624.73
      2540135.47     13547485.53        2540575.       13547325.

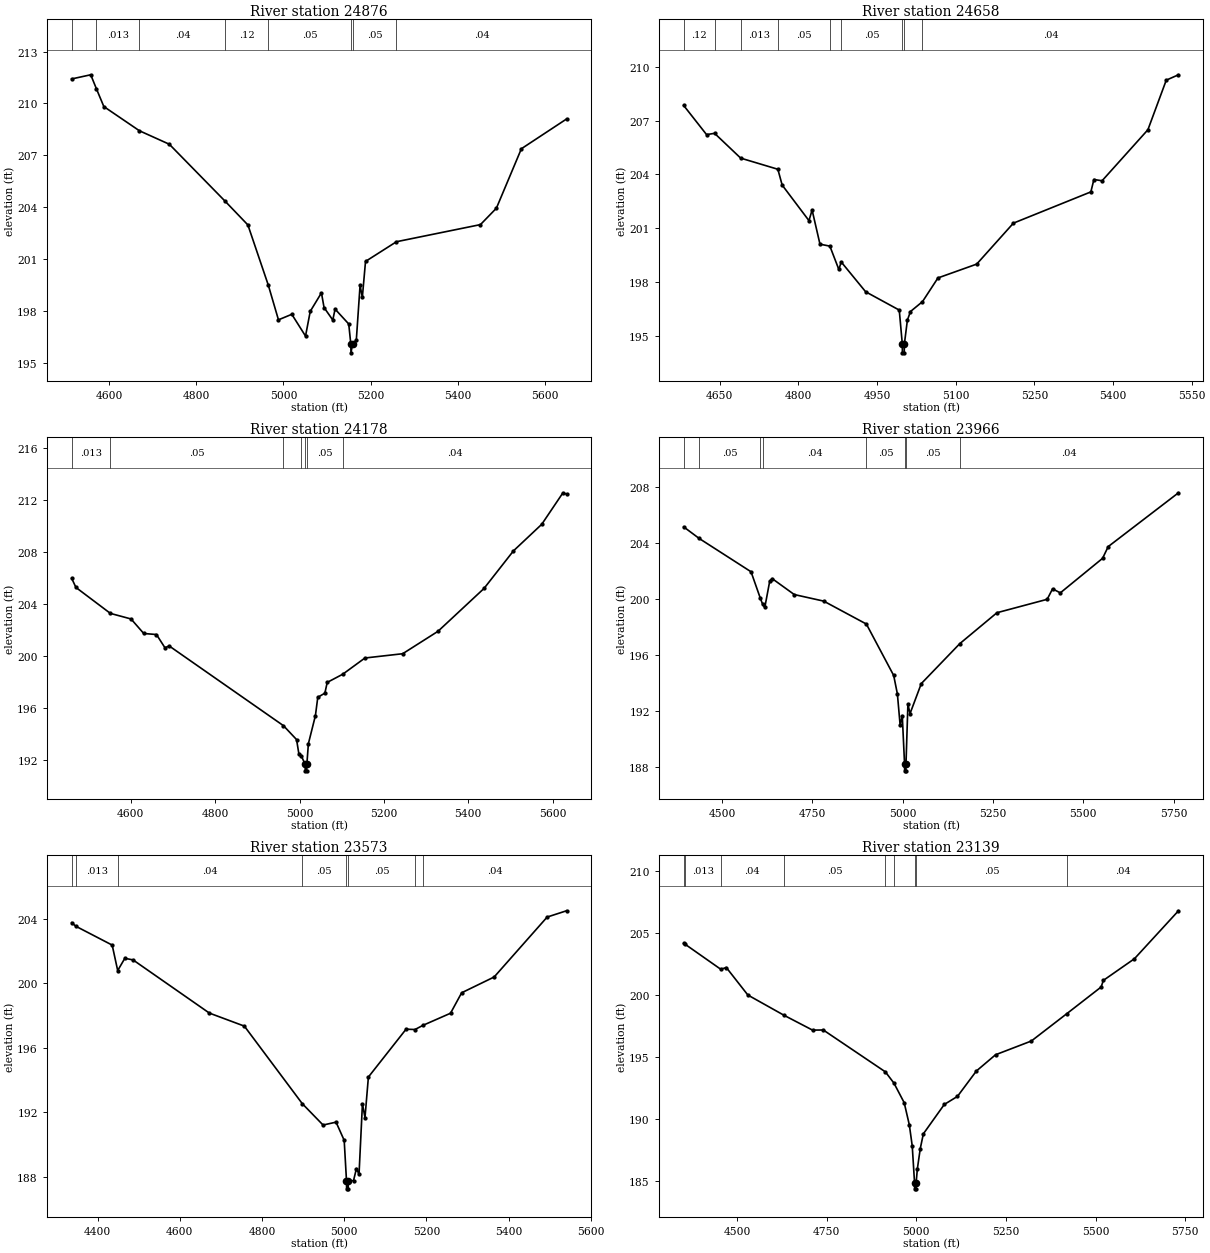
Type RM Length L Ch R = 1 ,24876   ,218,218,218
BEGIN DESCRIPTION:
Mapping XS 301a799c
END DESCRIPTION:
XS GIS Cut Line= 3
      2528041.14     13544168.58      2528065.45      13543675.5
      2527857.48     13543068.94
#Sta/Elev= 30
  4514.4  211.42    4558  211.66  4571.2  210.84  4588.1  209.82  4669.7  208.42
  4738.3  207.64  4866.8  204.33  4918.5  202.97  4965.4  199.48  4988.6  197.48
  5019.2   197.8  5050.7  196.54  5061.5  197.97  5087.2  199.04  5093.2  198.19
  5113.2  197.47  5118.5   198.1  5149.8  197.24  5154.6  196.07  5154.9  195.57
  5158.6  196.07  5167.2  196.31  5175.8  199.48    5181  198.78  5188.3  200.86
  5259.3     202  5451.9  202.99  5488.5  203.94  5545.8  207.38  5649.3   209.1
#Mann= 8 ,-1 , 0
  4514.4     .04       0  4571.2    .013       0  4669.7     .04       0
  4866.8     .12       0  4965.4     .05       0  5154.6     .05       0
  5158.6     .05       0  5259.3     .04       0
Bank Sta=5154.6,5158.6
XS Rating Curve= 0 ,0
Exp/Cntr=0.3,0.1

Type RM Length L Ch R = 1 ,24658   ,480,480,480
BEGIN DESCRIPTION:
TRIB 12 TO GUADALUPE RIVER 50.0
END DESCRIPTION:
XS GIS Cut Line= 3
      2528424.99     13543874.99        2528225.       13543575.
      2527925.02     13543075.03
#Sta/Elev= 30
  4581.3  207.84  4624.9  206.22  4640.2  206.29    4690  204.91  4760.9  204.29
  4769.1  203.41  4820.2  201.43  4826.2  202.02  4841.2  200.12  4860.1  200.01
  4877.2  198.71  4881.7  199.13  4928.3  197.47  4992.4  196.45  4998.2  194.57
  4998.4  194.07  5001.9  194.07  5002.2  194.57  5007.9  195.89  5013.8  196.37
  5036.7  196.92  5066.2  198.24  5140.1  199.01  5210.1  201.29  5357.8  203.03
  5363.6  203.72  5379.2  203.65  5466.6  206.49  5501.6  209.25  5524.9  209.55
#Mann= 9 ,-1 , 0
  4581.3     .12       0  4640.2     .05       0    4690    .013       0
  4760.9     .05       0  4860.1     .12       0  4881.7     .05       0
  4998.2     .05       0  5002.2     .05       0  5036.7     .04       0
Bank Sta=4998.2,5002.2
XS Rating Curve= 0 ,0
Exp/Cntr=0.3,0.1

Type RM Length L Ch R = 1 ,24178   ,212,212,212
BEGIN DESCRIPTION:
TRIB 12 TO GUADALUPE RIVER 49.0
END DESCRIPTION:
XS GIS Cut Line= 3
        2528575.     13543724.98        2528525.       13543225.
        2527925.       13542925.
#Sta/Elev= 30
  4459.8  205.97  4469.8  205.27  4551.5  203.27  4600.5  202.84  4630.6  201.72
  4660.8  201.64  4680.9  200.62  4690.9  200.76    4962  194.61    4993  193.54
  4998.6  192.41  5003.8  192.31  5013.4  191.63  5013.6  191.13  5017.1  191.13
  5017.4  191.63    5021  193.22  5037.7  195.39  5043.3   196.8  5060.1  197.12
  5065.7  197.95  5102.5  198.58  5155.1  199.83  5244.6  200.16  5328.4  201.89
  5437.4  205.19  5507.3  208.09  5574.4  210.14  5624.7  212.57  5633.1  212.47
#Mann= 7 ,-1 , 0
  4459.8    .013       0  4551.5     .05       0    4962     .04       0
  5003.8     .05       0  5013.4     .04       0  5017.4     .05       0
  5102.5     .04       0
Bank Sta=5013.4,5017.4
XS Rating Curve= 0 ,0
Exp/Cntr=0.3,0.1

Type RM Length L Ch R = 1 ,23966   ,393,393,393
BEGIN DESCRIPTION:
Mapping XS 03f1bc74
END DESCRIPTION:
XS GIS Cut Line= 4
      2528805.02     13543755.33      2528690.45     13543165.08
      2528614.06     13543036.61      2528082.84     13542720.66
#Sta/Elev= 30
  4394.3  205.16  4437.3  204.33  4580.6  201.95    4606  200.08  4612.9  199.61
  4618.7   199.4  4632.3  201.28  4639.1  201.46  4700.2  200.32  4781.7  199.85
  4899.7  198.21  4975.3  194.53  4985.5  193.21  4993.1  190.97    4999  191.66
  5005.3  188.21  5005.5  187.71    5009  187.71  5009.3  188.21  5014.6   192.5
  5020.4   191.8  5051.6  193.95  5158.2  196.81  5260.9  199.02  5399.9  199.98
  5414.8  200.73  5436.2  200.44  5553.1  202.91  5568.7  203.75  5763.1   207.6
#Mann= 8 ,-1 , 0
  4394.3     .12       0  4437.3     .05       0    4606    .013       0
  4612.9     .04       0  4899.7     .05       0  5005.3     .05       0
  5009.3     .05       0  5158.2     .04       0
Bank Sta=5005.3,5009.3
XS Rating Curve= 0 ,0
Exp/Cntr=0.3,0.1

Type RM Length L Ch R = 1 ,23573   ,434,434,434
BEGIN DESCRIPTION:
Mapping XS 54fdf783
END DESCRIPTION:
XS GIS Cut Line= 3
      2529134.88     13543560.89      2528982.11     13542904.67
      2528662.69     13542481.08
#Sta/Elev= 30
  4336.8  203.76  4346.8  203.54  4435.3  202.37  4448.7  200.79  4466.1  201.55
  4486.1  201.45  4671.8  198.15    4757  197.34  4897.9  192.53  4948.6   191.2
  4980.2  191.38    5000  190.25  5005.6  187.74  5005.9  187.24  5009.7  187.24
  5010.1  187.74  5022.7  187.75  5029.8   188.5  5036.1  188.14  5044.4  192.52
  5050.6  191.66  5058.9  194.18  5150.6  197.15  5172.4  197.13  5191.8  197.39
  5258.8  198.14  5285.9  199.41    5365  200.39    5494  204.11  5541.1   204.5
#Mann= 8 ,-1 , 0
  4336.8     .05       0  4346.8    .013       0  4448.7     .04       0
  4897.9     .05       0  5005.6     .05       0  5010.1     .05       0
  5172.4     .03       0  5191.8     .04       0
Bank Sta=5005.6,5010.1
XS Rating Curve= 0 ,0
Exp/Cntr=0.3,0.1

Type RM Length L Ch R = 1 ,23139   ,324,324,324
BEGIN DESCRIPTION:
Mapping XS bb4cbfce
END DESCRIPTION:
XS GIS Cut Line= 4
      2529357.11     13543463.72      2529388.36      13542901.2
      2529249.47     13542623.42      2528830.65     13542339.59
#Sta/Elev= 30
  4351.3  204.17  4356.2  204.09  4454.7  202.09  4470.2  202.23  4530.3  200.01
  4630.9  198.38  4710.6  197.18  4740.6  197.19  4913.8  193.81  4937.7   192.9
  4966.3  191.32  4980.6  189.53  4988.7  187.83  4995.1  184.87  4995.4  184.37
  4999.3  184.37  4999.6  184.87    5003  185.99  5011.1  187.62  5019.7  188.81
  5078.1  191.18  5114.8  191.83  5167.6  193.88    5221  195.19  5320.9   196.3
  5419.5   198.5  5515.6  200.66  5521.6  201.19  5608.4  202.94  5731.2  206.81
#Mann= 9 ,-1 , 0
  4351.3     .04       0  4356.2    .013       0  4454.7     .04       0
  4630.9     .05       0  4913.8     .04       0  4937.7     .05       0
  4995.1     .05       0  4999.6     .05       0  5419.5     .04       0
Bank Sta=4995.1,4999.6
XS Rating Curve= 0 ,0
Exp/Cntr=0.3,0.1

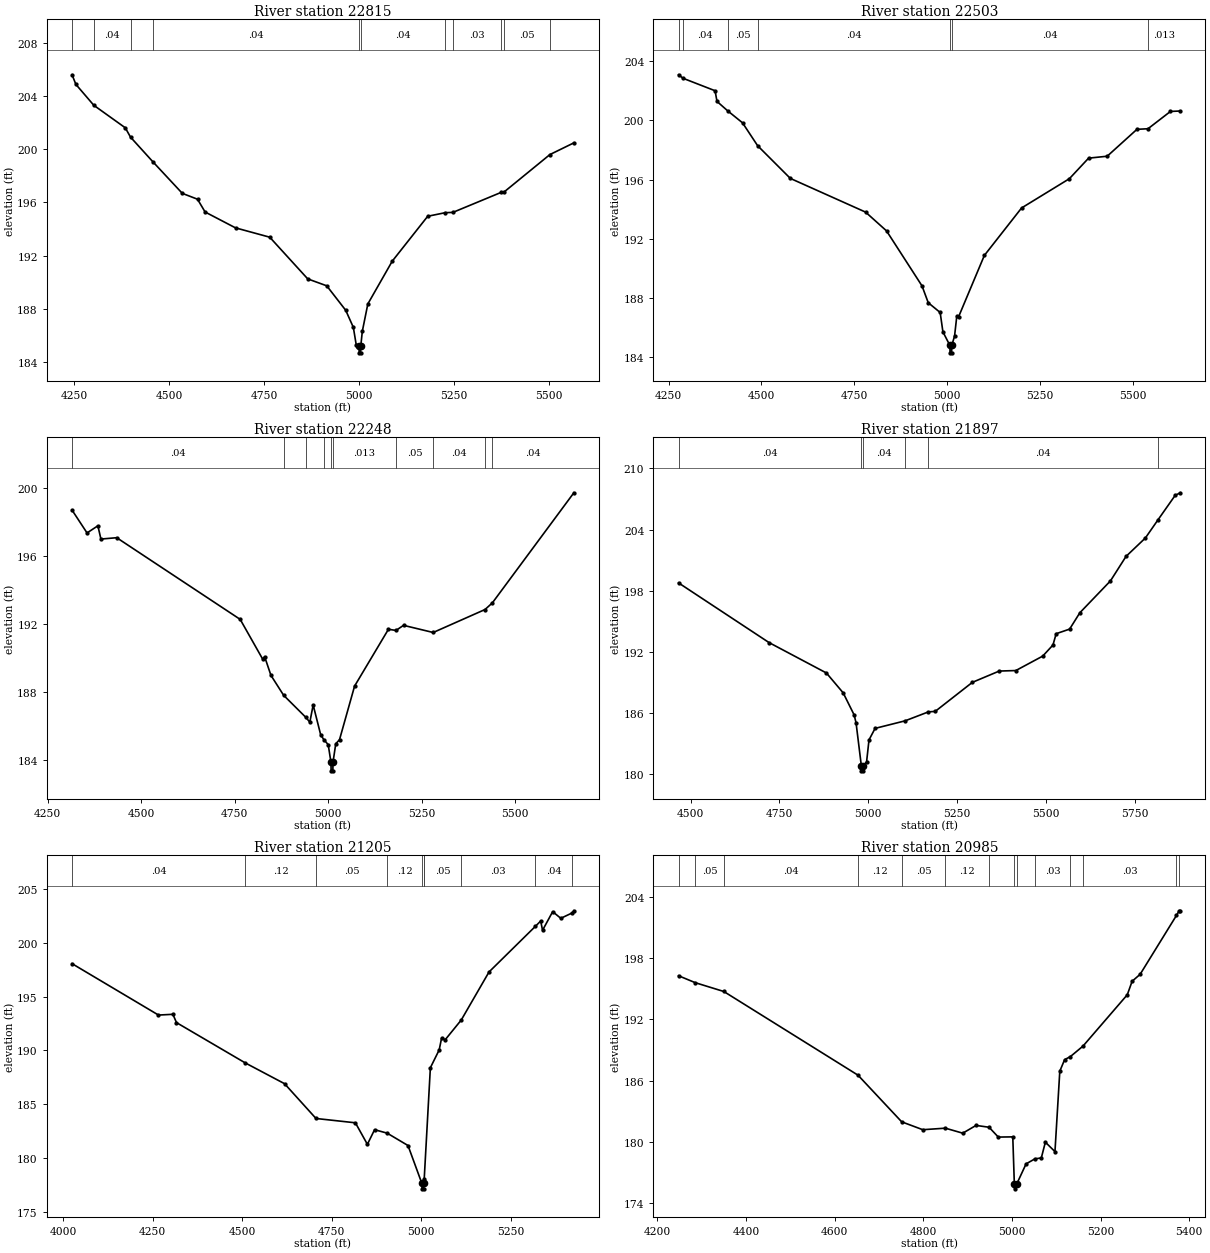
Type RM Length L Ch R = 1 ,22815   ,312,312,312
BEGIN DESCRIPTION:
TRIB 12 TO GUADALUPE RIVER 46.0
END DESCRIPTION:
XS GIS Cut Line= 3
        2529625.     13543425.05        2529625.       13542675.
      2529275.02     13542225.03
#Sta/Elev= 30
  4245.1  205.58  4255.1  204.86  4302.3  203.29  4385.1   201.6  4398.9   200.9
  4457.7  199.05  4535.1  196.68  4575.1  196.24  4595.1  195.28  4675.1  194.09
  4765.1  193.39  4865.1  190.26  4915.1  189.74  4965.1   187.9  4985.1  186.62
  4992.6  185.32  5000.1  185.21  5000.4  184.71  5004.3  184.71  5004.6  185.21
  5008.7  186.33  5023.2  188.38  5087.4  191.59  5180.7  194.96    5227  195.23
  5246.8  195.25  5374.5  196.76  5381.5  196.78  5502.1  199.59  5565.2  200.47
#Mann= 11 ,-1 , 0
  4245.1    .013       0  4302.3     .04       0  4398.9     .05       0
  4457.7     .04       0  5000.1     .04       0  5004.6     .04       0
    5227     .05       0  5246.8     .03       0  5374.5     .04       0
  5381.5     .05       0  5502.1     .04       0
Bank Sta=5000.1,5004.6
XS Rating Curve= 0 ,0
Exp/Cntr=0.3,0.1

Type RM Length L Ch R = 1 ,22503   ,255,255,255
BEGIN DESCRIPTION:
Mapping XS 6be8ed8c
END DESCRIPTION:
XS GIS Cut Line= 3
      2529759.89     13543383.83      2529902.25     13542682.45
      2529860.68     13542048.49
#Sta/Elev= 30
  4276.9  203.09  4289.3  202.85  4375.3  202.01  4380.4  201.29  4408.8  200.66
  4449.2  199.84  4489.9  198.29  4577.9  196.08  4780.5   193.8  4836.9  192.53
  4932.4  188.81  4949.2  187.67  4981.3  187.01  4988.7   185.7  5007.5  184.78
  5007.9  184.28  5012.2  184.28  5012.6  184.78  5020.1  185.42  5026.1  186.77
  5031.1  186.73  5100.3  190.87  5200.5  194.08  5329.2  196.06  5380.9  197.45
    5431  197.58  5511.1   199.4  5540.9  199.44  5601.3  200.61  5627.9  200.64
#Mann= 7 ,-1 , 0
  4276.9     .05       0  4289.3     .04       0  4408.8     .05       0
  4489.9     .04       0  5007.5     .04       0  5012.6     .04       0
  5540.9    .013       0
Bank Sta=5007.5,5012.6
XS Rating Curve= 0 ,0
Exp/Cntr=0.3,0.1

Type RM Length L Ch R = 1 ,22248   ,351,351,351
BEGIN DESCRIPTION:
Mapping XS e8e1d79a
END DESCRIPTION:
XS GIS Cut Line= 3
      2530308.49     13543342.12      2530162.67     13542727.58
       2530082.8      13542022.7
#Sta/Elev= 30
  4315.5  198.69  4355.5  197.35  4384.5  197.77  4392.6  196.99  4434.8  197.07
  4764.8  192.27    4825  189.93  4830.1  190.08    4847  188.98  4880.9  187.81
  4940.3  186.51  4950.9  186.23  4959.8  187.24  4979.9  185.49  4988.1  185.21
    5000  184.91  5007.4  183.87  5007.8  183.37  5012.4  183.37  5012.8  183.87
  5020.2  184.96  5030.2   185.2  5070.5  188.35    5161  191.69  5181.1  191.62
  5201.3  191.92  5280.6   191.5  5419.1  192.85  5438.7  193.24  5656.5  199.71
#Mann= 10 ,-1 , 0
  4315.5     .04       0  4880.9    .013       0  4940.3     .04       0
  4988.1    .013       0  5007.4     .03       0  5012.8    .013       0
  5181.1     .05       0  5280.6     .04       0  5419.1     .05       0
  5438.7     .04       0
Bank Sta=5007.4,5012.8
XS Rating Curve= 0 ,0
Exp/Cntr=0.3,0.1

Type RM Length L Ch R = 1 ,21897   ,692,692,692
BEGIN DESCRIPTION:
TRIB 12 TO GUADALUPE RIVER 44.0
END DESCRIPTION:
XS GIS Cut Line= 3
      2530675.02     13543075.04        2530475.       13542575.
      2530124.99     13541774.98
#Sta/Elev= 30
    4466  198.76  4720.5   192.9  4882.1  189.91  4929.2  187.96  4960.1  185.79
  4965.5  185.01  4980.3   180.8  4980.7   180.3  4985.3   180.3  4985.8   180.8
  4995.1  181.19  5001.9  183.34    5019  184.47  5103.3  185.21    5169  186.09
  5188.2  186.14  5292.6  188.99  5368.3   190.1    5415  190.15  5490.7  191.57
  5519.5  192.66  5528.5  193.77  5566.3  194.22  5595.2  195.83  5681.3  198.96
    5725  201.36  5779.5  203.17  5814.7  204.94  5863.4  207.36  5877.8  207.61
#Mann= 6 ,-1 , 0
    4466     .04       0  4980.3     .04       0  4985.8     .04       0
  5103.3     .05       0    5169     .04       0  5814.7     .05       0
Bank Sta=4980.3,4985.8
XS Rating Curve= 0 ,0
Exp/Cntr=0.3,0.1

Type RM Length L Ch R = 1 ,21205   ,220,220,220
BEGIN DESCRIPTION:
Mapping XS ec042734
END DESCRIPTION:
XS GIS Cut Line= 3
      2530759.89     13542994.96      2530857.11     13542144.25
      2530704.35       13541620.
#Sta/Elev= 30
  4024.4  198.05  4265.9  193.28  4306.2  193.35  4316.2  192.58  4508.3  188.84
  4618.2  186.91  4706.1  183.68  4816.2  183.28  4849.7  181.28  4869.8  182.64
  4904.9  182.32  4963.2  181.17    5002  177.65  5002.5  177.15  5007.2  177.15
  5007.7  177.65  5008.5  178.06  5025.7  188.39  5050.4  190.05  5056.9  191.12
  5067.4     191    5112  192.82  5189.6  197.28    5319  201.51    5334  202.01
  5339.2  201.15  5367.5  202.88  5390.2  202.26  5422.5  202.77  5426.7  202.96
#Mann= 10 ,-1 , 0
  4024.4     .04       0  4508.3     .12       0  4706.1     .05       0
  4904.9     .12       0    5002     .05       0  5007.7     .12       0
  5008.5     .05       0    5112     .03       0    5319     .04       0
  5422.5     .05       0
Bank Sta=5002,5007.7
XS Rating Curve= 0 ,0
Exp/Cntr=0.3,0.1

Type RM Length L Ch R = 1 ,20985   ,510,510,510
BEGIN DESCRIPTION:
TRIB 12 TO GUADALUPE RIVER 42.0
END DESCRIPTION:
XS GIS Cut Line= 3
        2530975.     13542824.96        2531025.       13542075.
        2530875.     13541725.01
#Sta/Elev= 30
  4247.7  196.26  4285.5  195.58  4349.9  194.72  4652.7  186.54  4751.3  181.98
  4798.9  181.21  4849.9  181.36  4889.1  180.87  4919.1  181.63  4948.5  181.45
  4969.3  180.49    5002  180.51  5005.5  175.93    5006  175.43  5011.2  175.93
    5032  177.87  5051.9  178.36  5066.4  178.45  5075.5  179.99  5097.2  179.07
  5108.1  186.93    5119  188.06  5131.8  188.35  5160.4  189.38  5260.4   194.4
  5271.3  195.72  5289.4   196.4  5371.3  202.15  5377.5  202.61  5380.1  202.61
#Mann= 14 ,-1 , 0
  4247.7     .04       0  4285.5     .05       0  4349.9     .04       0
  4652.7     .12       0  4751.3     .05       0  4849.9     .12       0
  4948.5     .05       0  5005.5     .05       0  5011.2     .05       0
  5051.9     .03       0  5131.8     .05       0  5160.4     .03       0
  5371.3     .04       0  5377.5     .05       0
Bank Sta=5005.5,5011.2
XS Rating Curve= 0 ,0
Exp/Cntr=0.3,0.1

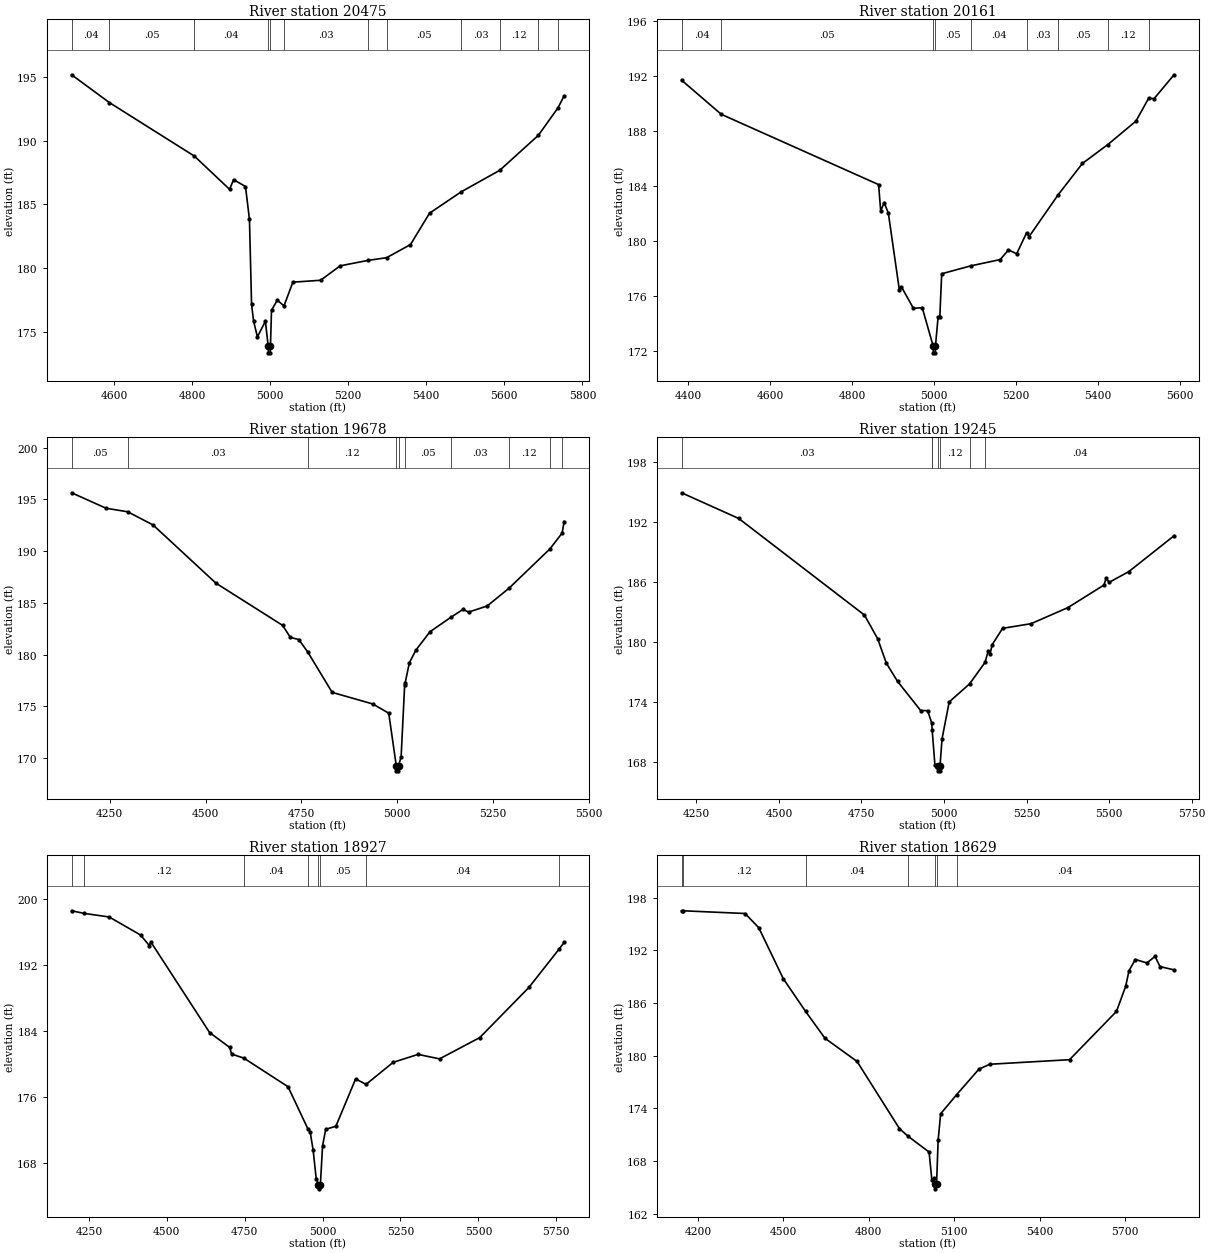
Type RM Length L Ch R = 1 ,20475   ,314,314,314
BEGIN DESCRIPTION:
Mapping XS 5abf877f
END DESCRIPTION:
XS GIS Cut Line= 3
      2531180.03     13542922.04      2531291.14       13542363.
      2531249.47     13541672.03
#Sta/Elev= 30
    4491  195.17  4587.9  192.99  4805.8  188.79  4895.8  186.19  4906.2  186.95
  4936.6  186.41  4946.8  183.84  4952.2  177.17  4957.3  175.87  4967.2  174.62
  4987.6  175.85  4994.9  173.87  4995.4  173.37  5000.2  173.37  5000.6  173.87
  5003.3  176.71  5018.2   177.5  5035.3  177.05  5058.1  178.91  5129.1  179.06
  5179.2  180.19  5250.9  180.62  5298.4  180.83  5359.5  181.86  5408.4  184.32
  5489.3  185.99  5588.2  187.68  5687.1  190.42  5737.1  192.56  5753.2  193.51
#Mann= 12 ,-1 , 0
    4491     .04       0  4587.9     .05       0  4805.8     .04       0
  4994.9     .04       0  5000.6     .04       0  5035.3     .03       0
  5250.9     .04       0  5298.4     .05       0  5489.3     .03       0
  5588.2     .12       0  5687.1     .04       0  5737.1     .12       0
Bank Sta=4994.9,5000.6
XS Rating Curve= 0 ,0
Exp/Cntr=0.3,0.1

Type RM Length L Ch R = 1 ,20161   ,483,483,483
BEGIN DESCRIPTION:
Mapping XS 2ff11819
END DESCRIPTION:
XS GIS Cut Line= 3
      2531655.73     13542869.95      2531530.72     13542251.89
      2531475.17     13541682.47
#Sta/Elev= 30
    4384  191.68  4481.1   189.2  4865.2   184.1  4870.3  182.18  4878.8  182.79
    4889  182.03  4915.9  176.45    4921  176.68  4950.2  175.12  4971.7  175.17
  4998.4  172.39  4998.8  171.89  5003.6  171.89  5004.1  172.39  5010.4  174.46
  5014.6  174.46  5019.3  177.63  5090.1   178.2  5162.2  178.66  5182.3  179.36
  5202.4  179.08  5226.6   180.6  5232.8  180.33  5304.1  183.38  5363.1  185.64
  5425.2  187.01  5493.7  188.71  5524.5  190.36    5538  190.34  5586.7  192.07
#Mann= 9 ,-1 , 0
    4384     .04       0  4481.1     .05       0  4998.4     .05       0
  5004.1     .05       0  5090.1     .04       0  5226.6     .03       0
  5304.1     .05       0  5425.2     .12       0  5524.5     .04       0
Bank Sta=4998.4,5004.1
XS Rating Curve= 0 ,0
Exp/Cntr=0.3,0.1

Type RM Length L Ch R = 1 ,19678   ,433,433,433
BEGIN DESCRIPTION:
Mapping XS aa3c6480
END DESCRIPTION:
XS GIS Cut Line= 3
      2532117.53     13542852.56      2531940.45     13542053.97
      2531766.85     13541619.99
#Sta/Elev= 30
  4150.5  195.63  4240.2  194.14  4297.1  193.79  4363.1  192.52    4527   186.9
  4701.1  182.82  4721.6  181.65  4743.4  181.45  4766.3  180.27  4830.6  176.34
  4936.7  175.22  4978.2  174.33  4997.8  169.26  4998.3  168.76  5003.3  168.76
  5003.8  169.26  5010.5  170.11  5019.7  177.03    5021  177.25    5032   179.2
  5049.3  180.44  5085.9   182.2    5140  183.59    5172  184.36  5186.6   184.1
  5235.1  184.69  5291.6  186.39    5399  190.21  5430.8  191.74  5435.9  192.85
#Mann= 10 ,-1 , 0
  4150.5     .05       0  4297.1     .03       0  4766.3     .12       0
  4997.8     .05       0  5003.8     .12       0    5021     .05       0
    5140     .03       0  5291.6     .12       0    5399     .04       0
  5430.8     .12       0
Bank Sta=4997.8,5003.8
XS Rating Curve= 0 ,0
Exp/Cntr=0.3,0.1

Type RM Length L Ch R = 1 ,19245   ,318,318,318
BEGIN DESCRIPTION:
Mapping XS a1c70005
END DESCRIPTION:
XS GIS Cut Line= 3
      2532311.98     13542817.85      2532357.11     13542081.75
      2531985.58      13541425.5
#Sta/Elev= 30
  4205.1  194.97  4378.3   192.4    4759  182.74  4799.1  180.37  4825.2  177.94
  4859.2  176.11  4929.3  173.19  4950.3  173.18  4962.4  171.99  4964.2  171.23
  4972.4  167.76  4981.8  167.66  4982.3  167.16  4987.4  167.16  4987.9  167.66
  4994.1  170.38  5015.7  174.05  5077.5  175.86  5124.3  178.01  5134.1  179.17
  5139.8  178.89  5145.7  179.77  5177.4  181.41  5263.9  181.88  5375.5  183.49
  5484.7  185.75  5490.5   186.4  5500.6  186.02  5559.4  187.08  5696.7  190.67
#Mann= 7 ,-1 , 0
  4205.1     .03       0  4962.4     .05       0  4964.2     .12       0
  4981.8     .05       0  4987.9     .12       0  5077.5     .05       0
  5124.3     .04       0
Bank Sta=4981.8,4987.9
XS Rating Curve= 0 ,0
Exp/Cntr=0.3,0.1

Type RM Length L Ch R = 1 ,18927   ,298,298,298
BEGIN DESCRIPTION:
Mapping XS 305a9974
END DESCRIPTION:
XS GIS Cut Line= 3
      2532520.31     13542824.78      2532617.53     13542005.36
      2532302.06     13541318.95
#Sta/Elev= 30
  4194.5  198.55  4235.3  198.23  4315.1   197.8  4415.8  195.62  4443.7  194.35
  4448.8  194.78  4637.4  183.82    4702  182.02  4707.9  181.22  4747.2  180.73
  4889.1  177.27  4952.7  172.18  4960.2   171.8  4969.7  169.58  4979.7  166.08
  4986.7  165.42  4987.2  164.92  4992.9  165.42  4999.9  170.13    5010  172.12
  5042.6  172.49  5106.1  178.22  5139.4  177.55  5226.5  180.22  5306.4  181.18
  5375.3  180.64  5504.3  183.21  5662.1  189.28  5759.7  193.95  5775.1  194.72
#Mann= 8 ,-1 , 0
  4194.5     .04       0  4235.3     .12       0  4747.2     .04       0
  4952.7     .05       0  4986.7     .05       0  4992.9     .05       0
  5139.4     .04       0  5759.7     .05       0
Bank Sta=4986.7,4992.9
XS Rating Curve= 0 ,0
Exp/Cntr=0.3,0.1

Type RM Length L Ch R = 1 ,18629   ,367,367,367
BEGIN DESCRIPTION:
Mapping XS 4d6509ec
END DESCRIPTION:
XS GIS Cut Line= 3
      2532770.31     13542856.05      2532943.92     13542092.17
      2532551.54     13541231.01
#Sta/Elev= 30
  4142.8  196.48  4146.8  196.49  4365.7  196.18  4413.9  194.57    4500  188.76
  4578.2  185.04  4646.4  181.97  4759.2  179.33  4908.2  171.67  4938.3  170.81
  5012.2  169.01    5022  165.81  5029.8  166.09  5032.2  165.32  5032.7  164.82
  5038.4  165.32  5043.9  170.35  5052.8  173.37  5108.5  175.53  5186.8  178.44
  5225.1  179.01  5505.5  179.53  5670.3  185.03  5702.6  187.89  5714.3  189.67
  5736.6  190.94  5777.2  190.55  5805.8  191.29  5823.3  190.13  5872.5  189.76
#Mann= 7 ,-1 , 0
  4142.8     .04       0  4146.8     .12       0  4578.2     .04       0
  4938.3     .05       0  5032.2     .05       0  5038.4     .05       0
  5108.5     .04       0
Bank Sta=5032.2,5038.4
XS Rating Curve= 0 ,0
Exp/Cntr=0.3,0.1

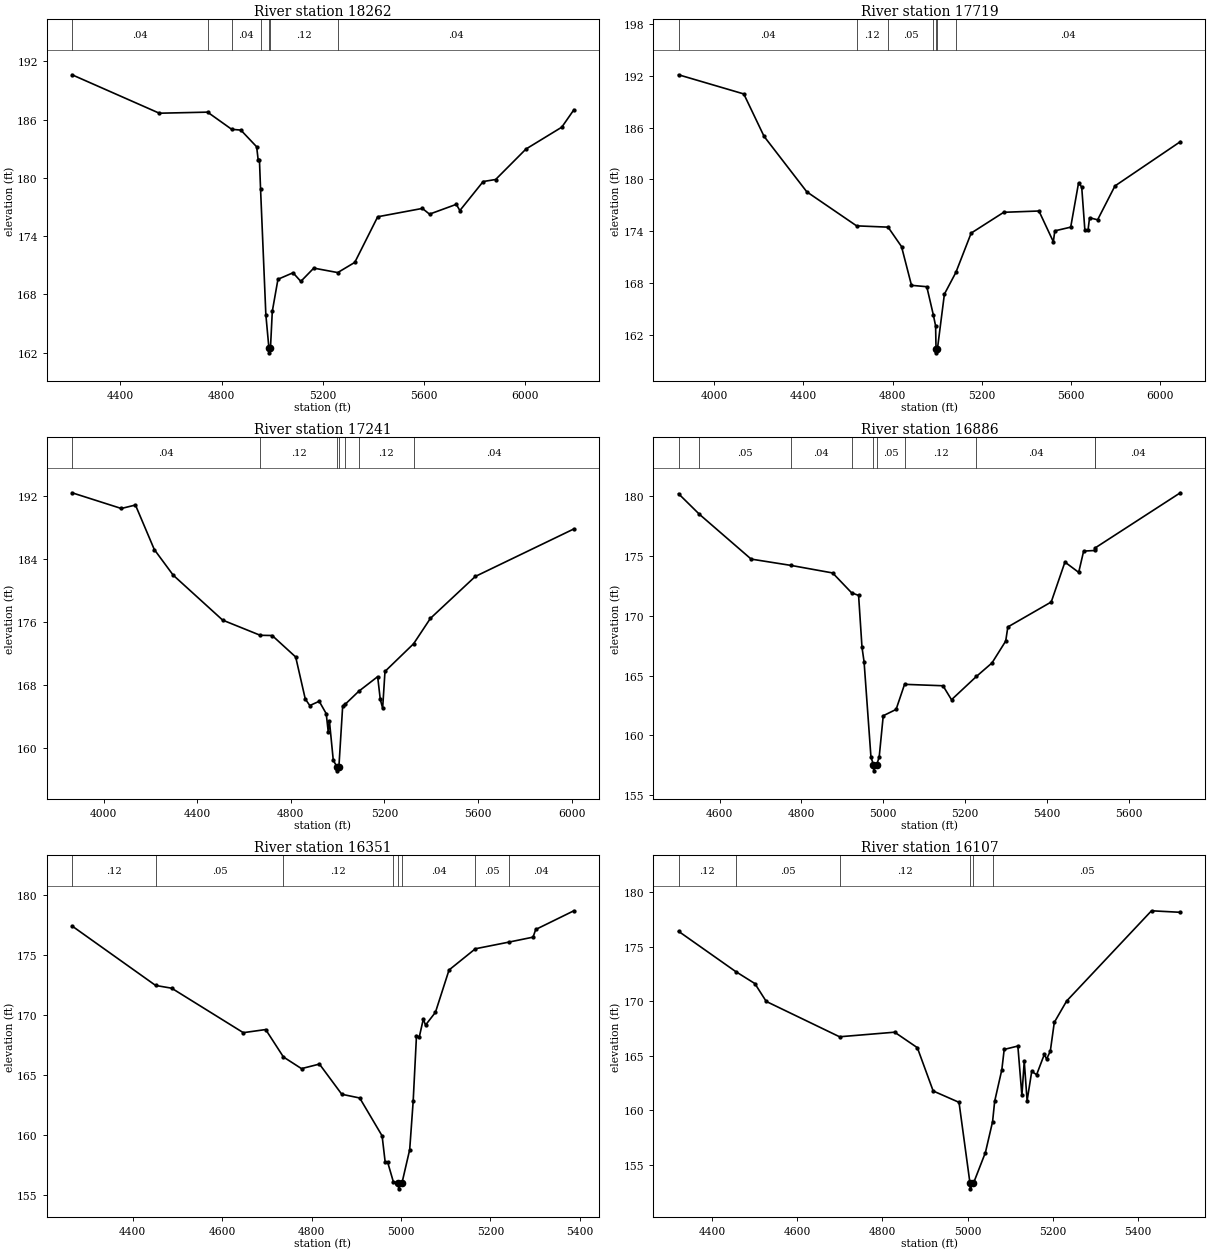
Type RM Length L Ch R = 1 ,18262   ,543,543,543
BEGIN DESCRIPTION:
Mapping XS cb184f4f
END DESCRIPTION:
XS GIS Cut Line= 4
      2532992.54     13542783.11      2533266.84     13542099.11
      2533169.61     13541678.97       2532607.1     13541085.21
#Sta/Elev= 30
  4208.4  190.63  4553.7  186.67  4744.7  186.78  4840.2  185.01  4876.5  184.93
    4939  183.21  4944.9  181.88    4950  181.88  4954.4  178.89  4975.4   165.9
  4987.5  162.48    4988  161.98  4993.7  162.48  5000.9  166.25  5023.3  169.56
    5083  170.23  5113.8  169.34  5165.1  170.71  5259.9  170.25  5327.4   171.3
  5418.1     176  5594.9  176.86  5623.2  176.27  5729.2  177.28  5743.3  176.64
  5835.5  179.63  5884.9  179.84    6005  182.98  6146.6  185.23  6194.5  187.02
#Mann= 7 ,-1 , 0
  4208.4     .04       0  4744.7     .05       0  4840.2     .04       0
  4954.4     .12       0  4987.5     .05       0  4993.7     .12       0
  5259.9     .04       0
Bank Sta=4987.5,4993.7
XS Rating Curve= 0 ,0
Exp/Cntr=0.3,0.1

Type RM Length L Ch R = 1 ,17719   ,478,478,478
BEGIN DESCRIPTION:
Mapping XS b8a99e8a
END DESCRIPTION:
XS GIS Cut Line= 4
      2533676.56     13542574.81      2533791.14     13541703.28
      2533127.95     13541519.25      2532677.07     13541009.41
#Sta/Elev= 30
  3841.1  192.13  4133.4  189.91  4224.2     185  4415.8  178.57  4638.8  174.63
  4779.8  174.48    4840  172.23  4884.7  167.74  4953.2  167.58  4982.3  164.34
  4992.7  163.04  4994.6  160.42  4995.1  159.92  5001.1  160.42  5032.1  166.72
  5083.6  169.24    5152  173.79  5297.9   176.2  5455.7  176.35  5520.1  172.79
  5526.8  174.05  5597.9  174.48    5633  179.59  5647.2  179.13  5661.5   174.1
  5675.7  174.18  5682.4  175.57  5718.4  175.33  5796.1  179.25    6089  184.38
#Mann= 7 ,-1 , 0
  3841.1     .04       0  4638.8     .12       0  4779.8     .05       0
  4982.3     .12       0  4994.6     .05       0  5001.1     .12       0
  5083.6     .04       0
Bank Sta=4994.6,5001.1
XS Rating Curve= 0 ,0
Exp/Cntr=0.3,0.1

Type RM Length L Ch R = 1 ,17241   ,355,355,355
BEGIN DESCRIPTION:
Mapping XS 177d0e36
END DESCRIPTION:
XS GIS Cut Line= 4
      2533742.53     13542553.93      2533850.17      13541675.5
      2533798.09     13541126.89      2533246.03     13540682.46
#Sta/Elev= 30
    3865  192.35  4075.5  190.36  4135.9   190.8  4216.5  185.16  4297.1  181.92
  4508.7  176.22  4669.2   174.3  4720.3  174.27  4820.8  171.55  4861.8  166.23
  4881.1   165.4  4921.3  165.94  4951.4  164.37  4959.9  162.07  4964.9  163.47
  4981.5  158.46  4997.7  157.63  4998.2  157.13  5005.5  157.63  5021.7  165.35
  5033.7   165.6  5090.5  167.21  5171.2  169.06  5182.4  166.17  5192.5  165.07
  5202.5  169.72  5324.9  173.23  5396.6  176.44  5588.5  181.75  6009.8  187.77
#Mann= 7 ,-1 , 0
    3865     .04       0  4669.2     .12       0  4997.7     .05       0
  5005.5     .12       0  5033.7     .05       0  5090.5     .12       0
  5324.9     .04       0
Bank Sta=4997.7,5005.5
XS Rating Curve= 0 ,0
Exp/Cntr=0.3,0.1

Type RM Length L Ch R = 1 ,16886   ,535,535,535
BEGIN DESCRIPTION:
Mapping XS 262a41c4
END DESCRIPTION:
XS GIS Cut Line= 3
      2534232.12     13541970.67      2534162.67     13541470.64
      2533961.83     13540778.11
#Sta/Elev= 30
  4499.9  180.23  4550.9  178.51  4677.3  174.76  4774.9  174.23  4876.4   173.6
  4922.7  171.94  4939.8  171.72  4948.1  167.38  4953.2  166.16    4970  158.19
  4976.2  157.54  4976.7  157.04  4984.1  157.54  4990.2  158.22    5000  161.65
  5031.4  162.18  5052.1  164.28    5146  164.16  5166.8  162.99  5227.6  164.94
  5265.7  166.07  5299.2   167.9  5304.4  169.08  5410.4  171.17  5443.9  174.51
  5477.5  173.65  5489.6  175.43    5517  175.48  5518.4  175.71  5725.8  180.31
#Mann= 10 ,-1 , 0
  4499.9     .03       0  4550.9     .05       0  4774.9     .04       0
  4922.7     .05       0  4976.2     .05       0  4984.1     .05       0
  5052.1     .12       0  5227.6     .04       0    5517     .12       0
  5518.4     .04       0
Bank Sta=4976.2,4984.1
XS Rating Curve= 0 ,0
Exp/Cntr=0.3,0.1

Type RM Length L Ch R = 1 ,16351   ,244,244,244
BEGIN DESCRIPTION:
Mapping XS 4d24076c
END DESCRIPTION:
XS GIS Cut Line= 3
      2534485.58     13541807.44      2534447.39     13541106.06
      2534221.69     13540751.88
#Sta/Elev= 30
  4264.3  177.43  4451.2  172.47  4487.1  172.24  4647.3  168.53  4697.4  168.79
  4737.1   166.5  4777.5  165.53  4817.6  165.91  4867.6  163.39  4907.7  163.08
  4957.8  159.92  4964.7  157.71  4970.3  157.71  4982.9  156.09  4994.3     156
  4994.8   155.5  5002.3     156  5019.5  158.77  5027.3  162.82  5034.7  168.29
  5040.7  168.13    5050  169.67  5054.9  169.16  5077.1  170.23  5107.5  173.76
  5166.4  175.53  5240.6  176.08  5295.4   176.5  5301.4  177.14  5386.7   178.7
#Mann= 8 ,-1 , 0
  4264.3     .12       0  4451.2     .05       0  4737.1     .12       0
  4982.9     .04       0  4994.3     .04       0  5002.3     .04       0
  5166.4     .05       0  5240.6     .04       0
Bank Sta=4994.3,5002.3
XS Rating Curve= 0 ,0
Exp/Cntr=0.3,0.1

Type RM Length L Ch R = 1 ,16107   ,447,447,447
BEGIN DESCRIPTION:
Mapping XS fc8732bd
END DESCRIPTION:
XS GIS Cut Line= 3
      2534728.64     13541699.83      2534655.72     13541008.83
      2534464.74     13540564.36
#Sta/Elev= 30
  4321.1  176.42  4455.3  172.73  4500.3  171.63  4527.1  169.99  4699.3  166.75
  4828.7  167.17    4882  165.75  4919.2  161.78  4979.9  160.74  5005.7  153.31
  5006.2  152.81  5013.7  153.31  5041.9  156.14  5058.7  158.96  5063.6  160.83
  5080.5  163.74    5086  165.59  5118.1   165.9  5127.6  161.37  5133.1  164.52
  5139.8  160.89  5150.7  163.58  5162.1  163.27  5180.2  165.13  5185.6  164.71
  5194.3  165.43  5203.7  168.07  5232.7  170.03    5432   178.3  5499.7  178.16
#Mann= 6 ,-1 , 0
  4321.1     .12       0  4455.3     .05       0  4699.3     .12       0
  5005.7     .05       0  5013.7     .12       0  5058.7     .05       0
Bank Sta=5005.7,5013.7
XS Rating Curve= 0 ,0
Exp/Cntr=0.3,0.1