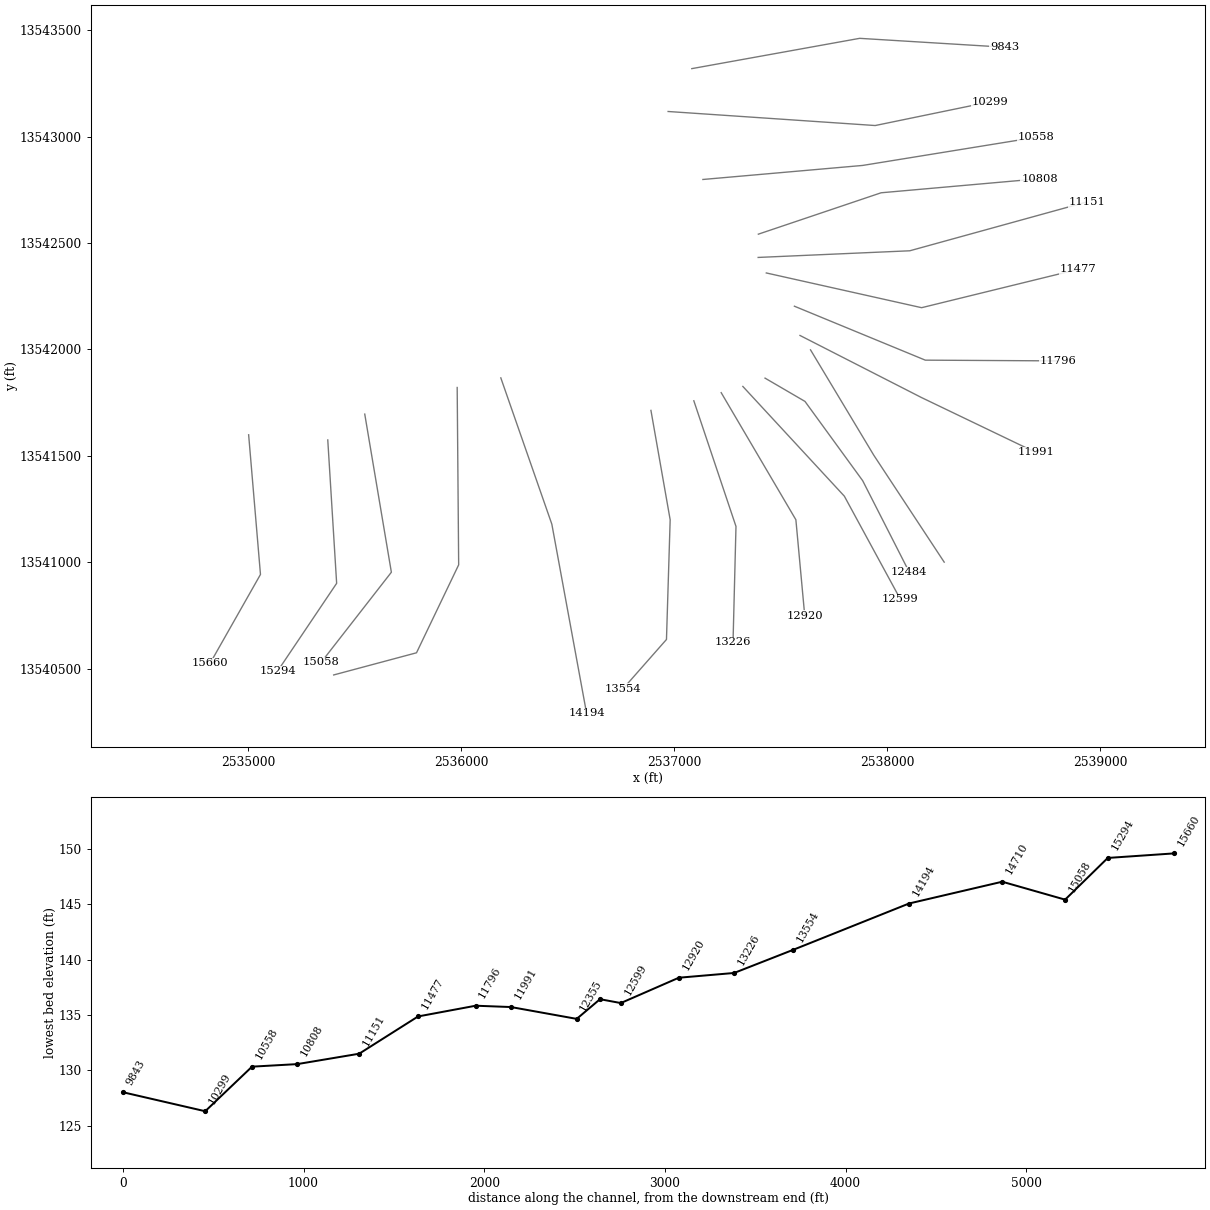
HEC-RAS study TRIB 12 TO GUADALUPE RIVER.prj: TRIB 12 TO GUADALUPE RIVER Base Level Engineering

--- TRIB 12 TO GUADALUPE RIVER.g01 (geometry) --- (continued)

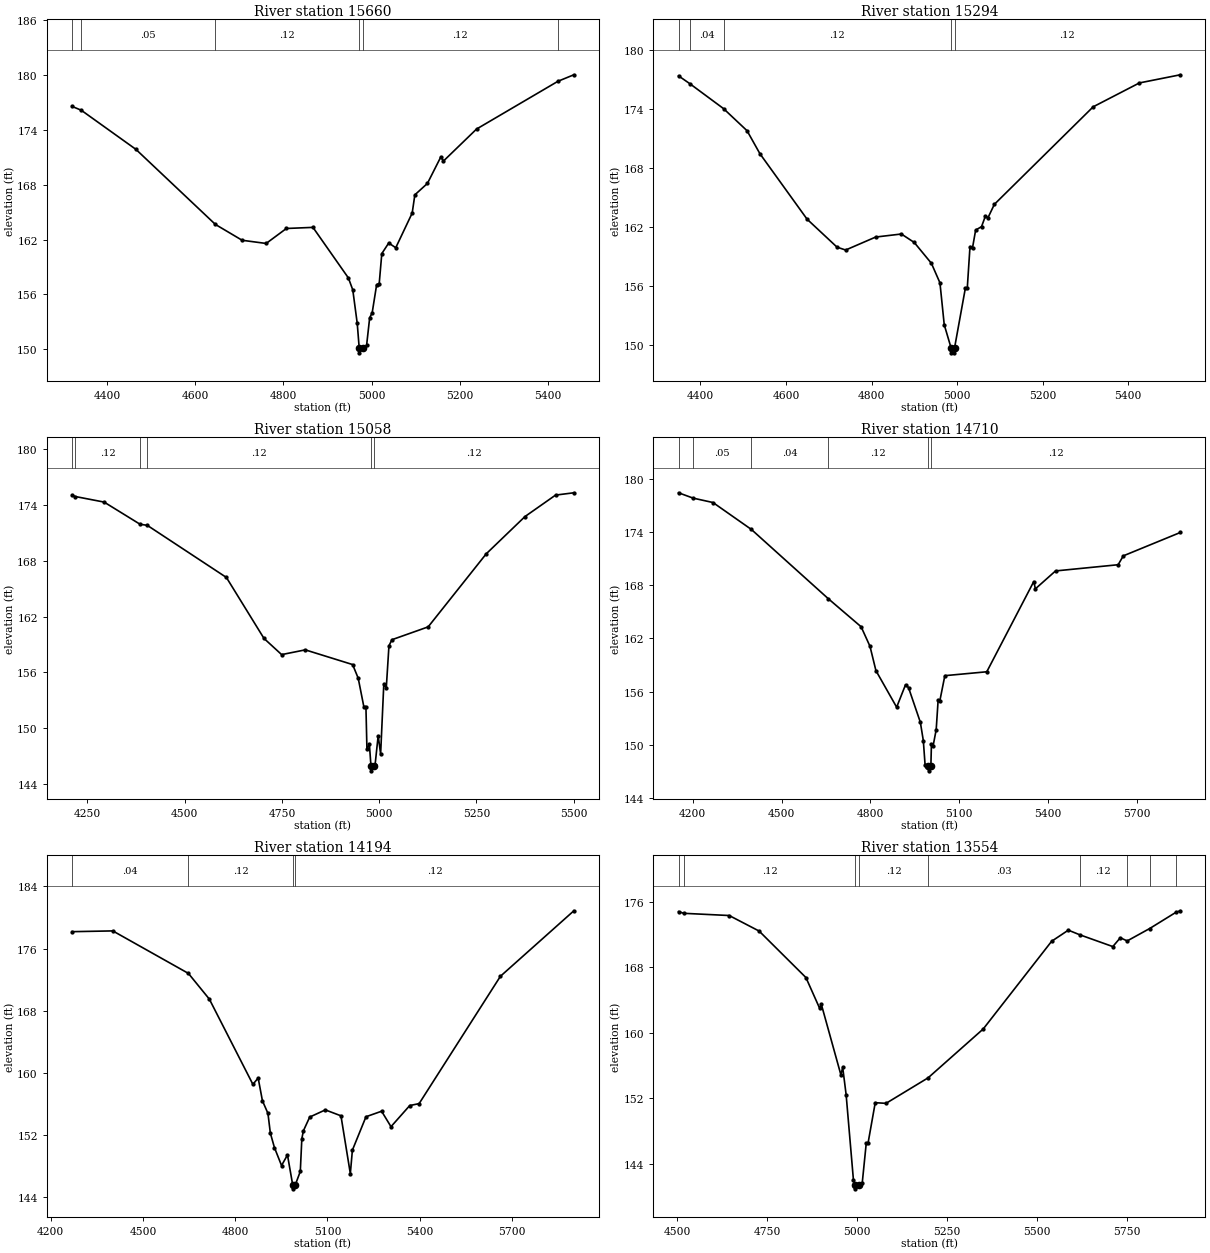
Type RM Length L Ch R = 1 ,15660   ,366,366,366
BEGIN DESCRIPTION:
Mapping XS fd9d964e
END DESCRIPTION:
XS GIS Cut Line= 3
      2535002.94     13541599.16       2535058.5     13540942.86
      2534822.37     13540526.16
#Sta/Elev= 30
  4320.8  176.58  4341.6  176.16  4465.5  171.88  4645.8  163.66  4706.3  161.93
  4760.8  161.58  4806.7  163.22  4866.9  163.34  4947.2  157.81  4957.2   156.5
  4967.3  152.83  4971.8  150.11  4972.3  149.61  4979.9  150.11  4988.5  150.42
  4995.5  153.45  5001.2     154  5011.3  157.07  5017.1  157.18    5023  160.47
  5038.7  161.63  5054.6  161.11  5091.9  164.91  5097.9   166.9  5126.4  168.15
    5157  171.07  5162.8   170.6  5237.8   174.1  5422.4  179.33  5458.4  180.04
#Mann= 6 ,-1 , 0
  4320.8     .04       0  4341.6     .05       0  4645.8     .12       0
  4971.8     .05       0  4979.9     .12       0  5422.4     .04       0
Bank Sta=4971.8,4979.9
XS Rating Curve= 0 ,0
Exp/Cntr=0.3,0.1

Type RM Length L Ch R = 1 ,15294   ,236,236,236
BEGIN DESCRIPTION:
Mapping XS 80c6f1b9
END DESCRIPTION:
XS GIS Cut Line= 3
      2535374.47     13541574.84      2535416.14      13540901.2
      2535138.37     13540488.02
#Sta/Elev= 30
  4348.9  177.38  4375.4  176.58    4454  174.05    4509   171.8  4539.1  169.46
  4649.3   162.8  4719.4  159.95  4739.5  159.66  4809.6  160.98  4869.7  161.29
  4899.8  160.43  4939.9  158.31  4959.9  156.32  4969.9  152.06  4985.9   149.7
  4986.4   149.2  4993.5   149.2    4994   149.7  5019.4  155.81  5023.8  155.81
  5030.1  160.01  5036.1  159.91  5043.3  161.69  5057.1  162.04  5066.1  163.11
  5072.1  162.94  5087.1  164.31    5318  174.23    5426  176.66  5521.7  177.49
#Mann= 5 ,-1 , 0
  4348.9     .12       0  4375.4     .04       0    4454     .12       0
  4985.9     .05       0    4994     .12       0
Bank Sta=4985.9,4994
XS Rating Curve= 0 ,0
Exp/Cntr=0.3,0.1

Type RM Length L Ch R = 1 ,15058   ,348,348,348
BEGIN DESCRIPTION:
Mapping XS 8c4f4138
END DESCRIPTION:
XS GIS Cut Line= 3
      2535548.09      13541696.3      2535673.09     13540953.28
      2535343.38     13540529.87
#Sta/Elev= 30
  4210.5  175.05  4218.5  174.91  4292.9  174.31  4385.2  171.93  4403.9  171.81
  4607.3  166.21  4703.9  159.66  4749.3  157.92  4810.1  158.43  4931.8  156.85
  4946.2  155.38  4960.6  152.33    4966  152.33  4968.6  147.77  4974.9  148.27
    4979  145.93  4979.5  145.43  4987.1  145.93  4989.4  146.01  4997.5  149.21
  5003.8  147.24    5012   154.8  5018.3  154.31  5025.2  158.86  5032.8  159.52
    5126   160.9  5275.3  168.75  5374.8  172.75  5453.5  175.06  5500.6  175.31
#Mann= 6 ,-1 , 0
  4210.5     .05       0  4218.5     .12       0  4385.2     .04       0
  4403.9     .12       0    4979     .05       0  4987.1     .12       0
Bank Sta=4979,4987.1
XS Rating Curve= 0 ,0
Exp/Cntr=0.3,0.1

Type RM Length L Ch R = 1 ,14710   ,516,516,516
BEGIN DESCRIPTION:
Mapping XS 0cf690b3
END DESCRIPTION:
XS GIS Cut Line= 4
      2535982.11     13541821.33      2535989.06       13540988.
      2535791.14     13540574.81      2535402.26     13540470.64
#Sta/Elev= 30
  4152.2  178.43  4201.1  177.83  4268.5  177.33  4398.2  174.29    4658  166.47
  4768.6  163.31  4798.6   161.1  4818.6  158.36  4888.6  154.23  4918.6  156.77
  4928.6  156.45  4968.6  152.53  4978.6  150.47  4984.6  147.71  4995.8  147.55
  4996.3  147.05  5004.1  147.55    5006  150.05  5011.6  149.85  5022.1   151.7
  5028.7  155.07  5034.2  154.92  5051.3  157.79  5192.9  158.23  5351.5  168.41
    5357  167.59    5425  169.61  5636.4  170.31  5653.7  171.31  5846.3  173.95
#Mann= 6 ,-1 , 0
  4152.2     .04       0  4201.1     .05       0  4398.2     .04       0
    4658     .12       0  4995.8     .05       0  5004.1     .12       0
Bank Sta=4995.8,5004.1
XS Rating Curve= 0 ,0
Exp/Cntr=0.3,0.1

Type RM Length L Ch R = 1 ,14194   ,640,640,640
BEGIN DESCRIPTION:
Mapping XS fc08bb40
END DESCRIPTION:
XS GIS Cut Line= 3
      2536186.97     13541866.49      2536426.56     13541178.97
      2536589.75      13540290.1
#Sta/Elev= 30
  4269.6  178.18    4402  178.28  4647.9  172.81    4716   169.5  4857.6  158.53
  4874.8  159.34  4888.6  156.42  4906.6  154.79  4914.4  152.25  4927.7  150.39
  4950.8  148.08  4970.1  149.44  4987.1  145.58  4987.6  145.08  4995.4  145.58
  5011.8  147.32  5016.8  151.55    5022  152.56  5042.4  154.32  5093.2  155.24
    5144  154.48  5174.5  147.04  5181.2  150.06  5225.4  154.36  5276.2  155.07
  5306.7  153.08  5367.7   155.8  5398.2  156.05  5662.6  172.44  5901.4  180.87
#Mann= 4 ,-1 , 0
  4269.6     .04       0  4647.9     .12       0  4987.1     .05       0
  4995.4     .12       0
Bank Sta=4987.1,4995.4
XS Rating Curve= 0 ,0
Exp/Cntr=0.3,0.1

Type RM Length L Ch R = 1 ,13554   ,328,328,328
BEGIN DESCRIPTION:
Mapping XS 1774d9d5
END DESCRIPTION:
XS GIS Cut Line= 4
      2536891.83     13541713.71      2536982.11     13541199.81
      2536964.75     13540637.31      2536759.97     13540404.76
#Sta/Elev= 30
  4504.2  174.82  4518.7  174.61    4645  174.34  4728.1  172.44  4858.2  166.75
    4896  163.02  4901.1  163.46  4955.3  154.86  4960.4  155.75  4969.9  152.43
  4990.2  141.99  4995.3   141.4  4995.8   140.9  5005.5   141.4  5014.7  141.63
  5025.9  146.51  5030.9  146.51  5050.8  151.44  5080.8  151.36  5197.7  154.48
  5350.9  160.46    5541  171.19  5587.4  172.55  5618.7  171.99    5711  170.54
  5731.9  171.62  5750.9  171.23  5813.5  172.75  5885.6  174.71  5898.6  174.92
#Mann= 9 ,-1 , 0
  4504.2     .05       0  4518.7     .12       0  4995.3     .05       0
  5005.5     .12       0  5197.7     .03       0  5618.7     .12       0
  5750.9    .013       0  5813.5     .12       0  5885.6    .013       0
Bank Sta=4995.3,5005.5
XS Rating Curve= 0 ,0
Exp/Cntr=0.3,0.1

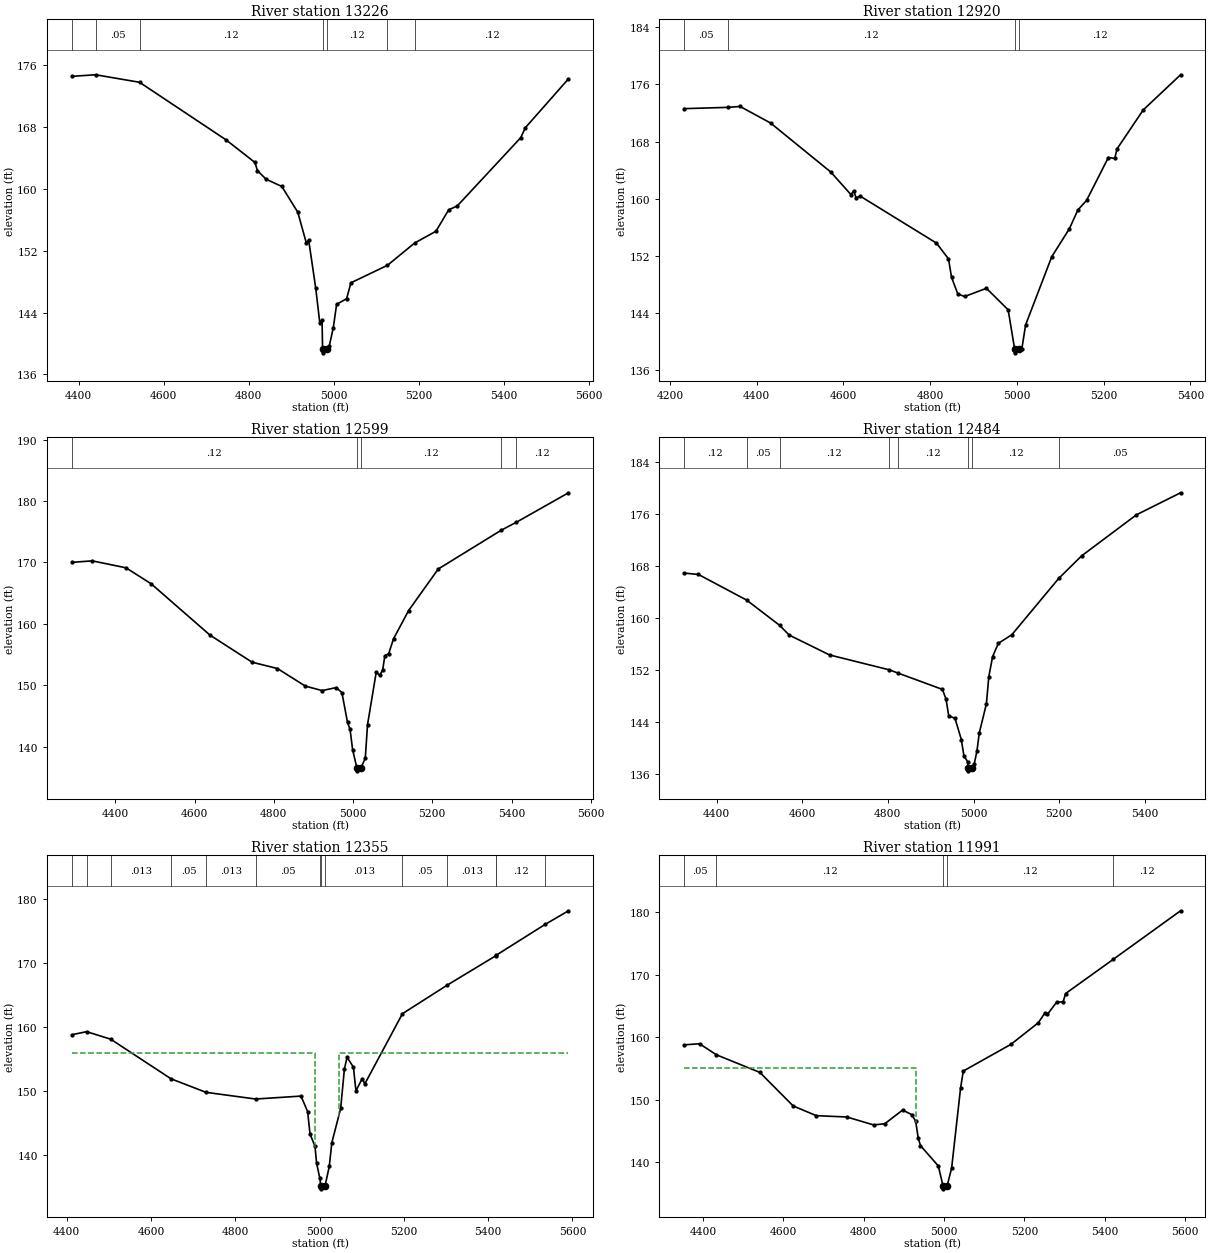
Type RM Length L Ch R = 1 ,13226   ,306,306,306
BEGIN DESCRIPTION:
Mapping XS fa2d7239
END DESCRIPTION:
XS GIS Cut Line= 3
      2537093.22     13541758.85      2537291.14     13541168.56
      2537277.25     13540623.43
#Sta/Elev= 30
  4383.9  174.58  4440.1  174.78  4543.1  173.81  4746.3  166.37  4814.6  163.43
  4820.4  162.37  4840.9  161.26  4877.7  160.33  4915.3  156.99  4935.6  152.96
  4940.8  153.41  4957.5  147.14  4967.1  142.62  4972.4  143.06  4973.5   139.3
    4974   138.8  4983.7   139.3  4989.1  139.65  4998.7  142.03  5006.5  145.07
  5030.1  145.81  5040.1  147.86  5126.2  150.13    5190  153.01  5240.1  154.53
  5270.1  157.31  5290.1   157.8  5439.6  166.65  5450.2  167.92  5551.8  174.26
#Mann= 7 ,-1 , 0
  4383.9     .12       0  4440.1     .05       0  4543.1     .12       0
  4973.5     .05       0  4983.7     .12       0  5126.2     .03       0
    5190     .12       0
Bank Sta=4973.5,4983.7
XS Rating Curve= 0 ,0
Exp/Cntr=0.3,0.1

Type RM Length L Ch R = 1 ,12920   ,321,321,321
BEGIN DESCRIPTION:
Mapping XS 0109f9ca
END DESCRIPTION:
XS GIS Cut Line= 3
      2537221.68     13541797.05      2537572.39     13541199.81
      2537613.98     13540749.23
#Sta/Elev= 30
  4232.1  172.61    4333  172.79  4361.6  172.92  4431.8   170.6  4570.8  163.72
  4617.2  160.56  4623.4  161.07  4629.2  160.12    4639  160.33  4814.3  153.76
  4842.1  151.55  4849.1  148.97  4863.6  146.62  4879.3  146.27  4929.6  147.42
  4979.7   144.4  4994.7  138.87  4995.2  138.37  5004.9  138.87  5011.2   138.9
  5019.9  142.29  5080.2  151.85  5120.8  155.77  5140.4   158.4  5160.5  159.75
  5210.7  165.76  5225.4  165.63  5230.8  166.98  5291.1  172.43  5377.2  177.36
#Mann= 4 ,-1 , 0
  4232.1     .05       0    4333     .12       0  4994.7     .05       0
  5004.9     .12       0
Bank Sta=4994.7,5004.9
XS Rating Curve= 0 ,0
Exp/Cntr=0.3,0.1

Type RM Length L Ch R = 1 ,12599   ,115,115,115
BEGIN DESCRIPTION:
Mapping XS 4948ee88
END DESCRIPTION:
XS GIS Cut Line= 3
      2537323.41     13541826.26      2537799.98     13541310.64
      2538062.99     13540826.27
#Sta/Elev= 30
  4290.4  170.01    4342  170.25  4427.1  169.12  4490.6  166.52  4639.2  158.16
  4745.2  153.76  4809.3  152.73  4879.6  149.87  4922.1  149.14  4957.8  149.63
    4972  148.79  4986.1  143.95  4992.5  142.83  4998.9  139.55  5009.6  136.58
  5010.1  136.08  5019.9  136.58  5030.9  138.12  5036.6  143.59  5058.5  152.12
  5067.2  151.63  5074.7  152.47  5080.3  154.81    5090  155.15  5102.2  157.57
  5140.2  162.16  5215.1  168.93    5374  175.24  5412.1  176.53  5543.7  181.33
#Mann= 5 ,-1 , 0
  4290.4     .12       0  5009.6     .05       0  5019.9     .12       0
    5374     .05       0  5412.1     .12       0
Bank Sta=5009.6,5019.9
XS Rating Curve= 0 ,0
Exp/Cntr=0.3,0.1

Type RM Length L Ch R = 1 ,12484   ,129,129,129
BEGIN DESCRIPTION:
Mapping XS 447ae1e5
END DESCRIPTION:
XS GIS Cut Line= 4
      2537427.55     13541865.34      2537615.08     13541755.95
      2537885.91     13541383.56      2538104.65      13540953.9
#Sta/Elev= 30
  4323.8  166.86  4357.8  166.64  4470.3   162.7  4547.2  158.82  4569.6  157.32
  4663.9  154.26  4803.3  151.97  4823.7  151.47  4927.4  148.96  4935.9  147.46
  4942.1  144.89  4956.8  144.52  4971.5  141.25  4977.7  138.72  4986.2  137.85
  4987.2  136.93  4987.7  136.43  4997.5  136.93  5001.4  137.41  5007.9  139.41
  5013.5  142.27  5030.1  146.73  5035.7  150.91  5044.6     154    5058  156.05
  5089.5  157.37  5198.9  166.03  5252.5  169.51  5380.4  175.82  5483.5  179.21
#Mann= 8 ,-1 , 0
  4323.8     .12       0  4470.3     .05       0  4547.2     .12       0
  4803.3    .013       0  4823.7     .12       0  4987.2     .05       0
  4997.5     .12       0  5198.9     .05       0
Bank Sta=4987.2,4997.5
XS Rating Curve= 0 ,0
Exp/Cntr=0.3,0.1

Type RM Length L Ch R = 1 ,12355   ,364,364,364
BEGIN DESCRIPTION:
Mapping XS 38cc60fc
END DESCRIPTION:
XS GIS Cut Line= 3
      2537641.14      13541998.1        2537938.     13541503.35
       2538268.7     13541000.77
#Sta/Elev= 30
  4412.1  158.79  4447.2  159.27  4504.5  158.09  4647.7  151.88  4730.5  149.77
  4848.2  148.72    4956  149.18  4971.6  146.76  4977.4  143.23  4989.1  141.33
  4992.9   138.7  5000.7  136.28  5002.8  135.15  5003.3  134.65  5013.1  135.15
    5023  138.15  5029.1  141.88  5050.1  147.24  5058.9   153.4  5065.2  155.26
  5080.3  153.72  5086.3  150.01  5101.4  151.93  5107.3  151.08  5196.7  162.09
  5303.4  166.58  5418.3  171.17    5419  171.24  5535.1  176.07  5590.7  178.21
#Mann= 14 ,-1 , 0
  4412.1    .013       0  4447.2     .12       0  4504.5    .013       0
  4647.7     .05       0  4730.5    .013       0  4848.2     .05       0
  5000.7    .013       0  5002.8     .05       0  5013.1    .013       0
  5196.7     .05       0  5303.4    .013       0  5418.3     .05       0
    5419     .12       0  5535.1    .013       0
#XS Ineff= 2 , 0
       0    4990     156    5045       0     156
Permanent Ineff=
       F       F
Bank Sta=5002.8,5013.1
XS Rating Curve= 0 ,0
Exp/Cntr=0.3,0.1

Type RM Length L Ch R = 1 ,11991   ,195,195,195
BEGIN DESCRIPTION:
Mapping XS dd43a197
END DESCRIPTION:
XS GIS Cut Line= 3
      2537591.68     13542065.83      2538161.95     13541774.18
       2538698.4     13541516.37
#Sta/Elev= 30
  4352.8  158.76  4391.7  158.94  4433.6  157.17  4541.6  154.36  4624.8  148.98
  4682.3  147.43  4758.1  147.22  4824.7  145.95  4852.6  146.14    4897  148.33
  4919.2  147.61  4929.4  146.56  4935.8  143.83  4941.4  142.64  4985.8  139.38
  4997.4  136.22  4997.9  135.72  5007.8  136.22  5018.9  139.04  5041.1  151.83
  5047.9  154.57  5166.6  158.85  5234.5   162.3  5251.6  163.92  5257.2  163.64
  5279.8  165.57  5296.3  165.66  5302.5  166.98  5420.6  172.43  5588.5  180.22
#Mann= 5 ,-1 , 0
  4352.8     .05       0  4433.6     .12       0  4997.4     .05       0
  5007.8     .12       0  5420.6     .12       0
#XS Ineff= 2 , 0
       0    4930     155               0
Permanent Ineff=
       F       F
Bank Sta=4997.4,5007.8
XS Rating Curve= 0 ,0
Exp/Cntr=0.3,0.1

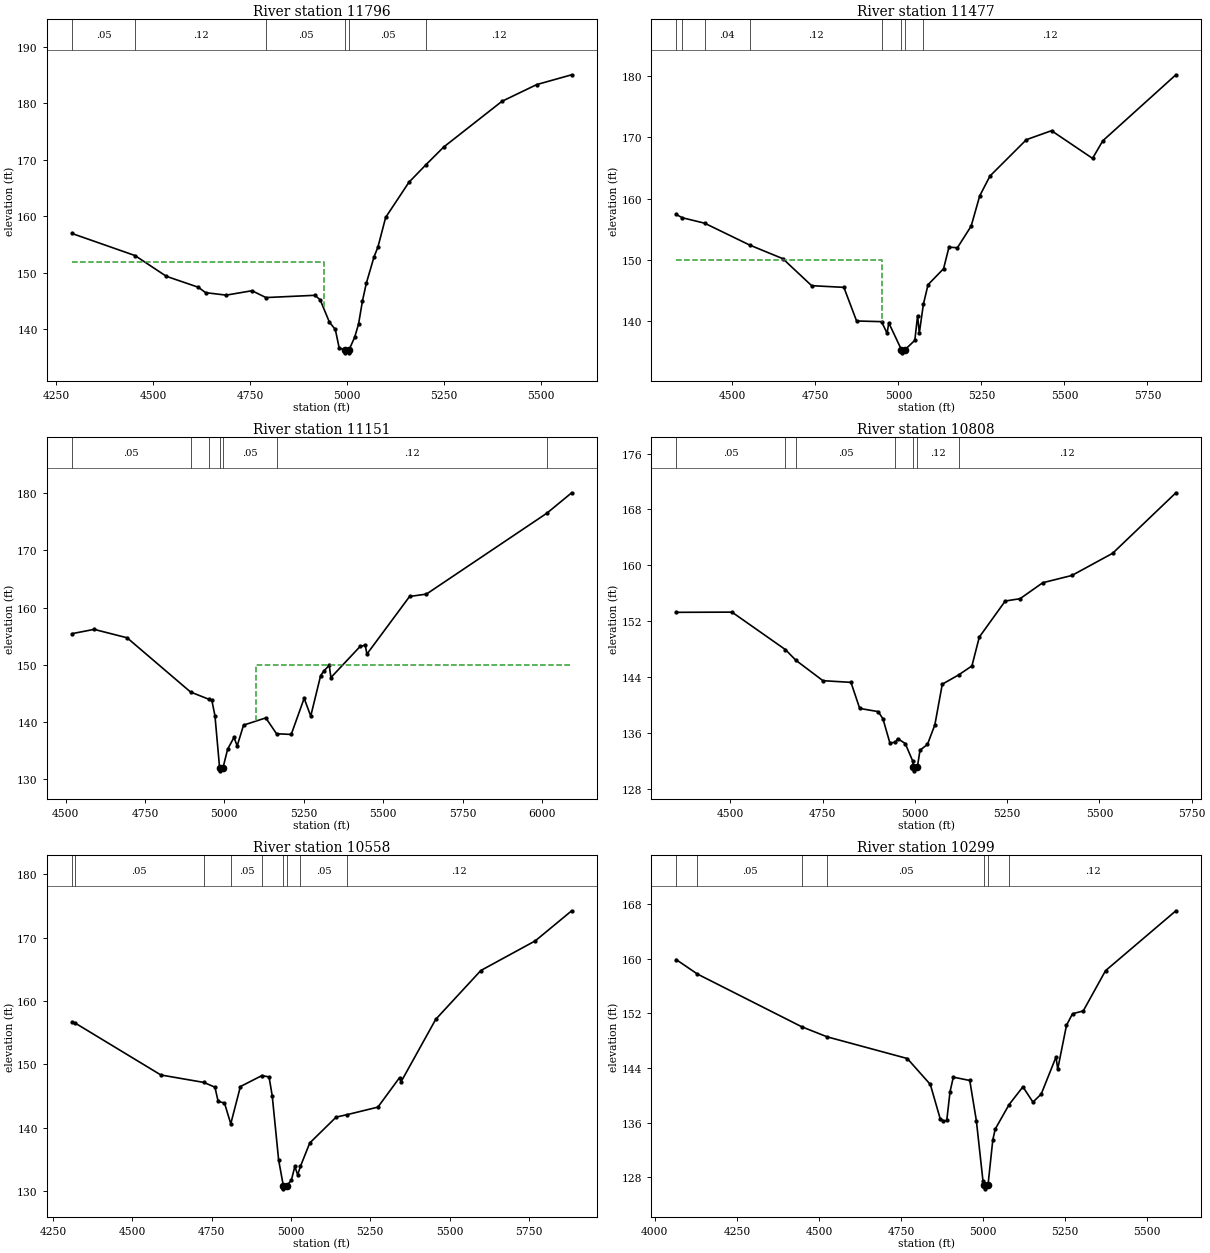
Type RM Length L Ch R = 1 ,11796   ,319,319,319
BEGIN DESCRIPTION:
Mapping XS 39acb98b
END DESCRIPTION:
XS GIS Cut Line= 3
      2537565.49     13542203.26      2538180.03     13541949.81
      2538805.07     13541946.33
#Sta/Elev= 30
    4290  156.96  4452.5  153.06  4533.7  149.38  4616.3  147.44  4634.9  146.49
  4688.1  146.05  4754.6  146.83  4790.7  145.62  4916.9  146.02  4930.6  145.23
  4954.5  141.26  4969.7  139.98  4979.7   136.7  4994.5  136.34    4995  135.84
  5004.4  135.84  5004.9  136.34  5019.7   138.6  5029.7  140.94  5039.7     145
  5049.7  148.15  5069.7  152.83  5079.7  154.56  5099.7  159.81  5159.7  166.02
    5204  169.15  5249.7  172.27  5399.7  180.34  5489.7  183.31  5579.8  185.04
#Mann= 6 ,-1 , 0
    4290     .05       0  4452.5     .12       0  4790.7     .05       0
  4994.5     .05       0  5004.9     .05       0    5204     .12       0
#XS Ineff= 2 , 0
       0    4940     152               0
Permanent Ineff=
       F       F
Bank Sta=4994.5,5004.9
XS Rating Curve= 0 ,0
Exp/Cntr=0.3,0.1

Type RM Length L Ch R = 1 ,11477   ,326,326,326
BEGIN DESCRIPTION:
Mapping XS b4b2622b
END DESCRIPTION:
XS GIS Cut Line= 3
      2537433.53     13542359.52      2538162.67     13542196.33
      2538898.77     13542376.89
#Sta/Elev= 30
  4330.7  157.41  4349.3  156.88  4416.4  155.99  4552.1  152.43    4652  150.21
  4738.8  145.81  4835.8  145.54  4874.1  140.06  4949.3  139.95    4966  138.06
  4971.1  139.75  5009.2  135.37  5009.7  134.87  5019.7  135.37  5049.5  136.91
  5057.9  140.94    5063  138.07  5075.2  142.76  5089.3  145.97  5136.1  148.58
  5152.4  152.09  5177.7  151.99  5219.2  155.52    5245  160.45  5275.9  163.68
  5385.6   169.6  5461.2  171.06  5584.8  166.55  5615.7  169.42  5835.8  180.17
#Mann= 8 ,-1 , 0
  4330.7    .013       0  4349.3     .05       0  4416.4     .04       0
  4552.1     .12       0  4949.3     .05       0  5009.2     .05       0
  5019.7     .05       0  5075.2     .12       0
#XS Ineff= 2 , 0
       0    4950     150               0
Permanent Ineff=
       F       F
Bank Sta=5009.2,5019.7
XS Rating Curve= 0 ,0
Exp/Cntr=0.3,0.1

Type RM Length L Ch R = 1 ,11151   ,343,343,343
BEGIN DESCRIPTION:
Mapping XS c6123caa
END DESCRIPTION:
XS GIS Cut Line= 3
      2537395.26     13542432.44      2538107.11      13542463.7
      2538937.01     13542692.87
#Sta/Elev= 30
  4520.3  155.46  4590.1  156.21  4693.9  154.74  4893.7  145.27  4951.8  143.99
  4960.5  143.86  4970.5  141.14  4985.2     132  4985.7   131.5  4995.7     132
  5010.5  135.29  5030.5  137.34  5040.5  135.86  5060.6  139.48  5130.6  140.75
  5164.4  137.98  5210.7  137.86  5251.4  144.17  5272.1  141.06  5303.3  148.14
  5313.6  148.96  5330.4  149.93  5335.6  147.79  5427.8  153.24  5443.8  153.45
    5449  151.89  5583.4  161.96  5636.3  162.37  6015.8  176.51  6093.8  180.07
#Mann= 7 ,-1 , 0
  4520.3     .05       0  4893.7     .12       0  4951.8     .05       0
  4985.2     .05       0  4995.7     .05       0  5164.4     .12       0
  6015.8     .05       0
#XS Ineff= 2 , 0
       0                    5100       0     150
Permanent Ineff=
       F       F
Bank Sta=4985.2,4995.7
XS Rating Curve= 0 ,0
Exp/Cntr=0.3,0.1

Type RM Length L Ch R = 1 ,10808   ,250,250,250
BEGIN DESCRIPTION:
Mapping XS 698826e4
END DESCRIPTION:
XS GIS Cut Line= 3
      2537396.19     13542541.82      2537972.56     13542736.26
      2538715.65     13542802.24
#Sta/Elev= 30
    4353  153.26  4504.2  153.29  4649.1  147.92  4677.9  146.37  4750.8  143.47
  4826.7  143.23  4850.4   139.5  4900.5  139.04  4913.4  138.01  4932.2  134.56
  4947.2  134.66  4953.3  135.18  4973.8  134.47  4993.9  131.99  4995.9  131.06
  4996.4  130.56  5006.5  131.06  5013.9  133.52    5034  134.34  5054.1  137.15
  5074.2  142.97  5118.3  144.29  5154.5  145.58  5174.6  149.72  5244.8  154.88
    5285  155.21  5346.5   157.5  5425.5  158.54    5536  161.72  5707.3  170.38
#Mann= 7 ,-1 , 0
    4353     .05       0  4649.1     .12       0  4677.9     .05       0
  4947.2     .12       0  4995.9     .05       0  5006.5     .12       0
  5118.3     .12       0
Bank Sta=4995.9,5006.5
XS Rating Curve= 0 ,0
Exp/Cntr=0.3,0.1

Type RM Length L Ch R = 1 ,10558   ,259,259,259
BEGIN DESCRIPTION:
Mapping XS 1faa6782
END DESCRIPTION:
XS GIS Cut Line= 3
      2537135.81     13542798.77      2537885.76     13542864.74
      2538698.27     13542996.68
#Sta/Elev= 30
  4309.3  156.61  4317.7  156.57  4589.6  148.32  4725.4  147.14  4760.2  146.39
  4770.3  144.14  4790.3  143.89  4810.1   140.6  4840.5  146.49  4908.6  148.23
  4930.9     148  4940.9  145.01    4961  134.92  4975.8  130.83  4976.3  130.33
  4986.4  130.83  5001.2  131.69  5012.1  133.86  5021.2  132.54  5029.7  133.87
  5059.3  137.58  5142.4  141.66  5176.1  142.04  5274.1  143.24  5342.3  147.89
  5347.3  147.25  5456.5  157.11  5598.7  164.82  5770.5  169.51  5885.3  174.26
#Mann= 9 ,-1 , 0
  4309.3    .013       0  4317.7     .05       0  4725.4     .12       0
  4810.1     .05       0  4908.6     .12       0  4975.8     .05       0
  4986.4     .12       0  5029.7     .05       0  5176.1     .12       0
Bank Sta=4975.8,4986.4
XS Rating Curve= 0 ,0
Exp/Cntr=0.3,0.1

Type RM Length L Ch R = 1 ,10299   ,456,456,456
BEGIN DESCRIPTION:
Mapping XS 283d1600
END DESCRIPTION:
XS GIS Cut Line= 3
      2536972.52     13543118.21      2537944.79     13543052.24
      2538481.46     13543163.03
#Sta/Elev= 30
  4065.2   159.9  4129.9  157.78  4447.4  150.06  4524.9  148.58  4769.3   145.4
  4839.5   141.6  4869.5  136.59  4879.6  136.25  4889.6  136.32  4899.6  140.54
  4909.6  142.67  4959.7  142.18  4979.8  136.29  4999.8  127.52  5004.5   126.8
    5005   126.3  5015.2   126.8  5029.9  133.48  5037.3  135.06  5079.4  138.64
  5121.6  141.25  5152.2  139.01  5177.4  140.19  5222.5  145.62  5227.7  143.85
  5254.4  150.27  5272.8  151.96  5305.4  152.37  5373.3  158.27  5587.7  167.05
#Mann= 7 ,-1 , 0
  4065.2     .03       0  4129.9     .05       0  4447.4     .12       0
  4524.9     .05       0  5004.5     .05       0  5015.2     .05       0
  5079.4     .12       0
Bank Sta=5004.5,5015.2
XS Rating Curve= 0 ,0
Exp/Cntr=0.3,0.1

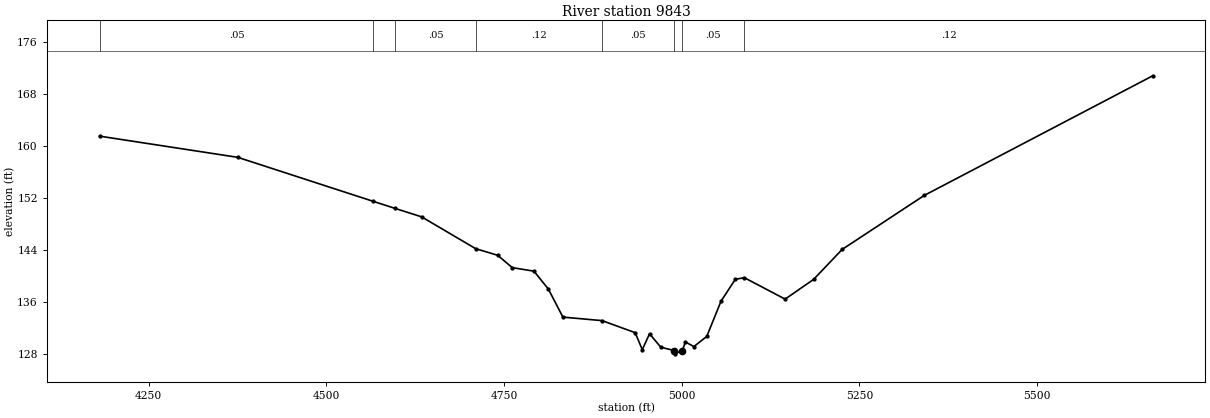
Type RM Length L Ch R = 1 ,9843    ,508,508,508
BEGIN DESCRIPTION:
Mapping XS ffead908
END DESCRIPTION:
XS GIS Cut Line= 3
      2537083.72     13543319.61      2537871.87     13543461.96
      2538551.19     13543420.37
#Sta/Elev= 30
  4181.2  161.51  4375.6  158.25  4566.4  151.47    4597  150.39  4634.1   149.1
  4710.2   144.2  4741.2  143.18  4761.7  141.28  4792.2  140.74  4812.5  137.98
  4832.9  133.67    4888  133.13  4934.5  131.28  4944.6  128.66  4954.8  131.11
  4970.6  129.04  4989.7  128.52  4990.2  128.02  5000.8  128.52  5005.3  129.84
  5017.2  129.14  5035.3   130.7  5055.4  136.13  5075.4  139.48  5088.1  139.74
  5145.5  136.44  5185.6  139.47  5225.7  144.08  5341.2  152.39  5662.7   170.8
#Mann= 8 ,-1 , 0
  4181.2     .05       0  4566.4     .12       0    4597     .05       0
  4710.2     .12       0    4888     .05       0  4989.7     .05       0
  5000.8     .05       0  5088.1     .12       0
Bank Sta=4989.7,5000.8
XS Rating Curve= 0 ,0
Exp/Cntr=0.3,0.1