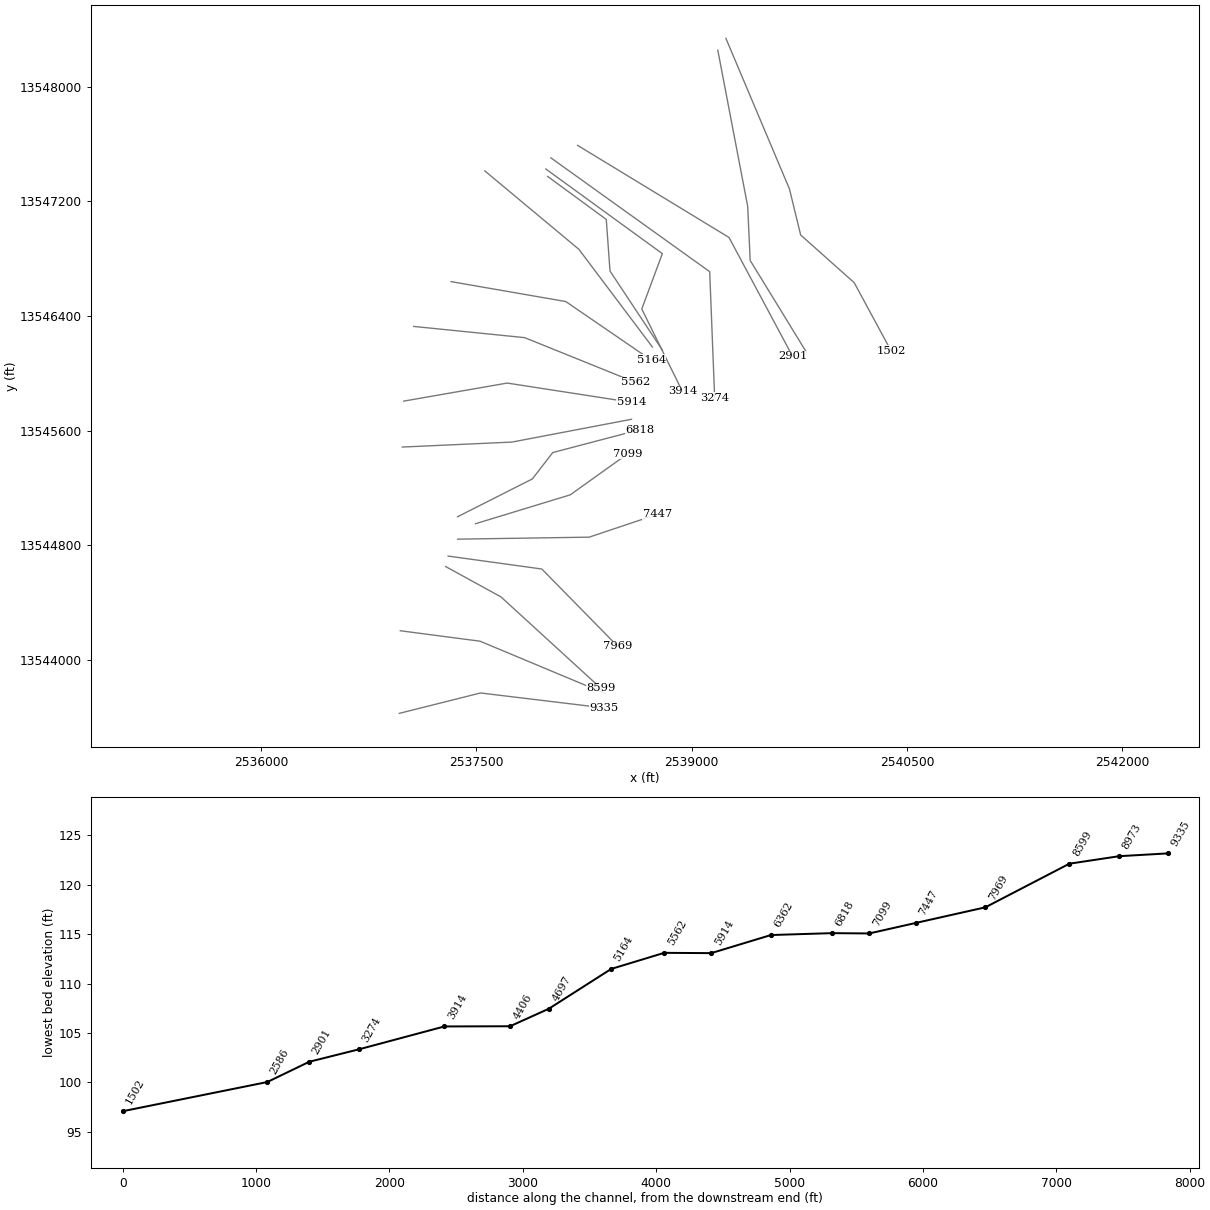
HEC-RAS study TRIB 12 TO GUADALUPE RIVER.prj: TRIB 12 TO GUADALUPE RIVER Base Level Engineering

--- TRIB 12 TO GUADALUPE RIVER.g01 (geometry) --- (continued)

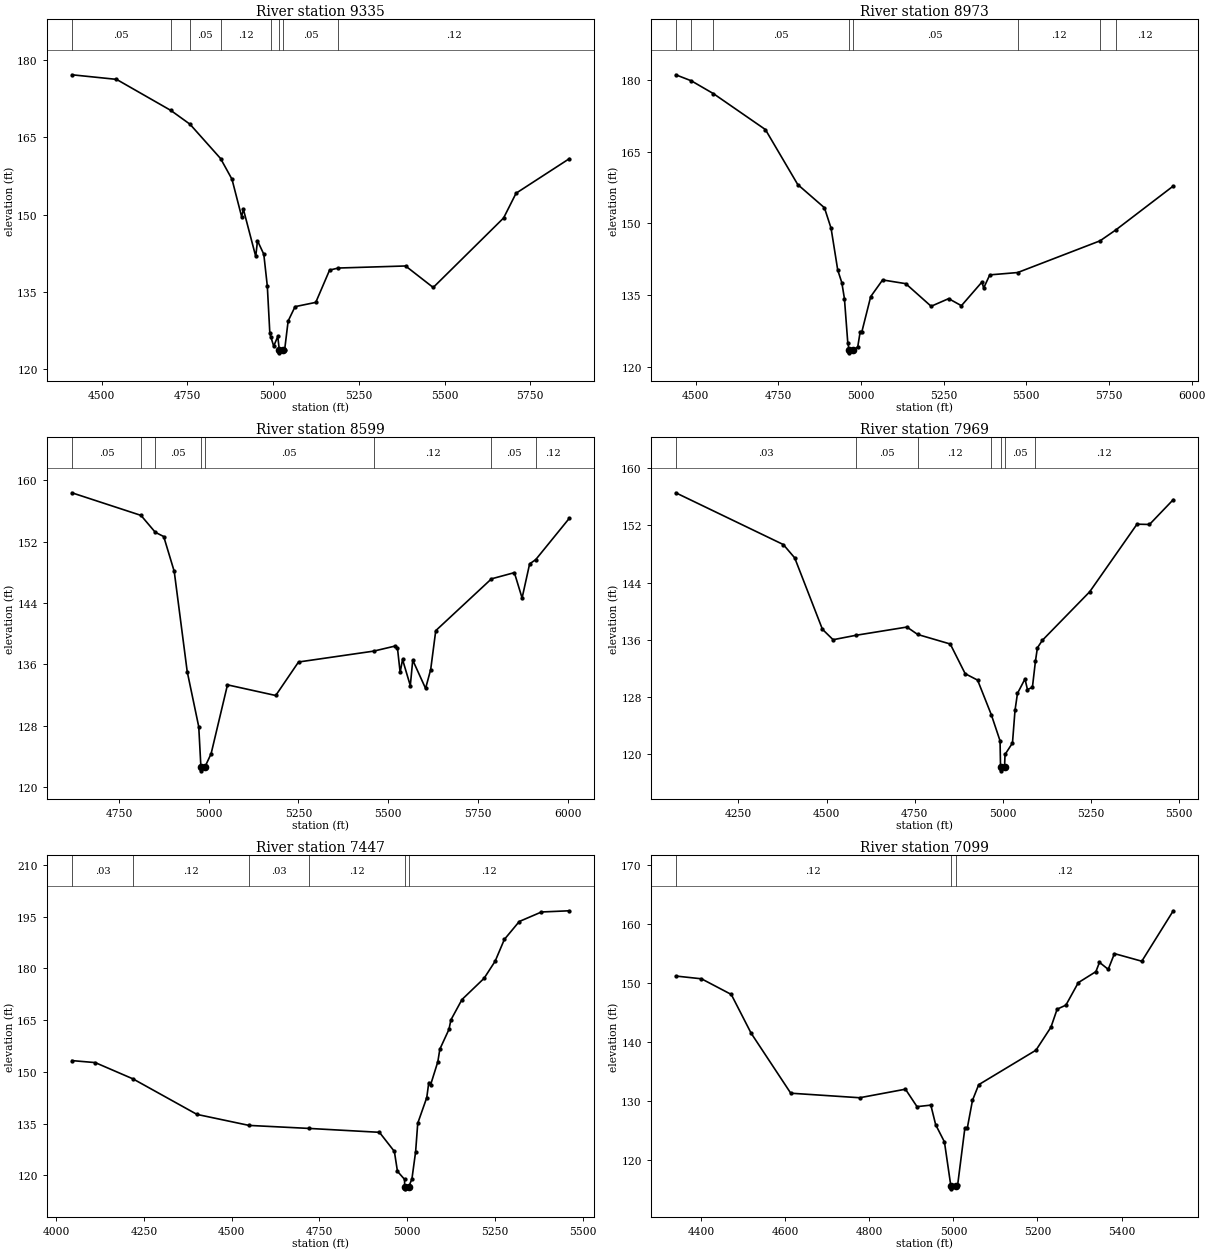
Type RM Length L Ch R = 1 ,9335    ,362,362,362
BEGIN DESCRIPTION:
Mapping XS 31e17fde
END DESCRIPTION:
XS GIS Cut Line= 3
      2536962.15     13543628.63      2537528.12     13543770.99
      2538389.24     13543666.82
#Sta/Elev= 30
  4412.8  177.15    4543  176.26  4701.4  170.23  4757.3  167.55  4846.6  160.88
  4879.8  156.87  4907.9  149.61  4913.1  151.03  4949.1  141.87  4954.2  144.92
  4972.6   142.3  4982.9  136.09  4990.2  126.98  4992.8  126.32  5001.5  124.45
  5013.4  126.33  5017.9  123.65  5018.4  123.15    5029  123.65  5033.5  123.79
  5043.6  129.33  5063.8  132.12  5124.2  132.95  5164.5  139.22    5190  139.62
  5386.1  140.02  5466.7  135.84    5672  149.34  5708.4  154.15  5863.8  160.86
#Mann= 8 ,-1 , 0
  4412.8     .05       0  4701.4     .12       0  4757.3     .05       0
  4846.6     .12       0  4992.8     .05       0  5017.9     .05       0
    5029     .05       0    5190     .12       0
Bank Sta=5017.9,5029
XS Rating Curve= 0 ,0
Exp/Cntr=0.3,0.1

Type RM Length L Ch R = 1 ,8973    ,374,374,374
BEGIN DESCRIPTION:
Mapping XS b4731e5f
END DESCRIPTION:
XS GIS Cut Line= 3
      2536969.07     13544205.02      2537524.65      13544132.1
      2538396.22      13543767.5
#Sta/Elev= 30
  4439.3  181.15  4486.2  179.89  4553.4  177.19  4710.5  169.67  4808.4  158.14
  4889.1  153.28  4909.2  148.98  4929.4   140.2  4941.7  137.58  4949.6  134.23
  4959.7  125.01  4964.2  123.37  4964.7  122.87  4975.3  123.37  4989.9  124.14
  4997.3  127.31  5002.4  127.31  5029.1  134.66  5065.1  138.15  5135.1  137.37
  5211.9  132.63  5264.9  134.23  5303.5  132.75  5365.5   137.7  5370.9  136.46
  5389.3  139.21  5473.7   139.7    5723  146.35  5770.2  148.61  5944.4  157.83
#Mann= 8 ,-1 , 0
  4439.3     .05       0  4486.2     .03       0  4553.4     .05       0
  4964.2     .05       0  4975.3     .05       0  5473.7     .12       0
    5723     .05       0  5770.2     .12       0
Bank Sta=4964.2,4975.3
XS Rating Curve= 0 ,0
Exp/Cntr=0.3,0.1

Type RM Length L Ch R = 1 ,8599    ,630,630,630
BEGIN DESCRIPTION:
Mapping XS 02063b5b
END DESCRIPTION:
XS GIS Cut Line= 3
       2537285.1     13544652.91      2537670.48     13544441.13
      2538368.37     13543802.26
#Sta/Elev= 30
  4618.9  158.39  4811.4  155.44  4851.2  153.24  4874.8  152.68  4904.1  148.13
  4940.2  135.07  4972.4  127.86  4978.4  122.61  4978.9  122.11  4989.5  122.61
  5006.8  124.34  5052.4  133.33  5186.8  131.94  5250.3  136.31  5459.7  137.73
  5519.2  138.39    5526   138.1  5533.4  134.95  5540.1  136.64  5561.7  133.22
  5568.5  136.55  5604.3  132.86  5618.5  135.33  5632.6   140.4  5787.7  147.16
  5851.6  147.97  5873.1  144.66  5894.1  149.11  5911.1  149.67  6004.8  155.07
#Mann= 8 ,-1 , 0
  4618.9     .05       0  4811.4     .03       0  4851.2     .05       0
  4978.4     .05       0  4989.5     .05       0  5459.7     .12       0
  5787.7     .05       0  5911.1     .12       0
Bank Sta=4978.4,4989.5
XS Rating Curve= 0 ,0
Exp/Cntr=0.3,0.1

Type RM Length L Ch R = 1 ,7969    ,522,522,522
BEGIN DESCRIPTION:
Mapping XS 63d6cb8c
END DESCRIPTION:
XS GIS Cut Line= 3
       2537302.4     13544725.85       2537955.2     13544635.57
      2538482.97     13544097.39
#Sta/Elev= 30
  4071.9  156.57  4377.4  149.33  4409.7  147.47  4488.4  137.49  4518.7  136.03
  4583.8  136.65  4728.3   137.8  4759.1  136.76  4851.4  135.43  4893.8  131.28
  4929.1  130.38  4968.1  125.53  4992.8   121.9  4994.2   118.2  4994.7   117.7
  5005.5   118.2    5007  119.99  5028.1  121.59  5035.3  126.16  5042.3  128.53
  5063.6  130.54  5070.6  129.07  5084.7  129.37  5093.3  133.02  5098.9   134.9
    5113  135.95  5247.4  142.73  5381.7  152.18  5417.2  152.14  5484.7  155.61
#Mann= 7 ,-1 , 0
  4071.9     .03       0  4583.8     .05       0  4759.1     .12       0
  4968.1     .05       0  4994.2     .05       0  5005.5     .05       0
  5093.3     .12       0
Bank Sta=4994.2,5005.5
XS Rating Curve= 0 ,0
Exp/Cntr=0.3,0.1

Type RM Length L Ch R = 1 ,7447    ,348,348,348
BEGIN DESCRIPTION:
Mapping XS d9fe517d
END DESCRIPTION:
XS GIS Cut Line= 3
      2537368.45      13544843.9      2538285.06     13544857.79
      2538760.36     13545017.38
#Sta/Elev= 30
  4044.2  153.28  4110.8   152.7  4218.5  147.98  4400.8  137.69  4549.2   134.5
  4719.5  133.63  4920.9   132.5  4963.5  126.96  4972.3  121.19  4992.5  118.88
  4992.9  116.62  4993.4  116.12  5004.2  116.62  5013.6  119.03  5024.1  126.91
  5030.1  135.12  5055.8  142.55  5061.6  146.92  5066.9   146.3  5087.4  152.96
  5093.1  156.59  5119.1  162.32  5124.6  165.06  5156.2  170.97  5219.2  177.12
  5250.8  182.09    5277  188.39  5319.5  193.58  5382.8  196.34  5462.3  196.69
#Mann= 6 ,-1 , 0
  4044.2     .03       0  4218.5     .12       0  4549.2     .03       0
  4719.5     .12       0  4992.9     .05       0  5004.2     .12       0
Bank Sta=4992.9,5004.2
XS Rating Curve= 0 ,0
Exp/Cntr=0.3,0.1

Type RM Length L Ch R = 1 ,7099    ,281,281,281
BEGIN DESCRIPTION:
Mapping XS d8220d07
END DESCRIPTION:
XS GIS Cut Line= 3
      2537493.39     13544951.54      2538153.12     13545152.93
      2538555.13     13545440.58
#Sta/Elev= 30
  4339.1  151.13  4400.3  150.66  4471.2  148.01  4518.5  141.44  4612.8  131.27
  4776.9   130.5  4885.8  131.95  4913.3  128.99  4946.2  129.25  4957.7  125.93
  4978.6  123.01  4993.8  115.56  4994.3  115.06  5005.2  115.56  5009.9  115.64
  5027.3   125.4  5033.1   125.4  5045.3  130.05  5060.1  132.71  5196.4  138.56
  5232.1  142.46  5246.8  145.51  5267.7   146.2  5297.2  150.01    5339  151.87
  5347.6  153.45  5368.4  152.26  5383.2  154.93  5448.3  153.64  5523.2  162.19
#Mann= 3 ,-1 , 0
  4339.1     .12       0  4993.8     .05       0  5005.2     .12       0
Bank Sta=4993.8,5005.2
XS Rating Curve= 0 ,0
Exp/Cntr=0.3,0.1

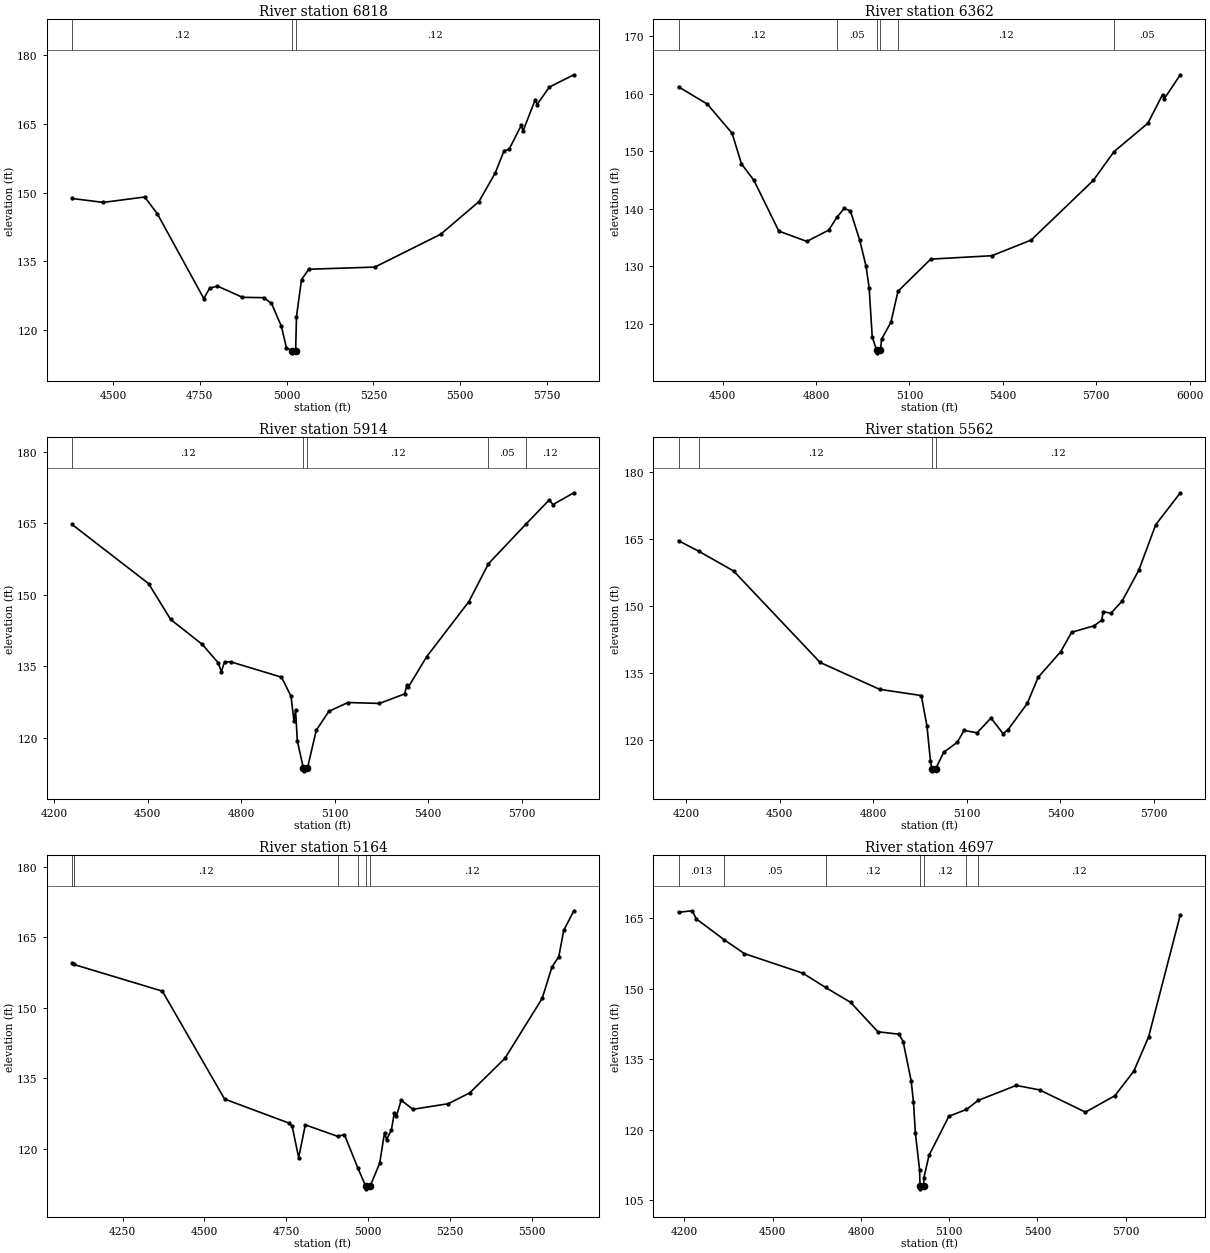
Type RM Length L Ch R = 1 ,6818    ,456,456,456
BEGIN DESCRIPTION:
Mapping XS 51362b1a
END DESCRIPTION:
XS GIS Cut Line= 4
      2537368.43     13545000.17      2537889.23     13545264.04
      2538031.59     13545448.07      2538639.25      13545607.8
#Sta/Elev= 30
  4382.3  148.71  4472.1  147.86  4591.5  149.04    4628  145.36  4761.6  126.92
  4778.3  129.15  4800.6  129.64    4873  127.18  4934.2  127.11  4956.5  125.88
    4985  120.87  4999.5  116.19  5014.6  115.59  5015.1  115.09    5026  115.59
  5028.5     123    5043  131.05  5063.8   133.3    5254  133.77  5443.9  140.93
  5553.9  148.04  5600.1  154.18  5626.3  159.11  5640.4  159.39  5675.6  164.64
  5680.8  163.41  5715.9  170.25  5721.1  169.17  5756.3  172.98  5827.1  175.66
#Mann= 3 ,-1 , 0
  4382.3     .12       0  5014.6     .05       0    5026     .12       0
Bank Sta=5014.6,5026
XS Rating Curve= 0 ,0
Exp/Cntr=0.3,0.1

Type RM Length L Ch R = 1 ,6362    ,448,448,448
BEGIN DESCRIPTION:
Mapping XS 6ae10db7
END DESCRIPTION:
XS GIS Cut Line= 3
        2536983.     13545486.27      2537746.87     13545520.99
      2538579.97       13545680.
#Sta/Elev= 30
  4357.7  161.16  4449.8  158.18  4529.9  153.09  4559.9  147.77  4599.9  144.91
    4680  136.07  4770.1  134.28  4840.2  136.24  4866.4  138.44  4890.2  140.04
  4910.3  139.55  4940.3  134.44  4960.3  129.98  4970.3  126.22  4980.3  117.64
  4994.2   115.4  4994.7   114.9  5006.6   115.4  5010.4  117.28  5040.4  120.23
    5063  125.61  5168.3   131.2  5364.8  131.79  5491.2  134.52  5690.6  144.88
  5757.5   149.9  5866.3  154.83  5913.3   159.8  5918.4  159.05  5970.5  163.26
#Mann= 6 ,-1 , 0
  4357.7     .12       0  4866.4     .05       0  4994.2     .05       0
  5006.6     .05       0    5063     .12       0  5757.5     .05       0
Bank Sta=4994.2,5006.6
XS Rating Curve= 0 ,0
Exp/Cntr=0.3,0.1

Type RM Length L Ch R = 1 ,5914    ,352,352,352
BEGIN DESCRIPTION:
Mapping XS 5e2ece4a
END DESCRIPTION:
XS GIS Cut Line= 3
       2536993.6     13545806.79       2537714.1     13545932.66
      2538581.04     13545798.29
#Sta/Elev= 30
    4258  164.78  4503.1  152.38  4574.1  144.84  4675.6   139.6  4726.4  135.75
  4736.5   133.9  4746.7   135.9    4767  135.94  4929.4  132.73  4959.9  128.73
  4969.4  123.53  4974.5  125.82  4980.2  119.33  4999.9  113.57  5000.4  113.07
  5012.4  113.57  5040.9   121.6  5081.4  125.56  5142.3  127.41  5243.3  127.22
  5324.3  129.21  5331.3  131.13  5336.3  130.67  5394.3  136.98  5530.4  148.61
  5592.8  156.53  5713.4  164.88  5787.5  169.91  5799.9  168.96  5866.7  171.43
#Mann= 5 ,-1 , 0
    4258     .12       0  4999.9     .05       0  5012.4     .12       0
  5592.8     .05       0  5713.4     .12       0
Bank Sta=4999.9,5012.4
XS Rating Curve= 0 ,0
Exp/Cntr=0.3,0.1

Type RM Length L Ch R = 1 ,5562    ,398,398,398
BEGIN DESCRIPTION:
Mapping XS 18575bb2
END DESCRIPTION:
XS GIS Cut Line= 3
      2537063.03     13546327.63      2537835.63      13546249.5
      2538608.18     13545937.01
#Sta/Elev= 30
  4174.9  164.57    4241  162.17  4351.5   157.8  4629.2  137.34  4820.1  131.33
  4953.8  129.94  4971.9  123.13  4983.1  115.33  4987.6   113.6  4988.1   113.1
  5000.2   113.6  5025.5  117.24  5069.4   119.5    5091  122.14  5132.8   121.6
  5177.3  124.91  5215.9  121.44  5231.2  122.23  5293.7  128.17  5328.6  134.02
  5400.9  139.73  5436.2  144.09  5508.2  145.55  5532.3  146.77  5537.7  148.73
  5561.9  148.32    5598  151.07  5651.9  158.03  5705.9  168.15  5784.8  175.29
#Mann= 4 ,-1 , 0
  4174.9     .05       0    4241     .12       0  4987.6     .05       0
  5000.2     .12       0
Bank Sta=4987.6,5000.2
XS Rating Curve= 0 ,0
Exp/Cntr=0.3,0.1

Type RM Length L Ch R = 1 ,5164    ,467,467,467
BEGIN DESCRIPTION:
Mapping XS 49fb349b
END DESCRIPTION:
XS GIS Cut Line= 3
      2537323.52     13546640.12      2538122.09     13546501.24
      2538716.72     13546093.24
#Sta/Elev= 30
    4096  159.48  4100.4  159.23  4371.6  153.53  4561.5  130.57  4757.3  125.48
  4767.4   124.9  4787.7  118.12    4808  125.08  4906.6  122.64  4927.3  123.01
  4967.7  116.01  4992.7  111.97  4993.2  111.47  5005.4  111.97  5034.9  116.89
  5049.8  123.41  5055.9  121.96  5070.8     124  5079.7  127.67  5085.7  126.89
  5100.6  130.32  5136.5  128.39  5244.1  129.58  5309.8  131.88  5417.4  139.24
    5531  151.99  5560.8  158.65  5581.8  160.89  5596.7  166.45  5627.7  170.63
#Mann= 6 ,-1 , 0
    4096     .05       0  4100.4     .12       0  4906.6     .05       0
  4967.7     .12       0  4992.7     .05       0  5005.4     .12       0
Bank Sta=4992.7,5005.4
XS Rating Curve= 0 ,0
Exp/Cntr=0.3,0.1

Type RM Length L Ch R = 1 ,4697    ,291,291,291
BEGIN DESCRIPTION:
Mapping XS 1879dfc7
END DESCRIPTION:
XS GIS Cut Line= 3
      2537557.84     13547412.71      2538213.23     13546865.82
      2538725.37     13546184.42
#Sta/Elev= 30
  4179.9   166.3  4226.4  166.62  4240.7  164.87  4335.3  160.45  4403.4  157.52
  4602.5  153.34  4679.6  150.31  4765.2  147.12  4857.6  140.87  4929.2  140.36
  4943.5  138.79  4970.9   130.4  4978.7  125.86  4985.2  119.29  4999.5  111.47
  5000.9  107.95  5001.4  107.45  5013.7  107.95  5013.8  109.75  5031.4  114.56
    5099  122.89  5158.9  124.35  5198.3  126.26  5328.1  129.46  5407.2   128.5
  5563.5  123.77  5663.4  127.27    5728  132.52    5778  139.78  5885.9  165.79
#Mann= 7 ,-1 , 0
  4179.9    .013       0  4335.3     .05       0  4679.6     .12       0
  5000.9     .05       0  5013.7     .12       0  5158.9     .05       0
  5198.3     .12       0
Bank Sta=5000.9,5013.7
XS Rating Curve= 0 ,0
Exp/Cntr=0.3,0.1

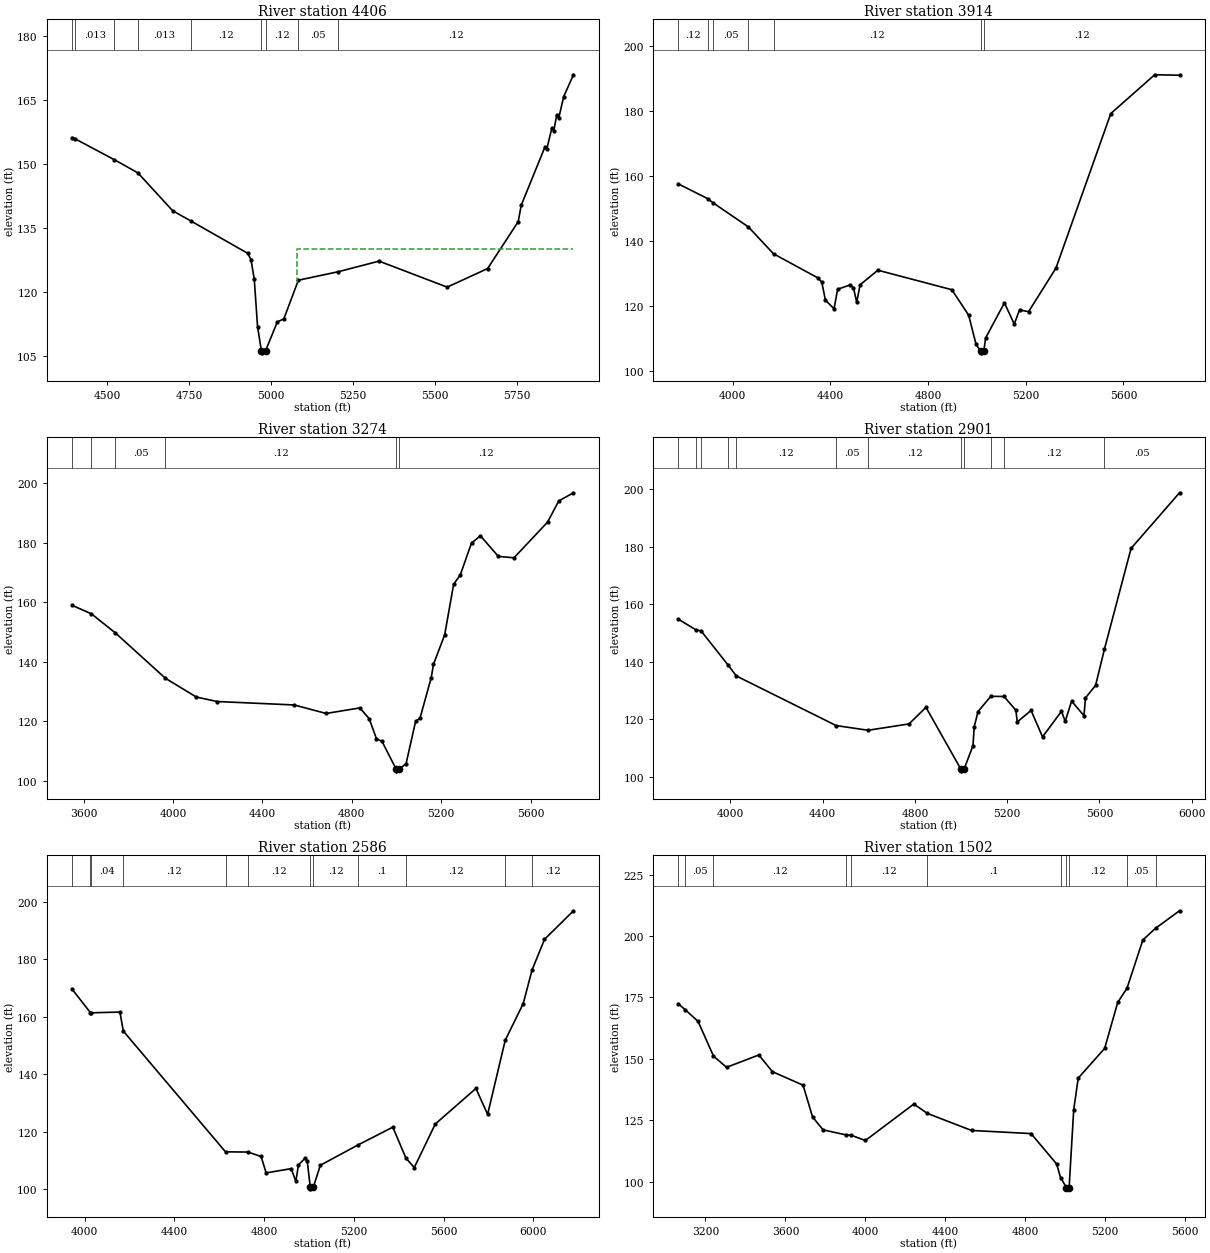
Type RM Length L Ch R = 1 ,4406    ,492,492,492
BEGIN DESCRIPTION:
Mapping XS 80616c1f
END DESCRIPTION:
XS GIS Cut Line= 4
       2537996.2     13547373.64      2538404.21     13547074.16
      2538430.25     13546713.91      2538794.84     13546162.68
#Sta/Elev= 30
  4393.3  156.19  4402.8  155.89  4521.8  151.02  4594.2   147.9  4699.7  139.04
  4754.6  136.66  4928.7  129.03  4938.7  127.53  4948.7  122.92  4958.7  111.84
  4970.3  106.18  4970.8  105.68  4983.2  106.18  5018.9  112.93  5038.9  113.66
    5083  122.72  5204.9  124.72    5329   127.2  5536.6   121.1  5659.9  125.46
  5753.2  136.47  5762.3  140.32  5834.5  153.97  5840.5   153.6  5855.6   158.4
  5861.6  157.77  5870.6   161.6  5876.6  160.75  5891.7  165.81  5921.5  170.93
#Mann= 9 ,-1 , 0
  4393.3     .12       0  4402.8    .013       0  4521.8     .05       0
  4594.2    .013       0  4754.6     .12       0  4970.3     .05       0
  4983.2     .12       0    5083     .05       0  5204.9     .12       0
#XS Ineff= 2 , 0
       0                    5080       0     130
Permanent Ineff=
       F       F
Bank Sta=4970.3,4983.2
XS Rating Curve= 0 ,0
Exp/Cntr=0.3,0.1

Type RM Length L Ch R = 1 ,3914    ,640,640,640
BEGIN DESCRIPTION:
Mapping XS 53953be6
END DESCRIPTION:
XS GIS Cut Line= 4
      2537983.19     13547425.73      2538794.83     13546835.44
       2538651.6     13546449.16      2538933.72     13545876.23
#Sta/Elev= 30
  3775.7  157.71  3896.5  153.15  3918.4  151.88  4063.6  144.44  4166.6  136.16
  4349.7  128.68  4364.4  127.42  4379.1  121.92  4414.6  119.21  4429.3  125.24
  4479.5  126.55  4494.2  125.73  4507.5  121.22  4521.3   126.6    4594   131.1
  4897.1   125.1  4966.1  117.25  4996.5  108.24  5015.1  106.16  5015.6  105.66
    5028  106.16  5035.7  110.26  5112.7  121.05    5153   114.5  5174.4  118.88
  5211.5  118.33  5323.8  131.76  5548.4  179.34  5728.2  191.28  5829.9  191.15
#Mann= 7 ,-1 , 0
  3775.7     .12       0  3896.5    .013       0  3918.4     .05       0
  4063.6    .013       0  4166.6     .12       0  5015.1     .05       0
    5028     .12       0
Bank Sta=5015.1,5028
XS Rating Curve= 0 ,0
Exp/Cntr=0.3,0.1

Type RM Length L Ch R = 1 ,3274    ,373,373,373
BEGIN DESCRIPTION:
Mapping XS 13cf30ff
END DESCRIPTION:
XS GIS Cut Line= 3
      2538017.91     13547503.85      2539124.69     13546709.57
      2539159.38     13545829.25
#Sta/Elev= 30
  3548.4  159.01  3635.3  156.13  3742.7  149.69    3966  134.48  4104.4  128.17
  4197.2  126.66  4541.8   125.5  4685.2  122.64  4836.2  124.51    4878  120.85
  4910.3  114.16  4935.3  113.22  4998.9  103.85  4999.4  103.35  5011.8  103.85
  5042.9   105.8  5085.4  119.95  5105.4  121.13  5155.5  134.71  5165.5  139.17
  5215.5  149.07  5255.5  166.02  5285.6  169.28  5335.6  179.95  5375.6  182.37
  5455.7  175.44  5525.7  174.99  5675.9  186.97  5725.9   194.1  5791.7  196.84
#Mann= 6 ,-1 , 0
  3548.4     .05       0  3635.3     .12       0  3742.7     .05       0
    3966     .12       0  4998.9     .05       0  5011.8     .12       0
Bank Sta=4998.9,5011.8
XS Rating Curve= 0 ,0
Exp/Cntr=0.3,0.1

Type RM Length L Ch R = 1 ,2901    ,315,315,315
BEGIN DESCRIPTION:
Mapping XS e045d775
END DESCRIPTION:
XS GIS Cut Line= 3
      2538204.53     13547590.66      2539259.24     13546948.29
      2539701.74     13546119.68
#Sta/Elev= 30
  3773.1  154.91  3848.9  151.22  3872.9  150.77    3990  138.89  4025.7   135.1
  4458.6  117.84  4596.9  116.21  4774.4  118.41    4848  124.18  4999.9  102.59
  5000.4  102.09  5012.9  102.59  5051.8  110.86  5057.4   117.5  5073.7   122.7
  5128.9  128.01  5186.7  127.96    5238  123.15  5243.7  119.09  5303.8  123.11
  5353.4  113.91  5435.6   122.8  5451.8  119.31  5479.5  126.35  5533.2  121.27
  5539.6  127.47  5583.5  131.81    5622  144.46  5737.3  179.48  5947.4  198.84
#Mann= 12 ,-1 , 0
  3773.1     .12       0  3848.9     .05       0  3872.9     .12       0
    3990     .05       0  4025.7     .12       0  4458.6     .05       0
  4596.9     .12       0  4999.9     .05       0  5012.9     .12       0
  5128.9      .1       0  5186.7     .12       0    5622     .05       0
Bank Sta=4999.9,5012.9
XS Rating Curve= 0 ,0
Exp/Cntr=0.3,0.1

Type RM Length L Ch R = 1 ,2586    ,1084,1084,1084
BEGIN DESCRIPTION:
Mapping XS f658aeb1
END DESCRIPTION:
XS GIS Cut Line= 4
      2539181.11     13548254.71      2539389.45      13547165.3
      2539406.81      13546787.7      2539797.35     13546149.81
#Sta/Elev= 30
  3943.4  169.56  4025.4  161.39  4026.2  161.32  4156.9  161.59  4171.9  154.97
  4627.5  112.92  4727.3  112.85  4786.2   111.3  4808.5  105.58  4920.5  107.08
  4940.9  102.64  4952.6  108.35  4981.6  110.68  4991.8  109.71  5005.5  100.54
    5006  100.04  5018.7  100.54  5050.2  108.25  5217.2  115.28  5373.2  121.52
  5431.8  110.71  5468.9  107.45  5562.7  122.62  5743.8  134.99  5795.9  125.96
  5874.3  151.76  5954.6  164.55  5993.9  176.22  6049.4  186.89  6178.5  196.85
#Mann= 12 ,-1 , 0
  3943.4     .04       0  4025.4     .05       0  4026.2     .04       0
  4171.9     .12       0  4627.5     .05       0  4727.3     .12       0
  5005.5     .05       0  5018.7     .12       0  5217.2      .1       0
  5431.8     .12       0  5874.3     .05       0  5993.9     .12       0
Bank Sta=5005.5,5018.7
XS Rating Curve= 0 ,0
Exp/Cntr=0.3,0.1

Type RM Length L Ch R = 1 ,1502    ,0,0,0
BEGIN DESCRIPTION:
Mapping XS 926eb0c9
END DESCRIPTION:
XS GIS Cut Line= 5
      2539237.52     13548337.22      2539680.25     13547286.83
      2539758.37     13546965.65      2540131.57     13546632.69
      2540387.27     13546159.18
#Sta/Elev= 30
  3063.2  172.47  3099.6  169.93  3163.3  165.23  3240.2  151.13  3305.5  146.54
  3467.1  151.57  3535.3  144.77  3688.5  139.27    3736  126.33  3788.9  121.08
    3903  119.06  3928.1  118.94  4000.4  116.77  4242.7   131.6    4311  127.76
  4531.4  120.85  4829.1  119.58    4957  107.21    4977  101.64  5006.4   97.59
  5006.9   97.09  5019.7   97.59  5042.5  129.22  5065.2  142.15  5197.4  154.25
    5263  173.01  5308.9  178.68  5388.7  198.41  5452.4  203.16  5571.9  210.26
#Mann= 11 ,-1 , 0
  3063.2     .04       0  3099.6     .05       0  3240.2     .12       0
    3903     .05       0  3928.1     .12       0    4311      .1       0
    4977     .12       0  5006.4     .05       0  5019.7     .12       0
  5308.9     .05       0  5452.4     .12       0
Bank Sta=5006.4,5019.7
XS Rating Curve= 0 ,0
Exp/Cntr=0.3,0.1

Chan Stop Cuts=-1
Use User Specified Reach Order=0
Composite Channel Slope=5