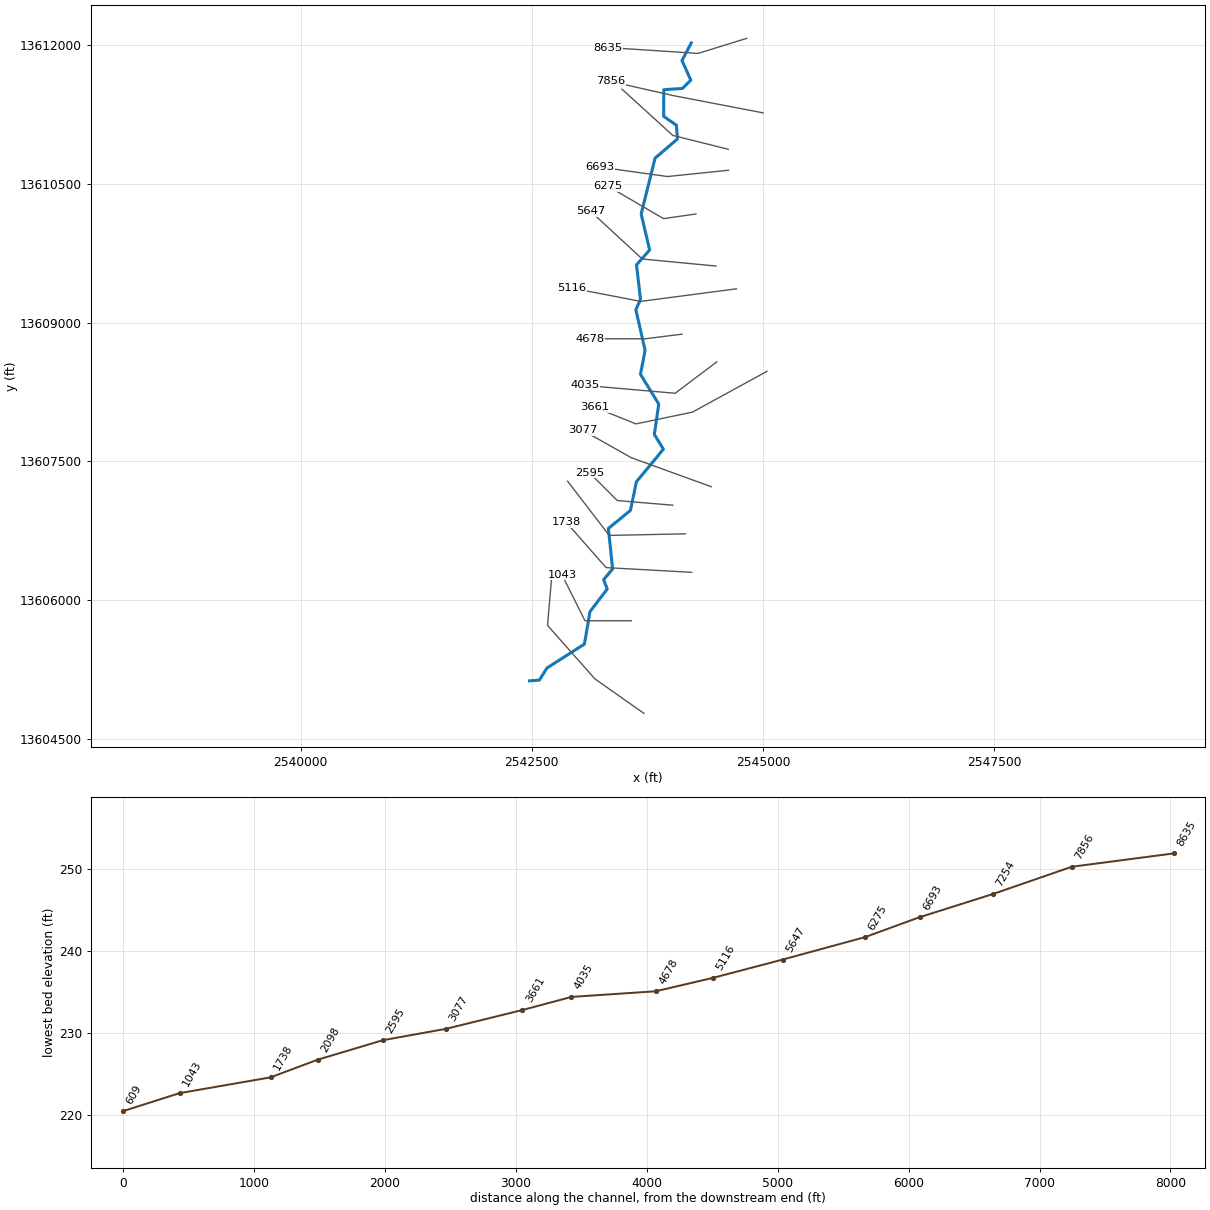
--- TRIB 12 TO IRISH CREEK.prj (project) ---

Proj Title=TRIB 12 TO IRISH CREEK Base Level Engineering
Current Plan=p01
Default Exp/Contr=0.3,0.1
English Units
Geom File=g01
Flow File=f01
Plan File=p01
Y Axis Title=Elevation
X Axis Title(PF)=Main Channel Distance
X Axis Title(XS)=Station
BEGIN DESCRIPTION:
TRIB 12 TO IRISH CREEK
END DESCRIPTION:
DSS Export Rating Curves= 0
DSS Export Rating Curve Sorted= 0
DSS Export Volume Flow Curves= 0
DXF OffsetX= 0
DXF OffsetY= 0
DXF ScaleX= 1
DXF ScaleY= 10

--- TRIB 12 TO IRISH CREEK.p01 (plan) ---

Plan Title=Multiple Run
Short Identifier=Multiple
Geom File=g01
Flow File=f01
Subcritical Flow
K Sum by GR= 0
Std Step Tol= 0.01
Critical Tol= 0.01
Num of Std Step Trials= 20
Max Error Tol= 0.3
Flow Tol Ratio= 0.001
Split Flow NTrial= 30
Split Flow Tol= 0.02
Split Flow Ratio= 0.02
Log Output Level= 0
Friction Slope Method= 1
Unsteady Friction Slope Method= 2
Unsteady Bridges Friction Slope Method= 1
Parabolic Critical Depth
Global Vel Dist=  1 , 1 , 1
Global Log Level= 0
CheckData=True
Encroach Param= -1, 0, 0, 0
BEGIN DESCRIPTION:
Multiple Run
END DESCRIPTION:

--- TRIB 12 TO IRISH CREEK.f01 (steady flow) ---

Flow Title=Multiple
Number of Profiles=7
Profile Names=10-year,25-year,50-year,1pct_min,100-year,1pct_plu,500-year
River Rch & RM= TRIB 12 TO IRISH,Reach-1,8635
     482     757     998     639    1275    2545    2057
River Rch & RM= TRIB 12 TO IRISH,Reach-1,7254
     698    1119    1498     971    1937    3865    3206
Boundary for River Rch & Prof#=TRIB 12 TO IRISH,Reach-1,1
Up Type=0
Dn Type=3
Dn Slope=0.005
Boundary for River Rch & Prof#=TRIB 12 TO IRISH,Reach-1,2
Up Type=0
Dn Type=3
Dn Slope=0.005
Boundary for River Rch & Prof#=TRIB 12 TO IRISH,Reach-1,3
Up Type=0
Dn Type=3
Dn Slope=0.005
Boundary for River Rch & Prof#=TRIB 12 TO IRISH,Reach-1,4
Up Type=0
Dn Type=3
Dn Slope=0.005
Boundary for River Rch & Prof#=TRIB 12 TO IRISH,Reach-1,5
Up Type=0
Dn Type=3
Dn Slope=0.005
Boundary for River Rch & Prof#=TRIB 12 TO IRISH,Reach-1,6
Up Type=0
Dn Type=3
Dn Slope=0.005
Boundary for River Rch & Prof#=TRIB 12 TO IRISH,Reach-1,7
Up Type=0
Dn Type=3
Dn Slope=0.005

--- TRIB 12 TO IRISH CREEK.g01 (geometry) ---

Geom Title=Existing Conditions

River Reach=TRIB 12 TO IRISH,Reach-1
Reach XY= 30
      2544225.00     13612025.00      2544124.20     13611835.05
      2544219.94     13611622.68      2544128.35     13611532.98
      2543927.05     13611519.54      2543926.58     13611230.87
      2544063.89     13611135.32      2544074.36     13610985.64
      2543832.89     13610778.58      2543682.53     13610175.01
      2543774.40     13609785.62      2543632.35     13609625.09
      2543675.39     13609250.00      2543625.10     13609140.40
      2543725.23     13608700.07      2543675.25     13608440.22
      2543872.95     13608119.14      2543825.37     13607790.17
      2543923.41     13607631.05      2543630.47     13607277.45
      2543567.14     13606968.83      2543328.04     13606773.58
      2543373.94     13606335.44      2543276.67     13606218.95
      2543315.85     13606118.27      2543128.75     13605873.45
      2543069.17     13605522.70      2542664.90     13605264.61
      2542581.54     13605132.60      2542475.00     13605125.00

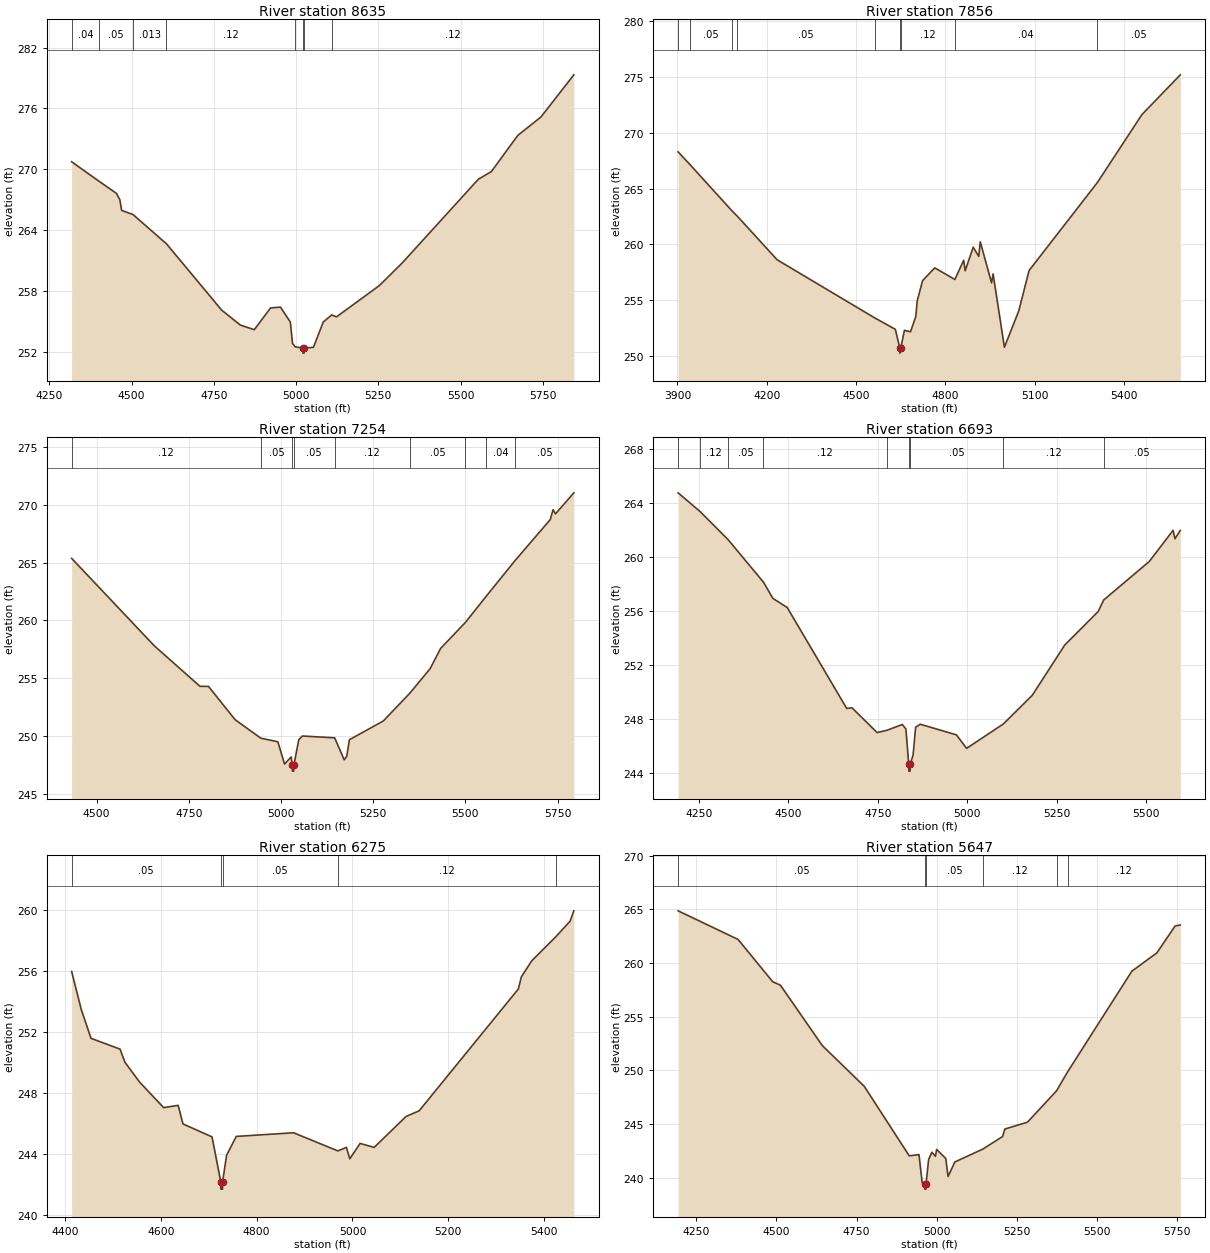
Type RM Length L Ch R = 1,8635,779,779,779
BEGIN DESCRIPTION:
TRIB 12 TO IRISH CREEK 15.0
END DESCRIPTION:
XS GIS Cut Line= 3
      2544824.97     13612074.99      2544298.87     13611912.13
      2543325.03     13611975.00
#Sta/Elev= 30
  4317.7  270.75  4401.9  268.81  4453.8  267.64  4464.2  267.01  4469.7  265.96
  4504.0  265.56  4606.0  262.67  4773.6  256.15  4830.6  254.67  4872.9  254.22
  4922.4  256.36  4952.5  256.44  4982.5  254.97  4989.1  252.87  4997.3  252.53
  5020.6  252.41  5020.9  251.91  5024.4  251.91  5024.6  252.41  5052.7  252.48
  5082.7  254.98  5108.4  255.67  5122.8  255.48  5253.1  258.56  5323.2  260.81
  5553.7  269.02  5593.8  269.79  5674.0  273.35  5744.1  275.15  5844.3  279.31
#Mann=8,-1,0
  4317.7    0.04       0  4401.9    0.05       0  4504.0   0.013       0
  4606.0    0.12       0  4997.3    0.03       0  5020.6    0.03       0
  5024.6    0.03       0  5108.4    0.12       0
Bank Sta=5020.6,5024.6
Exp/Cntr=0.3,0.1

Type RM Length L Ch R = 1,7856,602,602,602
BEGIN DESCRIPTION:
Mapping XS 897344ba
END DESCRIPTION:
XS GIS Cut Line= 3
      2545001.79     13611268.88      2544026.23     13611456.32
      2543349.46     13611609.55
#Sta/Elev= 30
  3902.3  268.29  3941.8  267.16  4083.3  263.01  4100.9  262.54  4235.1  258.63
  4562.4  253.44  4632.2  252.41  4646.8  250.78  4647.1  250.28  4650.8  250.78
  4662.7  252.32  4683.1  252.19  4700.8  253.55  4705.9  254.99  4723.8  256.77
  4764.6  257.91  4832.2  256.87  4861.8  258.59  4866.8  257.65  4893.8  259.76
  4912.4  258.94  4917.5  260.24  4955.5  256.57  4960.6  257.37  4998.6  250.81
  5046.9  254.06  5081.5  257.67  5311.1  265.55  5460.9  271.63  5589.6  275.18
#Mann=9,-1,0
  3902.3    0.04       0  3941.8    0.05       0  4083.3    0.12       0
  4100.9    0.05       0  4562.4    0.12       0  4646.8    0.04       0
  4650.8    0.12       0  4832.2    0.04       0  5311.1    0.05       0
Bank Sta=4646.8,4650.8
Exp/Cntr=0.3,0.1

Type RM Length L Ch R = 1,7254,561,561,561
BEGIN DESCRIPTION:
TRIB 12 TO IRISH CREEK 13.0
END DESCRIPTION:
XS GIS Cut Line= 3
      2544625.04     13610874.99      2544025.00     13611025.00
      2543475.01     13611525.00
#Sta/Elev= 30
  4432.4  265.36  4656.6  257.79  4780.3  254.29  4803.5  254.28  4875.7  251.40
  4945.4  249.80  4991.6  249.49  5009.7  247.56  5027.7  248.18  5030.9  247.45
  5031.1  246.95  5034.6  246.95  5034.9  247.45  5048.3  249.66  5058.0  249.99
  5145.6  249.83  5171.5  247.93  5178.3  248.23  5185.7  249.67  5277.6  251.29
  5349.7  253.70  5404.6  255.82  5433.0  257.57  5500.0  259.81  5556.3  262.07
  5635.1  265.18  5730.4  268.72  5737.8  269.57  5744.5  269.21  5794.2  271.03
#Mann=9,-1,0
  4432.4    0.12       0  4945.4    0.05       0  5030.9    0.05       0
  5034.9    0.05       0  5145.6    0.12       0  5349.7    0.05       0
  5500.0    0.12       0  5556.3    0.04       0  5635.1    0.05       0
Bank Sta=5030.9,5034.9
Exp/Cntr=0.3,0.1

Type RM Length L Ch R = 1,6693,418,418,418
BEGIN DESCRIPTION:
Mapping XS 2866945f
END DESCRIPTION:
XS GIS Cut Line= 3
      2544628.37     13610648.13      2543965.77     13610580.17
      2543235.22     13610682.11
#Sta/Elev= 30
  4191.8  264.76  4252.9  263.38  4331.8  261.28  4430.4  258.13  4456.6  256.93
  4496.8  256.25  4663.1  248.76  4677.7  248.81  4748.1  246.97  4775.4  247.14
  4818.4  247.57  4828.5  247.24  4836.5  244.61  4836.8  244.11  4840.3  244.11
  4840.5  244.61  4848.6  245.31  4855.7  247.37  4868.8  247.59  4969.7  246.80
  4998.2  245.80  5100.9  247.61  5181.8  249.74  5272.6  253.47  5365.9  255.95
  5381.4  256.81  5508.9  259.67  5575.4  261.98  5580.4  261.35  5595.5  261.97
#Mann=9,-1,0
  4191.8    0.05       0  4252.9    0.12       0  4331.8    0.05       0
  4430.4    0.12       0  4775.4    0.05       0  4836.5    0.05       0
  4840.5    0.05       0  5100.9    0.12       0  5381.4    0.05       0
Bank Sta=4836.5,4840.5
Exp/Cntr=0.3,0.1

Type RM Length L Ch R = 1,6275,628,628,628
BEGIN DESCRIPTION:
TRIB 12 TO IRISH CREEK 11.0
END DESCRIPTION:
XS GIS Cut Line= 3
      2544275.04     13610175.01      2543925.00     13610125.00
      2543325.01     13610474.99
#Sta/Elev= 30
  4413.9  255.96  4434.1  253.45  4454.3  251.57  4515.0  250.86  4525.1  250.00
  4555.4  248.71  4605.9  247.02  4636.2  247.17  4646.3  245.95  4706.9  245.10
  4725.1  242.17  4725.3  241.67  4728.8  241.67  4729.1  242.17  4737.2  243.88
  4757.4  245.13  4877.1  245.37  4969.5  244.18  4987.5  244.41  4994.5  243.66
  5016.0  244.67  5045.3  244.41  5111.9  246.44  5139.2  246.81  5346.3  254.81
  5352.5  255.60  5374.0  256.65  5425.7  258.28  5454.3  259.26  5462.1  259.94
#Mann=5,-1,0
  4413.9    0.05       0  4725.1    0.05       0  4729.1    0.05       0
  4969.5    0.12       0  5425.7    0.05       0
Bank Sta=4725.1,4729.1
Exp/Cntr=0.3,0.1

Type RM Length L Ch R = 1,5647,531,531,531
BEGIN DESCRIPTION:
Mapping XS 71210b1a
END DESCRIPTION:
XS GIS Cut Line= 3
      2544492.46     13609611.80      2543693.95     13609688.26
      2543133.30     13610206.43
#Sta/Elev= 30
  4193.7  264.87  4380.8  262.20  4488.5  258.26  4512.6  257.94  4643.2  252.31
  4773.8  248.52  4914.4  242.03  4944.6  242.15  4954.6  239.54  4962.7  239.43
  4962.9  238.93  4966.4  238.93  4966.7  239.43  4974.7  241.70  4984.8  242.37
  4995.9  241.99  4999.8  242.63  5028.2  241.78  5035.3  240.11  5056.5  241.46
  5143.5  242.66  5205.1  243.83  5212.3  244.53  5282.8  245.17  5373.5  248.09
  5408.8  249.90  5608.2  259.24  5686.5  260.96  5743.2  263.46  5759.3  263.55
#Mann=6,-1,0
  4193.7    0.05       0  4962.7    0.05       0  4966.7    0.05       0
  5143.5    0.12       0  5373.5    0.05       0  5408.8    0.12       0
Bank Sta=4962.7,4966.7
Exp/Cntr=0.3,0.1

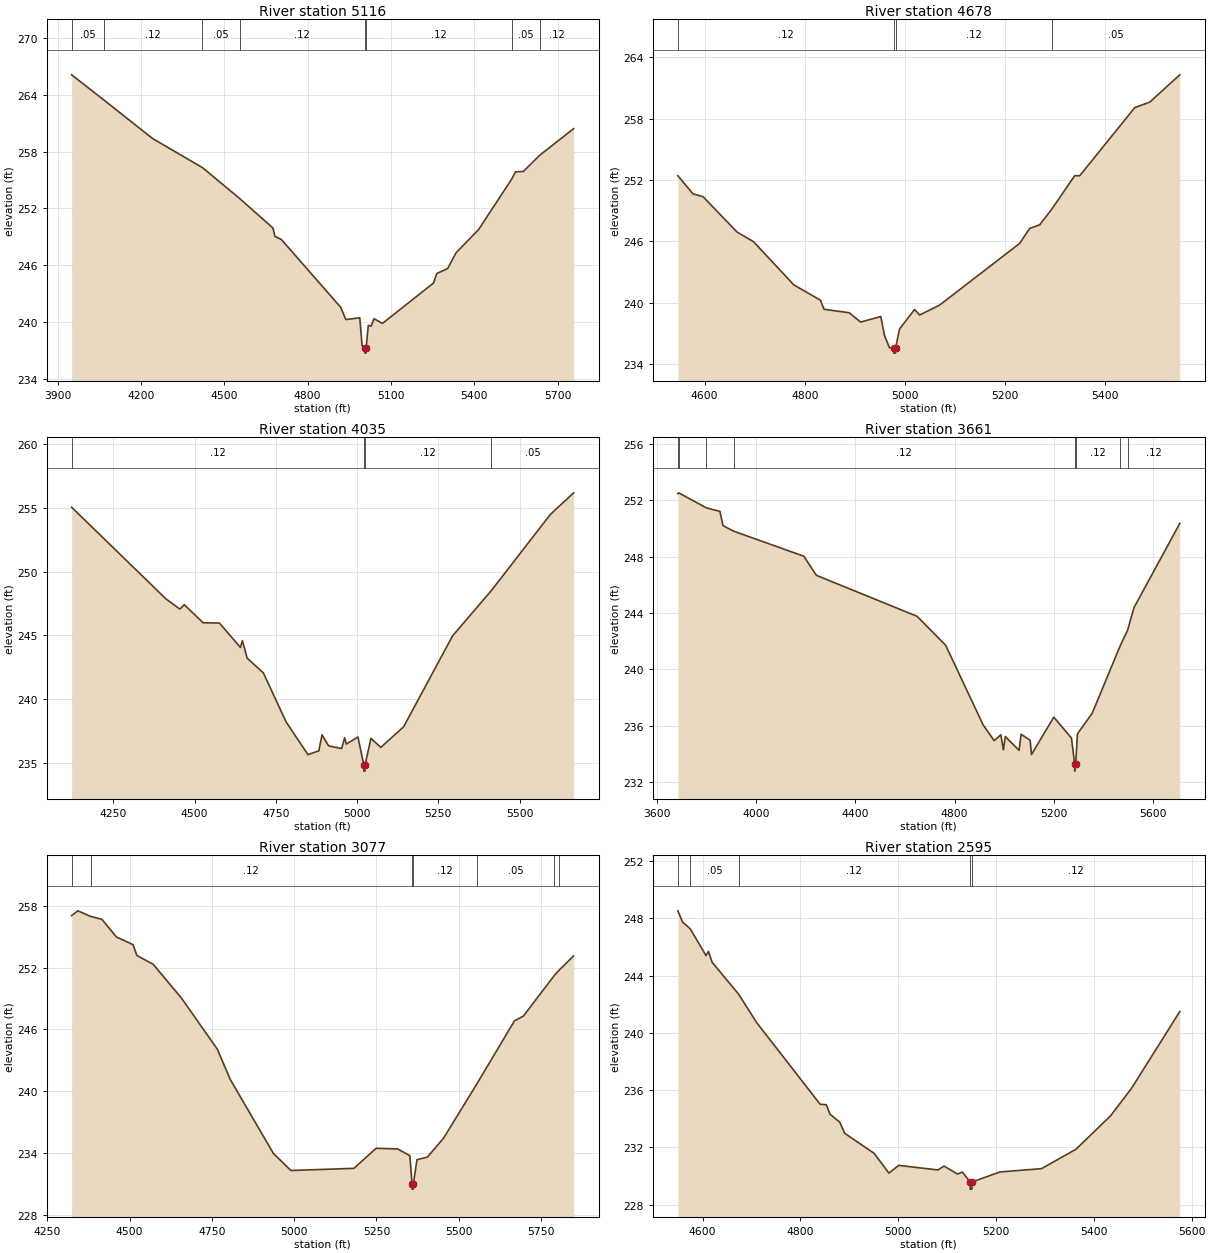
Type RM Length L Ch R = 1,5116,438,438,438
BEGIN DESCRIPTION:
Mapping XS 4aea3723
END DESCRIPTION:
XS GIS Cut Line= 3
      2544713.33     13609365.47      2543676.96     13609229.56
      2542929.72     13609373.91
#Sta/Elev= 30
  3950.6  266.11  4065.3  263.48  4241.4  259.39  4421.5  256.30  4555.3  253.04
  4675.1  249.92  4682.5  249.03  4705.3  248.71  4918.9  241.54  4937.3  240.25
  4987.6  240.43  4995.8  237.49  5006.0  237.20  5006.3  236.70  5009.8  236.70
  5010.0  237.20  5018.2  239.63  5028.4  239.55  5038.6  240.34  5069.1  239.84
  5252.5  244.10  5264.8  245.12  5303.4  245.63  5333.9  247.30  5415.1  249.76
  5534.3  255.10  5547.8  255.86  5575.7  255.89  5635.0  257.61  5756.9  260.42
#Mann=8,-1,0
  3950.6    0.05       0  4065.3    0.12       0  4421.5    0.05       0
  4555.3    0.12       0  5006.0    0.05       0  5010.0    0.12       0
  5534.3    0.05       0  5635.0    0.12       0
Bank Sta=5006,5010
Exp/Cntr=0.3,0.1

Type RM Length L Ch R = 1,4678,643,643,643
BEGIN DESCRIPTION:
TRIB 12 TO IRISH CREEK 8.0
END DESCRIPTION:
XS GIS Cut Line= 3
      2544125.00     13608875.00      2543725.00     13608825.00
      2543125.02     13608825.00
#Sta/Elev= 30
  4546.5  252.43  4576.7  250.65  4596.9  250.37  4664.9  246.91  4697.7  245.97
  4778.3  241.74  4831.2  240.25  4838.8  239.35  4889.1  239.01  4911.8  238.10
  4952.1  238.64  4959.6  236.76  4969.6  235.58  4977.6  235.56  4977.9  235.06
  4981.4  235.06  4981.6  235.56  4989.6  237.43  5019.6  239.33  5029.6  238.79
  5069.6  239.76  5229.6  245.80  5249.6  247.26  5269.6  247.62  5294.2  249.18
  5339.6  252.43  5349.6  252.42  5459.6  259.09  5489.6  259.63  5549.6  262.30
#Mann=4,-1,0
  4546.5    0.12       0  4977.6    0.05       0  4981.6    0.12       0
  5294.2    0.05       0
Bank Sta=4977.6,4981.6
Exp/Cntr=0.3,0.1

Type RM Length L Ch R = 1,4035,374,374,374
BEGIN DESCRIPTION:
Mapping XS bc829384
END DESCRIPTION:
XS GIS Cut Line= 3
      2544500.93     13608575.49      2544050.72     13608235.71
      2543073.85     13608320.65
#Sta/Elev= 30
  4121.8  255.04  4412.1  247.86  4455.0  247.06  4468.3  247.41  4526.6  245.99
  4576.6  245.97  4641.1  244.06  4647.3  244.59  4661.9  243.22  4711.7  242.07
  4781.9  238.22  4849.0  235.66  4882.3  235.96  4892.3  237.21  4912.4  236.35
  4952.6  236.14  4961.9  236.99  4967.0  236.49  5002.8  237.04  5020.8  234.87
  5021.1  234.37  5024.6  234.37  5024.8  234.87  5042.9  236.94  5073.0  236.23
  5143.3  237.84  5293.9  244.96  5413.6  248.52  5595.0  254.48  5666.4  256.17
#Mann=4,-1,0
  4121.8    0.12       0  5020.8    0.05       0  5024.8    0.12       0
  5413.6    0.05       0
Bank Sta=5020.8,5024.8
Exp/Cntr=0.3,0.1

Type RM Length L Ch R = 1,3661,584,584,584
BEGIN DESCRIPTION:
Mapping XS 8b25e699
END DESCRIPTION:
XS GIS Cut Line= 4
      2545044.54     13608473.54      2544237.60     13608031.84
      2543626.00     13607904.42      2543184.31     13608082.80
#Sta/Elev= 30
  3685.5  252.47  3689.0  252.53  3799.4  251.47  3854.9  251.21  3867.4  250.20
  3909.9  249.81  4192.5  248.03  4243.6  246.67  4648.9  243.76  4764.0  241.70
  4914.5  236.06  4959.1  234.93  4986.0  235.35  4996.2  234.28  5004.0  235.22
  5059.2  234.25  5067.7  235.39  5104.1  234.96  5109.2  233.94  5199.1  236.60
  5270.4  235.12  5283.2  233.27  5283.4  232.77  5287.2  233.27  5294.5  235.42
  5353.6  236.87  5466.1  241.65  5496.0  242.76  5522.4  244.39  5706.5  250.36
#Mann=8,-1,0
  3685.5    0.05       0  3689.0    0.04       0  3799.4    0.05       0
  3909.9    0.12       0  5283.2    0.05       0  5287.2    0.12       0
  5466.1    0.05       0  5496.0    0.12       0
Bank Sta=5283.2,5287.2
Exp/Cntr=0.3,0.1

Type RM Length L Ch R = 1,3077,482,482,482
BEGIN DESCRIPTION:
Mapping XS 6c28ee39
END DESCRIPTION:
XS GIS Cut Line= 3
      2544441.49     13607224.86      2543575.03     13607539.16
      2543049.14     13607836.03
#Sta/Elev= 30
  4323.7  257.06  4342.7  257.52  4381.4  256.98  4415.7  256.69  4459.8  254.98
  4510.4  254.23  4522.1  253.18  4571.7  252.32  4658.2  249.01  4766.7  244.06
  4806.0  241.12  4936.9  233.94  4990.1  232.28  5181.6  232.49  5249.1  234.44
  5314.3  234.38  5351.7  233.72  5358.3  230.97  5358.5  230.47  5362.0  230.47
  5362.3  230.97  5373.3  233.33  5405.2  233.59  5454.2  235.43  5556.3  240.75
  5669.4  246.82  5696.8  247.29  5791.1  251.25  5805.0  251.74  5849.3  253.14
#Mann=7,-1,0
  4323.7    0.05       0  4381.4    0.12       0  5358.3    0.05       0
  5362.3    0.12       0  5556.3    0.05       0  5791.1    0.12       0
  5805.0    0.05       0
Bank Sta=5358.3,5362.3
Exp/Cntr=0.3,0.1

Type RM Length L Ch R = 1,2595,497,497,497
BEGIN DESCRIPTION:
TRIB 12 TO IRISH CREEK 4.0
END DESCRIPTION:
XS GIS Cut Line= 3
      2544024.99     13607025.00      2543425.00     13607075.00
      2543125.03     13607374.97
#Sta/Elev= 30
  4549.5  248.53  4559.5  247.73  4574.7  247.28  4607.2  245.40  4612.2  245.69
  4619.7  244.93  4673.7  242.71  4710.0  240.75  4840.5  235.01  4853.0  234.98
  4860.6  234.32  4880.6  233.76  4890.7  232.98  4950.9  231.58  4981.0  230.20
  5001.1  230.74  5081.3  230.42  5093.9  230.69  5121.5  230.13  5131.5  230.27
  5147.1  229.58  5147.3  229.08  5150.8  229.08  5151.1  229.58  5208.1  230.28
  5293.0  230.51  5363.7  231.87  5434.4  234.21  5476.8  236.11  5575.8  241.49
#Mann=5,-1,0
  4549.5    0.12       0  4574.7    0.05       0  4673.7    0.12       0
  5147.1    0.05       0  5151.1    0.12       0
Bank Sta=5147.1,5151.1
Exp/Cntr=0.3,0.1

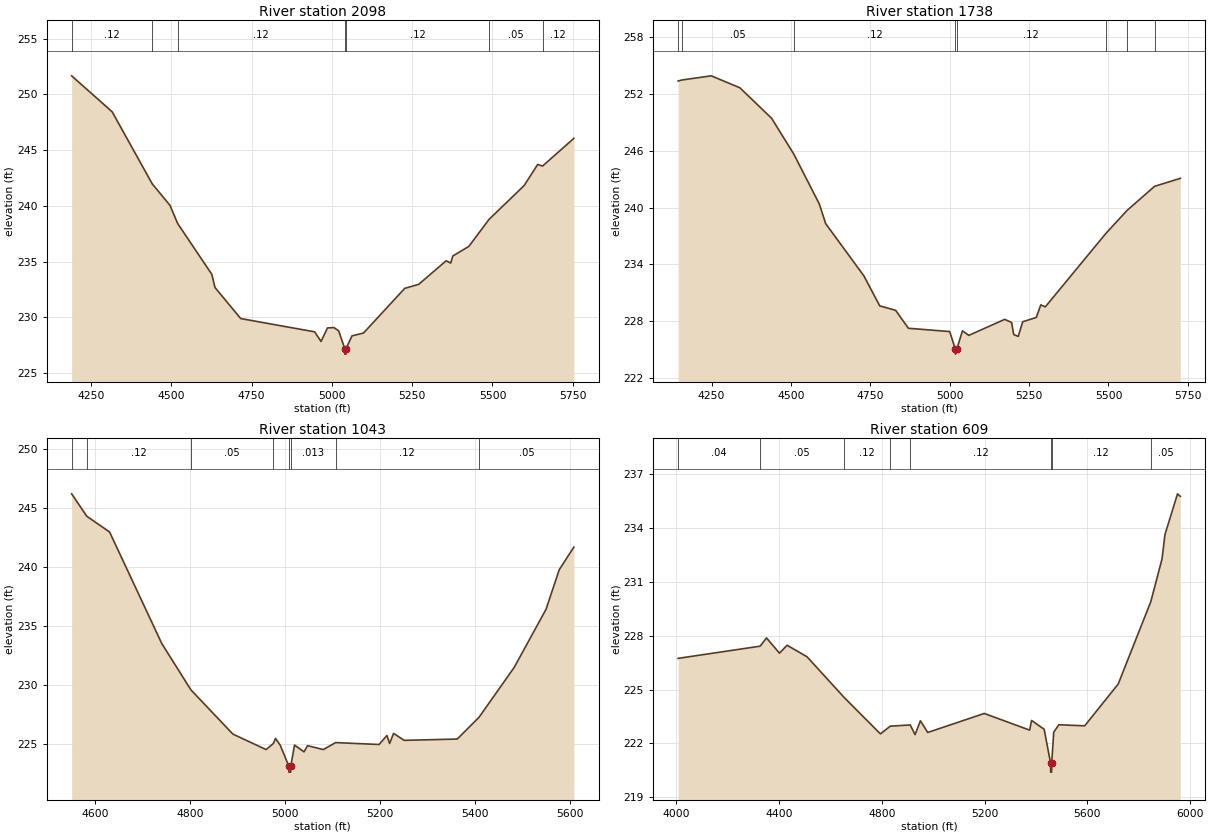
Type RM Length L Ch R = 1,2098,360,360,360
BEGIN DESCRIPTION:
Mapping XS 3d6fdd1f
END DESCRIPTION:
XS GIS Cut Line= 3
      2544161.18     13606715.20      2543337.18     13606698.21
      2542887.00     13607284.30
#Sta/Elev= 30
  4190.0  251.66  4316.2  248.43  4440.9  241.97  4496.2  240.04  4519.9  238.42
  4626.3  233.86  4636.3  232.67  4716.3  229.89  4946.3  228.70  4966.3  227.84
  4986.4  229.05  5006.4  229.08  5021.2  228.79  5040.0  227.20  5040.3  226.70
  5043.8  226.70  5044.0  227.20  5062.8  228.34  5098.4  228.59  5226.9  232.60
  5270.4  232.96  5355.6  235.07  5370.1  234.87  5376.4  235.50  5426.3  236.36
  5489.1  238.78  5598.5  241.82  5640.6  243.71  5655.9  243.57  5753.2  246.05
#Mann=7,-1,0
  4190.0    0.12       0  4440.9    0.05       0  4519.9    0.12       0
  5040.0    0.05       0  5044.0    0.12       0  5489.1    0.05       0
  5655.9    0.12       0
Bank Sta=5040,5044
Exp/Cntr=0.3,0.1

Type RM Length L Ch R = 1,1738,695,695,695
BEGIN DESCRIPTION:
Mapping XS 6bfc49f1
END DESCRIPTION:
XS GIS Cut Line= 3
      2544229.10     13606298.97      2543303.21     13606349.94
      2542871.14     13606841.31
#Sta/Elev= 30
  4144.7  253.36  4156.9  253.47  4249.0  253.91  4339.1  252.65  4439.2  249.43
  4509.2  245.64  4589.5  240.38  4609.5  238.31  4729.7  232.80  4779.8  229.63
  4829.8  229.16  4869.9  227.27  5000.1  226.92  5018.1  225.04  5018.3  224.54
  5022.2  225.04  5040.2  227.00  5060.2  226.52  5173.2  228.21  5195.0  227.88
  5201.6  226.61  5215.8  226.41  5230.1  227.96  5272.8  228.41  5287.0  229.74
  5301.2  229.53  5491.4  237.26  5558.8  239.71  5645.3  242.25  5726.3  243.09
#Mann=8,-1,0
  4144.7    0.04       0  4156.9    0.05       0  4509.2    0.12       0
  5018.1    0.05       0  5022.2    0.12       0  5491.4   0.013       0
  5558.8    0.05       0  5645.3   0.013       0
Bank Sta=5018.1,5022.2
Exp/Cntr=0.3,0.1

Type RM Length L Ch R = 1,1043,434,434,434
BEGIN DESCRIPTION:
TRIB 12 TO IRISH CREEK 1.0
END DESCRIPTION:
XS GIS Cut Line= 3
      2543575.02     13605775.00      2543075.00     13605775.00
      2542825.02     13606274.97
#Sta/Elev= 30
  4549.9  246.17  4581.9  244.27  4629.9  242.94  4739.9  233.50  4801.3  229.58
  4889.9  225.83  4959.9  224.52  4975.4  225.04  4979.9  225.46  4989.9  224.88
  5007.9  223.11  5008.1  222.61  5011.7  222.61  5012.0  223.11  5019.9  224.90
  5039.9  224.33  5047.4  224.85  5080.7  224.52  5106.4  225.11  5198.1  224.95
  5214.8  225.71  5220.4  225.04  5228.8  225.89  5251.2  225.30  5363.0  225.41
  5408.9  227.25  5483.2  231.48  5550.2  236.39  5578.2  239.75  5608.9  241.66
#Mann=8,-1,0
  4549.9    0.05       0  4581.9    0.12       0  4801.3    0.05       0
  4975.4   0.013       0  5007.9    0.03       0  5012.0   0.013       0
  5106.4    0.12       0  5408.9    0.05       0
Bank Sta=5007.9,5012
Exp/Cntr=0.3,0.1

Type RM Length L Ch R = 1,609,0,0,0
BEGIN DESCRIPTION:
TRIB 12 TO IRISH CREEK 0.5
END DESCRIPTION:
XS GIS Cut Line= 4
      2543712.63     13604773.18      2543183.52     13605144.99
      2542669.92     13605724.90      2542715.42     13606255.72
#Sta/Elev= 30
  4007.6  226.74  4326.8  227.42  4351.5  227.88  4402.0  227.03  4431.6  227.47
  4509.2  226.83  4653.8  224.56  4794.9  222.53  4833.0  222.96  4910.7  223.03
  4929.6  222.49  4950.5  223.26  4978.9  222.61  5198.9  223.67  5375.6  222.74
  5382.9  223.28  5431.9  222.79  5457.1  220.90  5457.3  220.40  5460.9  220.40
  5461.2  220.90  5469.2  222.63  5489.2  223.04  5589.6  222.98  5720.1  225.31
  5846.9  229.90  5890.7  232.29  5902.0  233.64  5950.9  235.91  5961.7  235.77
#Mann=8,-1,0
  4007.6    0.04       0  4326.8    0.05       0  4653.8    0.12       0
  4833.0   0.013       0  4910.7    0.12       0  5457.1    0.05       0
  5461.2    0.12       0  5846.9    0.05       0
Bank Sta=5457.1,5461.2
Exp/Cntr=0.3,0.1

Chan Stop Cuts=-1