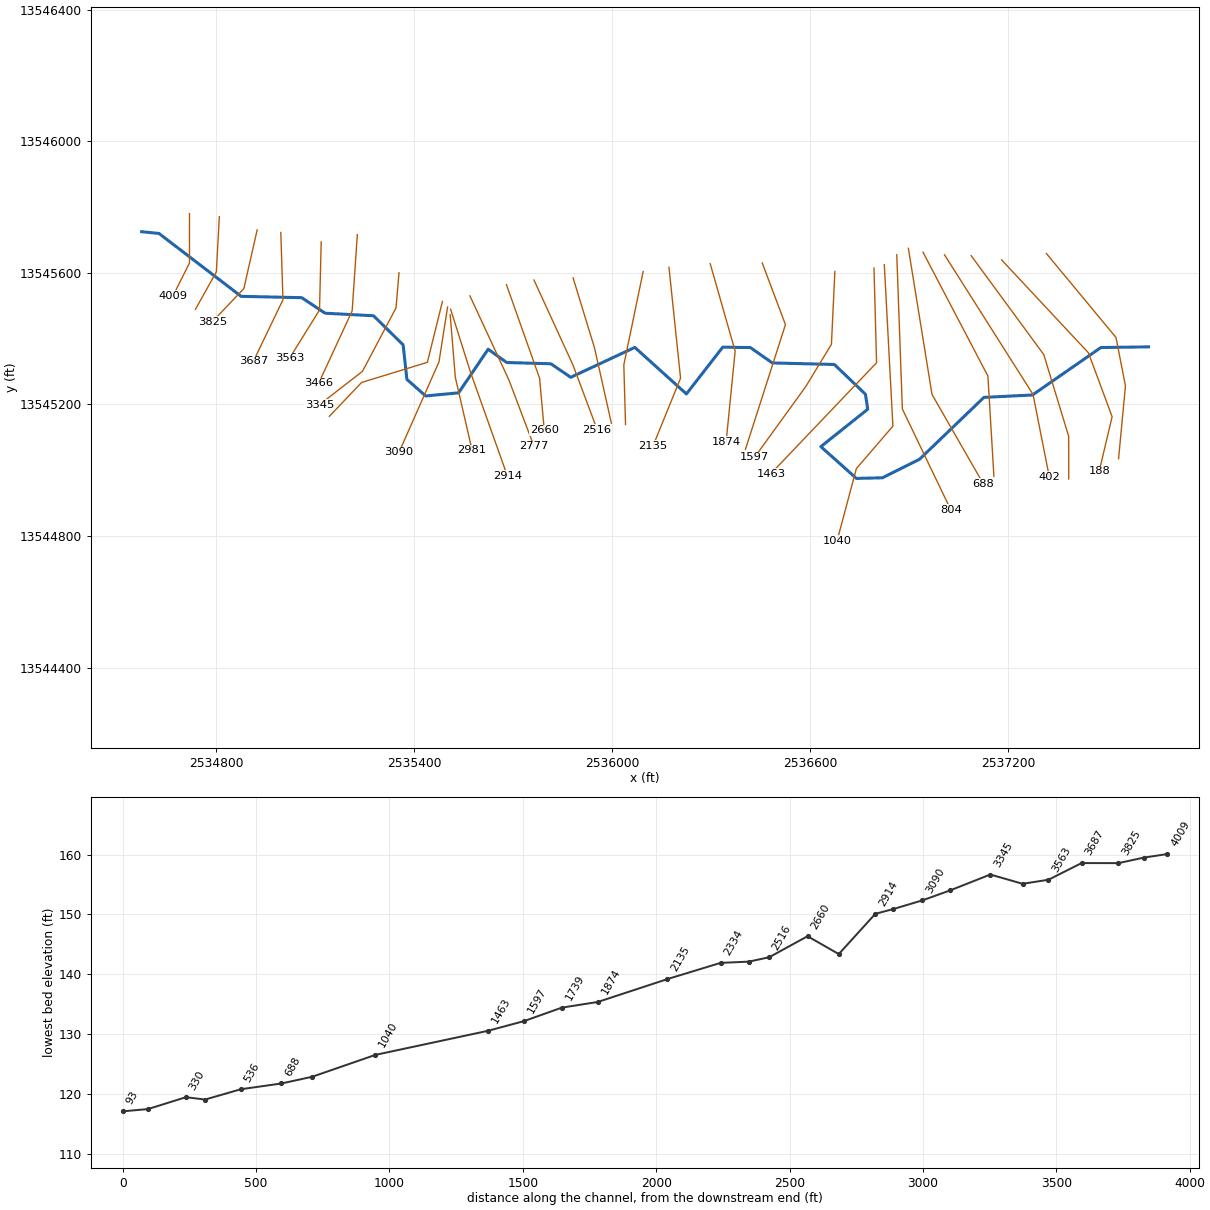
--- TRIB 12_1 TO GUADALUPE RIVER.prj (project) ---

Proj Title=TRIB 12_1 TO GUADALUPE RIVER Base Level Engineering
Current Plan=p01
Default Exp/Contr=0.3,0.1
English Units
Geom File=g01
Flow File=f01
Plan File=p01
Y Axis Title=Elevation
X Axis Title(PF)=Main Channel Distance
X Axis Title(XS)=Station
BEGIN DESCRIPTION:
TRIB 12_1 TO GUADALUPE RIVER
END DESCRIPTION:
DSS Export Rating Curves= 0
DSS Export Rating Curve Sorted= 0
DSS Export Volume Flow Curves= 0
DXF OffsetX= 0
DXF OffsetY= 0
DXF ScaleX= 1
DXF ScaleY= 10

--- TRIB 12_1 TO GUADALUPE RIVER.p01 (plan) ---

Plan Title=Multiple Run
Short Identifier=Multiple
Geom File=g01
Flow File=f01
Subcritical Flow
K Sum by GR= 0
Std Step Tol= 0.01
Critical Tol= 0.01
Num of Std Step Trials= 20
Max Error Tol= 0.3
Flow Tol Ratio= 0.001
Split Flow NTrial= 30
Split Flow Tol= 0.02
Split Flow Ratio= 0.02
Log Output Level= 0
Friction Slope Method= 1
Unsteady Friction Slope Method= 2
Unsteady Bridges Friction Slope Method= 1
Parabolic Critical Depth
Global Vel Dist=  1 , 1 , 1
Global Log Level= 0
CheckData=True
Encroach Param= -1, 0, 0, 0
BEGIN DESCRIPTION:
Multiple Run
END DESCRIPTION:

--- TRIB 12_1 TO GUADALUPE RIVER.f01 (steady flow) ---

Flow Title=Multiple
Number of Profiles=7
Profile Names=10-year,25-year,50-year,1pct_min,100-year,1pct_plu,500-year
River Rch & RM= TRIB 12_1 TO GUA,Reach-1,4009
     581     935    1254     817    1630    3252    2717
River Rch & RM= TRIB 12_1 TO GUA,Reach-1,2777
     649    1051    1415     925    1845    3681    3097
Boundary for River Rch & Prof#=TRIB 12_1 TO GUA,Reach-1,1
Up Type=0
Dn Type=3
Dn Slope=0.005
Boundary for River Rch & Prof#=TRIB 12_1 TO GUA,Reach-1,2
Up Type=0
Dn Type=3
Dn Slope=0.005
Boundary for River Rch & Prof#=TRIB 12_1 TO GUA,Reach-1,3
Up Type=0
Dn Type=3
Dn Slope=0.005
Boundary for River Rch & Prof#=TRIB 12_1 TO GUA,Reach-1,4
Up Type=0
Dn Type=3
Dn Slope=0.005
Boundary for River Rch & Prof#=TRIB 12_1 TO GUA,Reach-1,5
Up Type=0
Dn Type=3
Dn Slope=0.005
Boundary for River Rch & Prof#=TRIB 12_1 TO GUA,Reach-1,6
Up Type=0
Dn Type=3
Dn Slope=0.005
Boundary for River Rch & Prof#=TRIB 12_1 TO GUA,Reach-1,7
Up Type=0
Dn Type=3
Dn Slope=0.005

--- TRIB 12_1 TO GUADALUPE RIVER.g01 (geometry) ---

Geom Title=Existing Conditions

River Reach=TRIB 12_1 TO GUA,Reach-1
Reach XY= 30
      2534575.00     13545725.00      2534627.51     13545719.67
      2534876.47     13545528.55      2535059.78     13545524.48
      2535130.94     13545477.27      2535277.46     13545469.54
      2535367.14     13545381.19      2535378.51     13545276.25
      2535435.32     13545225.86      2535535.10     13545235.30
      2535624.69     13545367.77      2535680.85     13545327.48
      2535814.56     13545323.60      2535875.01     13545282.53
      2536068.96     13545373.39      2536225.21     13545231.98
      2536335.33     13545374.13      2536419.02     13545372.84
      2536485.50     13545326.22      2536673.55     13545321.47
      2536767.55     13545231.05      2536774.51     13545185.49
      2536632.51     13545071.83      2536740.20     13544975.24
      2536819.03     13544977.14      2536931.06     13545033.14
      2537126.47     13545221.46      2537273.44     13545228.76
      2537480.83     13545372.98      2537625.00     13545375.00

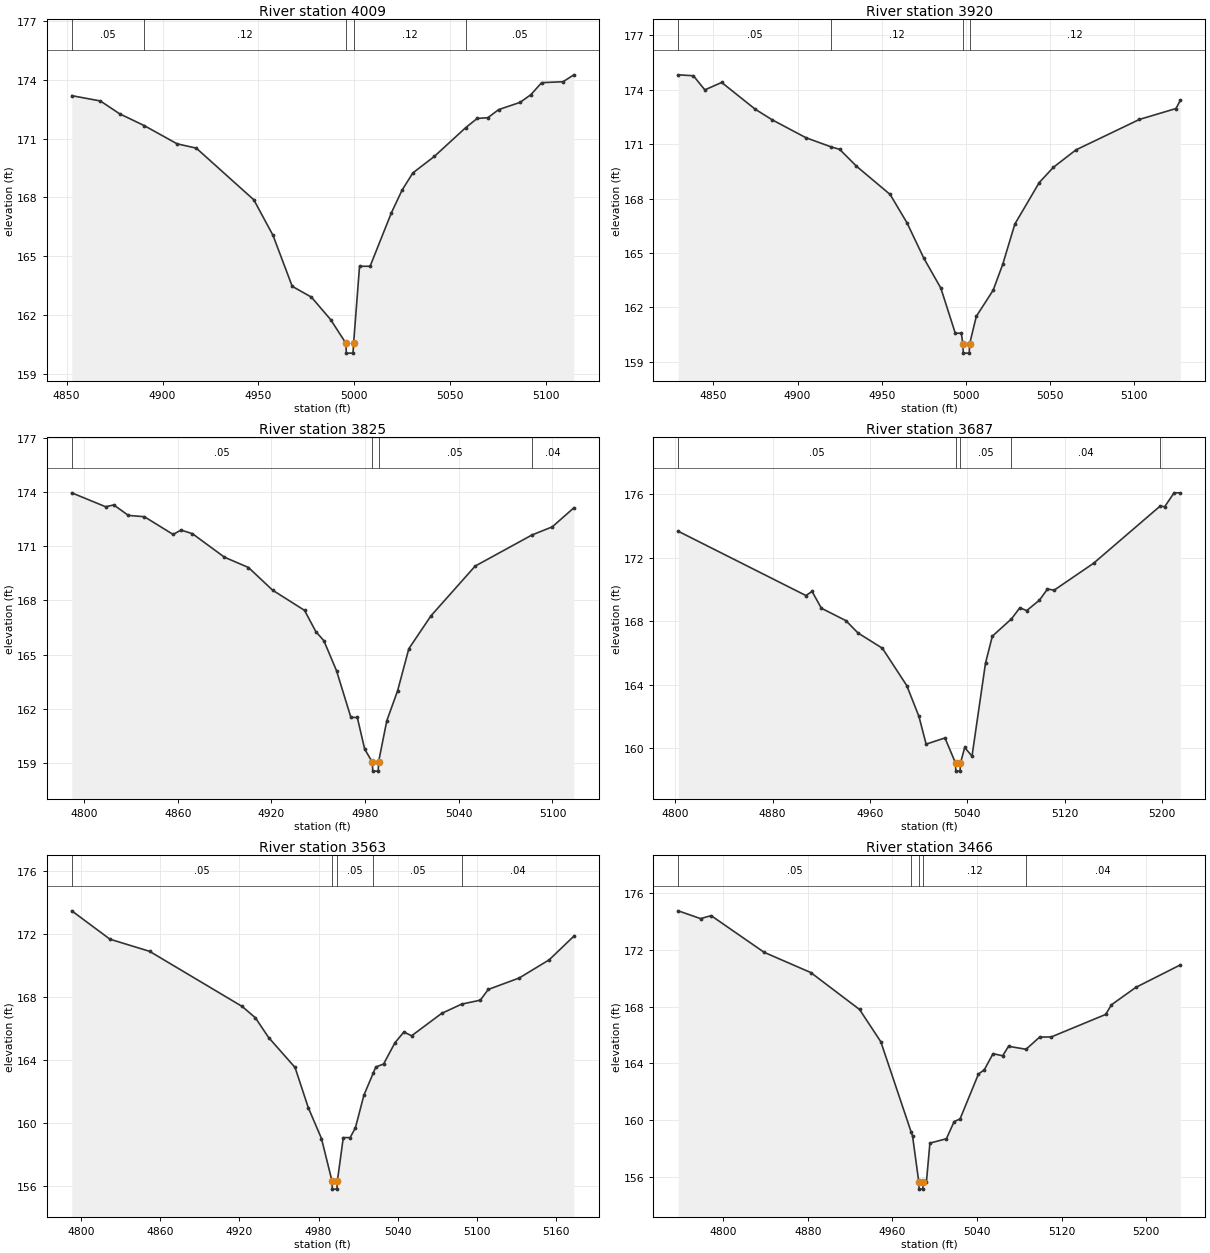
Type RM Length L Ch R = 1,4009,89,89,89
BEGIN DESCRIPTION:
TRIB 12_1 TO GUADALUPE RIVER 8.0
END DESCRIPTION:
XS GIS Cut Line= 3
      2534719.93     13545779.86      2534719.93     13545629.83
      2534669.99     13545529.95
#Sta/Elev= 30
  4852.7  173.18  4867.6  172.91  4877.6  172.26  4890.6  171.65  4907.6  170.73
  4917.6  170.51  4947.6  167.88  4957.6  166.07  4967.6  163.48  4977.6  162.93
  4987.6  161.79  4995.6  160.58  4995.8  160.08  4999.3  160.08  4999.6  160.58
  5002.7  164.50  5008.2  164.50  5019.3  167.22  5024.9  168.38  5030.5  169.25
  5041.7  170.09  5058.0  171.55  5064.0  172.02  5069.6  172.06  5075.2  172.47
  5086.4  172.84  5092.0  173.23  5097.6  173.84  5108.8  173.89  5114.4  174.24
#Mann=5,-1,0
  4852.7    0.05       0  4890.6    0.12       0  4995.6    0.05       0
  4999.6    0.12       0  5058.0    0.05       0
Bank Sta=4995.6,4999.6
Exp/Cntr=0.3,0.1

Type RM Length L Ch R = 1,3920,95,95,95
BEGIN DESCRIPTION:
Mapping XS fba4c0de
END DESCRIPTION:
XS GIS Cut Line= 3
      2534810.39     13545770.74      2534801.28     13545602.80
      2534737.98     13545489.12
#Sta/Elev= 30
  4829.1  174.83  4838.1  174.78  4844.9  174.00  4854.9  174.41  4874.9  172.93
  4884.9  172.35  4905.0  171.36  4919.8  170.86  4925.0  170.72  4935.0  169.79
  4955.0  168.23  4965.0  166.67  4975.1  164.70  4985.1  163.07  4993.7  160.58
  4997.3  160.58  4998.2  159.98  4998.5  159.48  5002.0  159.48  5002.2  159.98
  5006.2  161.51  5016.2  162.95  5021.9  164.38  5029.1  166.60  5043.6  168.89
  5052.0  169.73  5065.4  170.69  5103.1  172.37  5124.8  172.97  5127.4  173.42
#Mann=4,-1,0
  4829.1    0.05       0  4919.8    0.12       0  4998.2    0.05       0
  5002.2    0.12       0
Bank Sta=4998.2,5002.2
Exp/Cntr=0.3,0.1

Type RM Length L Ch R = 1,3825,138,138,138
BEGIN DESCRIPTION:
Mapping XS aab81dd8
END DESCRIPTION:
XS GIS Cut Line= 3
      2534924.97     13545730.40      2534884.61     13545552.02
      2534789.14     13545451.39
#Sta/Elev= 30
  4792.1  173.95  4813.8  173.18  4819.0  173.28  4828.4  172.70  4838.6  172.63
  4857.0  171.65  4862.1  171.89  4869.4  171.69  4889.9  170.39  4905.3  169.82
  4920.7  168.57  4941.2  167.45  4948.4  166.28  4953.6  165.77  4961.7  164.11
  4970.9  161.53  4975.0  161.53  4979.7  159.78  4984.6  159.06  4984.9  158.56
  4988.4  158.56  4988.6  159.06  4993.9  161.35  5000.8  163.00  5008.0  165.33
  5022.2  167.15  5050.5  169.90  5086.9  171.62  5099.9  172.07  5113.7  173.12
#Mann=4,-1,0
  4792.1    0.05       0  4984.6    0.05       0  4988.6    0.05       0
  5086.9    0.04       0
Bank Sta=4984.6,4988.6
Exp/Cntr=0.3,0.1

Type RM Length L Ch R = 1,3687,124,124,124
BEGIN DESCRIPTION:
Mapping XS 8641c6d8
END DESCRIPTION:
XS GIS Cut Line= 3
      2534996.59     13545722.59      2535003.10     13545518.16
      2534913.27     13545330.70
#Sta/Elev= 30
  4802.5  173.68  4907.4  169.63  4912.4  169.89  4920.1  168.83  4940.2  168.05
  4950.2  167.27  4970.2  166.31  4990.2  163.96  5000.2  162.02  5006.1  160.27
  5021.6  160.66  5030.3  159.07  5030.5  158.57  5034.0  158.57  5034.3  159.07
  5037.8  160.06  5043.8  159.51  5054.9  165.38  5060.5  167.07  5076.2  168.16
  5083.1  168.86  5088.7  168.68  5099.2  169.34  5105.8  170.04  5111.3  169.97
  5143.6  171.66  5198.4  175.27  5202.0  175.22  5209.8  176.10  5214.9  176.10
#Mann=5,-1,0
  4802.5    0.05       0  5030.3    0.05       0  5034.3    0.05       0
  5076.2    0.04       0  5198.4    0.05       0
Bank Sta=5030.3,5034.3
Exp/Cntr=0.3,0.1

Type RM Length L Ch R = 1,3563,97,97,97
BEGIN DESCRIPTION:
Mapping XS d816d04d
END DESCRIPTION:
XS GIS Cut Line= 3
      2535118.98     13545693.91      2535113.78     13545486.91
      2535022.71     13545339.90
#Sta/Elev= 30
  4793.2  173.45  4822.1  171.65  4852.1  170.88  4922.2  167.38  4932.2  166.66
  4942.2  165.41  4962.2  163.51  4972.2  160.96  4982.2  159.00  4990.2  156.29
  4990.4  155.79  4993.9  155.79  4994.2  156.29  4998.7  159.06  5003.9  159.06
  5007.9  159.69  5014.3  161.75  5021.4  163.16  5023.3  163.54  5029.2  163.73
  5037.8  165.08  5044.6  165.76  5050.4  165.52  5073.1  166.94  5088.3  167.53
  5102.4  167.78  5108.4  168.46  5131.9  169.19  5154.5  170.34  5173.2  171.84
#Mann=5,-1,0
  4793.2    0.05       0  4990.2    0.05       0  4994.2    0.05       0
  5021.4    0.05       0  5088.3    0.04       0
Bank Sta=4990.2,4994.2
Exp/Cntr=0.3,0.1

Type RM Length L Ch R = 1,3466,121,121,121
BEGIN DESCRIPTION:
Mapping XS 9dae0093
END DESCRIPTION:
XS GIS Cut Line= 3
      2535228.36     13545716.05      2535212.73     13545484.31
      2535111.18     13545264.28
#Sta/Elev= 30
  4757.6  174.77  4778.7  174.22  4788.7  174.43  4838.8  171.84  4882.9  170.41
  4929.0  167.80  4949.1  165.52  4977.8  159.14  4979.1  158.86  4985.0  155.61
  4985.3  155.11  4988.8  155.11  4989.0  155.61  4992.2  155.61  4995.5  158.36
  5011.1  158.67  5018.4  159.88  5024.0  160.07  5041.4  163.24  5046.9  163.54
  5055.2  164.68  5064.3  164.53  5069.8  165.20  5086.4  164.99  5099.2  165.85
  5110.2  165.86  5161.6  167.45  5167.1  168.13  5190.1  169.36  5232.2  170.95
#Mann=5,-1,0
  4757.6    0.05       0  4977.8    0.12       0  4985.0    0.05       0
  4989.0    0.12       0  5086.4    0.04       0
Bank Sta=4985,4989
Exp/Cntr=0.3,0.1

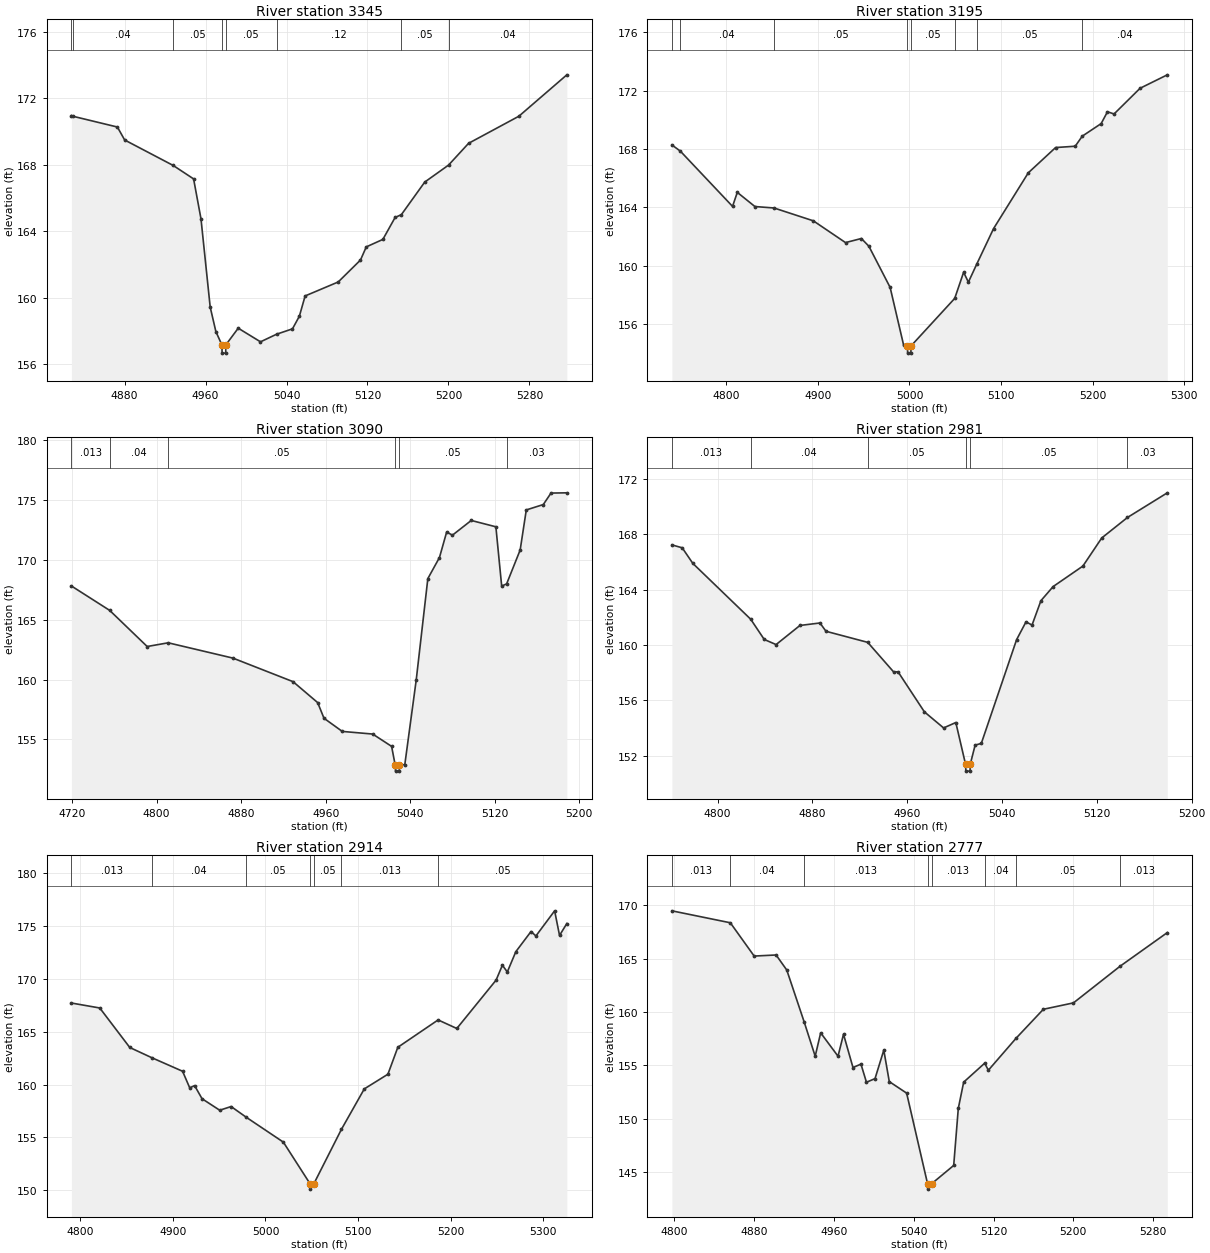
Type RM Length L Ch R = 1,3345,150,150,150
BEGIN DESCRIPTION:
Mapping XS 0e9313b6
END DESCRIPTION:
XS GIS Cut Line= 4
      2535354.66     13545600.22      2535345.55     13545493.42
      2535243.98     13545300.72      2535114.29     13545199.56
#Sta/Elev= 30
  4827.5  170.95  4828.8  170.91  4872.9  170.26  4880.1  169.48  4928.0  167.95
  4948.2  167.14  4955.5  164.74  4964.6  159.43  4970.2  157.96  4976.1  157.16
  4976.4  156.66  4979.9  156.66  4980.1  157.16  4992.3  158.16  5014.3  157.34
  5030.3  157.80  5045.9  158.12  5052.7  158.88  5058.4  160.10  5091.1  160.94
  5113.1  162.26  5118.8  163.05  5135.2  163.50  5147.3  164.82  5153.5  164.99
  5176.6  166.95  5200.1  167.97  5219.9  169.28  5269.6  170.91  5317.0  173.40
#Mann=8,-1,0
  4827.5    0.05       0  4828.8    0.04       0  4928.0    0.05       0
  4976.1    0.05       0  4980.1    0.05       0  5030.3    0.12       0
  5153.5    0.05       0  5200.1    0.04       0
Bank Sta=4976.1,4980.1
Exp/Cntr=0.3,0.1

Type RM Length L Ch R = 1,3195,105,105,105
BEGIN DESCRIPTION:
Mapping XS 8e369bab
END DESCRIPTION:
XS GIS Cut Line= 4
      2535486.18     13545512.99      2535440.60     13545328.06
      2535241.38     13545266.86      2535143.73     13545164.00
#Sta/Elev= 30
  4740.7  168.28  4750.0  167.85  4806.9  164.07  4812.1  165.03  4831.3  164.06
  4852.2  163.96  4895.1  163.08  4930.2  161.59  4947.5  161.87  4955.7  161.34
  4978.9  158.52  4993.6  154.57  4997.8  154.52  4998.0  154.02  5001.5  154.02
  5001.8  154.52  5049.4  157.77  5059.1  159.56  5064.3  158.88  5073.6  160.14
  5091.8  162.55  5129.7  166.37  5159.5  168.10  5180.9  168.19  5188.6  168.88
  5209.2  169.74  5216.1  170.55  5223.3  170.40  5251.7  172.16  5281.4  173.08
#Mann=8,-1,0
  4740.7    0.05       0  4750.0    0.04       0  4852.2    0.05       0
  4997.8    0.05       0  5001.8    0.05       0  5049.4    0.12       0
  5073.6    0.05       0  5188.6    0.04       0
Bank Sta=4997.8,5001.8
Exp/Cntr=0.3,0.1

Type RM Length L Ch R = 1,3090,109,109,109
BEGIN DESCRIPTION:
Mapping XS d8df359e
END DESCRIPTION:
XS GIS Cut Line= 3
      2535501.80     13545496.07      2535475.75     13545329.36
      2535354.65     13545054.60
#Sta/Elev= 30
  4719.3  167.82  4755.5  165.78  4791.0  162.76  4810.9  163.07  4872.2  161.79
  4929.1  159.82  4952.4  158.07  4958.4  156.76  4975.7  155.66  5004.5  155.44
  5022.4  154.41  5025.8  152.84  5026.1  152.34  5029.6  152.34  5029.8  152.84
  5034.9  152.89  5045.7  159.96  5056.7  168.44  5067.7  170.20  5074.5  172.33
  5080.0  172.07  5097.8  173.30  5121.1  172.77  5126.6  167.81  5131.3  168.00
  5144.1  170.83  5149.9  174.18  5166.0  174.63  5173.3  175.59  5188.3  175.61
#Mann=6,-1,0
  4719.3   0.013       0  4755.5    0.04       0  4810.9    0.05       0
  5025.8    0.05       0  5029.8    0.05       0  5131.3    0.03       0
Bank Sta=5025.8,5029.8
Exp/Cntr=0.3,0.1

Type RM Length L Ch R = 1,2981,67,67,67
BEGIN DESCRIPTION:
Mapping XS e72e358b
END DESCRIPTION:
XS GIS Cut Line= 3
      2535509.61     13545472.61      2535525.23     13545282.49
      2535576.02     13545061.10
#Sta/Elev= 30
  4761.5  167.23  4770.2  167.02  4779.2  165.89  4828.0  161.86  4839.4  160.40
  4849.4  160.03  4869.5  161.41  4886.4  161.59  4891.5  160.99  4926.7  160.19
  4948.5  158.06  4952.3  158.06  4974.5  155.17  4990.7  154.01  5001.0  154.40
  5009.2  151.39  5009.5  150.89  5013.0  150.89  5013.2  151.39  5017.3  152.77
  5022.5  152.89  5052.3  160.39  5060.2  161.67  5065.3  161.44  5072.8  163.20
  5083.1  164.22  5108.2  165.70  5124.1  167.73  5145.8  169.21  5179.4  170.99
#Mann=6,-1,0
  4761.5   0.013       0  4828.0    0.04       0  4926.7    0.05       0
  5009.2    0.05       0  5013.2    0.05       0  5145.8    0.03       0
Bank Sta=5009.2,5013.2
Exp/Cntr=0.3,0.1

Type RM Length L Ch R = 1,2914,137,137,137
BEGIN DESCRIPTION:
Mapping XS 34fce4ef
END DESCRIPTION:
XS GIS Cut Line= 3
      2535510.92     13545489.48      2535571.26     13545297.75
      2535682.78     13544983.02
#Sta/Elev= 30
  4790.5  167.72  4821.1  167.25  4853.5  163.51  4877.1  162.55  4910.5  161.26
  4918.2  159.69  4923.5  159.90  4931.5  158.66  4950.6  157.57  4962.9  157.92
  4979.5  156.89  5019.3  154.55  5048.2  150.60  5048.4  150.10  5052.2  150.60
  5082.0  155.76  5106.7  159.59  5132.2  160.98  5142.9  163.53  5186.4  166.12
  5206.6  165.31  5249.0  169.89  5255.8  171.30  5261.1  170.66  5270.3  172.58
  5286.7  174.49  5292.0  174.07  5312.2  176.45  5317.5  174.12  5325.4  175.25
#Mann=7,-1,0
  4790.5   0.013       0  4877.1    0.04       0  4979.5    0.05       0
  5048.2    0.05       0  5052.2    0.05       0  5082.0   0.013       0
  5186.4    0.05       0
Bank Sta=5048.2,5052.2
Exp/Cntr=0.3,0.1

Type RM Length L Ch R = 1,2777,117,117,117
BEGIN DESCRIPTION:
Mapping XS 9bc3f38d
END DESCRIPTION:
XS GIS Cut Line= 3
      2535569.50     13545529.90      2535687.99     13545273.37
      2535763.50     13545072.89
#Sta/Elev= 30
  4797.4  169.47  4856.0  168.35  4879.9  165.23  4901.9  165.33  4912.6  163.92
  4930.1  159.04  4941.1  155.84  4946.6  158.03  4964.0  155.84  4969.5  157.90
  4979.0  154.78  4987.0  155.10  4992.5  153.40  5001.1  153.74  5009.9  156.41
  5015.4  153.46  5032.8  152.38  5053.8  143.88  5054.0  143.38  5057.8  143.88
  5080.0  145.60  5084.6  150.94  5090.0  153.41  5111.0  155.18  5114.8  154.53
  5142.7  157.54  5169.9  160.24  5200.1  160.84  5246.9  164.28  5294.2  167.43
#Mann=8,-1,0
  4797.4   0.013       0  4856.0    0.04       0  4930.1   0.013       0
  5053.8    0.03       0  5057.8   0.013       0  5111.0    0.04       0
  5142.7    0.05       0  5246.9   0.013       0
Bank Sta=5053.8,5057.8
Exp/Cntr=0.3,0.1

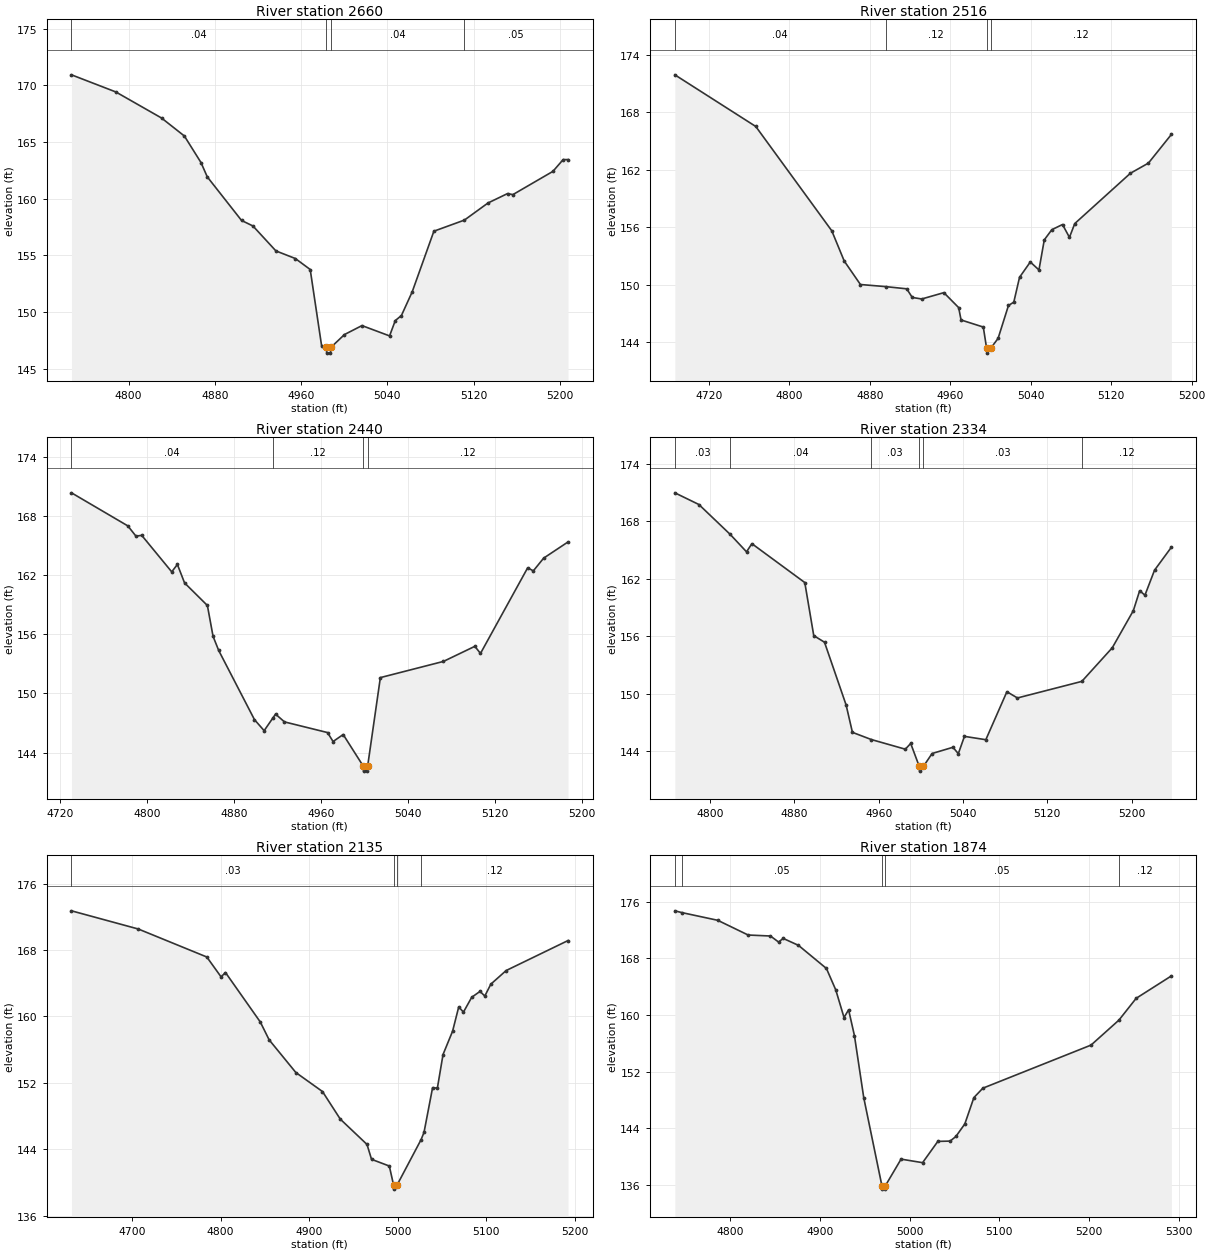
Type RM Length L Ch R = 1,2660,144,144,144
BEGIN DESCRIPTION:
Mapping XS 3115bb94
END DESCRIPTION:
XS GIS Cut Line= 3
      2535680.18     13545563.74      2535780.44     13545279.88
      2535794.76     13545121.07
#Sta/Elev= 30
  4747.0  170.92  4788.1  169.41  4830.5  167.11  4851.7  165.52  4867.1  163.18
  4872.9  161.92  4904.7  158.07  4915.3  157.58  4936.6  155.38  4954.6  154.71
  4968.4  153.74  4979.0  146.99  4983.5  146.86  4983.7  146.36  4987.2  146.36
  4987.5  146.86  5000.2  148.00  5016.4  148.79  5042.0  147.88  5047.3  149.23
  5053.0  149.68  5063.0  151.77  5083.1  157.12  5111.4  158.10  5133.3  159.61
  5151.4  160.44  5156.4  160.35  5193.5  162.40  5203.0  163.44  5207.5  163.44
#Mann=4,-1,0
  4747.0    0.04       0  4983.5    0.04       0  4987.5    0.04       0
  5111.4    0.05       0
Bank Sta=4983.5,4987.5
Exp/Cntr=0.3,0.1

Type RM Length L Ch R = 1,2516,76,76,76
BEGIN DESCRIPTION:
Mapping XS 454c5f82
END DESCRIPTION:
XS GIS Cut Line= 3
      2535763.50     13545578.08      2535882.00     13545318.94
      2535954.91     13545123.66
#Sta/Elev= 30
  4686.4  171.89  4766.8  166.50  4842.3  155.62  4854.7  152.46  4870.8  150.01
  4895.9  149.79  4916.8  149.56  4922.3  148.66  4931.7  148.50  4953.7  149.16
  4968.4  147.60  4970.8  146.31  4992.9  145.57  4996.2  143.35  4996.5  142.85
  5000.2  143.35  5007.6  144.39  5017.9  147.82  5023.2  148.17  5028.9  150.76
  5039.6  152.36  5048.2  151.53  5053.5  154.67  5061.0  155.73  5071.6  156.27
  5078.5  154.93  5083.8  156.37  5139.1  161.62  5157.0  162.68  5179.8  165.67
#Mann=4,-1,0
  4686.4    0.04       0  4895.9    0.12       0  4996.2    0.05       0
  5000.2    0.12       0
Bank Sta=4996.2,5000.2
Exp/Cntr=0.3,0.1

Type RM Length L Ch R = 1,2440,106,106,106
BEGIN DESCRIPTION:
Mapping XS 87029fc0
END DESCRIPTION:
XS GIS Cut Line= 3
      2535882.02     13545584.53      2535947.11     13545371.03
      2535997.90     13545143.12
#Sta/Elev= 30
  4730.3  170.33  4782.1  166.98  4789.6  165.94  4794.9  166.02  4822.5  162.32
  4827.7  163.07  4834.3  161.20  4855.3  158.91  4860.5  155.79  4865.7  154.35
  4898.6  147.34  4907.5  146.22  4915.5  147.50  4918.0  147.90  4926.2  147.11
  4965.8  146.03  4970.9  145.12  4980.2  145.83  4998.7  142.62  4998.9  142.12
  5002.4  142.12  5002.7  142.62  5014.4  151.60  5072.4  153.24  5101.3  154.77
  5106.5  154.05  5149.9  162.73  5155.1  162.42  5164.6  163.71  5187.0  165.35
#Mann=4,-1,0
  4730.3    0.04       0  4915.5    0.12       0  4998.7    0.05       0
  5002.7    0.12       0
Bank Sta=4998.7,5002.7
Exp/Cntr=0.3,0.1

Type RM Length L Ch R = 1,2334,199,199,199
BEGIN DESCRIPTION:
Mapping XS f25d16e0
END DESCRIPTION:
XS GIS Cut Line= 3
      2536094.24     13545604.10      2536035.65     13545320.25
      2536040.83     13545138.96
#Sta/Elev= 30
  4766.5  170.97  4789.3  169.75  4819.0  166.63  4834.5  164.81  4839.6  165.66
  4889.8  161.60  4898.3  156.06  4908.5  155.37  4929.0  148.82  4935.0  145.96
  4952.9  145.21  4985.2  144.20  4990.3  144.80  4998.4  142.41  4998.7  141.91
  5002.4  142.41  5010.6  143.75  5030.4  144.40  5035.5  143.73  5041.3  145.54
  5061.6  145.19  5081.6  150.20  5091.6  149.55  5152.7  151.28  5181.6  154.79
  5201.6  158.67  5207.6  160.75  5212.6  160.28  5221.7  162.89  5237.7  165.29
#Mann=6,-1,0
  4766.5    0.03       0  4819.0    0.04       0  4952.9    0.03       0
  4998.4    0.03       0  5002.4    0.03       0  5152.7    0.12       0
Bank Sta=4998.4,5002.4
Exp/Cntr=0.3,0.1

Type RM Length L Ch R = 1,2135,261,261,261
BEGIN DESCRIPTION:
Mapping XS f44158dd
END DESCRIPTION:
XS GIS Cut Line= 3
      2536172.37     13545617.10      2536207.53     13545279.88
      2536124.20     13545074.17
#Sta/Elev= 30
  4631.5  172.72  4707.0  170.53  4784.4  167.16  4800.5  164.77  4805.5  165.29
  4844.8  159.34  4854.8  157.19  4885.0  153.25  4915.1  150.96  4935.2  147.64
  4965.4  144.59  4970.5  142.80  4990.6  141.99  4995.4  139.71  4995.6  139.21
  4999.4  139.71  5026.5  145.17  5029.8  146.04  5039.5  151.43  5044.9  151.37
  5051.3  155.42  5062.1  158.23  5069.0  161.14  5074.4  160.53  5083.7  162.31
  5093.1  163.02  5098.5  162.46  5105.3  163.89  5122.6  165.53  5192.5  169.14
#Mann=4,-1,0
  4631.5    0.03       0  4995.4    0.03       0  4999.4    0.03       0
  5026.5    0.12       0
Bank Sta=4995.4,4999.4
Exp/Cntr=0.3,0.1

Type RM Length L Ch R = 1,1874,135,135,135
BEGIN DESCRIPTION:
Mapping XS 1de88495
END DESCRIPTION:
XS GIS Cut Line= 3
      2536297.36     13545627.57      2536372.89     13545361.91
      2536345.54     13545085.85
#Sta/Elev= 30
  4738.3  174.73  4746.1  174.48  4786.1  173.39  4820.0  171.31  4844.9  171.17
  4853.9  170.32  4859.1  170.83  4876.1  169.85  4907.3  166.58  4917.7  163.55
  4926.9  159.65  4932.0  160.74  4938.5  157.10  4948.9  148.31  4969.1  135.89
  4969.4  135.39  4972.9  135.39  4973.1  135.89  4990.5  139.63  5014.5  139.13
  5031.5  142.14  5045.2  142.18  5051.6  142.83  5061.6  144.61  5071.7  148.33
  5081.7  149.66  5202.3  155.75  5233.4  159.28  5252.6  162.36  5291.9  165.53
#Mann=5,-1,0
  4738.3    0.03       0  4746.1    0.05       0  4969.1    0.05       0
  4973.1    0.05       0  5233.4    0.12       0
Bank Sta=4969.1,4973.1
Exp/Cntr=0.3,0.1

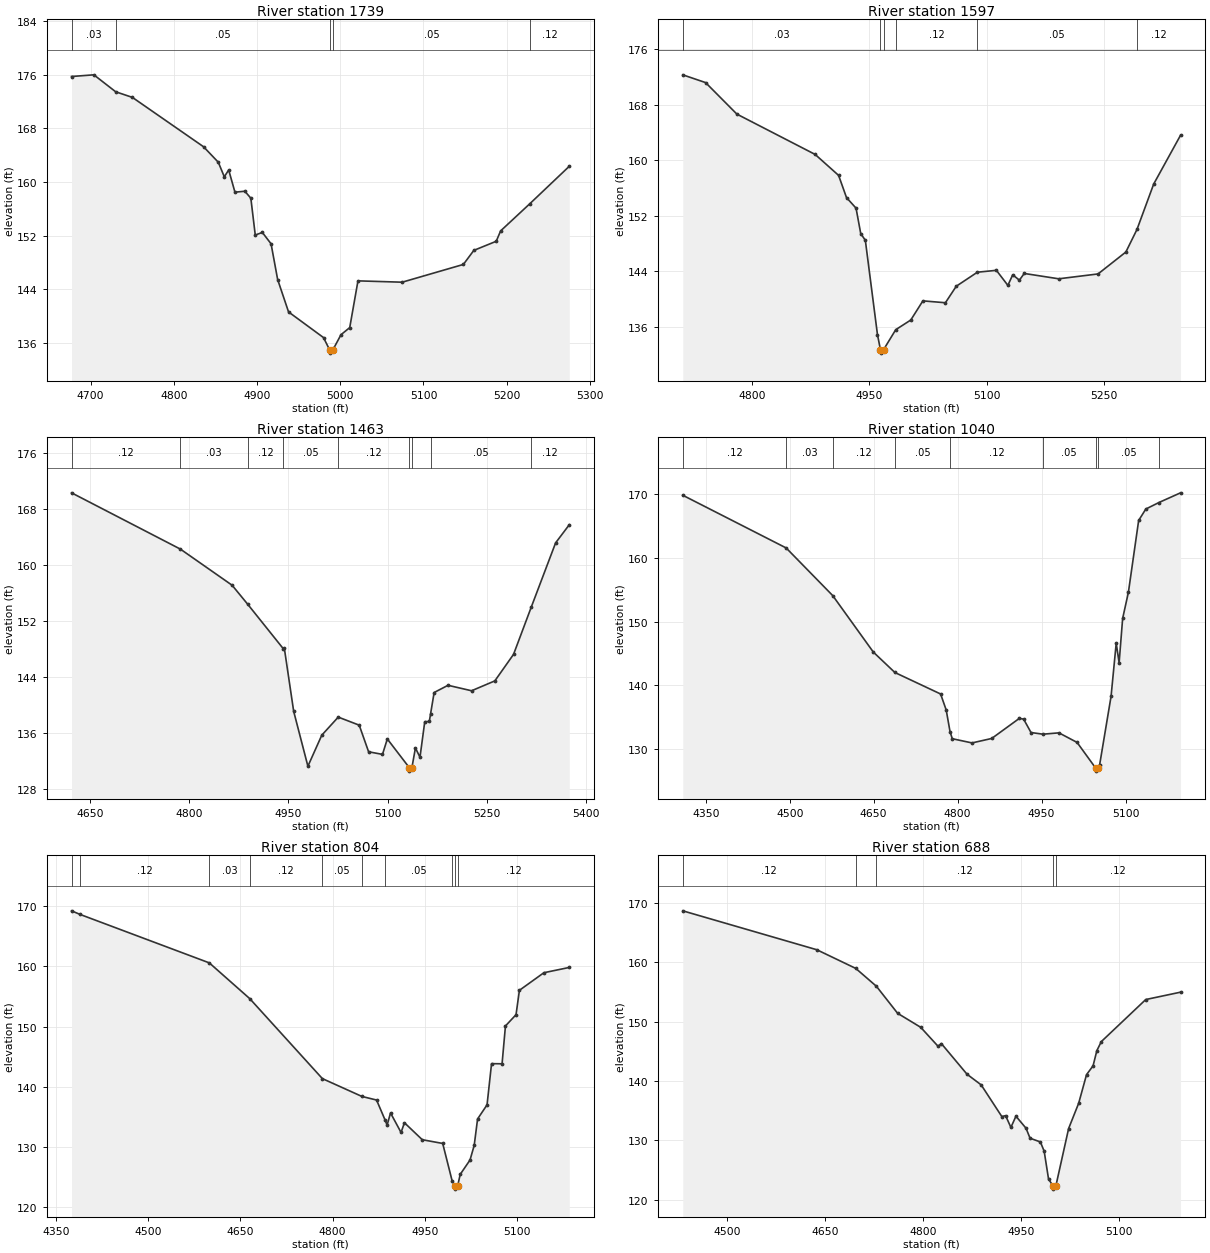
Type RM Length L Ch R = 1,1739,142,142,142
BEGIN DESCRIPTION:
Mapping XS 269ba11c
END DESCRIPTION:
XS GIS Cut Line= 3
      2536454.94     13545630.10      2536525.23     13545442.64
      2536404.14     13545063.73
#Sta/Elev= 30
  4677.2  175.74  4704.0  175.99  4730.2  173.46  4750.3  172.62  4835.8  165.25
  4853.5  162.94  4860.7  160.77  4866.0  161.78  4873.5  158.47  4885.4  158.61
  4892.6  157.57  4897.9  152.07  4906.4  152.46  4916.9  150.76  4924.8  145.43
  4937.9  140.59  4979.9  136.76  4987.2  134.94  4987.4  134.44  4991.2  134.94
  5000.9  137.19  5011.4  138.25  5021.3  145.23  5074.4  145.03  5147.9  147.68
  5160.5  149.78  5187.4  151.14  5192.7  152.69  5227.9  156.76  5275.2  162.34
#Mann=5,-1,0
  4677.2    0.03       0  4730.2    0.05       0  4987.2    0.05       0
  4991.2    0.05       0  5227.9    0.12       0
Bank Sta=4987.2,4991.2
Exp/Cntr=0.3,0.1

Type RM Length L Ch R = 1,1597,134,134,134
BEGIN DESCRIPTION:
Mapping XS ede4605f
END DESCRIPTION:
XS GIS Cut Line= 4
      2536674.97     13545604.13      2536664.56     13545382.75
      2536586.43     13545253.84      2536431.86     13545039.52
#Sta/Elev= 30
  4711.4  172.29  4740.6  171.17  4780.6  166.63  4880.7  160.82  4910.7  157.80
  4920.8  154.60  4933.0  153.08  4939.0  149.42  4944.9  148.44  4960.4  134.86
  4964.2  132.69  4964.5  132.19  4968.2  132.69  4983.8  135.57  5003.0  136.96
  5018.5  139.72  5047.3  139.45  5061.2  141.83  5088.2  143.85  5112.5  144.12
  5127.2  141.95  5133.4  143.48  5141.9  142.70  5148.1  143.67  5192.2  142.90
  5242.5  143.60  5278.1  146.76  5292.3  150.01  5313.7  156.56  5348.0  163.58
#Mann=6,-1,0
  4711.4    0.03       0  4964.2    0.05       0  4968.2    0.03       0
  4983.8    0.12       0  5088.2    0.05       0  5292.3    0.12       0
Bank Sta=4964.2,4968.2
Exp/Cntr=0.3,0.1

Type RM Length L Ch R = 1,1463,423,423,423
BEGIN DESCRIPTION:
Mapping XS 92524e47
END DESCRIPTION:
XS GIS Cut Line= 3
      2536793.46     13545614.54      2536801.28     13545326.76
      2536481.17     13544989.74
#Sta/Elev= 30
  4622.1  170.30  4786.8  162.26  4864.9  157.11  4888.2  154.43  4942.3  148.05
  4943.9  148.10  4958.0  139.11  4979.5  131.28  5000.5  135.71  5025.4  138.29
  5057.1  137.14  5071.3  133.34  5092.3  132.97  5099.6  135.17  5132.8  131.08
  5133.1  130.58  5136.8  131.08  5142.1  133.89  5149.0  132.56  5156.2  137.63
  5163.1  137.67  5165.1  138.80  5170.4  141.80  5191.4  142.83  5227.0  142.05
  5262.2  143.46  5290.5  147.25  5317.2  153.97  5354.1  163.16  5374.8  165.75
#Mann=9,-1,0
  4622.1    0.12       0  4786.8    0.03       0  4888.2    0.12       0
  4942.3    0.05       0  5025.4    0.12       0  5132.8    0.05       0
  5136.8    0.12       0  5165.1    0.05       0  5317.2    0.12       0
Bank Sta=5132.8,5136.8
Exp/Cntr=0.3,0.1

Type RM Length L Ch R = 1,1040,236,236,236
BEGIN DESCRIPTION:
Mapping XS 28d3bc7a
END DESCRIPTION:
XS GIS Cut Line= 4
      2536824.71     13545624.92      2536850.75     13545134.05
      2536740.08     13545005.14      2536681.48     13544785.08
#Sta/Elev= 30
  4309.0  169.79  4493.7  161.53  4576.9  154.06  4649.4  145.21  4687.9  142.01
  4769.6  138.64  4779.6  136.13  4786.5  132.71  4790.5  131.63  4825.7  130.97
  4860.9  131.67  4910.3  134.82  4917.9  134.70  4931.1  132.60  4952.5  132.34
  4981.0  132.55  5013.4  131.05  5046.4  127.05  5046.6  126.55  5050.4  127.05
  5053.5  127.44  5074.1  138.26  5083.3  146.60  5088.5  143.54  5094.8  150.48
  5105.1  154.59  5123.4  165.84  5136.2  167.63  5159.6  168.65  5198.2  170.17
#Mann=9,-1,0
  4309.0    0.12       0  4493.7    0.03       0  4576.9    0.12       0
  4687.9    0.05       0  4786.5    0.12       0  4952.5    0.05       0
  5046.4    0.05       0  5050.4    0.05       0  5159.6    0.12       0
Bank Sta=5046.4,5050.4
Exp/Cntr=0.3,0.1

Type RM Length L Ch R = 1,804,116,116,116
BEGIN DESCRIPTION:
Mapping XS 4a071e85
END DESCRIPTION:
XS GIS Cut Line= 3
      2536862.47     13545654.87      2536879.40     13545186.13
      2537026.26     13544879.42
#Sta/Elev= 30
  4375.7  169.27  4389.3  168.68  4599.6  160.60  4665.5  154.63  4783.4  141.32
  4847.7  138.35  4871.5  137.75  4885.4  134.41  4888.6  133.57  4894.2  135.60
  4911.3  132.35  4916.8  133.97  4945.8  131.14  4979.0  130.52  4994.3  124.30
  4999.2  123.41  4999.5  122.91  5003.2  123.41  5007.5  125.37  5023.4  127.76
  5030.2  130.19  5035.7  134.60  5051.1  136.95  5058.4  143.81  5075.5  143.79
  5081.0  150.09  5098.2  151.97  5103.7  156.03  5143.5  158.96  5184.8  159.84
#Mann=10,-1,0
  4375.7    0.05       0  4389.3    0.12       0  4599.6    0.03       0
  4665.5    0.12       0  4783.4    0.05       0  4847.7    0.12       0
  4885.4    0.05       0  4994.3    0.12       0  4999.2    0.05       0
  5003.2    0.12       0
Bank Sta=4999.2,5003.2
Exp/Cntr=0.3,0.1

Type RM Length L Ch R = 1,688,152,152,152
BEGIN DESCRIPTION:
Mapping XS 6ec71858
END DESCRIPTION:
XS GIS Cut Line= 3
      2536897.63     13545674.38      2536969.24     13545230.40
      2537124.07     13544959.78
#Sta/Elev= 30
  4432.2  168.68  4637.3  162.12  4696.8  158.98  4728.4  155.97  4760.9  151.41
  4796.2  149.05  4822.7  145.86  4827.8  146.31  4867.1  141.14  4888.7  139.35
  4920.3  134.01  4926.1  134.16  4934.2  132.18  4941.9  134.07  4957.3  132.05
  4963.5  130.36  4979.3  129.73  4985.1  128.17  4991.8  123.47  4998.9  122.28
  4999.2  121.78  5002.9  122.28  5022.5  131.99  5037.9  136.26  5049.9  141.07
  5059.9  142.56  5065.7  145.12  5072.5  146.64  5140.5  153.73  5193.7  154.97
#Mann=5,-1,0
  4432.2    0.12       0  4696.8    0.03       0  4728.4    0.12       0
  4998.9    0.05       0  5002.9    0.12       0
Bank Sta=4998.9,5002.9
Exp/Cntr=0.3,0.1

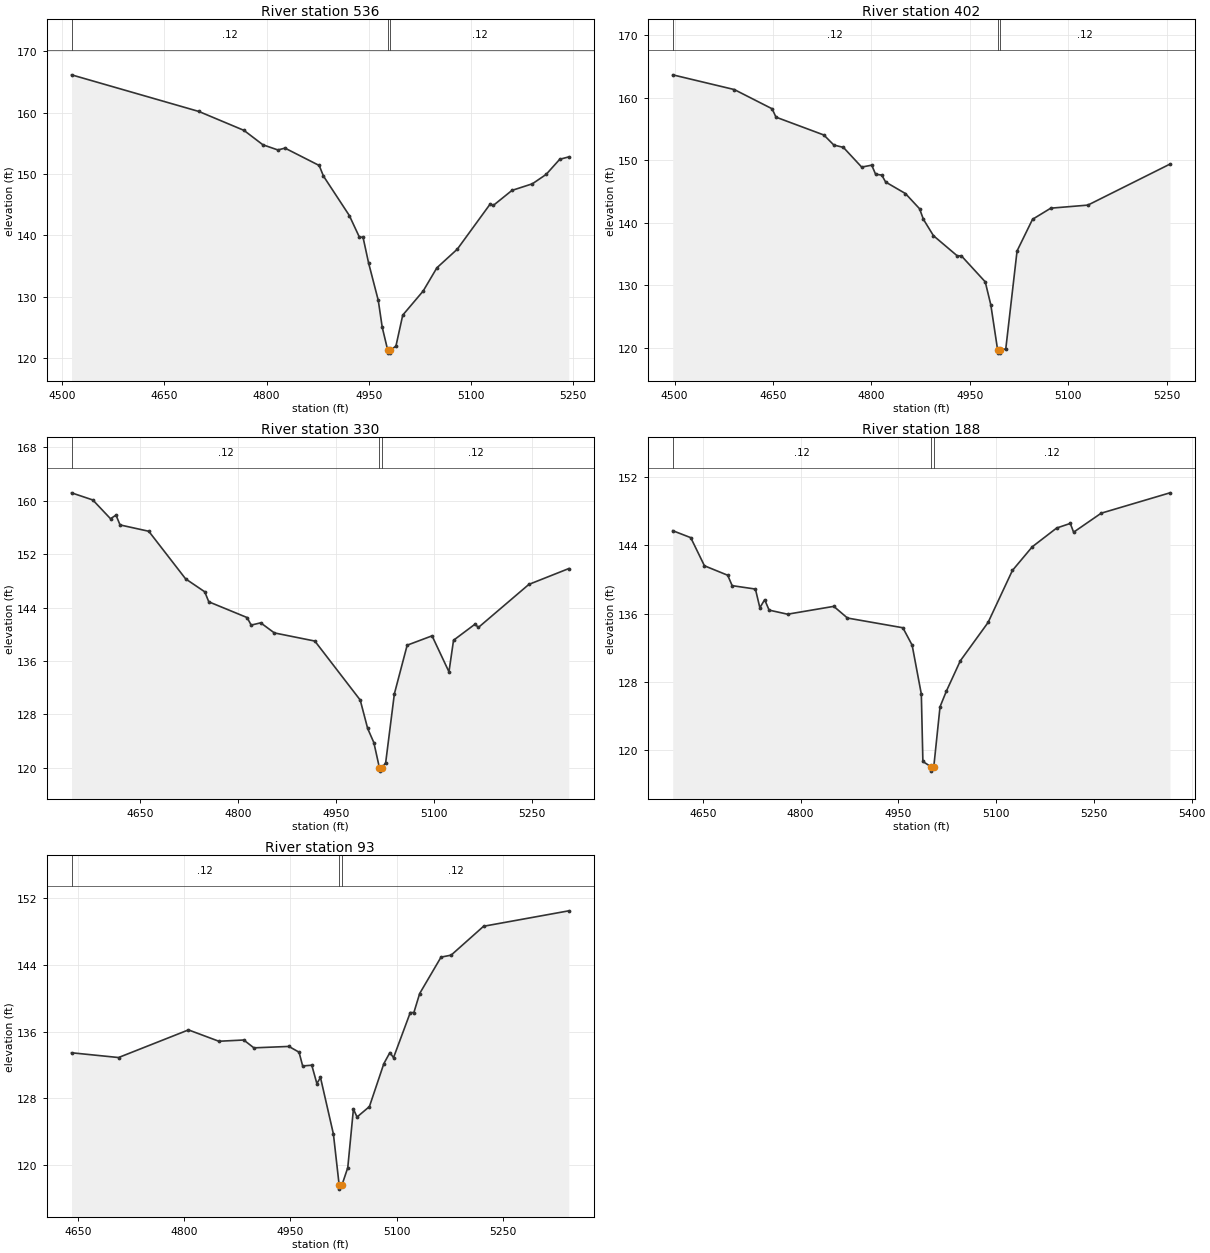
Type RM Length L Ch R = 1,536,134,134,134
BEGIN DESCRIPTION:
Mapping XS 8a56c48c
END DESCRIPTION:
XS GIS Cut Line= 3
      2536941.90     13545662.70      2537138.52     13545286.39
      2537156.74     13544981.71
#Sta/Elev= 30
  4513.7  166.16  4700.6  160.19  4766.8  157.11  4794.6  154.76  4816.6  153.92
  4827.0  154.22  4877.2  151.39  4883.4  149.67  4921.4  143.24  4936.2  139.71
  4941.5  139.71  4949.7  135.50  4963.9  129.41  4969.7  125.03  4977.7  121.32
  4978.0  120.82  4981.5  120.82  4981.7  121.32  4989.8  121.96  4999.8  127.01
  5029.8  130.94  5049.9  134.72  5079.9  137.76  5127.8  145.06  5132.8  144.89
  5160.1  147.33  5190.1  148.41  5210.2  149.93  5230.2  152.40  5243.5  152.79
#Mann=3,-1,0
  4513.7    0.12       0  4977.7    0.05       0  4981.7    0.12       0
Bank Sta=4977.7,4981.7
Exp/Cntr=0.3,0.1

Type RM Length L Ch R = 1,402,72,72,72
BEGIN DESCRIPTION:
Mapping XS e0a726af
END DESCRIPTION:
XS GIS Cut Line= 3
      2537007.02     13545654.87      2537275.23     13545230.40
      2537324.63     13544979.53
#Sta/Elev= 30
  4497.2  163.68  4591.1  161.32  4648.7  158.24  4654.6  156.90  4727.6  154.04
  4742.8  152.43  4757.3  152.06  4785.2  148.90  4800.5  149.21  4806.4  147.76
  4815.8  147.62  4821.7  146.51  4851.9  144.66  4873.4  142.23  4879.3  140.53
  4894.6  137.91  4931.1  134.66  4937.0  134.70  4973.5  130.52  4982.0  126.83
  4992.4  119.60  4992.7  119.10  4996.2  119.10  4996.4  119.60  5004.8  119.77
  5022.0  135.47  5045.6  140.54  5073.4  142.32  5129.9  142.81  5255.0  149.38
#Mann=3,-1,0
  4497.2    0.12       0  4992.4    0.05       0  4996.4    0.12       0
Bank Sta=4992.4,4996.4
Exp/Cntr=0.3,0.1

Type RM Length L Ch R = 1,330,142,142,142
BEGIN DESCRIPTION:
Mapping XS 7d5e4d2a
END DESCRIPTION:
XS GIS Cut Line= 4
      2537087.75     13545652.25      2537307.79     13545351.50
      2537383.31     13545102.80      2537383.31     13544973.86
#Sta/Elev= 30
  4544.7  161.19  4577.3  160.12  4604.4  157.31  4612.8  157.85  4619.0  156.38
  4663.0  155.43  4719.4  148.30  4748.7  146.36  4754.9  144.86  4813.6  142.50
  4819.8  141.37  4834.4  141.71  4855.3  140.20  4917.3  138.98  4986.8  130.14
  4998.2  125.88  5007.7  123.76  5016.2  119.99  5016.4  119.49  5020.2  119.99
  5025.8  120.76  5039.1  131.07  5058.7  138.36  5096.8  139.76  5122.7  134.37
  5129.7  139.10  5162.6  141.51  5167.8  141.02  5245.1  147.47  5306.2  149.84
#Mann=3,-1,0
  4544.7    0.12       0  5016.2    0.05       0  5020.2    0.12       0
Bank Sta=5016.2,5020.2
Exp/Cntr=0.3,0.1

Type RM Length L Ch R = 1,188,95,95,95
BEGIN DESCRIPTION:
Mapping XS 1718b7f3
END DESCRIPTION:
XS GIS Cut Line= 4
      2537180.17     13545639.27      2537443.20     13545356.71
      2537514.82     13545162.69      2537475.75     13544997.30
#Sta/Elev= 30
  4603.9  145.72  4631.6  144.90  4652.6  141.60  4688.3  140.49  4695.1  139.27
  4730.8  138.87  4737.6  136.68  4745.0  137.62  4751.8  136.40  4780.1  135.92
  4851.0  136.84  4872.0  135.47  4957.0  134.33  4971.2  132.29  4985.3  126.55
  4987.7  118.64  5000.4  118.01  5000.7  117.51  5004.4  118.01  5014.0  125.06
  5023.7  126.89  5045.1  130.45  5087.7  134.95  5125.0  141.05  5155.5  143.83
  5192.9  146.03  5213.8  146.57  5218.9  145.54  5261.2  147.77  5366.7  150.16
#Mann=3,-1,0
  4603.9    0.12       0  5000.4    0.05       0  5004.4    0.12       0
Bank Sta=5000.4,5004.4
Exp/Cntr=0.3,0.1

Type RM Length L Ch R = 1,93,0,0,0
BEGIN DESCRIPTION:
Mapping XS 6559be8b
END DESCRIPTION:
XS GIS Cut Line= 4
      2537315.63     13545658.75      2537526.54     13545403.58
      2537555.18     13545256.44      2537534.35     13545035.08
#Sta/Elev= 30
  4640.3  133.47  4706.8  132.90  4805.7  136.21  4848.7  134.85  4883.9  135.00
  4898.2  134.06  4947.7  134.23  4962.1  133.54  4967.2  131.89  4980.1  131.98
  4987.3  129.78  4992.4  130.51  5010.7  123.73  5018.8  117.63  5019.1  117.13
  5022.8  117.63  5031.0  119.70  5039.0  126.72  5044.1  125.77  5061.6  127.02
  5082.0  132.16  5090.6  133.50  5095.7  132.88  5119.4  138.29  5124.5  138.29
  5132.7  140.57  5162.9  144.93  5177.2  145.17  5223.1  148.63  5343.6  150.48
#Mann=3,-1,0
  4640.3    0.12       0  5018.8    0.05       0  5022.8    0.12       0
Bank Sta=5018.8,5022.8
Exp/Cntr=0.3,0.1

Chan Stop Cuts=-1