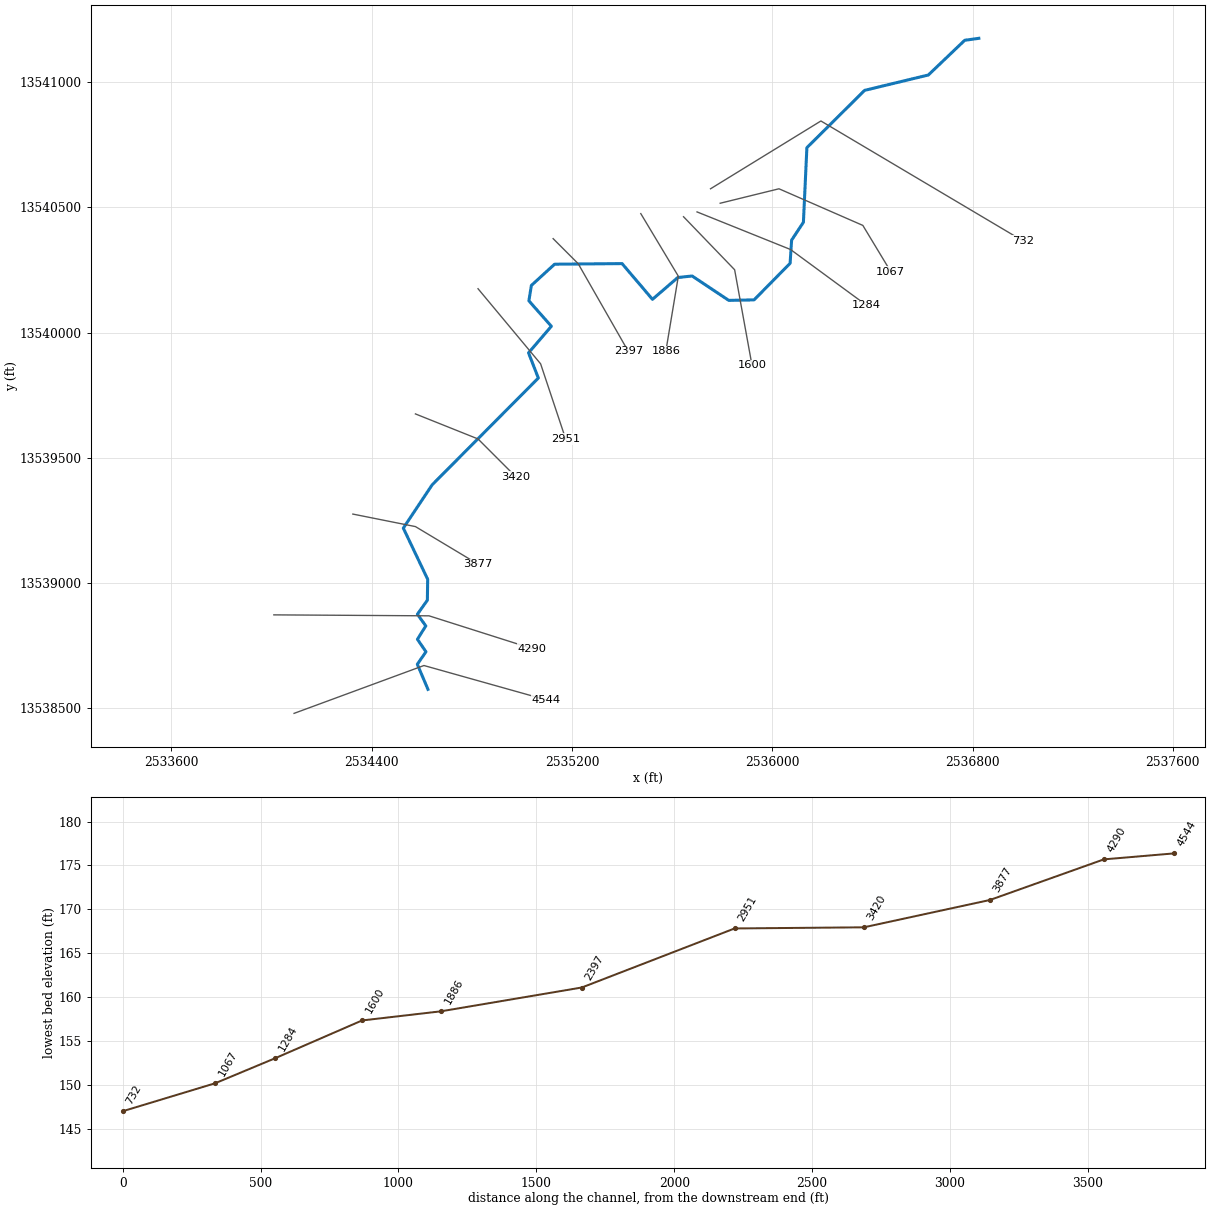
--- TRIB 12_2 TO GUADALUPE RIVER.prj (project) ---

Proj Title=TRIB 12_2 TO GUADALUPE RIVER Base Level Engineering
Current Plan=p01
Default Exp/Contr=0.3,0.1
English Units
Geom File=g01
Flow File=f01
Plan File=p01
Y Axis Title=Elevation
X Axis Title(PF)=Main Channel Distance
X Axis Title(XS)=Station
BEGIN DESCRIPTION:
TRIB 12_2 TO GUADALUPE RIVER
END DESCRIPTION:
DSS Export Rating Curves= 0
DSS Export Rating Curve Sorted= 0
DSS Export Volume Flow Curves= 0
DXF OffsetX= 0
DXF OffsetY= 0
DXF ScaleX= 1
DXF ScaleY= 10

--- TRIB 12_2 TO GUADALUPE RIVER.p01 (plan) ---

Plan Title=Multiple Run
Short Identifier=Multiple
Geom File=g01
Flow File=f01
Subcritical Flow
K Sum by GR= 0
Std Step Tol= 0.01
Critical Tol= 0.01
Num of Std Step Trials= 20
Max Error Tol= 0.3
Flow Tol Ratio= 0.001
Split Flow NTrial= 30
Split Flow Tol= 0.02
Split Flow Ratio= 0.02
Log Output Level= 0
Friction Slope Method= 1
Unsteady Friction Slope Method= 2
Unsteady Bridges Friction Slope Method= 1
Parabolic Critical Depth
Global Vel Dist=  1 , 1 , 1
Global Log Level= 0
CheckData=True
Encroach Param= -1, 0, 0, 0
BEGIN DESCRIPTION:
Multiple Run
END DESCRIPTION:

--- TRIB 12_2 TO GUADALUPE RIVER.f01 (steady flow) ---

Flow Title=Multiple
Number of Profiles=7
Profile Names=10-year,25-year,50-year,1pct_min,100-year,1pct_plu,500-year
River Rch & RM= TRIB 12_2 TO GUA,Reach-1,4544
     626    1006    1348     876    1747    3486    2900
River Rch & RM= TRIB 12_2 TO GUA,Reach-1,1284
     646    1038    1392     905    1805    3601    2998
Boundary for River Rch & Prof#=TRIB 12_2 TO GUA,Reach-1,1
Up Type=0
Dn Type=3
Dn Slope=0.005
Boundary for River Rch & Prof#=TRIB 12_2 TO GUA,Reach-1,2
Up Type=0
Dn Type=3
Dn Slope=0.005
Boundary for River Rch & Prof#=TRIB 12_2 TO GUA,Reach-1,3
Up Type=0
Dn Type=3
Dn Slope=0.005
Boundary for River Rch & Prof#=TRIB 12_2 TO GUA,Reach-1,4
Up Type=0
Dn Type=3
Dn Slope=0.005
Boundary for River Rch & Prof#=TRIB 12_2 TO GUA,Reach-1,5
Up Type=0
Dn Type=3
Dn Slope=0.005
Boundary for River Rch & Prof#=TRIB 12_2 TO GUA,Reach-1,6
Up Type=0
Dn Type=3
Dn Slope=0.005
Boundary for River Rch & Prof#=TRIB 12_2 TO GUA,Reach-1,7
Up Type=0
Dn Type=3
Dn Slope=0.005

--- TRIB 12_2 TO GUADALUPE RIVER.g01 (geometry) ---

Geom Title=Existing Conditions

River Reach=TRIB 12_2 TO GUA,Reach-1
Reach XY= 30
      2534625.00     13538575.00      2534582.56     13538675.07
      2534617.00     13538725.00      2534583.00     13538775.00
      2534616.46     13538828.33      2534582.79     13538874.90
      2534622.64     13538930.89      2534623.91     13539014.45
      2534526.62     13539218.96      2534641.65     13539391.67
      2535065.85     13539818.27      2535026.68     13539918.95
      2535117.90     13540025.00      2535028.12     13540126.65
      2535038.10     13540188.24      2535130.84     13540272.95
      2535400.21     13540275.33      2535521.65     13540132.59
      2535622.57     13540219.57      2535680.03     13540225.87
      2535826.50     13540128.47      2535927.43     13540130.40
      2536071.39     13540276.50      2536077.36     13540369.02
      2536124.48     13540440.22      2536138.37     13540738.32
      2536368.83     13540967.14      2536623.50     13541028.61
      2536768.79     13541167.24      2536825.00     13541175.00

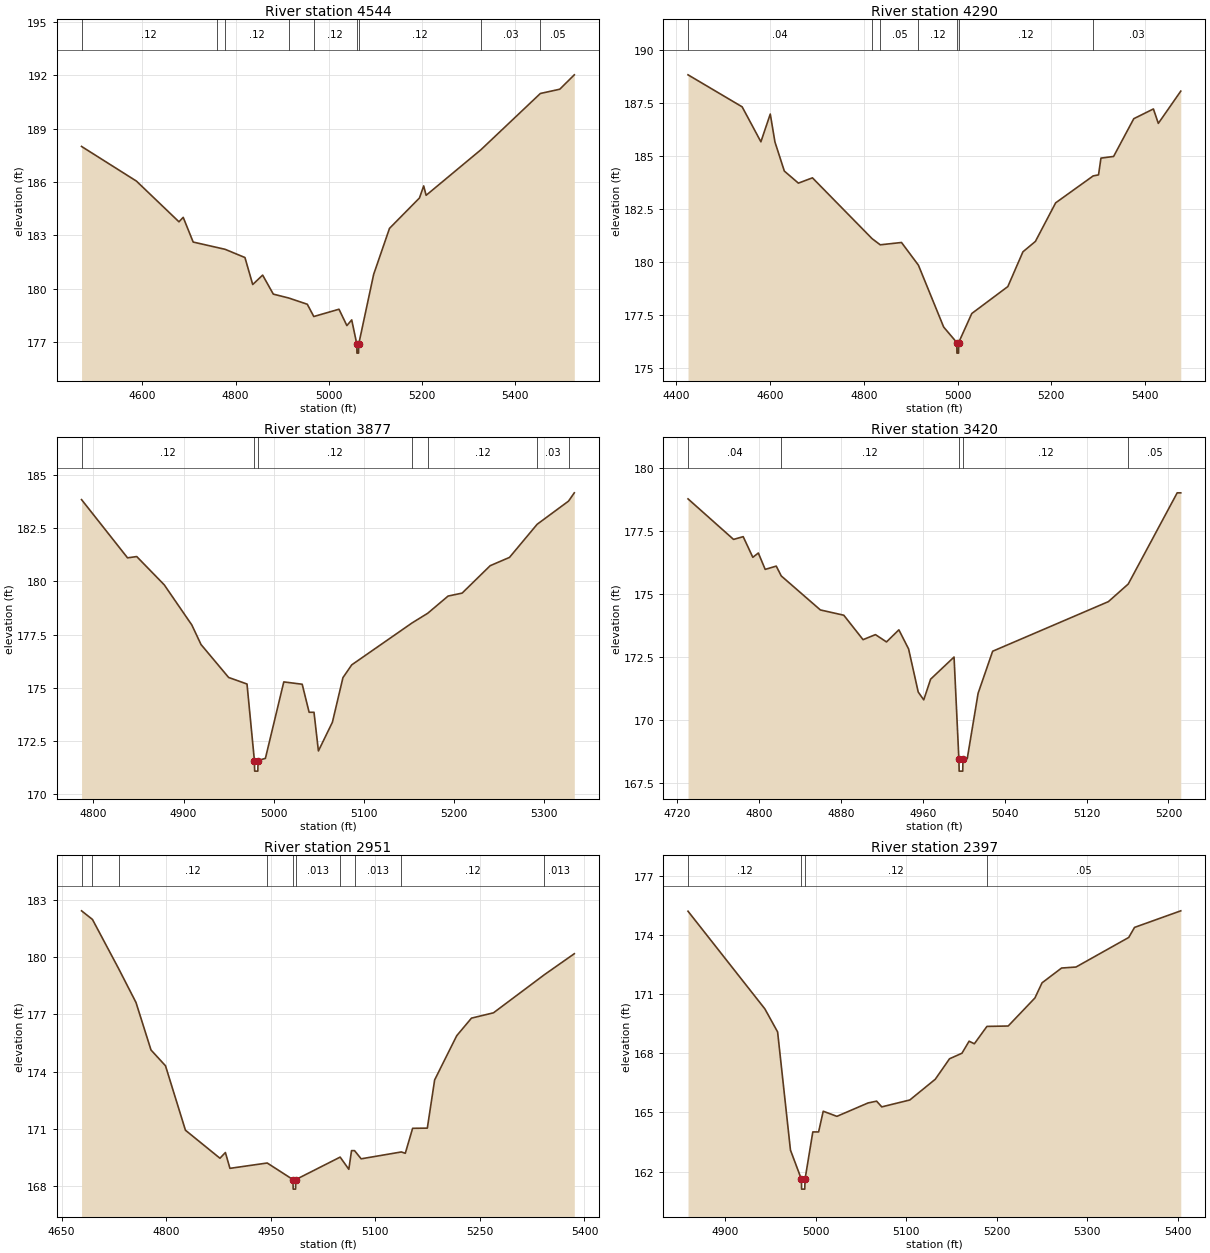
Type RM Length L Ch R = 1,4544,254,254,254
BEGIN DESCRIPTION:
Mapping XS deddf167
END DESCRIPTION:
XS GIS Cut Line= 3
      2534090.24     13538479.02      2534609.01     13538670.14
      2535095.04     13538533.62
#Sta/Elev= 30
  4469.4  188.00  4587.2  186.05  4678.5  183.76  4687.6  184.01  4709.0  182.62
  4759.4  182.32  4777.7  182.21  4820.1  181.75  4836.8  180.23  4858.1  180.76
  4881.0  179.69  4914.3  179.47  4954.0  179.12  4967.9  178.43  5022.0  178.84
  5038.9  177.92  5049.3  178.24  5060.3  176.87  5060.5  176.37  5064.0  176.37
  5064.3  176.87  5096.4  180.80  5130.4  183.39  5194.7  185.10  5203.8  185.78
  5209.0  185.25  5326.9  187.82  5454.2  190.98  5495.9  191.22  5527.1  192.03
#Mann=9,-1,0
  4469.4    0.12       0  4759.4    0.05       0  4777.7    0.12       0
  4914.3    0.05       0  4967.9    0.12       0  5060.3    0.05       0
  5064.3    0.12       0  5326.9    0.03       0  5454.2    0.05       0
Bank Sta=5060.3,5064.3
Exp/Cntr=0.3,0.1

Type RM Length L Ch R = 1,4290,413,413,413
BEGIN DESCRIPTION:
Mapping XS 301d26f3
END DESCRIPTION:
XS GIS Cut Line= 3
      2534009.50     13538872.45      2534629.38     13538868.60
      2535040.63     13538737.92
#Sta/Elev= 30
  4425.0  188.82  4540.5  187.31  4580.5  185.66  4600.5  186.97  4610.5  185.65
  4630.5  184.28  4660.5  183.71  4690.5  183.96  4817.8  181.09  4835.2  180.80
  4880.5  180.91  4916.6  179.84  4970.5  176.92  4998.5  176.19  4998.8  175.69
  5002.3  175.69  5002.5  176.19  5030.5  177.56  5107.4  178.83  5139.6  180.47
  5166.2  180.96  5209.4  182.78  5289.4  184.05  5300.9  184.10  5306.1  184.89
  5333.1  184.97  5376.1  186.75  5418.0  187.21  5428.5  186.53  5476.4  188.05
#Mann=7,-1,0
  4425.0    0.04       0  4817.8    0.12       0  4835.2    0.05       0
  4916.6    0.12       0  4998.5    0.05       0  5002.5    0.12       0
  5289.4    0.03       0
Bank Sta=4998.5,5002.5
Exp/Cntr=0.3,0.1

Type RM Length L Ch R = 1,3877,457,457,457
BEGIN DESCRIPTION:
TRIB 12_2 TO GUADALUPE RIVER 7.0
END DESCRIPTION:
XS GIS Cut Line= 3
      2534325.03     13539274.99      2534575.00     13539225.00
      2534825.03     13539074.98
#Sta/Elev= 30
  4786.8  183.85  4837.8  181.11  4848.0  181.17  4878.5  179.84  4909.1  177.95
  4919.3  177.03  4949.9  175.48  4970.3  175.17  4978.5  171.57  4978.8  171.07
  4982.3  171.07  4982.5  171.57  4990.7  171.67  5011.1  175.27  5031.5  175.16
  5039.2  173.84  5044.6  173.84  5049.5  172.02  5065.0  173.37  5076.7  175.47
  5086.4  176.07  5153.5  178.05  5170.7  178.50  5193.3  179.31  5208.9  179.45
  5240.0  180.74  5261.4  181.13  5292.1  182.69  5326.9  183.78  5333.3  184.17
#Mann=7,-1,0
  4786.8    0.12       0  4978.5    0.05       0  4982.5    0.12       0
  5153.5    0.03       0  5170.7    0.12       0  5292.1    0.03       0
  5326.9    0.12       0
Bank Sta=4978.5,4982.5
Exp/Cntr=0.3,0.1

Type RM Length L Ch R = 1,3420,469,469,469
BEGIN DESCRIPTION:
TRIB 12_2 TO GUADALUPE RIVER 6.0
END DESCRIPTION:
XS GIS Cut Line= 3
      2534574.96     13539675.02      2534825.00     13539575.00
      2534974.98     13539425.02
#Sta/Elev= 30
  4730.7  178.77  4775.2  177.16  4784.6  177.27  4794.0  176.45  4799.4  176.62
  4806.1  175.97  4816.9  176.10  4821.8  175.71  4860.0  174.36  4882.9  174.15
  4901.7  173.18  4913.8  173.38  4924.6  173.09  4936.7  173.57  4946.2  172.81
  4955.6  171.10  4961.0  170.79  4967.7  171.61  4990.6  172.49  4995.3  168.46
  4995.6  167.96  4999.1  167.96  4999.3  168.46  5003.5  168.46  5014.1  171.05
  5028.3  172.72  5141.4  174.69  5160.8  175.39  5208.6  179.01  5212.1  179.01
#Mann=5,-1,0
  4730.7    0.04       0  4821.8    0.12       0  4995.3    0.05       0
  4999.3    0.12       0  5160.8    0.05       0
Bank Sta=4995.3,4999.3
Exp/Cntr=0.3,0.1

Type RM Length L Ch R = 1,2951,554,554,554
BEGIN DESCRIPTION:
TRIB 12_2 TO GUADALUPE RIVER 5.0
END DESCRIPTION:
XS GIS Cut Line= 3
      2534825.01     13540174.99      2535075.00     13539875.00
      2535174.99     13539575.02
#Sta/Elev= 30
  4678.7  182.43  4694.3  181.98  4731.7  179.41  4756.8  177.62  4778.3  175.13
  4799.1  174.30  4827.7  170.92  4877.2  169.45  4885.0  169.75  4891.5  168.92
  4945.0  169.20  4981.9  168.33  4982.2  167.83  4985.7  167.83  4985.9  168.33
  5049.6  169.51  5062.0  168.87  5065.9  169.85  5070.2  169.85  5079.7  169.42
  5137.3  169.78  5143.0  169.71  5153.5  171.02  5174.6  171.03  5185.1  173.56
  5216.8  175.88  5237.9  176.80  5269.5  177.08  5342.5  179.08  5385.4  180.18
#Mann=10,-1,0
  4678.7    0.04       0  4694.3    0.03       0  4731.7    0.12       0
  4945.0   0.013       0  4981.9    0.03       0  4985.9   0.013       0
  5049.6    0.12       0  5070.2   0.013       0  5137.3    0.12       0
  5342.5   0.013       0
Bank Sta=4981.9,4985.9
Exp/Cntr=0.3,0.1

Type RM Length L Ch R = 1,2397,511,511,511
BEGIN DESCRIPTION:
TRIB 12_2 TO GUADALUPE RIVER 4.0
END DESCRIPTION:
XS GIS Cut Line= 3
      2535124.99     13540375.01      2535225.00     13540275.00
      2535424.98     13539925.04
#Sta/Elev= 30
  4858.7  175.20  4943.6  170.25  4957.7  169.08  4971.9  163.09  4984.0  161.61
  4984.2  161.11  4987.7  161.11  4988.0  161.61  4996.6  164.01  5003.0  164.01
  5008.1  165.06  5023.2  164.80  5057.7  165.48  5067.1  165.57  5072.8  165.28
  5103.8  165.63  5131.9  166.68  5147.7  167.72  5161.4  168.00  5169.3  168.61
  5175.1  168.48  5189.0  169.36  5212.5  169.38  5242.0  170.80  5249.9  171.57
  5271.5  172.32  5287.4  172.37  5345.7  173.87  5352.1  174.38  5403.2  175.22
#Mann=4,-1,0
  4858.7    0.12       0  4984.0    0.05       0  4988.0    0.12       0
  5189.0    0.05       0
Bank Sta=4984,4988
Exp/Cntr=0.3,0.1

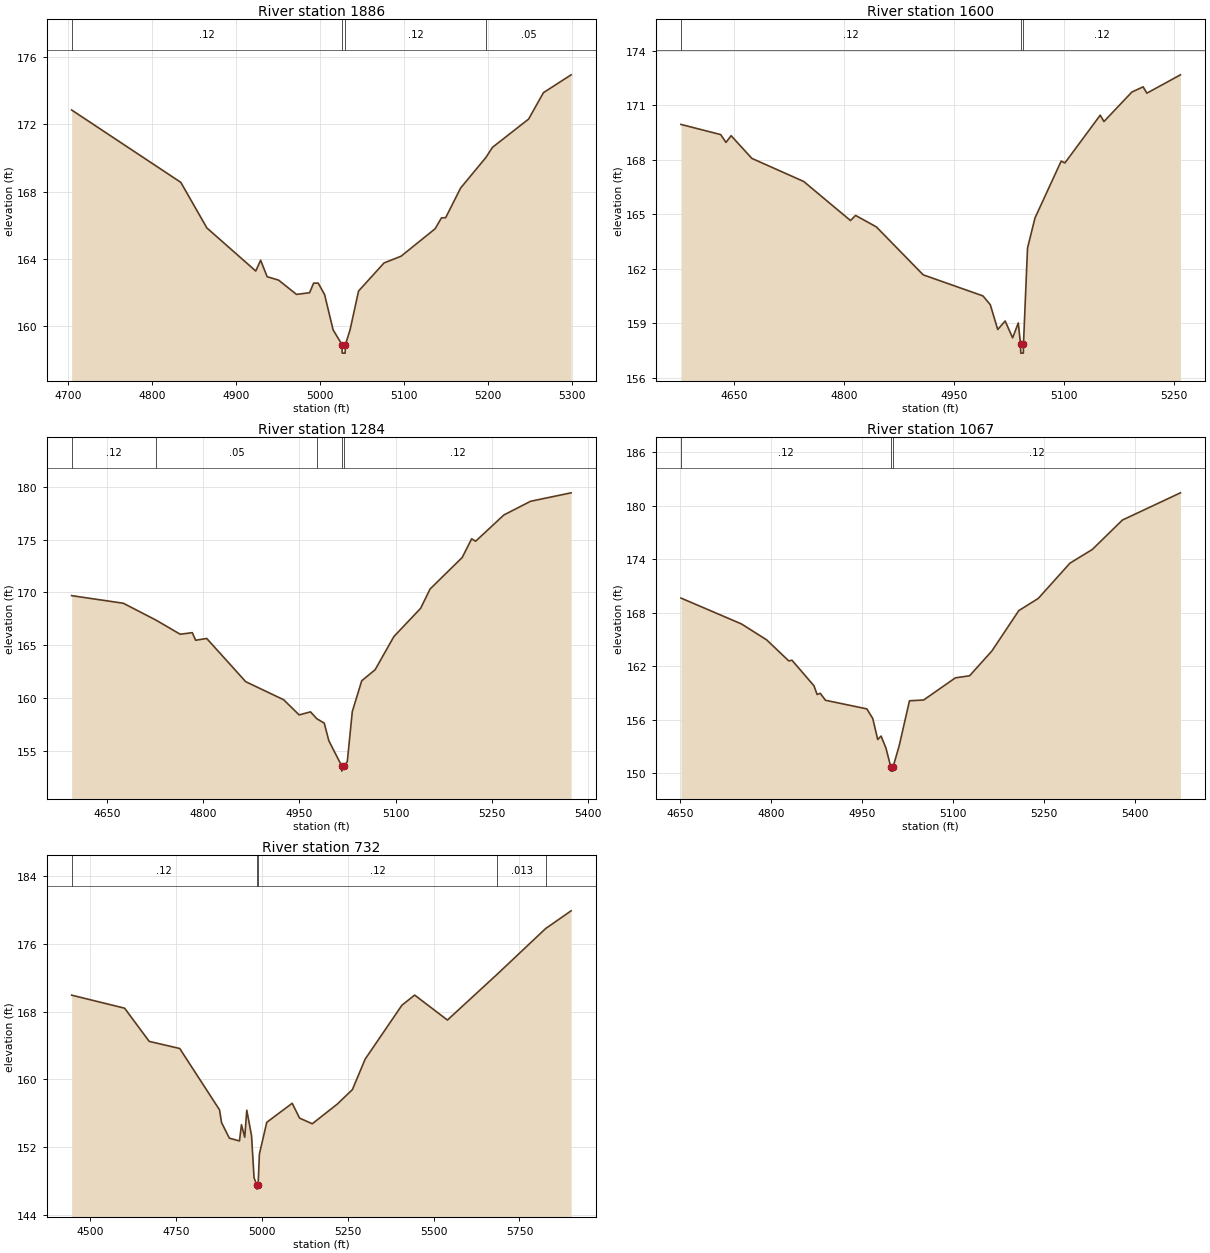
Type RM Length L Ch R = 1,1886,286,286,286
BEGIN DESCRIPTION:
TRIB 12_2 TO GUADALUPE RIVER 3.0
END DESCRIPTION:
XS GIS Cut Line= 3
      2535475.01     13540474.99      2535625.00     13540225.00
      2535575.00     13539924.97
#Sta/Elev= 30
  4703.8  172.85  4834.0  168.55  4865.1  165.84  4923.4  163.28  4929.2  163.92
  4937.0  162.94  4950.6  162.74  4972.0  161.89  4987.6  161.99  4992.4  162.56
  4997.9  162.56  5005.5  161.88  5015.6  159.79  5026.3  158.90  5026.5  158.40
  5030.0  158.40  5030.3  158.90  5035.9  159.79  5046.0  162.09  5076.4  163.76
  5096.7  164.16  5137.3  165.79  5144.9  166.44  5149.9  166.45  5167.7  168.21
  5197.9  170.03  5205.7  170.63  5248.8  172.31  5266.5  173.88  5299.5  174.94
#Mann=4,-1,0
  4703.8    0.12       0  5026.3    0.05       0  5030.3    0.12       0
  5197.9    0.05       0
Bank Sta=5026.3,5030.3
Exp/Cntr=0.3,0.1

Type RM Length L Ch R = 1,1600,316,316,316
BEGIN DESCRIPTION:
Mapping XS d26f62a1
END DESCRIPTION:
XS GIS Cut Line= 3
      2535645.75     13540462.53      2535849.83     13540250.75
      2535919.09     13539869.80
#Sta/Elev= 30
  4577.2  169.95  4631.4  169.39  4638.6  168.96  4645.6  169.33  4673.9  168.08
  4744.6  166.81  4808.4  164.66  4815.4  164.94  4843.7  164.31  4907.6  161.67
  4989.1  160.51  4999.1  160.03  5009.3  158.66  5019.4  159.13  5029.6  158.20
  5037.3  159.02  5040.4  157.86  5040.7  157.36  5044.2  157.36  5044.4  157.86
  5049.9  163.14  5060.1  164.80  5095.8  167.93  5100.9  167.83  5149.1  170.46
  5154.2  170.11  5192.2  171.73  5207.6  172.02  5212.7  171.67  5258.5  172.68
#Mann=3,-1,0
  4577.2    0.12       0  5040.4    0.05       0  5044.4    0.12       0
Bank Sta=5040.4,5044.4
Exp/Cntr=0.3,0.1

Type RM Length L Ch R = 1,1284,217,217,217
BEGIN DESCRIPTION:
Mapping XS 044db882
END DESCRIPTION:
XS GIS Cut Line= 3
      2535699.68     13540481.75      2536073.13     13540331.60
      2536376.13     13540109.14
#Sta/Elev= 30
  4595.2  169.69  4675.7  168.97  4726.7  167.37  4764.4  166.03  4783.2  166.18
  4788.5  165.46  4805.7  165.63  4866.5  161.53  4925.6  159.82  4949.8  158.38
  4967.4  158.67  4977.3  158.02  4988.9  157.60  4996.0  155.94  5016.0  153.55
  5016.2  153.05  5020.0  153.55  5024.8  153.96  5032.6  158.70  5047.3  161.62
  5068.1  162.66  5097.4  165.81  5139.1  168.49  5153.8  170.32  5203.9  173.31
  5218.6  175.08  5224.8  174.85  5268.8  177.34  5310.5  178.64  5373.6  179.44
#Mann=5,-1,0
  4595.2    0.12       0  4726.7    0.05       0  4977.3    0.12       0
  5016.0    0.05       0  5020.0    0.12       0
Bank Sta=5016,5020
Exp/Cntr=0.3,0.1

Type RM Length L Ch R = 1,1067,335,335,335
BEGIN DESCRIPTION:
Mapping XS a07231b1
END DESCRIPTION:
XS GIS Cut Line= 4
      2535792.11     13540516.41      2536026.93     13540574.15
      2536361.88     13540427.85      2536473.51     13540243.07
#Sta/Elev= 30
  4651.1  169.65  4750.9  166.74  4792.4  164.95  4828.8  162.59  4834.0  162.67
  4870.3  159.80  4875.5  158.82  4880.7  158.95  4889.3  158.17  4957.5  157.20
  4967.2  156.12  4975.4  153.76  4980.9  154.15  4989.0  152.79  4996.8  150.71
  4997.1  150.21  5000.6  150.21  5000.8  150.71  5010.8  153.07  5027.7  158.11
  5051.1  158.20  5103.4  160.69  5126.8  160.92  5163.6  163.71  5207.9  168.24
  5240.0  169.61  5292.2  173.57  5329.1  175.11  5378.6  178.41  5474.3  181.47
#Mann=3,-1,0
  4651.1    0.12       0  4996.8    0.05       0  5000.8    0.12       0
Bank Sta=4996.8,5000.8
Exp/Cntr=0.3,0.1

Type RM Length L Ch R = 1,732,0,0,0
BEGIN DESCRIPTION:
TRIB 12_2 TO GUADALUPE RIVER 1.0
END DESCRIPTION:
XS GIS Cut Line= 3
      2535753.56     13540574.14      2536194.37     13540844.93
      2537000.47     13540366.55
#Sta/Elev= 30
  4445.8  169.94  4600.1  168.40  4671.7  164.48  4760.6  163.64  4876.6  156.39
  4882.4  154.89  4905.2  153.05  4934.6  152.72  4940.4  154.64  4950.0  153.16
  4955.9  156.35  4969.7  153.37  4977.1  148.38  4984.9  147.53  4985.1  147.03
  4988.9  147.53  4992.7  151.18  5014.1  154.92  5088.2  157.17  5109.6  155.42
  5146.6  154.75  5219.7  157.08  5263.6  158.79  5300.6  162.38  5407.7  168.75
  5444.8  169.95  5540.3  167.00  5686.0  172.44  5826.4  177.81  5900.5  179.90
#Mann=5,-1,0
  4445.8    0.12       0  4984.9    0.05       0  4988.9    0.12       0
  5686.0   0.013       0  5826.4    0.04       0
Bank Sta=4984.9,4988.9
Exp/Cntr=0.3,0.1

Chan Stop Cuts=-1