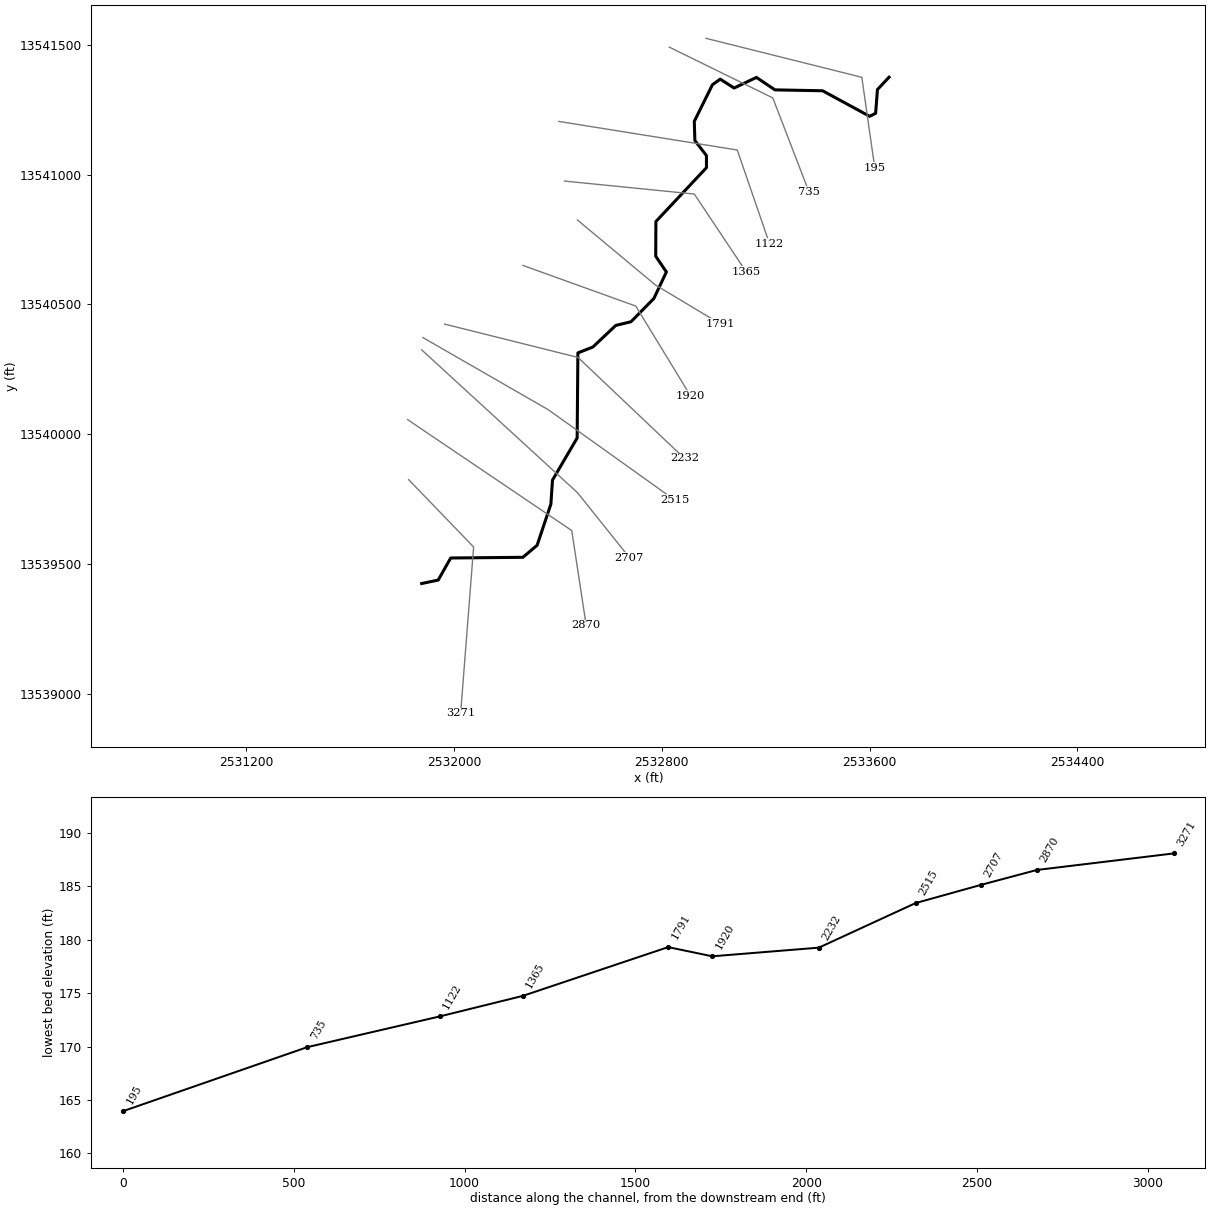
--- TRIB 12_3 TO GUADALUPE RIVER.prj (project) ---

Proj Title=TRIB 12_3 TO GUADALUPE RIVER Base Level Engineering
Current Plan=p01
Default Exp/Contr=0.3,0.1
English Units
Geom File=g01
Flow File=f01
Plan File=p01
Y Axis Title=Elevation
X Axis Title(PF)=Main Channel Distance
X Axis Title(XS)=Station
BEGIN DESCRIPTION:
TRIB 12_3 TO GUADALUPE RIVER
END DESCRIPTION:
DSS Export Rating Curves= 0
DSS Export Rating Curve Sorted= 0
DSS Export Volume Flow Curves= 0
DXF OffsetX= 0
DXF OffsetY= 0
DXF ScaleX= 1
DXF ScaleY= 10

--- TRIB 12_3 TO GUADALUPE RIVER.p01 (plan) ---

Plan Title=Multiple Run
Short Identifier=Multiple
Geom File=g01
Flow File=f01
Subcritical Flow
K Sum by GR= 0
Std Step Tol= 0.01
Critical Tol= 0.01
Num of Std Step Trials= 20
Max Error Tol= 0.3
Flow Tol Ratio= 0.001
Split Flow NTrial= 30
Split Flow Tol= 0.02
Split Flow Ratio= 0.02
Log Output Level= 0
Friction Slope Method= 1
Unsteady Friction Slope Method= 2
Unsteady Bridges Friction Slope Method= 1
Parabolic Critical Depth
Global Vel Dist=  1 , 1 , 1
Global Log Level= 0
CheckData=True
Encroach Param= -1, 0, 0, 0
BEGIN DESCRIPTION:
Multiple Run
END DESCRIPTION:

--- TRIB 12_3 TO GUADALUPE RIVER.f01 (steady flow) ---

Flow Title=Multiple
Number of Profiles=7
Profile Names=10-year,25-year,50-year,1pct_min,100-year,1pct_plu,500-year
River Rch & RM= TRIB 12_3 TO GUA,Reach-1,3271
     431     672     884     563    1124    2242    1794
Boundary for River Rch & Prof#=TRIB 12_3 TO GUA,Reach-1,1
Up Type=0
Dn Type=3
Dn Slope=0.005
Boundary for River Rch & Prof#=TRIB 12_3 TO GUA,Reach-1,2
Up Type=0
Dn Type=3
Dn Slope=0.005
Boundary for River Rch & Prof#=TRIB 12_3 TO GUA,Reach-1,3
Up Type=0
Dn Type=3
Dn Slope=0.005
Boundary for River Rch & Prof#=TRIB 12_3 TO GUA,Reach-1,4
Up Type=0
Dn Type=3
Dn Slope=0.005
Boundary for River Rch & Prof#=TRIB 12_3 TO GUA,Reach-1,5
Up Type=0
Dn Type=3
Dn Slope=0.005
Boundary for River Rch & Prof#=TRIB 12_3 TO GUA,Reach-1,6
Up Type=0
Dn Type=3
Dn Slope=0.005
Boundary for River Rch & Prof#=TRIB 12_3 TO GUA,Reach-1,7
Up Type=0
Dn Type=3
Dn Slope=0.005

--- TRIB 12_3 TO GUADALUPE RIVER.g01 (geometry) ---

Geom Title=Existing Conditions

River Reach=TRIB 12_3 TO GUA,Reach-1
Reach XY= 30
      2531875.00     13539425.00      2531938.74     13539438.37
      2531986.81     13539523.38      2532264.74     13539525.98
      2532319.60     13539572.29      2532372.65     13539730.97
      2532378.83     13539823.42      2532473.80     13539985.50
      2532476.62     13540313.17      2532534.36     13540335.93
      2532622.72     13540419.13      2532681.07     13540433.15
      2532769.20     13540522.70      2532817.47     13540624.99
      2532776.37     13540685.44      2532777.05     13540819.14
      2532971.87     13541026.63      2532971.66     13541073.25
      2532927.19     13541130.97      2532924.89     13541204.91
      2532994.78     13541345.99      2533024.78     13541367.54
      2533078.22     13541333.33      2533164.29     13541374.19
      2533235.50     13541326.24      2533419.07     13541322.76
      2533600.31     13541224.37      2533623.32     13541236.15
      2533630.26     13541327.45      2533675.00     13541375.00

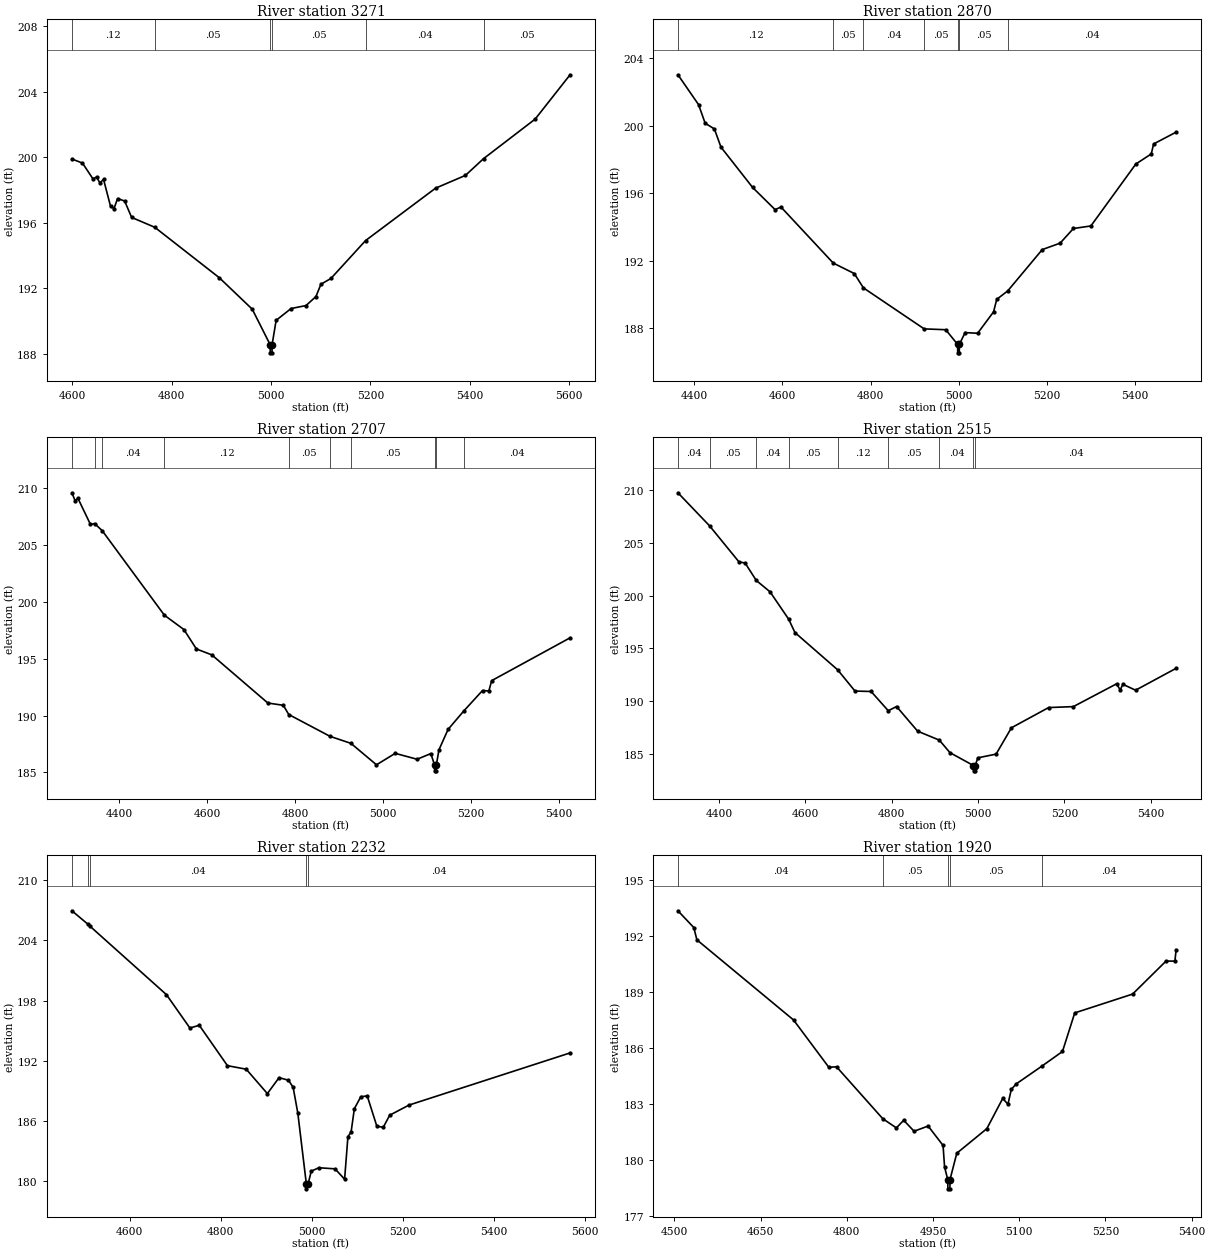
Type RM Length L Ch R = 1,3271,401,401,401
BEGIN DESCRIPTION:
TRIB 12_3 TO GUADALUPE RIVER 6.0
END DESCRIPTION:
XS GIS Cut Line= 3
      2531824.97     13539825.03      2532075.09     13539565.75
      2532025.00     13538924.96
#Sta/Elev= 30
  4599.0  199.89  4620.3  199.64  4641.4  198.68  4648.6  198.79  4655.5  198.43
  4662.7  198.65  4676.9  197.00  4683.8  196.87  4691.0  197.48  4705.2  197.33
  4719.3  196.33  4765.8  195.73  4896.0  192.65  4962.1  190.74  4998.1  188.58
  4998.4  188.08  5001.9  188.08  5002.1  188.58  5010.2  190.06  5040.3  190.78
  5070.3  190.96  5090.4  191.51  5100.4  192.26  5120.5  192.61  5190.3  194.92
  5331.1  198.11  5391.3  198.89  5427.8  199.91  5531.7  202.32  5602.0  205.02
#Mann=6,-1,0
  4599.0    0.12       0  4765.8    0.05       0  4998.1    0.05       0
  5002.1    0.05       0  5190.3    0.04       0  5427.8    0.05       0
Bank Sta=4998.1,5002.1
Exp/Cntr=0.3,0.1

Type RM Length L Ch R = 1,2870,163,163,163
BEGIN DESCRIPTION:
Mapping XS 24956778
END DESCRIPTION:
XS GIS Cut Line= 3
      2531821.02     13540056.14      2532452.98     13539629.04
      2532508.53     13539264.50
#Sta/Elev= 30
  4362.5  203.01  4409.4  201.24  4424.3  200.14  4445.3  199.80  4460.3  198.72
  4532.2  196.33  4583.1  195.02  4596.6  195.17  4715.3  191.85  4763.0  191.23
  4783.8  190.38  4921.8  187.95  4970.8  187.90  4997.7  187.03  4998.0  186.53
  5001.5  186.53  5001.7  187.03  5014.7  187.73  5043.2  187.69  5079.4  188.96
  5086.6  189.70  5111.5  190.20  5190.0  192.65  5230.5  193.03  5260.8  193.90
  5300.4  194.05  5402.5  197.72  5437.6  198.32  5442.9  198.91  5494.0  199.61
#Mann=7,-1,0
  4362.5    0.12       0  4715.3    0.05       0  4783.8    0.04       0
  4921.8    0.05       0  4997.7    0.05       0  5001.7    0.05       0
  5111.5    0.04       0
Bank Sta=4997.7,5001.7
Exp/Cntr=0.3,0.1

Type RM Length L Ch R = 1,2707,192,192,192
BEGIN DESCRIPTION:
TRIB 12_3 TO GUADALUPE RIVER 5.0
END DESCRIPTION:
XS GIS Cut Line= 3
      2531874.98     13540325.01      2532475.00     13539775.00
      2532674.99     13539525.01
#Sta/Elev= 30
  4292.2  209.62  4299.3  208.94  4306.1  209.12  4334.5  206.83  4344.0  206.91
  4361.3  206.28  4502.8  198.84  4547.2  197.58  4575.6  195.87  4610.7  195.35
  4738.3  191.11  4773.5  190.91  4785.9  190.10  4879.7  188.18  4927.4  187.56
  4985.6  185.67  5028.2  186.68  5078.1  186.16  5109.4  186.66  5117.8  185.64
  5118.0  185.14  5121.5  185.14  5121.8  185.64  5127.8  186.99  5148.6  188.79
  5184.1  190.40  5227.0  192.21  5241.4  192.17  5247.8  193.08  5426.3  196.85
#Mann=10,-1,0
  4292.2    0.04       0  4344.0    0.05       0  4361.3    0.04       0
  4502.8    0.12       0  4785.9    0.05       0  4879.7    0.04       0
  4927.4    0.05       0  5117.8    0.05       0  5121.8    0.05       0
  5184.1    0.04       0
Bank Sta=5117.8,5121.8
Exp/Cntr=0.3,0.1

Type RM Length L Ch R = 1,2515,283,283,283
BEGIN DESCRIPTION:
Mapping XS d1a350b1
END DESCRIPTION:
XS GIS Cut Line= 3
      2531880.08     13540372.09      2532362.70     13540094.32
      2532848.79     13539747.12
#Sta/Elev= 30
  4304.6  209.71  4378.0  206.58  4446.0  203.18  4460.3  203.07  4486.2  201.42
  4518.0  200.35  4561.2  197.76  4575.7  196.50  4674.6  192.98  4714.8  190.97
  4752.2  190.93  4791.9  189.11  4811.1  189.51  4859.9  187.18  4910.3  186.33
  4934.8  185.15  4989.3  183.93  4989.6  183.43  4993.1  183.43  4993.3  183.93
  4999.5  184.66  5041.7  185.01  5077.3  187.50  5163.4  189.41  5220.7  189.50
  5320.7  191.65  5329.3  191.08  5335.4  191.61  5364.9  191.05  5458.8  193.12
#Mann=9,-1,0
  4304.6    0.04       0  4378.0    0.05       0  4486.2    0.04       0
  4561.2    0.05       0  4674.6    0.12       0  4791.9    0.05       0
  4910.3    0.04       0  4989.3    0.04       0  4993.3    0.04       0
Bank Sta=4989.3,4993.3
Exp/Cntr=0.3,0.1

Type RM Length L Ch R = 1,2232,312,312,312
BEGIN DESCRIPTION:
Mapping XS 975b0e7d
END DESCRIPTION:
XS GIS Cut Line= 3
      2531963.43     13540424.17      2532477.28     13540295.71
      2532887.03     13539906.80
#Sta/Elev= 30
  4473.2  206.94  4508.5  205.60  4512.8  205.41  4681.0  198.59  4732.5  195.27
  4753.1  195.54  4815.0  191.52  4856.2  191.17  4902.7  188.74  4928.4  190.33
  4949.0  190.07  4959.3  189.37  4969.6  186.80  4988.3  179.76  4988.5  179.26
  4992.3  179.76  4999.1  181.02  5015.8  181.36  5051.4  181.25  5072.4  180.22
  5079.7  184.46  5086.6  184.90  5093.8  187.23  5108.0  188.43  5122.1  188.51
  5143.2  185.50  5157.3  185.38  5171.5  186.59  5214.0  187.60  5567.8  192.79
#Mann=5,-1,0
  4473.2    0.04       0  4508.5    0.05       0  4512.8    0.04       0
  4988.3    0.04       0  4992.3    0.04       0
Bank Sta=4988.3,4992.3
Exp/Cntr=0.3,0.1

Type RM Length L Ch R = 1,1920,129,129,129
BEGIN DESCRIPTION:
Mapping XS 92df86cf
END DESCRIPTION:
XS GIS Cut Line= 3
      2532265.45     13540649.89      2532699.51     13540493.63
      2532910.66     13540147.47
#Sta/Elev= 30
  4506.1  193.37  4533.7  192.47  4539.1  191.81  4707.3  187.51  4768.7  184.97
  4782.0  185.00  4862.6  182.21  4886.2  181.72  4898.9  182.13  4917.0  181.54
  4941.4  181.82  4967.4  180.78  4970.0  179.63  4975.5  178.95  4975.8  178.45
  4979.3  178.45  4979.5  178.95  4991.3  180.36  5043.6  181.68  5071.2  183.30
  5080.3  182.99  5086.2  183.79  5094.7  184.08  5138.7  185.02  5175.2  185.82
  5196.5  187.89  5297.2  188.90  5355.3  190.67  5370.8  190.67  5372.9  191.28
#Mann=5,-1,0
  4506.1    0.04       0  4862.6    0.05       0  4975.5    0.05       0
  4979.5    0.05       0  5138.7    0.04       0
Bank Sta=4975.5,4979.5
Exp/Cntr=0.3,0.1

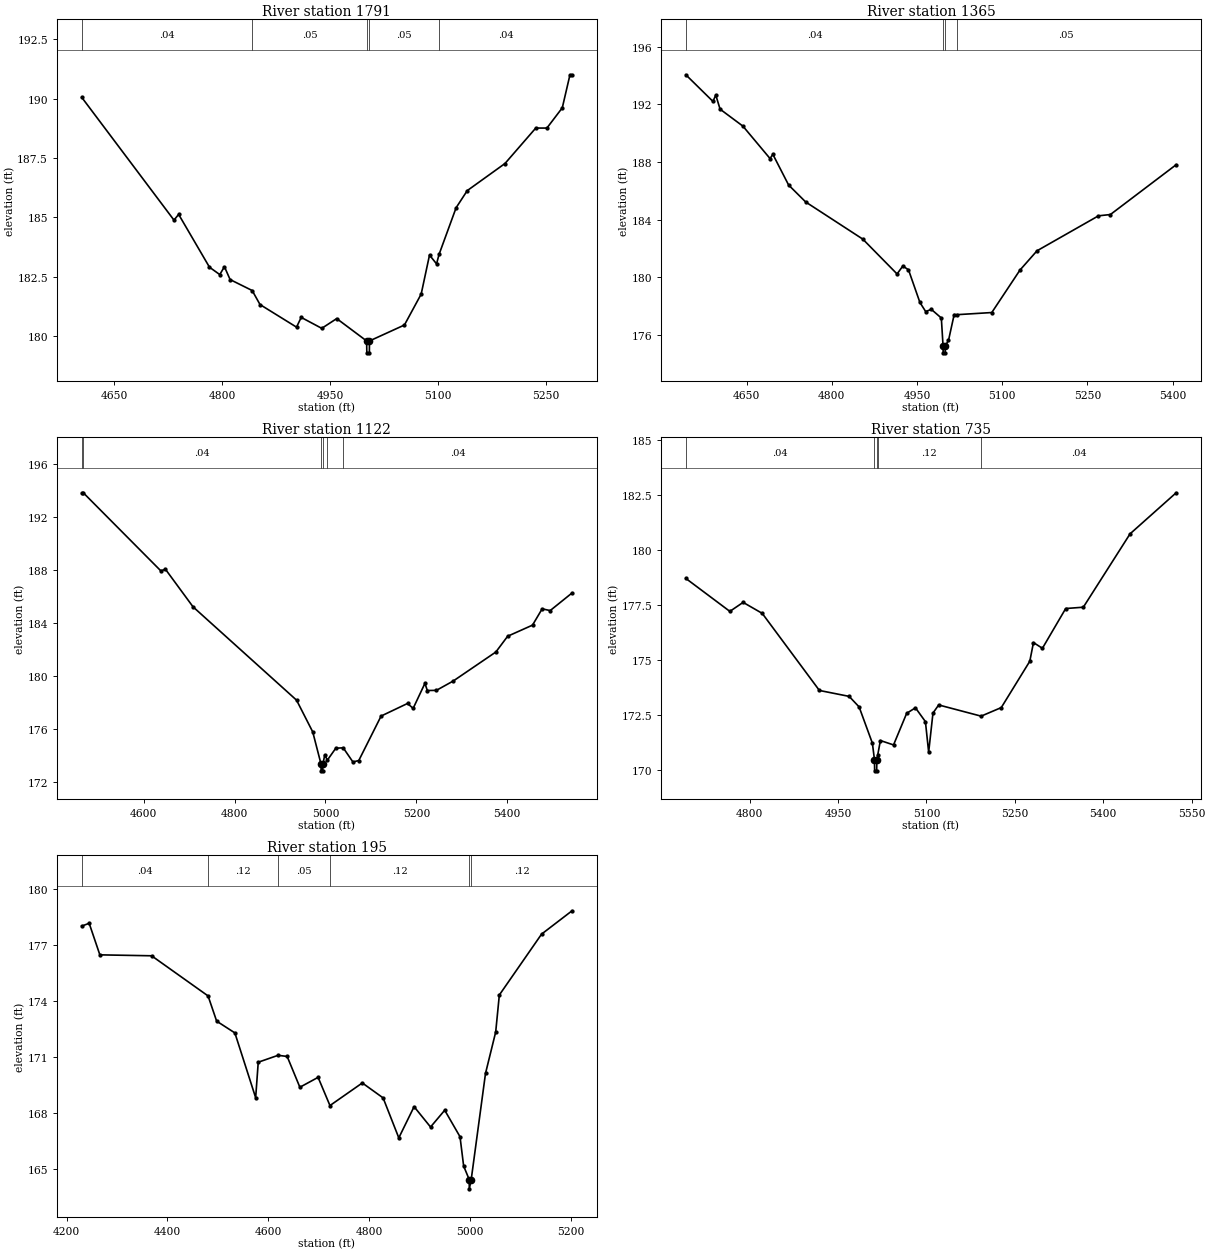
Type RM Length L Ch R = 1,1791,426,426,426
BEGIN DESCRIPTION:
TRIB 12_3 TO GUADALUPE RIVER 3.0
END DESCRIPTION:
XS GIS Cut Line= 3
      2532474.98     13540825.02      2532775.00     13540575.00
      2533025.01     13540425.00
#Sta/Elev= 30
  4604.6  190.05  4732.9  184.89  4739.4  185.13  4782.3  182.91  4796.6  182.60
  4803.1  182.93  4811.0  182.39  4841.7  181.93  4852.6  181.34  4903.4  180.39
  4909.9  180.80  4938.5  180.34  4959.3  180.75  5000.9  179.81  5001.2  179.31
  5004.7  179.31  5004.9  179.81  5053.5  180.48  5076.8  181.78  5088.4  183.42
  5098.2  183.05  5101.7  183.45  5125.4  185.41  5140.9  186.13  5193.4  187.27
  5236.2  188.76  5251.7  188.76  5273.1  189.61  5283.8  191.00  5286.7  191.00
#Mann=5,-1,0
  4604.6    0.04       0  4841.7    0.05       0  5000.9    0.05       0
  5004.9    0.05       0  5101.7    0.04       0
Bank Sta=5000.9,5004.9
Exp/Cntr=0.3,0.1

Type RM Length L Ch R = 1,1365,243,243,243
BEGIN DESCRIPTION:
TRIB 12_3 TO GUADALUPE RIVER 2.0
END DESCRIPTION:
XS GIS Cut Line= 3
      2532425.03     13540975.00      2532925.00     13540925.00
      2533124.99     13540625.01
#Sta/Elev= 30
  4543.2  194.06  4590.9  192.21  4595.9  192.65  4603.5  191.67  4643.7  190.49
  4691.4  188.24  4696.4  188.53  4724.1  186.40  4754.2  185.22  4854.7  182.64
  4915.0  180.22  4925.1  180.77  4935.1  180.51  4955.2  178.24  4965.3  177.61
  4975.3  177.76  4992.9  177.16  4995.9  175.24  4996.2  174.74  4999.7  174.74
  4999.9  175.24  5005.5  175.60  5015.5  177.40  5019.7  177.39  5081.7  177.54
  5131.3  180.49  5161.3  181.83  5269.5  184.26  5290.5  184.35  5406.2  187.81
#Mann=4,-1,0
  4543.2    0.04       0  4995.9    0.04       0  4999.9    0.04       0
  5019.7    0.05       0
Bank Sta=4995.9,4999.9
Exp/Cntr=0.3,0.1

Type RM Length L Ch R = 1,1122,387,387,387
BEGIN DESCRIPTION:
Mapping XS 71cc0ab2
END DESCRIPTION:
XS GIS Cut Line= 3
      2532403.16     13541204.69      2533090.33     13541094.64
      2533215.03     13540732.76
#Sta/Elev= 30
  4463.9  193.83  4467.6  193.82  4637.9  187.93  4648.1  188.05  4708.8  185.21
  4936.5  178.16  4972.1  175.76  4990.4  173.32  4990.6  172.82  4994.1  172.82
  4994.4  173.32  4998.5  174.02  5004.3  173.63  5022.8  174.53  5039.1  174.56
  5060.5  173.49  5073.4  173.60  5122.5  176.96  5180.6  177.91  5193.0  177.54
  5218.9  179.43  5224.2  178.89  5244.1  178.90  5281.3  179.61  5375.0  181.80
  5400.9  182.99  5455.6  183.83  5476.8  185.06  5494.5  184.93  5542.6  186.26
#Mann=6,-1,0
  4463.9    0.05       0  4467.6    0.04       0  4990.4    0.04       0
  4994.4    0.04       0  5004.3    0.12       0  5039.1    0.04       0
Bank Sta=4990.4,4994.4
Exp/Cntr=0.3,0.1

Type RM Length L Ch R = 1,735,540,540,540
BEGIN DESCRIPTION:
Mapping XS 67f5fa5f
END DESCRIPTION:
XS GIS Cut Line= 3
      2532828.63     13541490.82      2533227.28     13541295.17
      2533366.66     13540933.25
#Sta/Elev= 30
  4691.8  178.71  4766.5  177.21  4789.0  177.62  4821.4  177.12  4918.4  173.61
  4968.9  173.34  4985.8  172.86  5008.3  171.21  5011.9  170.45  5012.1  169.95
  5015.6  169.95  5015.9  170.45  5017.3  170.66  5021.9  171.33  5044.2  171.13
  5066.5  172.57  5081.4  172.82  5098.3  172.19  5103.8  170.80  5111.1  172.58
  5120.8  172.95  5192.8  172.44  5227.0  172.83  5275.4  174.94  5281.6  175.79
  5296.8  175.53  5336.3  177.34  5366.2  177.40  5445.5  180.74  5523.7  182.61
#Mann=5,-1,0
  4691.8    0.04       0  5011.9    0.04       0  5015.9    0.04       0
  5017.3    0.12       0  5192.8    0.04       0
Bank Sta=5011.9,5015.9
Exp/Cntr=0.3,0.1

Type RM Length L Ch R = 1,195,0,0,0
BEGIN DESCRIPTION:
TRIB 12_3 TO GUADALUPE RIVER 1.0
END DESCRIPTION:
XS GIS Cut Line= 3
      2532970.14     13541524.68      2533570.13     13541374.69
      2533620.06     13541025.19
#Sta/Elev= 30
  4230.1  178.02  4244.8  178.17  4266.0  176.48  4368.5  176.43  4480.4  174.28
  4497.4  172.93  4533.5  172.30  4574.7  168.83  4579.8  170.73  4619.1  171.10
  4637.1  171.04  4662.3  169.39  4698.4  169.92  4721.9  168.41  4786.0  169.62
  4827.2  168.82  4858.3  166.68  4888.6  168.35  4921.2  167.26  4949.3  168.16
  4979.6  166.74  4986.8  165.17  4997.8  164.45  4998.0  163.95  5001.8  164.45
  5030.1  170.13  5050.3  172.35  5057.5  174.33  5141.2  177.59  5201.6  178.84
#Mann=6,-1,0
  4230.1    0.04       0  4480.4    0.12       0  4619.1    0.05       0
  4721.9    0.12       0  4997.8    0.05       0  5001.8    0.12       0
Bank Sta=4997.8,5001.8
Exp/Cntr=0.3,0.1

Chan Stop Cuts=-1