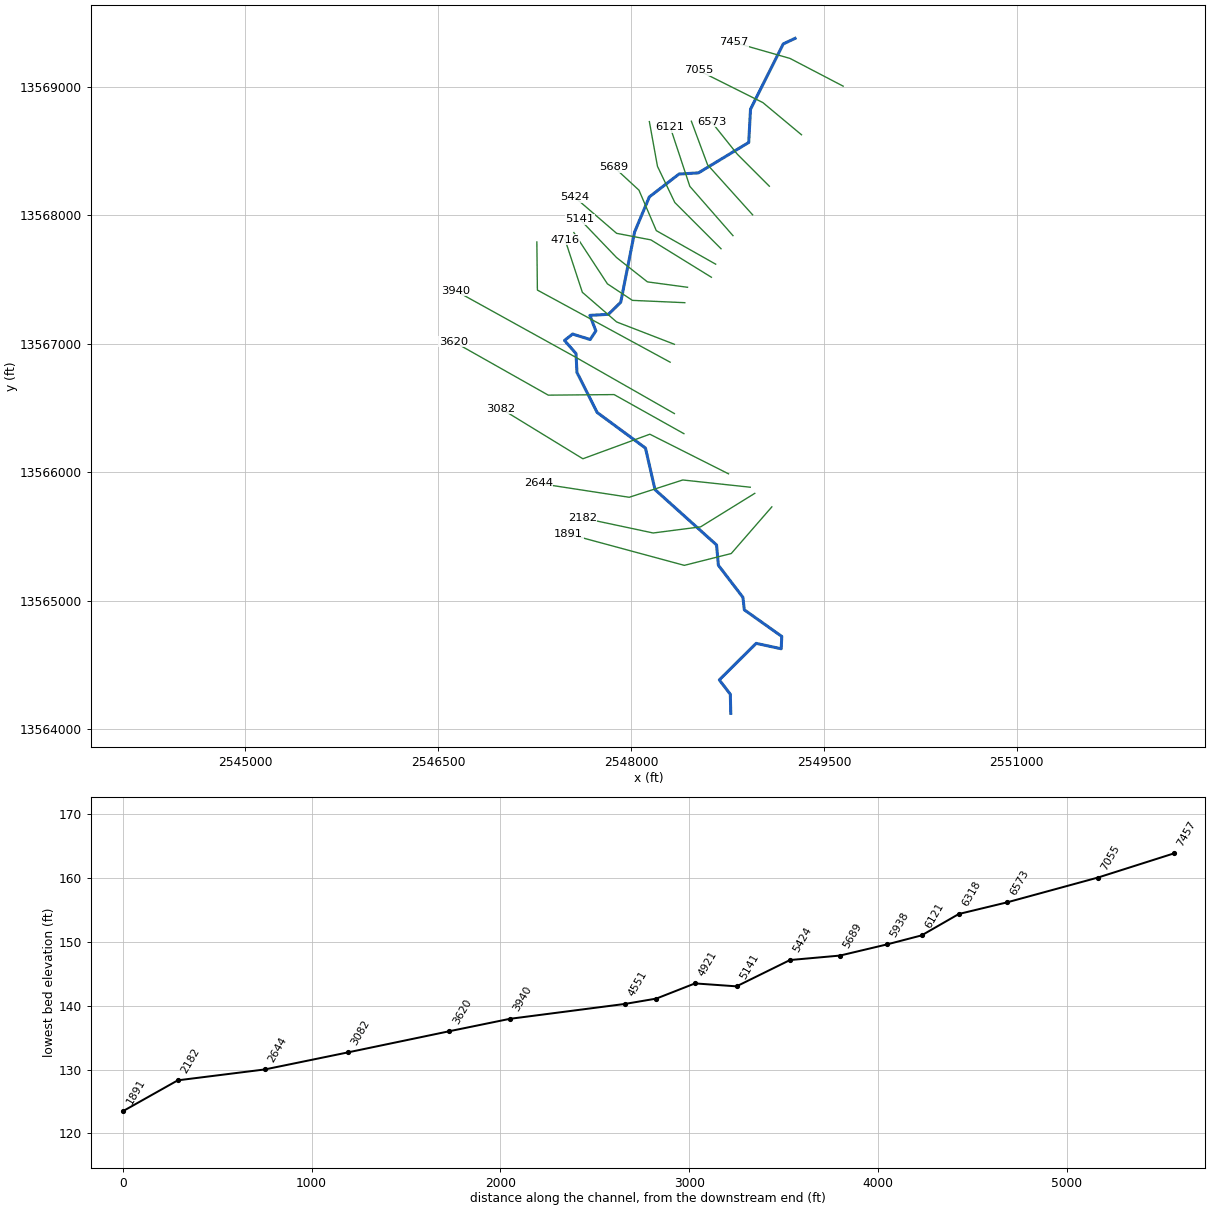
--- TRIB 13 TO GUADALUPE RIVER.prj (project) ---

Proj Title=TRIB 13 TO GUADALUPE RIVER Base Level Engineering
Current Plan=p01
Default Exp/Contr=0.3,0.1
English Units
Geom File=g01
Flow File=f01
Plan File=p01
Y Axis Title=Elevation
X Axis Title(PF)=Main Channel Distance
X Axis Title(XS)=Station
BEGIN DESCRIPTION:
TRIB 13 TO GUADALUPE RIVER
END DESCRIPTION:
DSS Export Rating Curves= 0
DSS Export Rating Curve Sorted= 0
DSS Export Volume Flow Curves= 0
DXF OffsetX= 0
DXF OffsetY= 0
DXF ScaleX= 1
DXF ScaleY= 10

--- TRIB 13 TO GUADALUPE RIVER.p01 (plan) ---

Plan Title=Multiple Run
Short Identifier=Multiple
Geom File=g01
Flow File=f01
Subcritical Flow
K Sum by GR= 0
Std Step Tol= 0.01
Critical Tol= 0.01
Num of Std Step Trials= 20
Max Error Tol= 0.3
Flow Tol Ratio= 0.001
Split Flow NTrial= 30
Split Flow Tol= 0.02
Split Flow Ratio= 0.02
Log Output Level= 0
Friction Slope Method= 1
Unsteady Friction Slope Method= 2
Unsteady Bridges Friction Slope Method= 1
Parabolic Critical Depth
Global Vel Dist=  1 , 1 , 1
Global Log Level= 0
CheckData=True
Encroach Param= -1, 0, 0, 0
BEGIN DESCRIPTION:
Multiple Run
END DESCRIPTION:

--- TRIB 13 TO GUADALUPE RIVER.f01 (steady flow) ---

Flow Title=Multiple
Number of Profiles=7
Profile Names=10-year,25-year,50-year,1pct_min,100-year,1pct_plu,500-year
River Rch & RM= TRIB 13 TO GUADA,Reach-1,7457
     503     799    1063     687    1372    2737    2255
River Rch & RM= TRIB 13 TO GUADA,Reach-1,6318
     548     875    1169     757    1511    3015    2497
River Rch & RM= TRIB 13 TO GUADA,Reach-1,4551
     922    1511    2052    1349    2692    5372    4586
Boundary for River Rch & Prof#=TRIB 13 TO GUADA,Reach-1,1
Up Type=0
Dn Type=3
Dn Slope=0.005
Boundary for River Rch & Prof#=TRIB 13 TO GUADA,Reach-1,2
Up Type=0
Dn Type=3
Dn Slope=0.005
Boundary for River Rch & Prof#=TRIB 13 TO GUADA,Reach-1,3
Up Type=0
Dn Type=3
Dn Slope=0.005
Boundary for River Rch & Prof#=TRIB 13 TO GUADA,Reach-1,4
Up Type=0
Dn Type=3
Dn Slope=0.005
Boundary for River Rch & Prof#=TRIB 13 TO GUADA,Reach-1,5
Up Type=0
Dn Type=3
Dn Slope=0.005
Boundary for River Rch & Prof#=TRIB 13 TO GUADA,Reach-1,6
Up Type=0
Dn Type=3
Dn Slope=0.005
Boundary for River Rch & Prof#=TRIB 13 TO GUADA,Reach-1,7
Up Type=0
Dn Type=3
Dn Slope=0.005

--- TRIB 13 TO GUADALUPE RIVER.g01 (geometry) ---

Geom Title=Existing Conditions

River Reach=TRIB 13 TO GUADA,Reach-1
Reach XY= 30
      2549275.00     13569375.00      2549182.96     13569331.31
      2548928.55     13568823.53      2548914.53     13568565.17
      2548523.53     13568328.55      2548372.56     13568319.52
      2548141.63     13568141.71      2548027.17     13567869.02
      2547919.18     13567322.69      2547823.54     13567228.53
      2547679.63     13567220.36      2547725.76     13567099.78
      2547681.43     13567032.35      2547544.90     13567075.39
      2547481.99     13567025.28      2547571.43     13566923.53
      2547578.76     13566776.56      2547735.76     13566465.30
      2548111.63     13566188.32      2548185.75     13565865.29
      2548664.52     13565434.80      2548678.76     13565276.56
      2548869.45     13565027.37      2548880.25     13564930.44
      2549171.58     13564723.48      2549167.28     13564627.41
      2548972.56     13564669.61      2548685.83     13564385.32
      2548771.48     13564273.55      2548775.00     13564125.00

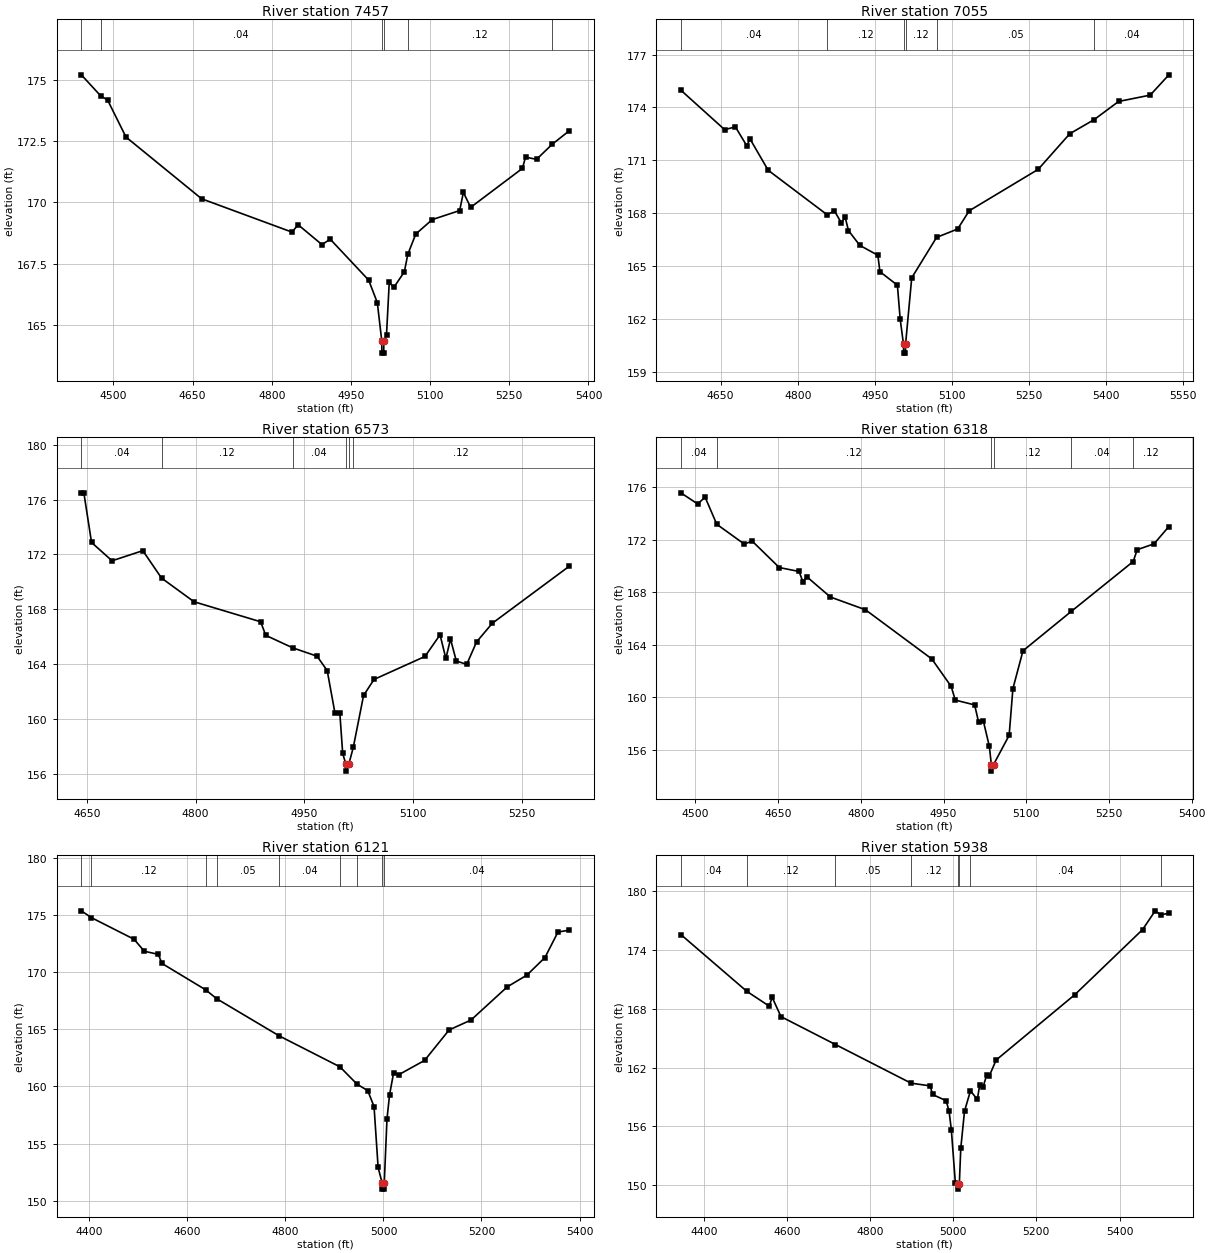
Type RM Length L Ch R = 1,7457,402,402,402
BEGIN DESCRIPTION:
Mapping XS 63f0306c
END DESCRIPTION:
XS GIS Cut Line= 3
      2549649.13     13569003.06      2549235.62     13569218.80
      2548795.15     13569344.65
#Sta/Elev= 30
  4439.3  175.21  4476.1  174.35  4489.1  174.18  4523.9  172.67  4667.2  170.15
  4838.3  168.79  4850.0  169.09  4895.1  168.28  4910.8  168.50  4983.6  166.83
  5000.0  165.91  5008.4  164.35  5008.6  163.85  5012.1  163.85  5012.4  164.35
  5017.4  164.60  5022.6  166.74  5031.2  166.53  5051.2  167.17  5057.7  167.88
  5072.8  168.71  5104.0  169.30  5156.0  169.67  5163.0  170.41  5176.8  169.80
  5274.8  171.39  5280.8  171.85  5301.6  171.76  5331.0  172.37  5363.8  172.93
#Mann=6,-1,0
  4439.3    0.12       0  4476.1    0.04       0  5008.4    0.04       0
  5012.4    0.04       0  5057.7    0.12       0  5331.0    0.04       0
Bank Sta=5008.4,5012.4
Exp/Cntr=0.3,0.1

Type RM Length L Ch R = 1,7055,482,482,482
BEGIN DESCRIPTION:
TRIB 13_2 TO GUADALUPE RIVER 6.0
END DESCRIPTION:
XS GIS Cut Line= 3
      2549324.99     13568625.00      2549025.00     13568875.00
      2548525.02     13569124.99
#Sta/Elev= 30
  4572.6  174.98  4657.9  172.74  4678.7  172.90  4700.8  171.83  4707.3  172.21
  4742.5  170.44  4857.5  167.91  4871.3  168.14  4885.0  167.45  4892.2  167.79
  4898.7  167.02  4920.8  166.18  4955.9  165.62  4959.9  164.69  4993.9  163.92
  4999.4  161.98  5005.8  160.57  5006.1  160.07  5009.6  160.07  5009.8  160.57
  5021.8  164.34  5070.1  166.63  5111.2  167.11  5133.6  168.14  5267.8  170.49
  5329.3  172.51  5376.7  173.31  5424.3  174.34  5485.8  174.70  5522.1  175.85
#Mann=6,-1,0
  4572.6    0.04       0  4857.5    0.12       0  5005.8    0.05       0
  5009.8    0.12       0  5070.1    0.05       0  5376.7    0.04       0
Bank Sta=5005.8,5009.8
Exp/Cntr=0.3,0.1

Type RM Length L Ch R = 1,6573,255,255,255
BEGIN DESCRIPTION:
TRIB 13_2 TO GUADALUPE RIVER 5.0
END DESCRIPTION:
XS GIS Cut Line= 3
      2549075.00     13568225.00      2548825.00     13568475.00
      2548625.01     13568724.99
#Sta/Elev= 30
  4642.3  176.49  4645.8  176.49  4656.4  172.87  4684.7  171.53  4727.2  172.27
  4753.0  170.27  4797.9  168.54  4889.8  167.08  4896.9  166.09  4934.0  165.18
  4967.6  164.57  4981.7  163.52  4992.3  160.45  4999.1  160.45  5003.1  157.47
  5007.5  156.68  5007.7  156.18  5011.5  156.68  5017.7  157.91  5031.9  161.70
  5046.3  162.87  5116.7  164.55  5137.5  166.13  5145.5  164.40  5151.9  165.82
  5159.9  164.22  5174.3  163.97  5187.9  165.61  5209.6  166.97  5316.0  171.14
#Mann=6,-1,0
  4642.3    0.04       0  4753.0    0.12       0  4934.0    0.04       0
  5007.5    0.04       0  5011.5    0.04       0  5017.7    0.12       0
Bank Sta=5007.5,5011.5
Exp/Cntr=0.3,0.1

Type RM Length L Ch R = 1,6318,197,197,197
BEGIN DESCRIPTION:
Mapping XS f5d0e33d
END DESCRIPTION:
XS GIS Cut Line= 3
      2548944.96     13568002.26      2548594.39     13568391.79
      2548468.60     13568730.21
#Sta/Elev= 30
  4473.6  175.59  4504.2  174.74  4517.6  175.26  4538.8  173.19  4588.7  171.68
  4602.9  171.91  4652.2  169.89  4688.1  169.59  4694.8  168.82  4702.3  169.18
  4744.9  167.64  4808.4  166.67  4928.7  162.92  4963.9  160.82  4971.3  159.78
  5006.4  159.41  5013.7  158.08  5022.4  158.15  5033.1  156.25  5036.7  154.86
  5036.9  154.36  5040.7  154.86  5069.0  157.09  5075.8  160.65  5094.1  163.54
  5181.8  166.55  5294.0  170.35  5301.2  171.25  5331.8  171.70  5358.7  173.02
#Mann=6,-1,0
  4473.6    0.04       0  4538.8    0.12       0  5036.7    0.05       0
  5040.7    0.12       0  5181.8    0.04       0  5294.0    0.12       0
Bank Sta=5036.7,5040.7
Exp/Cntr=0.3,0.1

Type RM Length L Ch R = 1,6121,183,183,183
BEGIN DESCRIPTION:
Mapping XS cb88367c
END DESCRIPTION:
XS GIS Cut Line= 3
      2548792.15     13567840.45      2548456.55     13568223.99
      2548303.74     13568685.41
#Sta/Elev= 30
  4383.6  175.38  4404.3  174.78  4491.2  172.89  4512.1  171.84  4540.6  171.57
  4548.2  170.77  4637.0  168.47  4659.9  167.68  4787.7  164.42  4911.2  161.72
  4945.9  160.21  4968.0  159.63  4980.8  158.24  4989.1  152.91  4997.6  151.51
  4997.9  151.01  5001.4  151.01  5001.6  151.51  5007.2  157.16  5012.5  159.28
  5020.7  161.20  5031.2  161.03  5083.9  162.28  5134.0  164.95  5178.7  165.82
  5252.5  168.72  5292.6  169.75  5329.5  171.29  5356.0  173.52  5379.3  173.69
#Mann=9,-1,0
  4383.6    0.04       0  4404.3    0.12       0  4637.0    0.04       0
  4659.9    0.05       0  4787.7    0.04       0  4911.2    0.12       0
  4945.9    0.04       0  4997.6    0.04       0  5001.6    0.04       0
Bank Sta=4997.6,5001.6
Exp/Cntr=0.3,0.1

Type RM Length L Ch R = 1,5938,249,249,249
BEGIN DESCRIPTION:
Mapping XS 2fcba6ab
END DESCRIPTION:
XS GIS Cut Line= 4
      2548699.28     13567738.55      2548339.69     13568098.14
      2548204.85     13568379.80      2548141.93     13568727.35
#Sta/Elev= 30
  4344.8  175.59  4503.3  169.80  4557.4  168.28  4564.5  169.18  4585.7  167.21
  4716.8  164.36  4898.4  160.42  4944.7  160.14  4950.2  159.26  4982.9  158.63
  4990.0  157.57  4995.5  155.66  5005.1  150.27  5010.7  150.10  5010.9  149.60
  5014.7  150.10  5018.2  153.78  5027.2  157.56  5041.5  159.64  5058.0  158.75
  5063.5  160.18  5071.6  160.00  5080.7  161.27  5086.2  161.10  5103.3  162.78
  5292.8  169.46  5455.4  176.09  5485.9  178.01  5499.3  177.61  5518.8  177.76
#Mann=8,-1,0
  4344.8    0.04       0  4503.3    0.12       0  4716.8    0.05       0
  4898.4    0.12       0  5010.7    0.05       0  5014.7    0.12       0
  5041.5    0.04       0  5499.3    0.12       0
Bank Sta=5010.7,5014.7
Exp/Cntr=0.3,0.1

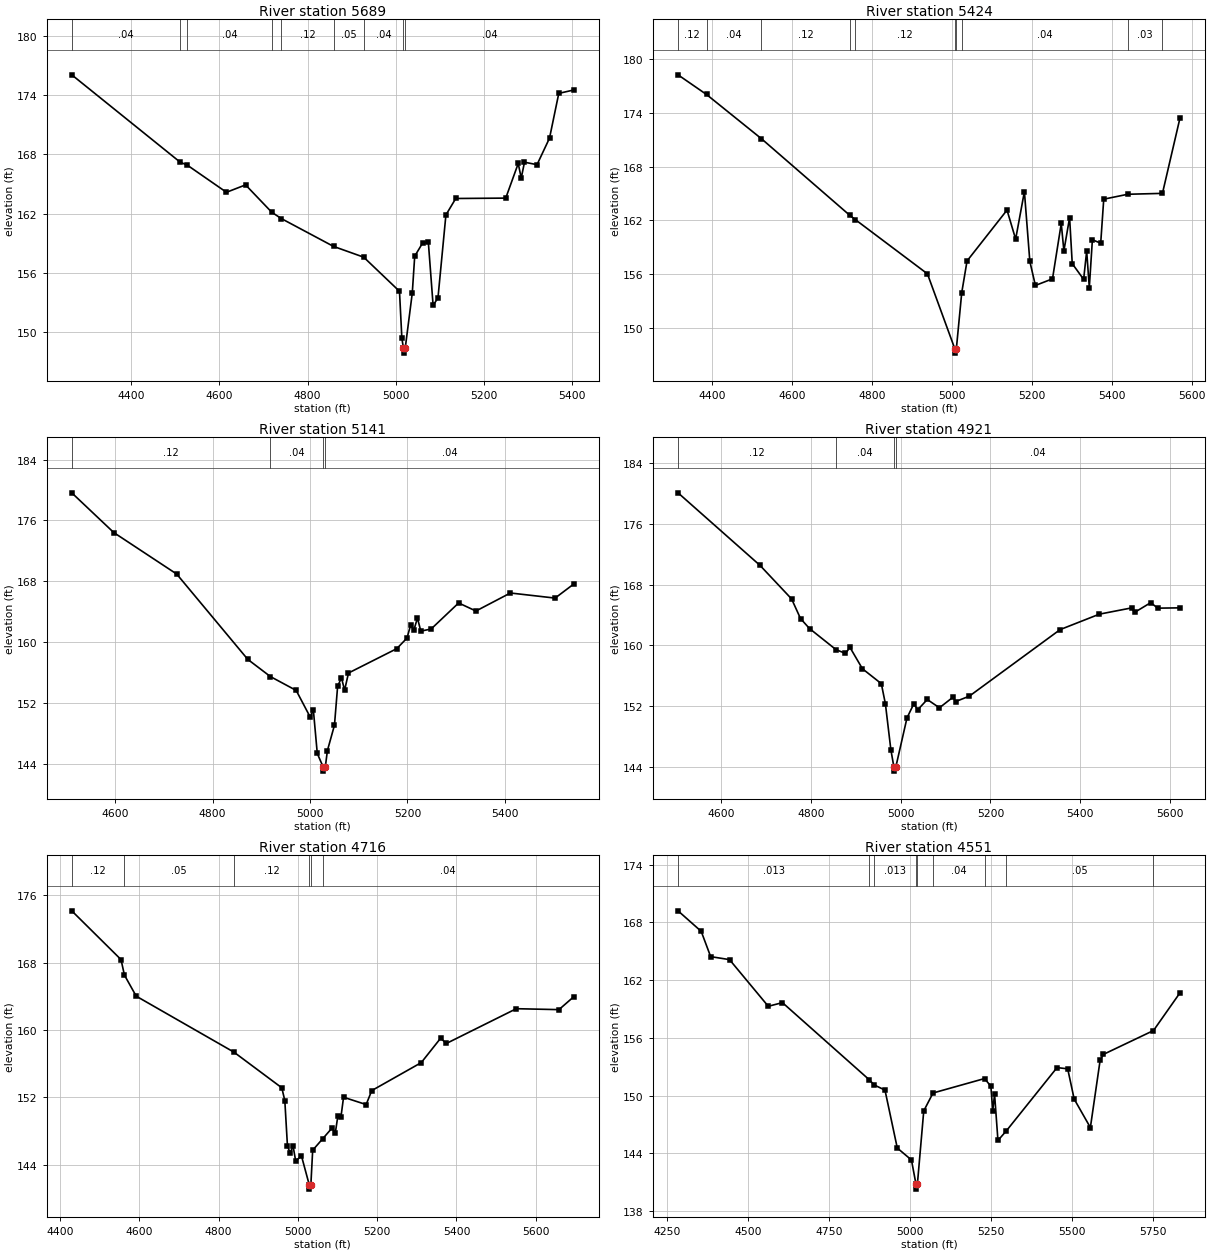
Type RM Length L Ch R = 1,5689,265,265,265
BEGIN DESCRIPTION:
Mapping XS 4db95357
END DESCRIPTION:
XS GIS Cut Line= 4
      2548657.35     13567618.69      2548195.86     13567879.40
      2548061.02     13568194.02      2547866.26     13568373.81
#Sta/Elev= 30
  4265.4  176.07  4510.9  167.22  4527.6  166.90  4616.0  164.16  4659.3  164.91
  4718.5  162.14  4740.5  161.49  4858.7  158.67  4927.0  157.58  5008.1  154.12
  5013.5  149.35  5017.1  148.35  5017.4  147.85  5021.1  148.35  5037.1  153.95
  5042.6  157.68  5060.7  159.03  5073.5  159.09  5084.3  152.69  5095.3  153.45
  5113.3  161.86  5135.6  163.53  5248.9  163.57  5277.2  167.08  5284.0  165.60
  5291.4  167.21  5319.8  166.96  5348.1  169.65  5369.1  174.19  5402.8  174.53
#Mann=9,-1,0
  4265.4    0.04       0  4510.9    0.12       0  4527.6    0.04       0
  4718.5    0.05       0  4740.5    0.12       0  4858.7    0.05       0
  4927.0    0.04       0  5017.1    0.04       0  5021.1    0.04       0
Bank Sta=5017.1,5021.1
Exp/Cntr=0.3,0.1

Type RM Length L Ch R = 1,5424,283,283,283
BEGIN DESCRIPTION:
Mapping XS 62733fb9
END DESCRIPTION:
XS GIS Cut Line= 4
      2548624.35     13567516.83      2548153.91     13567807.48
      2547887.23     13567858.42      2547560.67     13568140.04
#Sta/Elev= 30
  4315.0  178.28  4386.3  176.08  4523.8  171.13  4745.1  162.55  4759.0  162.07
  4939.0  156.02  5007.4  147.65  5007.7  147.15  5011.4  147.65  5024.8  153.91
  5038.1  157.46  5138.1  163.15  5159.7  159.90  5181.6  165.22  5195.2  157.41
  5209.1  154.72  5251.9  155.46  5273.8  161.65  5280.4  158.59  5294.7  162.31
  5301.3  157.16  5329.8  155.40  5337.4  158.57  5344.0  154.49  5351.7  159.83
  5372.5  159.45  5380.1  164.37  5440.3  164.92  5527.0  165.02  5570.7  173.42
#Mann=10,-1,0
  4315.0    0.12       0  4386.3    0.04       0  4523.8    0.12       0
  4745.1    0.04       0  4759.0    0.12       0  5007.4    0.05       0
  5011.4    0.12       0  5024.8    0.04       0  5440.3    0.03       0
  5527.0    0.04       0
Bank Sta=5007.4,5011.4
Exp/Cntr=0.3,0.1

Type RM Length L Ch R = 1,5141,220,220,220
BEGIN DESCRIPTION:
Mapping XS c92c43d6
END DESCRIPTION:
XS GIS Cut Line= 4
      2548438.54     13567438.93      2548126.94     13567480.87
      2547887.23     13567669.65      2547602.54     13567966.32
#Sta/Elev= 30
  4510.7  179.62  4596.9  174.40  4726.2  168.94  4872.2  157.72  4918.7  155.46
  4971.6  153.64  5000.5  150.12  5006.8  151.11  5014.9  145.35  5027.3  143.53
  5027.6  143.03  5031.3  143.53  5035.7  145.73  5050.2  149.07  5056.7  154.20
  5064.6  155.29  5071.0  153.67  5079.0  155.93  5178.1  159.13  5199.2  160.53
  5206.4  162.19  5213.4  161.60  5220.6  163.16  5227.5  161.44  5248.6  161.71
  5305.2  165.14  5340.7  164.08  5411.5  166.45  5503.3  165.78  5541.4  167.62
#Mann=4,-1,0
  4510.7    0.12       0  4918.7    0.04       0  5027.3    0.04       0
  5031.3    0.04       0
Bank Sta=5027.3,5031.3
Exp/Cntr=0.3,0.1

Type RM Length L Ch R = 1,4921,205,205,205
BEGIN DESCRIPTION:
Mapping XS c27f28c8
END DESCRIPTION:
XS GIS Cut Line= 4
      2548417.56     13567319.07      2548010.08     13567337.04
      2547815.32     13567465.89      2547554.64     13567864.40
#Sta/Elev= 30
  4504.4  180.05  4687.1  170.51  4757.3  166.11  4777.2  163.53  4797.2  162.22
  4856.4  159.44  4877.3  158.96  4887.3  159.74  4915.0  156.94  4957.1  154.98
  4966.2  152.32  4978.3  146.32  4985.2  143.99  4985.5  143.49  4989.2  143.99
  5014.3  150.49  5029.3  152.31  5038.3  151.56  5059.4  152.90  5086.5  151.81
  5116.6  153.20  5122.6  152.63  5153.1  153.34  5355.2  162.08  5442.6  164.11
  5515.0  164.94  5521.0  164.34  5557.2  165.63  5572.3  164.90  5622.0  164.94
#Mann=4,-1,0
  4504.4    0.12       0  4856.4    0.04       0  4985.2    0.04       0
  4989.2    0.04       0
Bank Sta=4985.2,4989.2
Exp/Cntr=0.3,0.1

Type RM Length L Ch R = 1,4716,165,165,165
BEGIN DESCRIPTION:
Mapping XS 5d20d9ab
END DESCRIPTION:
XS GIS Cut Line= 4
      2548336.68     13566995.46      2547887.23     13567169.24
      2547620.55     13567399.97      2547485.77     13567810.29
#Sta/Elev= 30
  4429.3  174.15  4553.6  168.36  4562.2  166.52  4591.9  164.02  4838.6  157.37
  4959.3  153.14  4966.9  151.62  4973.5  146.26  4980.2  145.39  4987.8  146.21
  4994.4  144.42  5008.7  145.09  5028.6  141.61  5028.8  141.11  5032.6  141.61
  5037.2  145.73  5062.3  147.08  5086.5  148.39  5094.2  147.75  5100.8  149.82
  5108.4  149.63  5115.1  152.02  5172.1  151.15  5186.3  152.81  5311.2  156.13
  5360.1  159.03  5374.4  158.40  5551.0  162.53  5658.6  162.42  5695.7  163.94
#Mann=6,-1,0
  4429.3    0.12       0  4562.2    0.05       0  4838.6    0.12       0
  5028.6    0.05       0  5032.6    0.12       0  5062.3    0.04       0
Bank Sta=5028.6,5032.6
Exp/Cntr=0.3,0.1

Type RM Length L Ch R = 1,4551,611,611,611
BEGIN DESCRIPTION:
Mapping XS fe63bf26
END DESCRIPTION:
XS GIS Cut Line= 4
      2548303.52     13566856.27      2547632.29     13567220.93
      2547270.99     13567417.22      2547266.84     13567791.33
#Sta/Elev= 30
  4284.0  169.20  4355.5  167.07  4384.7  164.44  4442.9  164.13  4562.6  159.28
  4606.3  159.66  4874.8  151.63  4889.2  151.11  4922.8  150.57  4960.8  144.55
  5004.5  143.31  5018.6  140.78  5018.9  140.28  5022.8  140.78  5042.5  148.41
  5071.1  150.27  5230.1  151.77  5249.7  150.97  5255.4  148.42  5261.1  150.14
  5271.5  145.34  5297.1  146.32  5453.9  152.91  5486.8  152.78  5506.8  149.64
  5556.8  146.68  5586.9  153.67  5596.9  154.28  5751.6  156.76  5833.2  160.67
#Mann=9,-1,0
  4284.0   0.013       0  4874.8    0.12       0  4889.2   0.013       0
  5018.6    0.03       0  5022.8   0.013       0  5071.1    0.04       0
  5230.1   0.013       0  5297.1    0.05       0  5751.6    0.04       0
Bank Sta=5018.6,5022.8
Exp/Cntr=0.3,0.1

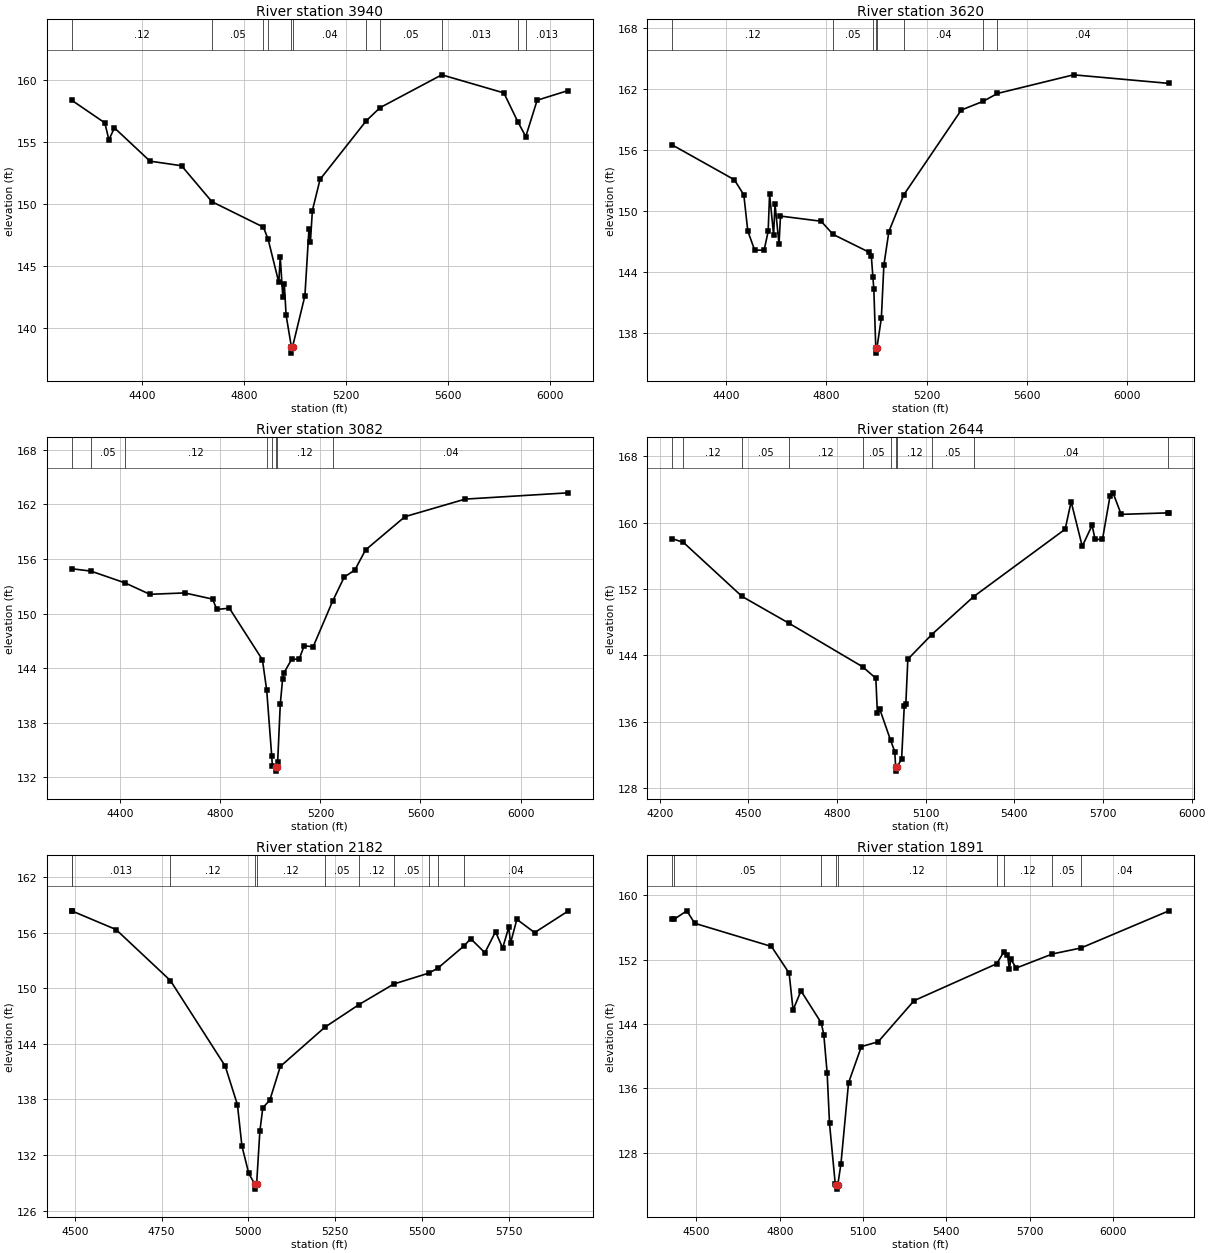
Type RM Length L Ch R = 1,3940,320,320,320
BEGIN DESCRIPTION:
Mapping XS 4594413d
END DESCRIPTION:
XS GIS Cut Line= 3
      2548336.54     13566456.73      2547568.28     13566895.11
      2546636.60     13567410.78
#Sta/Elev= 30
  4123.7  158.37  4254.6  156.53  4270.5  155.16  4292.1  156.13  4431.8  153.44
  4555.6  153.07  4674.6  150.17  4877.0  148.11  4895.6  147.12  4937.3  143.65
  4943.0  145.71  4953.1  142.46  4958.9  143.53  4966.0  141.00  4986.8  138.44
  4987.1  137.94  4991.2  138.44  5039.8  142.57  5055.8  147.99  5061.5  146.95
  5069.1  149.45  5099.3  151.97  5280.6  156.70  5334.8  157.76  5577.0  160.41
  5820.7  158.95  5876.2  156.59  5906.7  155.42  5951.3  158.36  6073.1  159.14
#Mann=11,-1,0
  4123.7    0.12       0  4674.6    0.05       0  4877.0    0.12       0
  4895.6    0.04       0  4986.8    0.04       0  4991.2    0.04       0
  5280.6   0.013       0  5334.8    0.05       0  5577.0   0.013       0
  5876.2    0.04       0  5906.7   0.013       0
Bank Sta=4986.8,4991.2
Exp/Cntr=0.3,0.1

Type RM Length L Ch R = 1,3620,538,538,538
BEGIN DESCRIPTION:
Mapping XS a97d6d41
END DESCRIPTION:
XS GIS Cut Line= 4
      2548410.26     13566300.51      2547867.76     13566604.32
      2547355.60     13566599.97      2546618.90     13567016.00
#Sta/Elev= 30
  4185.2  156.47  4433.7  153.04  4471.4  151.55  4487.3  147.99  4514.7  146.12
  4552.4  146.12  4568.4  147.96  4574.1  151.63  4590.1  147.63  4595.8  150.63
  4611.8  146.69  4617.5  149.47  4779.6  148.96  4827.2  147.67  4969.7  145.93
  4979.7  145.54  4986.1  143.45  4989.7  142.27  4997.5  136.50  4997.8  136.00
  5002.0  136.50  5019.7  139.45  5029.7  144.64  5049.7  147.95  5108.6  151.54
  5338.3  159.89  5424.8  160.74  5482.6  161.52  5785.9  163.35  6165.2  162.51
#Mann=8,-1,0
  4185.2    0.12       0  4827.2    0.05       0  4986.1    0.12       0
  4997.5    0.05       0  5002.0    0.12       0  5108.6    0.04       0
  5424.8    0.05       0  5482.6    0.04       0
Bank Sta=4997.5,5002
Exp/Cntr=0.3,0.1

Type RM Length L Ch R = 1,3082,438,438,438
BEGIN DESCRIPTION:
Mapping XS e5fe0b70
END DESCRIPTION:
XS GIS Cut Line= 4
      2548757.55     13565987.98      2548145.53     13566296.16
      2547624.70     13566105.18      2546988.36     13566494.78
#Sta/Elev= 30
  4204.5  154.92  4282.0  154.66  4418.8  153.36  4517.8  152.11  4657.2  152.26
  4768.8  151.58  4785.5  150.45  4835.8  150.58  4967.9  144.92  4985.1  141.57
  5005.1  134.35  5007.5  133.28  5021.4  133.18  5021.7  132.68  5025.9  133.18
  5028.9  133.68  5039.4  140.06  5048.8  142.84  5054.1  143.47  5084.6  144.96
  5115.1  145.00  5135.0  146.46  5170.8  146.34  5248.2  151.33  5295.0  154.00
  5337.6  154.78  5380.2  156.98  5537.9  160.64  5778.8  162.57  6190.6  163.26
#Mann=8,-1,0
  4204.5    0.12       0  4282.0    0.05       0  4418.8    0.12       0
  4985.1    0.05       0  5005.1    0.12       0  5021.4    0.05       0
  5025.9    0.12       0  5248.2    0.04       0
Bank Sta=5021.4,5025.9
Exp/Cntr=0.3,0.1

Type RM Length L Ch R = 1,2644,462,462,462
BEGIN DESCRIPTION:
Mapping XS 56504c66
END DESCRIPTION:
XS GIS Cut Line= 4
      2548926.78     13565883.83      2548401.61     13565940.25
      2547984.94     13565805.70      2547278.75     13565914.02
#Sta/Elev= 30
  4241.8  158.09  4280.2  157.63  4478.5  151.11  4638.9  147.84  4886.4  142.62
  4931.4  141.23  4936.7  136.98  4945.1  137.46  4981.1  133.76  4995.5  132.37
  4998.4  130.52  4998.8  130.02  5003.0  130.52  5018.6  131.47  5027.5  137.83
  5032.8  138.07  5039.7  143.53  5120.8  146.51  5262.5  151.09  5572.0  159.22
  5592.2  162.54  5629.8  157.15  5663.1  159.69  5673.2  157.99  5698.2  157.99
  5723.8  163.23  5733.9  163.61  5761.5  161.01  5918.8  161.19  5922.3  161.19
#Mann=11,-1,0
  4241.8   0.013       0  4280.2    0.12       0  4478.5    0.05       0
  4638.9    0.12       0  4886.4    0.05       0  4981.1    0.12       0
  4998.4    0.05       0  5003.0    0.12       0  5120.8    0.05       0
  5262.5    0.04       0  5918.8    0.05       0
Bank Sta=4998.4,5003
Exp/Cntr=0.3,0.1

Type RM Length L Ch R = 1,2182,291,291,291
BEGIN DESCRIPTION:
Mapping XS 5274309f
END DESCRIPTION:
XS GIS Cut Line= 4
      2548961.47     13565836.06      2548540.50     13565575.67
      2548171.58     13565527.93      2547620.39     13565645.11
#Sta/Elev= 30
  4490.6  158.35  4490.9  158.35  4618.9  156.33  4775.5  150.82  4933.3  141.59
  4968.5  137.42  4981.5  132.95  5001.2  130.00  5019.1  128.81  5019.4  128.31
  5023.7  128.81  5033.1  134.55  5041.6  137.10  5061.7  137.90  5092.0  141.55
  5219.8  145.77  5318.6  148.23  5418.8  150.45  5520.0  151.63  5546.0  152.17
  5621.1  154.56  5640.4  155.34  5681.2  153.83  5711.9  156.09  5732.4  154.33
  5750.0  156.59  5755.1  154.87  5773.3  157.43  5824.4  156.00  5921.1  158.33
#Mann=11,-1,0
  4490.6    0.05       0  4490.9   0.013       0  4775.5    0.12       0
  5019.1    0.05       0  5023.7    0.12       0  5219.8    0.05       0
  5318.6    0.12       0  5418.8    0.05       0  5520.0    0.12       0
  5546.0    0.05       0  5621.1    0.04       0
Bank Sta=5019.1,5023.7
Exp/Cntr=0.3,0.1

Type RM Length L Ch R = 1,1891,0,0,0
BEGIN DESCRIPTION:
Mapping XS 6e5c094b
END DESCRIPTION:
XS GIS Cut Line= 4
      2549094.30     13565731.02      2548778.70     13565368.21
      2548413.76     13565276.19      2547514.46     13565519.25
#Sta/Elev= 30
  4412.1  157.00  4418.7  157.00  4465.4  158.07  4493.9  156.52  4770.2  153.64
  4833.8  150.33  4848.1  145.74  4876.5  148.12  4949.4  144.15  4958.7  142.69
  4970.8  137.90  4979.3  131.64  4999.9  124.12  5004.4  123.97  5004.7  123.47
  5009.0  123.97  5020.5  126.63  5047.8  136.68  5094.0  141.19  5154.6  141.79
  5283.8  146.90  5581.5  151.49  5607.7  152.99  5620.2  152.62  5627.2  150.80
  5632.3  152.08  5651.3  150.95  5782.2  152.71  5884.9  153.45  6200.9  158.06
#Mann=9,-1,0
  4412.1    0.12       0  4418.7    0.05       0  4949.4    0.12       0
  5004.4    0.05       0  5009.0    0.12       0  5581.5    0.05       0
  5607.7    0.12       0  5782.2    0.05       0  5884.9    0.04       0
Bank Sta=5004.4,5009
Exp/Cntr=0.3,0.1

Chan Stop Cuts=-1