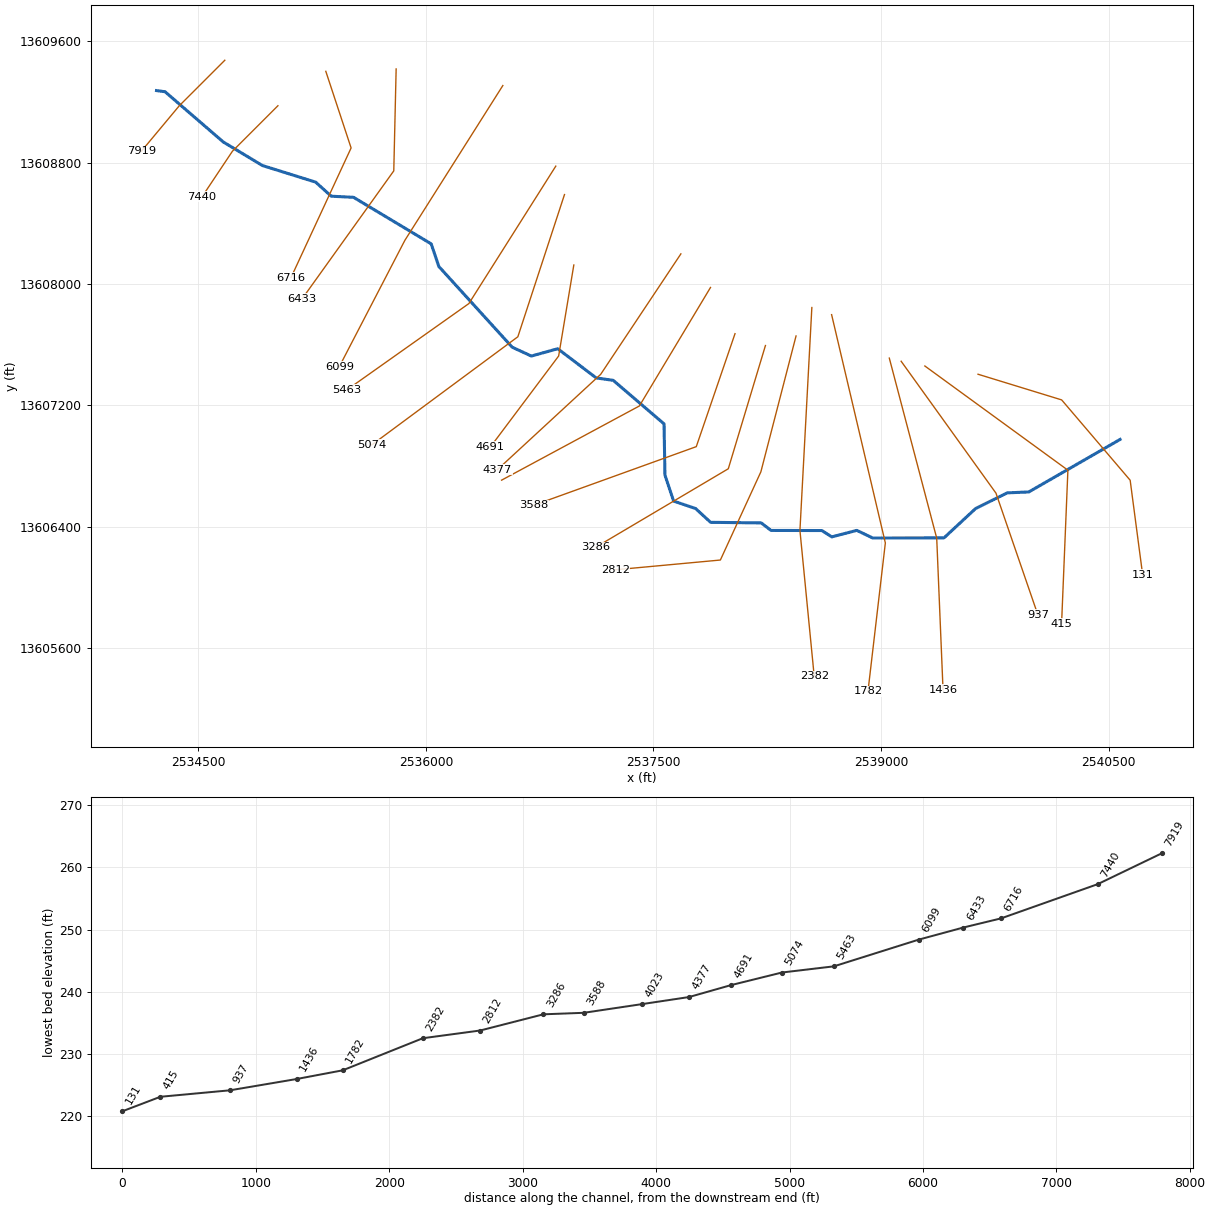
--- TRIB 13 TO IRISH CREEK.prj (project) ---

Proj Title=TRIB 13 TO IRISH CREEK Base Level Engineering
Current Plan=p01
Default Exp/Contr=0.3,0.1
English Units
Geom File=g01
Flow File=f01
Plan File=p01
Y Axis Title=Elevation
X Axis Title(PF)=Main Channel Distance
X Axis Title(XS)=Station
BEGIN DESCRIPTION:
TRIB 13 TO IRISH CREEK
END DESCRIPTION:
DSS Export Rating Curves= 0
DSS Export Rating Curve Sorted= 0
DSS Export Volume Flow Curves= 0
DXF OffsetX= 0
DXF OffsetY= 0
DXF ScaleX= 1
DXF ScaleY= 10

--- TRIB 13 TO IRISH CREEK.p01 (plan) ---

Plan Title=Multiple Run
Short Identifier=Multiple
Geom File=g01
Flow File=f01
Subcritical Flow
K Sum by GR= 0
Std Step Tol= 0.01
Critical Tol= 0.01
Num of Std Step Trials= 20
Max Error Tol= 0.3
Flow Tol Ratio= 0.001
Split Flow NTrial= 30
Split Flow Tol= 0.02
Split Flow Ratio= 0.02
Log Output Level= 0
Friction Slope Method= 1
Unsteady Friction Slope Method= 2
Unsteady Bridges Friction Slope Method= 1
Parabolic Critical Depth
Global Vel Dist=  1 , 1 , 1
Global Log Level= 0
CheckData=True
Encroach Param= -1, 0, 0, 0
BEGIN DESCRIPTION:
Multiple Run
END DESCRIPTION:

--- TRIB 13 TO IRISH CREEK.f01 (steady flow) ---

Flow Title=Multiple
Number of Profiles=7
Profile Names=10-year,25-year,50-year,1pct_min,100-year,1pct_plu,500-year
River Rch & RM= TRIB 13 TO IRISH,Reach-1,7919
     671    1094    1483     976    1948    3886    3321
River Rch & RM= TRIB 13 TO IRISH,Reach-1,6716
     874    1439    1962    1296    2587    5161    4450
River Rch & RM= TRIB 13 TO IRISH,Reach-1,2382
    1174    1967    2712    1811    3613    7208    6346
River Rch & RM= TRIB 13 TO IRISH,Reach-1,1436
    1206    2018    2781    1855    3702    7386    6492
Boundary for River Rch & Prof#=TRIB 13 TO IRISH,Reach-1,1
Up Type=0
Dn Type=3
Dn Slope=0.005
Boundary for River Rch & Prof#=TRIB 13 TO IRISH,Reach-1,2
Up Type=0
Dn Type=3
Dn Slope=0.005
Boundary for River Rch & Prof#=TRIB 13 TO IRISH,Reach-1,3
Up Type=0
Dn Type=3
Dn Slope=0.005
Boundary for River Rch & Prof#=TRIB 13 TO IRISH,Reach-1,4
Up Type=0
Dn Type=3
Dn Slope=0.005
Boundary for River Rch & Prof#=TRIB 13 TO IRISH,Reach-1,5
Up Type=0
Dn Type=3
Dn Slope=0.005
Boundary for River Rch & Prof#=TRIB 13 TO IRISH,Reach-1,6
Up Type=0
Dn Type=3
Dn Slope=0.005
Boundary for River Rch & Prof#=TRIB 13 TO IRISH,Reach-1,7
Up Type=0
Dn Type=3
Dn Slope=0.005

--- TRIB 13 TO IRISH CREEK.g01 (geometry) ---

Geom Title=Existing Conditions

River Reach=TRIB 13 TO IRISH,Reach-1
Reach XY= 30
      2534225.00     13609275.00      2534281.21     13609267.24
      2534665.32     13608935.76      2534922.71     13608780.84
      2535273.50     13608671.38      2535376.47     13608578.56
      2535523.44     13608571.24      2536035.05     13608264.37
      2536085.52     13608115.22      2536568.94     13607583.14
      2536695.17     13607524.71      2536869.11     13607573.03
      2537122.58     13607380.54      2537234.79     13607364.48
      2537569.64     13607077.70      2537575.52     13606740.22
      2537632.73     13606568.50      2537777.42     13606519.46
      2537876.47     13606428.55      2538209.85     13606424.64
      2538275.00     13606375.00      2538609.84     13606374.34
      2538675.00     13606332.56      2538840.16     13606375.47
      2538945.03     13606325.07      2539414.57     13606326.05
      2539622.70     13606519.17      2539830.93     13606622.75
      2539973.44     13606628.76      2540575.00     13606975.00

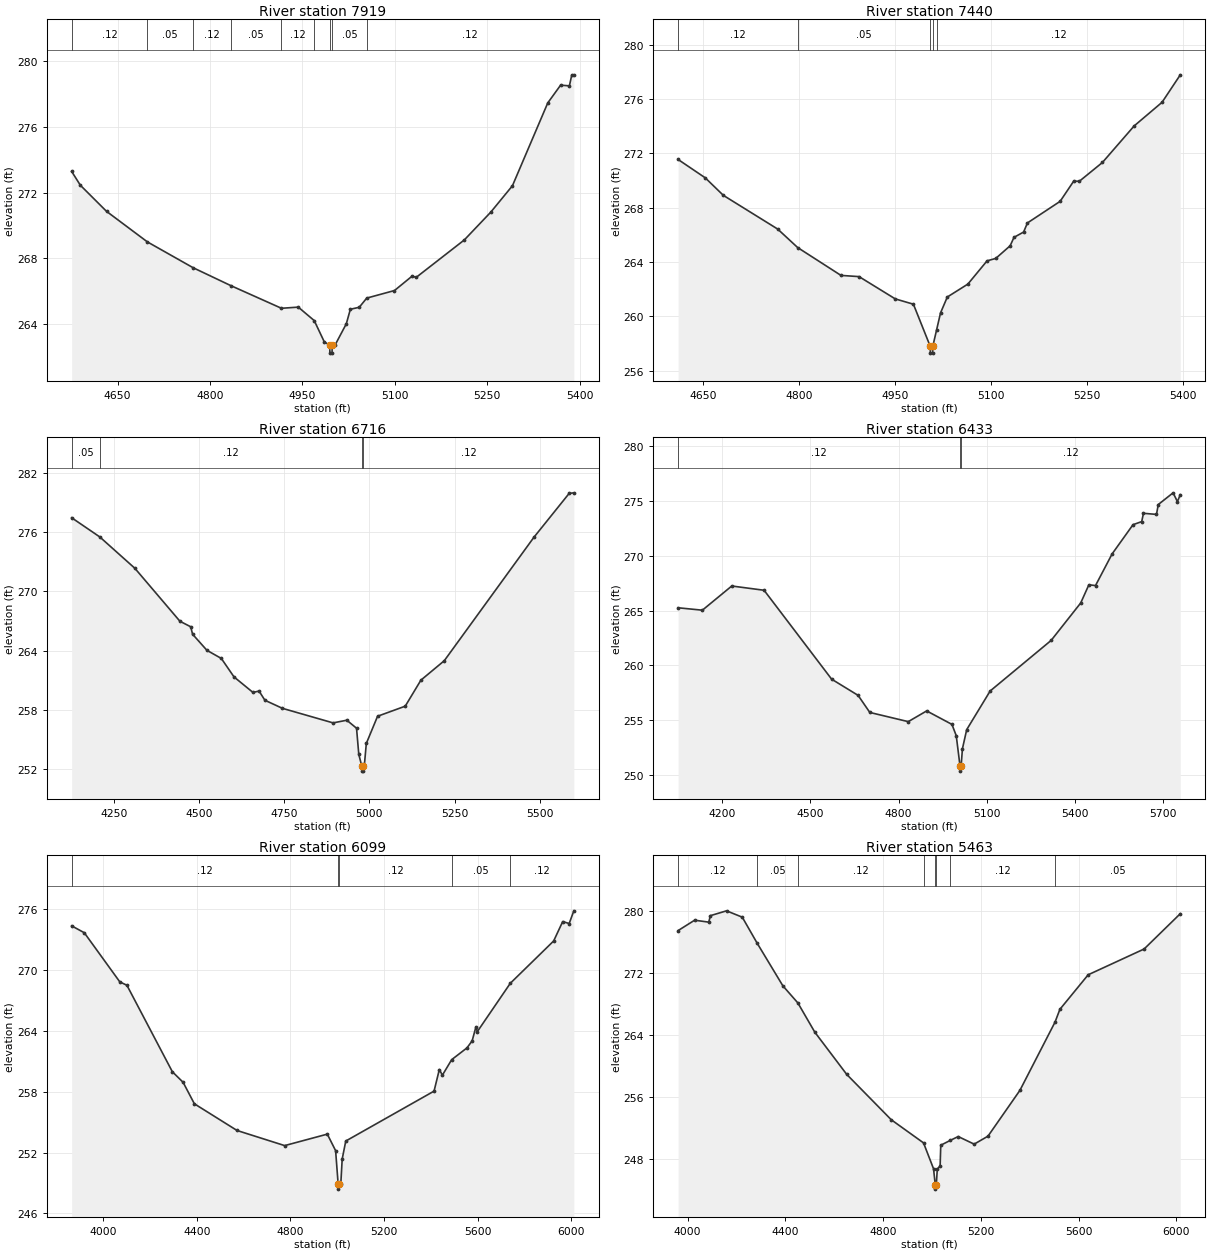
Type RM Length L Ch R = 1,7919,479,479,479
BEGIN DESCRIPTION:
TRIB 13 TO IRISH CREEK 17.0
END DESCRIPTION:
XS GIS Cut Line= 3
      2534675.00     13609475.00      2534375.00     13609175.00
      2534124.98     13608874.98
#Sta/Elev= 30
  4575.5  273.29  4589.6  272.45  4632.1  270.86  4698.4  269.00  4772.5  267.43
  4833.7  266.34  4915.9  264.96  4943.2  265.03  4969.1  264.21  4985.6  262.90
  4994.2  262.73  4994.5  262.23  4998.0  262.23  4998.2  262.73  5003.0  262.73
  5021.2  264.02  5027.7  264.90  5042.1  265.02  5054.3  265.58  5099.3  266.04
  5128.0  266.92  5134.5  266.84  5212.6  269.12  5255.5  270.81  5290.7  272.42
  5348.0  277.46  5368.8  278.54  5383.1  278.50  5387.0  279.17  5390.3  279.17
#Mann=9,-1,0
  4575.5    0.12       0  4698.4    0.05       0  4772.5    0.12       0
  4833.7    0.05       0  4915.9    0.12       0  4969.1    0.05       0
  4994.2    0.05       0  4998.2    0.05       0  5054.3    0.12       0
Bank Sta=4994.2,4998.2
Exp/Cntr=0.3,0.1

Type RM Length L Ch R = 1,7440,724,724,724
BEGIN DESCRIPTION:
TRIB 13 TO IRISH CREEK 16.0
END DESCRIPTION:
XS GIS Cut Line= 3
      2535024.99     13609174.99      2534725.00     13608875.00
      2534525.01     13608575.01
#Sta/Elev= 30
  4611.1  271.54  4653.5  270.19  4681.8  268.90  4766.7  266.42  4797.9  265.06
  4865.6  263.01  4893.9  262.92  4950.5  261.28  4978.8  260.89  5005.1  257.79
  5005.3  257.29  5008.8  257.29  5009.1  257.79  5015.1  259.01  5021.2  260.25
  5031.8  261.42  5063.9  262.37  5093.9  264.08  5107.5  264.26  5130.0  265.19
  5136.0  265.81  5151.0  266.20  5157.0  266.87  5208.1  268.46  5229.2  269.94
  5238.2  269.94  5274.2  271.32  5323.8  274.01  5367.4  275.75  5395.9  277.77
#Mann=5,-1,0
  4611.1    0.12       0  4797.9    0.05       0  5005.1    0.05       0
  5009.1    0.05       0  5015.1    0.12       0
Bank Sta=5005.1,5009.1
Exp/Cntr=0.3,0.1

Type RM Length L Ch R = 1,6716,283,283,283
BEGIN DESCRIPTION:
Mapping XS d0f4ffe0
END DESCRIPTION:
XS GIS Cut Line= 3
      2535340.58     13609401.95      2535507.26     13608896.70
      2535111.41     13608042.50
#Sta/Elev= 30
  4126.4  277.43  4208.9  275.49  4311.8  272.32  4444.1  266.96  4475.8  266.40
  4481.2  265.65  4523.3  264.02  4565.5  263.20  4602.8  261.33  4658.4  259.76
  4676.3  259.90  4693.4  258.97  4745.0  258.15  4893.5  256.68  4933.8  256.95
  4962.3  256.14  4968.9  253.50  4977.7  252.30  4977.9  251.80  4981.4  251.80
  4981.7  252.30  4985.2  252.38  4991.0  254.60  5024.0  257.35  5105.2  258.37
  5151.1  261.00  5219.8  262.97  5482.9  275.46  5586.1  279.89  5599.9  279.95
#Mann=4,-1,0
  4126.4    0.05       0  4208.9    0.12       0  4977.7    0.05       0
  4981.7    0.12       0
Bank Sta=4977.7,4981.7
Exp/Cntr=0.3,0.1

Type RM Length L Ch R = 1,6433,334,334,334
BEGIN DESCRIPTION:
Mapping XS 4f0c5dcb
END DESCRIPTION:
XS GIS Cut Line= 3
      2535804.13     13609417.57      2535788.51     13608745.65
      2535184.31     13607901.87
#Sta/Elev= 30
  4049.5  265.25  4132.1  265.03  4232.2  267.24  4342.2  266.85  4572.2  258.73
  4662.3  257.25  4702.2  255.69  4833.1  254.85  4895.8  255.83  4981.8  254.60
  4996.5  253.57  5009.2  250.83  5009.5  250.33  5013.2  250.83  5017.6  252.38
  5032.1  254.12  5112.0  257.65  5319.6  262.27  5420.3  265.69  5448.1  267.35
  5470.7  267.28  5527.2  270.17  5598.4  272.84  5627.9  273.12  5634.0  273.88
  5678.3  273.78  5684.4  274.68  5734.8  275.75  5749.5  274.95  5759.4  275.58
#Mann=3,-1,0
  4049.5    0.12       0  5009.2    0.05       0  5013.2    0.12       0
Bank Sta=5009.2,5013.2
Exp/Cntr=0.3,0.1

Type RM Length L Ch R = 1,6099,636,636,636
BEGIN DESCRIPTION:
Mapping XS aec0497b
END DESCRIPTION:
XS GIS Cut Line= 3
      2536507.25     13609308.15      2535861.42     13608287.32
      2535429.57     13607454.83
#Sta/Elev= 30
  3865.7  274.34  3919.7  273.66  4071.4  268.82  4101.9  268.48  4296.0  259.96
  4341.9  258.92  4390.1  256.80  4572.4  254.17  4775.9  252.68  4958.1  253.81
  4993.6  252.18  5004.4  248.89  5004.7  248.39  5008.4  248.89  5015.8  248.93
  5021.7  251.36  5037.0  253.13  5414.2  258.05  5436.8  260.18  5449.8  259.62
  5489.5  261.15  5554.8  262.31  5576.9  263.00  5593.4  264.40  5599.0  263.91
  5740.1  268.68  5925.3  272.85  5963.9  274.76  5991.6  274.57  6011.5  275.82
#Mann=5,-1,0
  3865.7    0.12       0  5004.4    0.05       0  5008.4    0.12       0
  5489.5    0.05       0  5740.1    0.12       0
Bank Sta=5004.4,5008.4
Exp/Cntr=0.3,0.1

Type RM Length L Ch R = 1,5463,389,389,389
BEGIN DESCRIPTION:
Mapping XS a8953bcd
END DESCRIPTION:
XS GIS Cut Line= 3
      2536856.21     13608776.90      2536283.30     13607870.65
      2535481.23     13607302.95
#Sta/Elev= 30
  3961.3  277.49  4028.8  278.83  4086.5  278.58  4093.7  279.42  4159.4  280.04
  4223.8  279.22  4285.1  275.84  4390.0  270.35  4451.4  268.14  4520.6  264.37
  4651.1  258.92  4833.4  253.06  4965.5  250.07  5006.4  246.73  5013.7  244.60
  5014.0  244.10  5017.7  244.60  5021.7  246.68  5033.4  247.10  5036.0  249.77
  5075.2  250.40  5107.4  250.89  5172.7  249.91  5229.2  250.94  5359.7  256.85
  5503.7  265.68  5523.4  267.32  5639.1  271.78  5868.0  275.11  6016.1  279.67
#Mann=8,-1,0
  3961.3    0.12       0  4285.1    0.05       0  4451.4    0.12       0
  4965.5    0.05       0  5013.7    0.05       0  5017.7    0.05       0
  5075.2    0.12       0  5503.7    0.05       0
Bank Sta=5013.7,5017.7
Exp/Cntr=0.3,0.1

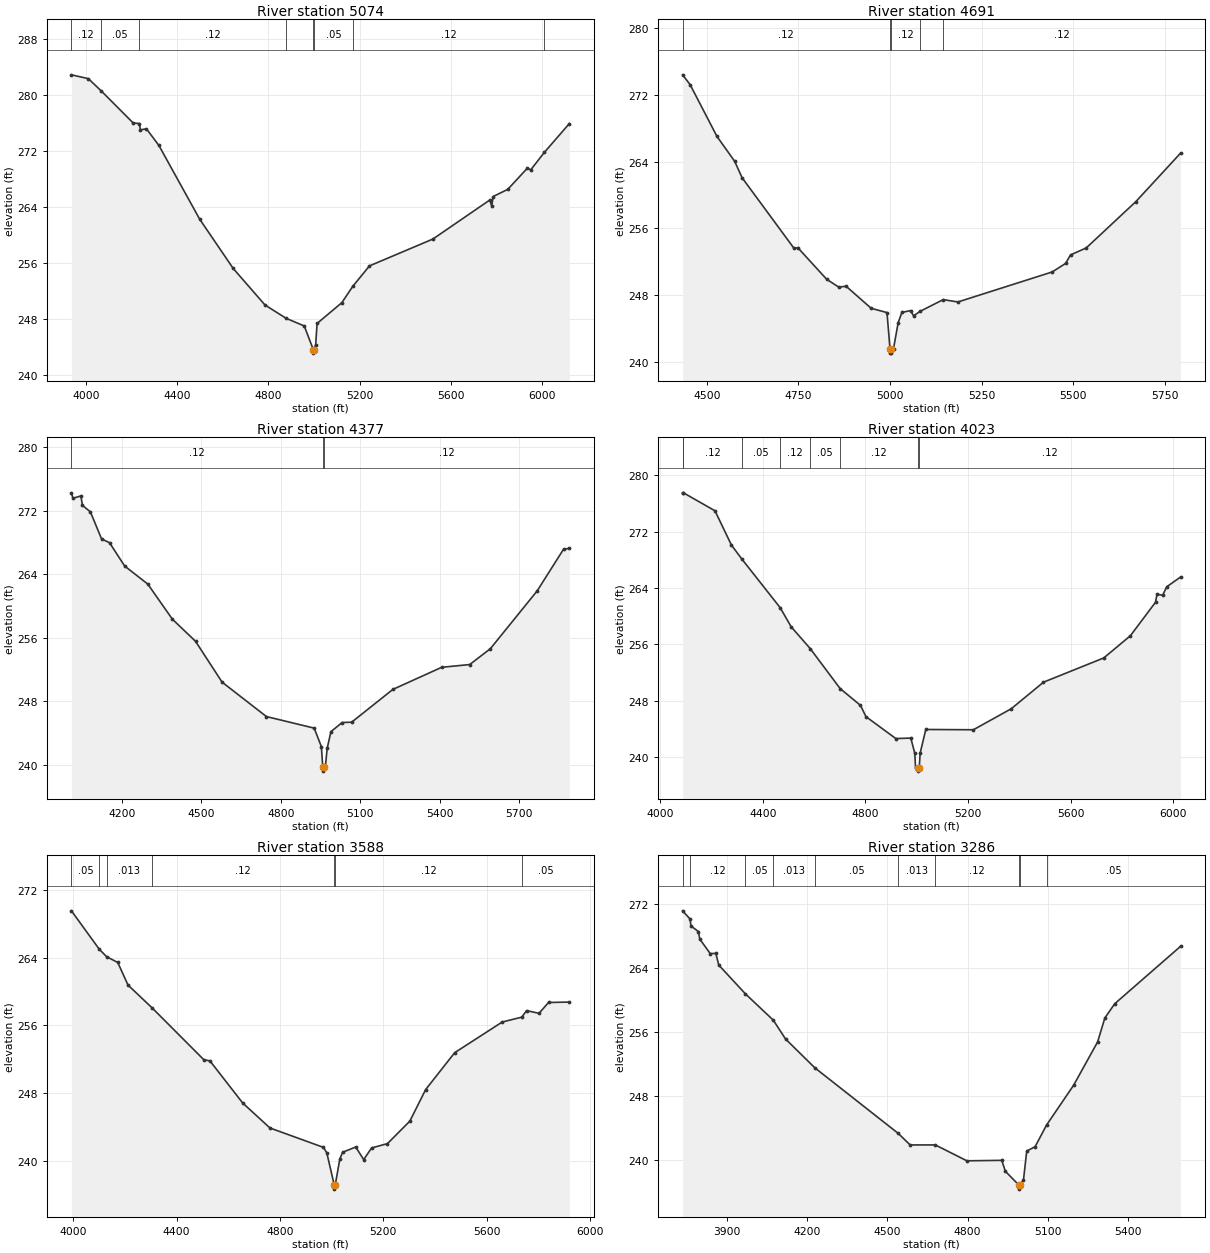
Type RM Length L Ch R = 1,5074,383,383,383
BEGIN DESCRIPTION:
Mapping XS 5e9ef6f4
END DESCRIPTION:
XS GIS Cut Line= 3
      2536913.52     13608589.44      2536606.22     13607651.90
      2535643.80     13606939.19
#Sta/Elev= 30
  3935.7  282.86  4010.0  282.31  4065.5  280.59  4206.3  275.99  4233.7  275.90
  4238.1  275.00  4264.7  275.15  4319.2  272.78  4498.1  262.25  4645.4  255.20
  4784.6  249.99  4877.5  248.08  4957.0  246.99  4996.7  243.61  4997.0  243.11
  5000.7  243.61  5007.1  244.32  5013.3  247.35  5121.9  250.32  5169.4  252.63
  5243.0  255.57  5521.1  259.40  5770.9  264.98  5779.3  264.11  5785.6  265.48
  5849.7  266.50  5935.8  269.53  5950.5  269.29  6009.9  271.77  6119.9  275.90
#Mann=8,-1,0
  3935.7    0.12       0  4065.5    0.05       0  4233.7    0.12       0
  4877.5    0.05       0  4996.7    0.05       0  5000.7    0.05       0
  5169.4    0.12       0  6009.9    0.05       0
Bank Sta=4996.7,5000.7
Exp/Cntr=0.3,0.1

Type RM Length L Ch R = 1,4691,314,314,314
BEGIN DESCRIPTION:
TRIB 13 TO IRISH CREEK 10.0
END DESCRIPTION:
XS GIS Cut Line= 3
      2536975.01     13608125.04      2536875.00     13607525.00
      2536425.01     13606925.02
#Sta/Elev= 30
  4433.9  274.37  4454.2  273.21  4527.7  267.00  4575.9  264.03  4596.2  262.06
  4738.1  253.60  4748.2  253.69  4826.8  249.92  4859.7  248.98  4880.0  249.08
  4948.4  246.44  4991.5  245.93  4999.7  241.58  4999.9  241.08  5003.4  241.08
  5003.7  241.58  5009.3  241.62  5021.9  244.71  5032.1  245.95  5055.8  246.17
  5064.1  245.54  5081.8  246.08  5144.8  247.48  5184.9  247.20  5442.2  250.79
  5478.7  251.81  5492.2  252.83  5534.9  253.66  5670.3  259.20  5792.2  265.00
#Mann=5,-1,0
  4433.9    0.12       0  4999.7    0.05       0  5003.7    0.12       0
  5081.8    0.05       0  5144.8    0.12       0
Bank Sta=4999.7,5003.7
Exp/Cntr=0.3,0.1

Type RM Length L Ch R = 1,4377,354,354,354
BEGIN DESCRIPTION:
Mapping XS fcef66b7
END DESCRIPTION:
XS GIS Cut Line= 3
      2537680.57     13608198.32      2537151.91     13607404.04
      2536472.20     13606776.41
#Sta/Elev= 30
  4009.4  274.26  4014.9  273.57  4045.0  273.87  4051.0  272.68  4081.0  271.86
  4123.1  268.45  4153.2  267.97  4210.3  265.03  4297.4  262.76  4390.6  258.32
  4477.8  255.54  4578.0  250.39  4745.3  246.05  4925.6  244.59  4952.7  242.26
  4958.0  239.67  4958.2  239.17  4962.0  239.67  4967.8  239.70  4974.6  242.03
  4988.8  244.15  5031.3  245.30  5067.0  245.34  5222.4  249.47  5406.7  252.26
  5512.7  252.61  5590.4  254.60  5767.3  261.90  5866.6  267.14  5888.7  267.26
#Mann=3,-1,0
  4009.4    0.12       0  4958.0    0.05       0  4962.0    0.12       0
Bank Sta=4958,4962
Exp/Cntr=0.3,0.1

Type RM Length L Ch R = 1,4023,435,435,435
BEGIN DESCRIPTION:
Mapping XS d1d4d50b
END DESCRIPTION:
XS GIS Cut Line= 3
      2537875.88     13607976.98      2537407.12     13607195.70
      2536499.10     13606706.57
#Sta/Elev= 30
  4086.7  277.52  4090.1  277.52  4213.1  274.97  4277.2  270.11  4316.7  268.18
  4467.4  261.22  4510.5  258.50  4584.3  255.43  4701.2  249.75  4780.7  247.36
  4802.0  245.76  4918.7  242.65  4977.0  242.72  4992.5  240.57  4995.3  238.64
  5005.9  238.53  5006.1  238.03  5009.9  238.53  5013.5  240.60  5035.5  243.94
  5221.2  243.90  5368.8  246.88  5494.6  250.65  5729.8  254.09  5833.6  257.24
  5931.6  261.99  5937.5  263.14  5959.4  262.98  5975.6  264.19  6029.2  265.57
#Mann=8,-1,0
  4086.7   0.013       0  4090.1    0.12       0  4316.7    0.05       0
  4467.4    0.12       0  4584.3    0.05       0  4701.2    0.12       0
  5005.9    0.05       0  5009.9    0.12       0
Bank Sta=5005.9,5009.9
Exp/Cntr=0.3,0.1

Type RM Length L Ch R = 1,3588,302,302,302
BEGIN DESCRIPTION:
Mapping XS e520f43a
END DESCRIPTION:
XS GIS Cut Line= 3
      2538037.32     13607672.24      2537782.12     13606927.48
      2536709.09     13606540.35
#Sta/Elev= 30
  3992.5  269.55  4100.2  265.01  4128.6  264.13  4171.9  263.44  4211.6  260.77
  4304.3  258.09  4505.5  251.93  4528.7  251.81  4655.5  246.83  4761.2  243.87
  4968.1  241.58  4981.3  240.93  5010.0  237.14  5010.2  236.64  5014.0  237.14
  5031.9  240.23  5042.7  241.00  5093.4  241.62  5124.1  240.13  5154.8  241.51
  5216.1  242.02  5302.8  244.68  5364.2  248.42  5476.3  252.77  5660.4  256.40
  5736.5  256.98  5754.8  257.75  5803.1  257.43  5839.8  258.71  5920.5  258.76
#Mann=7,-1,0
  3992.5    0.05       0  4100.2    0.12       0  4128.6   0.013       0
  4304.3    0.12       0  5010.0    0.05       0  5014.0    0.12       0
  5736.5    0.05       0
Bank Sta=5010,5014
Exp/Cntr=0.3,0.1

Type RM Length L Ch R = 1,3286,474,474,474
BEGIN DESCRIPTION:
Mapping XS 5d6dd987
END DESCRIPTION:
XS GIS Cut Line= 3
      2538237.85     13607594.14      2537993.06     13606781.64
      2537119.02     13606263.98
#Sta/Elev= 30
  3732.8  271.10  3760.7  270.08  3764.2  269.21  3792.0  268.52  3797.2  267.57
  3836.3  265.77  3857.2  265.79  3868.4  264.33  3968.3  260.74  4072.6  257.46
  4118.3  255.12  4227.8  251.53  4540.6  243.34  4584.8  241.91  4679.1  241.91
  4797.3  239.93  4927.8  239.99  4941.5  238.62  4992.2  236.90  4992.4  236.40
  4996.2  236.90  5009.1  237.53  5021.4  241.15  5052.7  241.69  5095.6  244.39
  5196.9  249.35  5286.7  254.75  5313.9  257.74  5351.0  259.52  5597.2  266.67
#Mann=10,-1,0
  3732.8    0.05       0  3760.7    0.12       0  3968.3    0.05       0
  4072.6   0.013       0  4227.8    0.05       0  4540.6   0.013       0
  4679.1    0.12       0  4992.2    0.05       0  4996.2    0.12       0
  5095.6    0.05       0
Bank Sta=4992.2,4996.2
Exp/Cntr=0.3,0.1

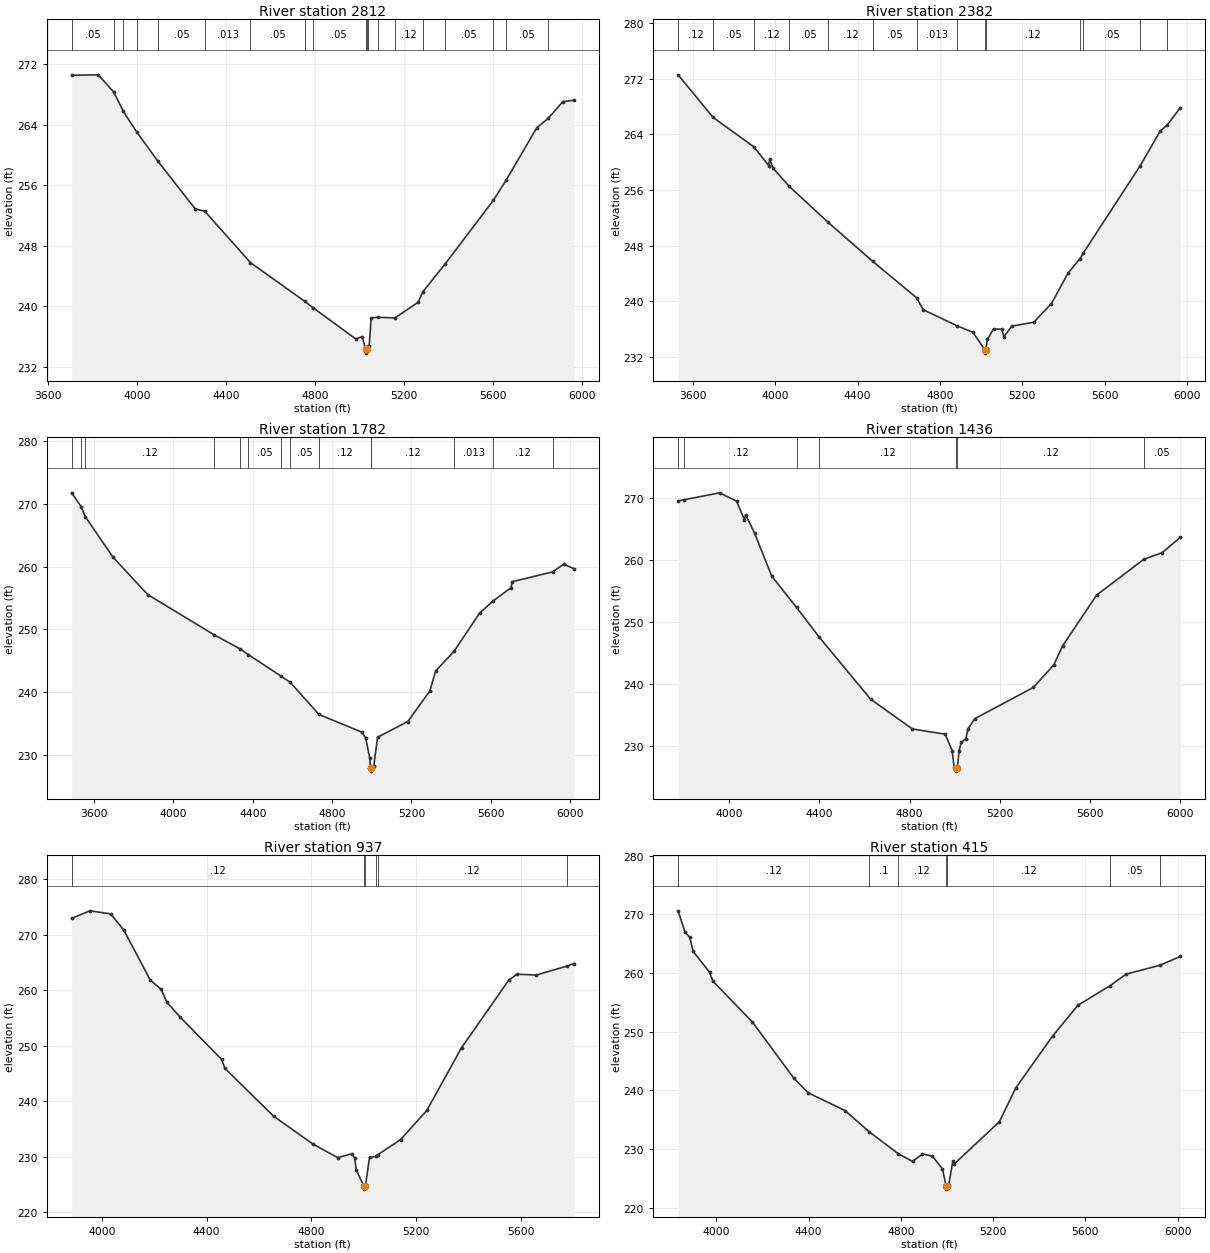
Type RM Length L Ch R = 1,2812,430,430,430
BEGIN DESCRIPTION:
Mapping XS 068858b7
END DESCRIPTION:
XS GIS Cut Line= 4
      2538439.56     13607657.14      2538207.81     13606761.55
      2537940.89     13606179.95      2537248.39     13606115.59
#Sta/Elev= 30
  3704.6  270.53  3824.1  270.58  3894.3  268.30  3937.6  265.74  3996.9  263.05
  4093.6  259.13  4260.6  252.87  4304.4  252.54  4509.4  245.76  4754.1  240.64
  4790.5  239.81  4983.8  235.67  5012.3  235.98  5027.8  234.30  5028.0  233.80
  5031.8  234.30  5038.5  234.78  5044.0  234.75  5052.7  238.46  5084.6  238.54
  5159.8  238.45  5264.1  240.52  5286.1  241.94  5384.7  245.55  5603.4  254.02
  5659.7  256.63  5797.8  263.56  5850.5  264.86  5915.4  267.03  5965.1  267.23
#Mann=19,-1,0
  3704.6    0.05       0  3894.3    0.12       0  3937.6    0.05       0
  3996.9    0.12       0  4093.6    0.05       0  4304.4   0.013       0
  4509.4    0.05       0  4754.1    0.12       0  4790.5    0.05       0
  5027.8    0.05       0  5031.8    0.05       0  5038.5    0.12       0
  5084.6    0.05       0  5159.8    0.12       0  5286.1   0.013       0
  5384.7    0.05       0  5603.4    0.12       0  5659.7    0.05       0
  5850.5    0.12       0
Bank Sta=5027.8,5031.8
Exp/Cntr=0.3,0.1

Type RM Length L Ch R = 1,2382,600,600,600
BEGIN DESCRIPTION:
Mapping XS 5b57c8be
END DESCRIPTION:
XS GIS Cut Line= 3
      2538543.72     13607844.63      2538465.19     13606375.03
      2538559.34     13605412.32
#Sta/Elev= 30
  3528.3  272.55  3698.7  266.42  3896.3  262.20  3968.2  259.51  3973.2  260.49
  3988.6  259.16  4067.5  256.54  4256.3  251.37  4474.3  245.73  4686.8  240.51
  4718.6  238.80  4884.5  236.47  4960.0  235.55  5017.7  233.06  5018.1  232.56
  5022.5  233.06  5030.2  234.53  5060.3  236.05  5100.5  236.00  5110.6  234.91
  5148.9  236.44  5255.6  237.00  5341.6  239.69  5422.0  244.05  5477.9  246.06
  5496.2  246.94  5773.1  259.52  5870.2  264.50  5903.1  265.31  5967.3  267.83
#Mann=14,-1,0
  3528.3    0.12       0  3698.7    0.05       0  3896.3    0.12       0
  4067.5    0.05       0  4256.3    0.12       0  4474.3    0.05       0
  4686.8   0.013       0  4884.5    0.12       0  5017.7    0.05       0
  5022.5    0.12       0  5477.9    0.03       0  5496.2    0.05       0
  5773.1    0.12       0  5903.1    0.05       0
Bank Sta=5017.7,5022.5
Exp/Cntr=0.3,0.1

Type RM Length L Ch R = 1,1782,346,346,346
BEGIN DESCRIPTION:
Mapping XS f526c784
END DESCRIPTION:
XS GIS Cut Line= 3
      2538673.92     13607797.77      2539028.09     13606292.53
      2538913.51     13605313.36
#Sta/Elev= 30
  3486.9  271.77  3535.8  269.52  3556.1  267.95  3695.2  261.52  3869.9  255.56
  4203.4  249.17  4335.8  246.91  4378.3  245.97  4540.2  242.60  4589.3  241.56
  4733.8  236.44  4948.5  233.65  4969.1  232.76  4989.6  229.56  4993.8  227.91
  4994.2  227.41  4998.8  227.91  5010.2  228.20  5029.4  232.81  5181.8  235.32
  5292.5  240.16  5322.7  243.40  5414.8  246.50  5544.2  252.61  5613.8  254.58
  5702.7  256.65  5707.8  257.60  5912.4  259.17  5967.7  260.39  6019.1  259.69
#Mann=14,-1,0
  3486.9    0.12       0  3535.8    0.05       0  3556.1    0.12       0
  4203.4    0.05       0  4335.8    0.12       0  4378.3    0.05       0
  4540.2    0.12       0  4589.3    0.05       0  4733.8    0.12       0
  4993.8    0.05       0  4998.8    0.12       0  5414.8   0.013       0
  5613.8    0.12       0  5912.4    0.05       0
Bank Sta=4993.8,4998.8
Exp/Cntr=0.3,0.1

Type RM Length L Ch R = 1,1436,499,499,499
BEGIN DESCRIPTION:
Mapping XS 49b8f30e
END DESCRIPTION:
XS GIS Cut Line= 3
      2539054.12     13607511.32      2539366.63     13606323.78
      2539408.30     13605323.82
#Sta/Elev= 30
  3772.9  269.56  3800.3  269.75  3956.8  270.86  4032.3  269.53  4067.4  266.50
  4072.6  267.33  4112.9  264.31  4188.4  257.44  4298.4  252.39  4399.5  247.59
  4627.4  237.60  4813.0  232.80  4958.2  231.96  4989.3  229.30  4997.7  226.67
  5007.1  226.51  5007.5  226.01  5012.2  226.51  5019.7  229.30  5029.7  230.67
  5049.7  231.21  5059.7  232.86  5089.7  234.47  5350.0  239.51  5440.0  243.13
  5480.1  246.25  5630.2  254.38  5840.1  260.16  5920.4  261.20  6001.7  263.68
#Mann=7,-1,0
  3772.9    0.05       0  3800.3    0.12       0  4298.4    0.05       0
  4399.5    0.12       0  5007.1    0.05       0  5012.2    0.12       0
  5840.1    0.05       0
Bank Sta=5007.1,5012.2
Exp/Cntr=0.3,0.1

Type RM Length L Ch R = 1,937,522,522,522
BEGIN DESCRIPTION:
Mapping XS 0f3508fe
END DESCRIPTION:
XS GIS Cut Line= 3
      2539132.24     13607490.48      2539757.26     13606620.65
      2540033.06     13605819.28
#Sta/Elev= 30
  3884.5  272.99  3954.1  274.35  4033.9  273.80  4084.2  270.85  4184.9  261.88
  4226.6  260.20  4248.3  257.89  4297.9  255.25  4457.4  247.58  4470.0  245.97
  4656.3  237.33  4807.3  232.29  4901.0  229.88  4955.6  230.58  4965.4  229.84
  4972.1  227.65  5001.3  224.70  5001.7  224.20  5006.5  224.70  5022.6  229.93
  5047.9  230.11  5054.2  230.40  5141.4  233.14  5241.2  238.37  5374.0  249.68
  5553.8  261.81  5585.5  262.93  5659.6  262.78  5776.6  264.39  5803.1  264.85
#Mann=6,-1,0
  3884.5    0.12       0  5001.3    0.05       0  5006.5    0.12       0
  5047.9    0.05       0  5054.2    0.12       0  5776.6    0.05       0
Bank Sta=5001.3,5006.5
Exp/Cntr=0.3,0.1

Type RM Length L Ch R = 1,415,284,284,284
BEGIN DESCRIPTION:
TRIB 13 TO IRISH CREEK 1.0
END DESCRIPTION:
XS GIS Cut Line= 3
      2539288.54     13607459.17      2540231.13     13606772.26
      2540189.55     13605761.25
#Sta/Elev= 30
  3833.7  270.60  3863.3  267.01  3884.1  266.09  3898.8  263.70  3969.9  260.15
  3984.5  258.62  4156.1  251.64  4336.1  242.04  4398.7  239.56  4557.8  236.55
  4661.7  232.96  4788.4  229.21  4850.6  227.89  4893.5  229.15  4936.4  228.79
  4980.1  226.62  4996.7  223.66  4997.1  223.16  5001.9  223.66  5007.3  223.89
  5025.0  227.87  5030.0  227.40  5227.5  234.67  5297.5  240.37  5457.7  249.24
  5567.8  254.50  5705.8  257.80  5777.9  259.83  5924.0  261.32  6011.9  262.83
#Mann=7,-1,0
  3833.7    0.12       0  4661.7     0.1       0  4788.4    0.12       0
  4996.7    0.05       0  5001.9    0.12       0  5705.8    0.05       0
  5924.0    0.12       0
Bank Sta=4996.7,5001.9
Exp/Cntr=0.3,0.1

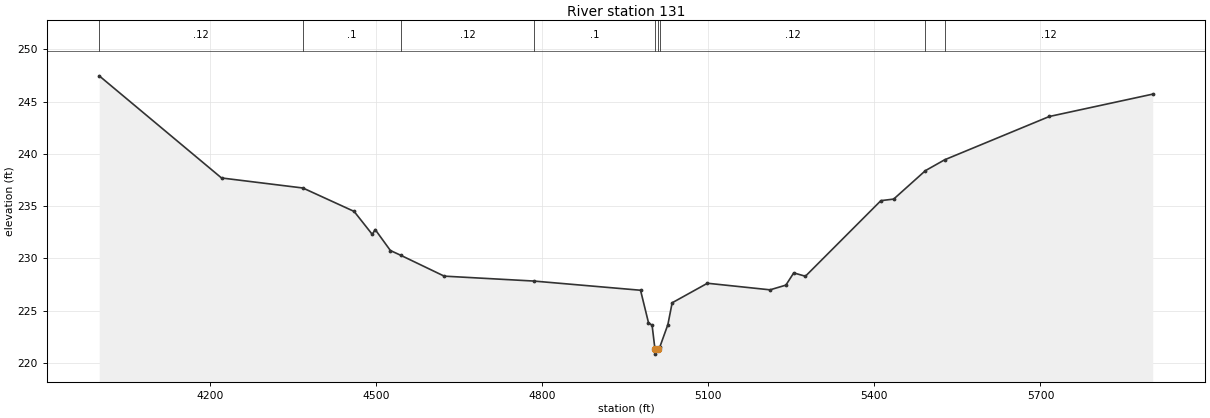
Type RM Length L Ch R = 1,131,0,0,0
BEGIN DESCRIPTION:
TRIB 13 TO IRISH CREEK 0.5
END DESCRIPTION:
XS GIS Cut Line= 4
      2539638.88     13607404.87      2540190.10     13607235.60
      2540641.48     13606706.09      2540723.94     13606081.12
#Sta/Elev= 30
  4000.0  247.46  4220.9  237.69  4367.9  236.73  4460.4  234.49  4493.2  232.29
  4498.4  232.76  4525.9  230.75  4545.2  230.28  4623.1  228.30  4784.9  227.83
  4977.7  226.95  4992.0  223.86  4998.6  223.59  5003.7  221.34  5004.1  220.84
  5008.9  221.34  5012.4  221.50  5027.1  223.67  5034.8  225.75  5098.5  227.62
  5211.6  226.99  5240.2  227.44  5254.4  228.61  5275.5  228.29  5411.8  235.52
  5434.9  235.67  5492.2  238.39  5527.0  239.43  5716.0  243.57  5902.8  245.71
#Mann=9,-1,0
  4000.0    0.12       0  4367.9     0.1       0  4545.2    0.12       0
  4784.9     0.1       0  5003.7    0.05       0  5008.9     0.1       0
  5012.4    0.12       0  5492.2    0.05       0  5527.0    0.12       0
Bank Sta=5003.7,5008.9
Exp/Cntr=0.3,0.1

Chan Stop Cuts=-1