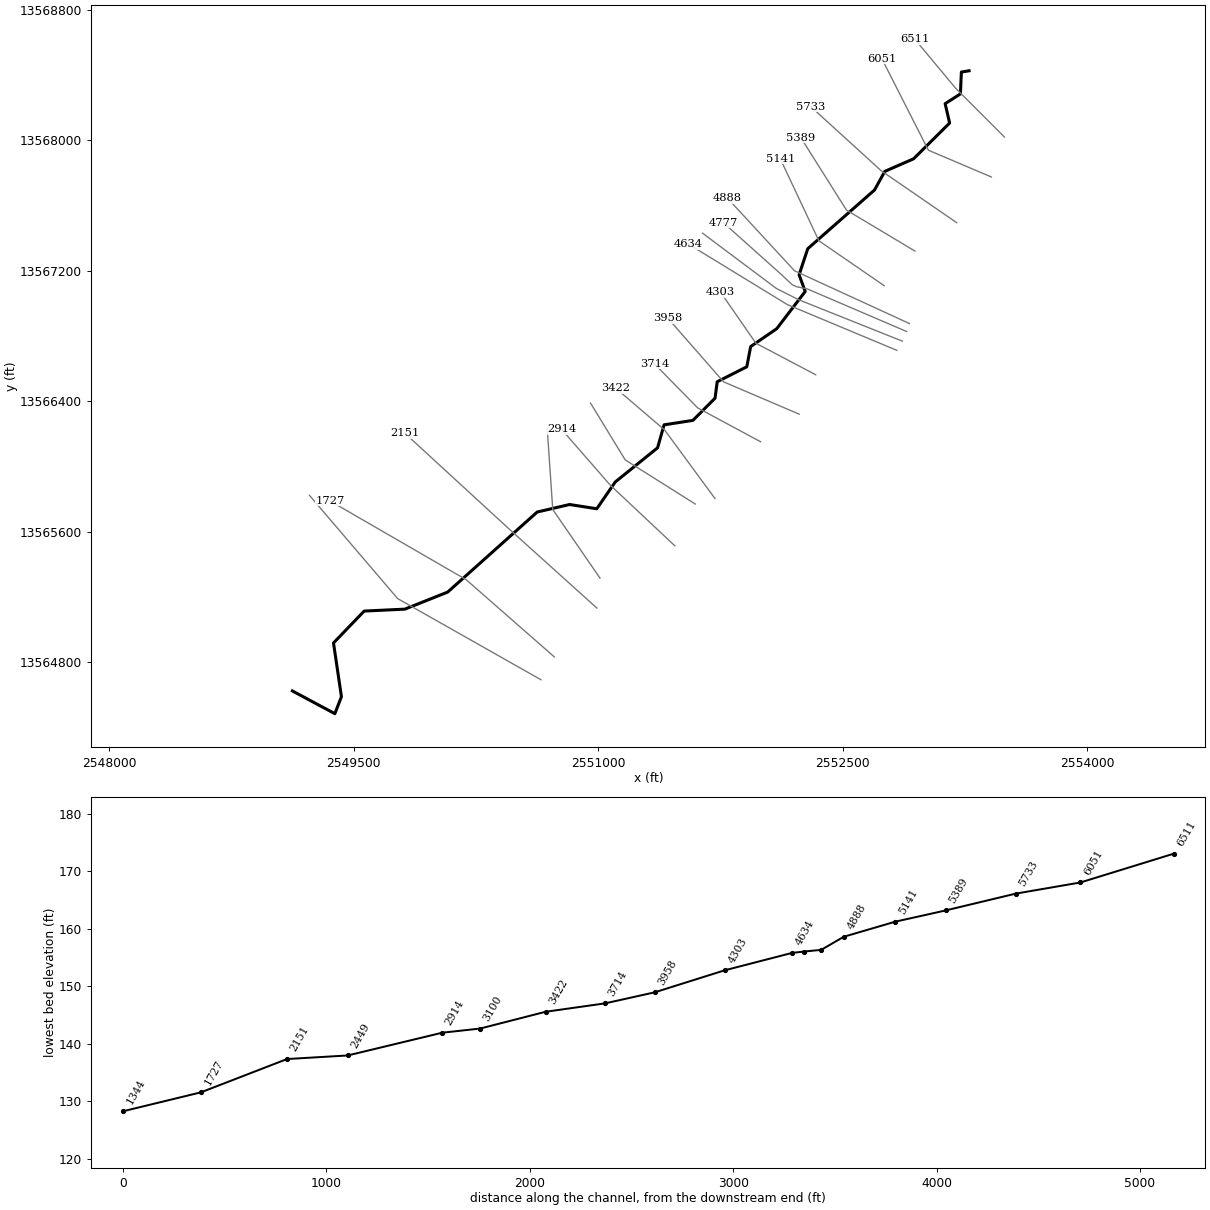
--- TRIB 13_1 TO GUADALUPE RIVER.prj (project) ---

Proj Title=TRIB 13_1 TO GUADALUPE RIVER Base Level Engineering
Current Plan=p01
Default Exp/Contr=0.3,0.1
English Units
Geom File=g01
Flow File=f01
Plan File=p01
Y Axis Title=Elevation
X Axis Title(PF)=Main Channel Distance
X Axis Title(XS)=Station
BEGIN DESCRIPTION:
TRIB 13_1 TO GUADALUPE RIVER
END DESCRIPTION:
DSS Export Rating Curves= 0
DSS Export Rating Curve Sorted= 0
DSS Export Volume Flow Curves= 0
DXF OffsetX= 0
DXF OffsetY= 0
DXF ScaleX= 1
DXF ScaleY= 10

--- TRIB 13_1 TO GUADALUPE RIVER.p01 (plan) ---

Plan Title=Multiple Run
Short Identifier=Multiple
Geom File=g01
Flow File=f01
Subcritical Flow
K Sum by GR= 0
Std Step Tol= 0.01
Critical Tol= 0.01
Num of Std Step Trials= 20
Max Error Tol= 0.3
Flow Tol Ratio= 0.001
Split Flow NTrial= 30
Split Flow Tol= 0.02
Split Flow Ratio= 0.02
Log Output Level= 0
Friction Slope Method= 1
Unsteady Friction Slope Method= 2
Unsteady Bridges Friction Slope Method= 1
Parabolic Critical Depth
Global Vel Dist=  1 , 1 , 1
Global Log Level= 0
CheckData=True
Encroach Param= -1, 0, 0, 0
BEGIN DESCRIPTION:
Multiple Run
END DESCRIPTION:

--- TRIB 13_1 TO GUADALUPE RIVER.f01 (steady flow) ---

Flow Title=Multiple
Number of Profiles=7
Profile Names=10-year,25-year,50-year,1pct_min,100-year,1pct_plu,500-year
River Rch & RM= TRIB 13_1 TO GUA,Reach-1,6511
     513     817    1090     706    1408    2809    2322
River Rch & RM= TRIB 13_1 TO GUA,Reach-1,4303
     834    1369    1861    1226    2447    4882    4186
Boundary for River Rch & Prof#=TRIB 13_1 TO GUA,Reach-1,1
Up Type=0
Dn Type=3
Dn Slope=0.005
Boundary for River Rch & Prof#=TRIB 13_1 TO GUA,Reach-1,2
Up Type=0
Dn Type=3
Dn Slope=0.005
Boundary for River Rch & Prof#=TRIB 13_1 TO GUA,Reach-1,3
Up Type=0
Dn Type=3
Dn Slope=0.005
Boundary for River Rch & Prof#=TRIB 13_1 TO GUA,Reach-1,4
Up Type=0
Dn Type=3
Dn Slope=0.005
Boundary for River Rch & Prof#=TRIB 13_1 TO GUA,Reach-1,5
Up Type=0
Dn Type=3
Dn Slope=0.005
Boundary for River Rch & Prof#=TRIB 13_1 TO GUA,Reach-1,6
Up Type=0
Dn Type=3
Dn Slope=0.005
Boundary for River Rch & Prof#=TRIB 13_1 TO GUA,Reach-1,7
Up Type=0
Dn Type=3
Dn Slope=0.005

--- TRIB 13_1 TO GUADALUPE RIVER.g01 (geometry) ---

Geom Title=Existing Conditions

River Reach=TRIB 13_1 TO GUA,Reach-1
Reach XY= 30
      2553275.00     13568425.00      2553227.72     13568417.28
      2553221.90     13568283.31      2553128.10     13568223.55
      2553155.70     13568104.97      2552934.68     13567885.76
      2552757.95     13567808.51      2552695.38     13567694.84
      2552285.52     13567334.79      2552232.59     13567174.99
      2552269.89     13567072.71      2552095.42     13566844.77
      2551935.39     13566735.10      2551911.74     13566611.34
      2551730.25     13566519.56      2551717.12     13566418.88
      2551581.19     13566282.82      2551404.36     13566255.59
      2551364.61     13566114.90      2551104.62     13565905.16
      2550991.79     13565741.39      2550825.00     13565767.44
      2550626.47     13565721.46      2550077.30     13565230.83
      2549814.50     13565126.22      2549565.20     13565114.52
      2549377.06     13564919.15      2549425.73     13564590.02
      2549385.39     13564485.80      2549125.00     13564625.00

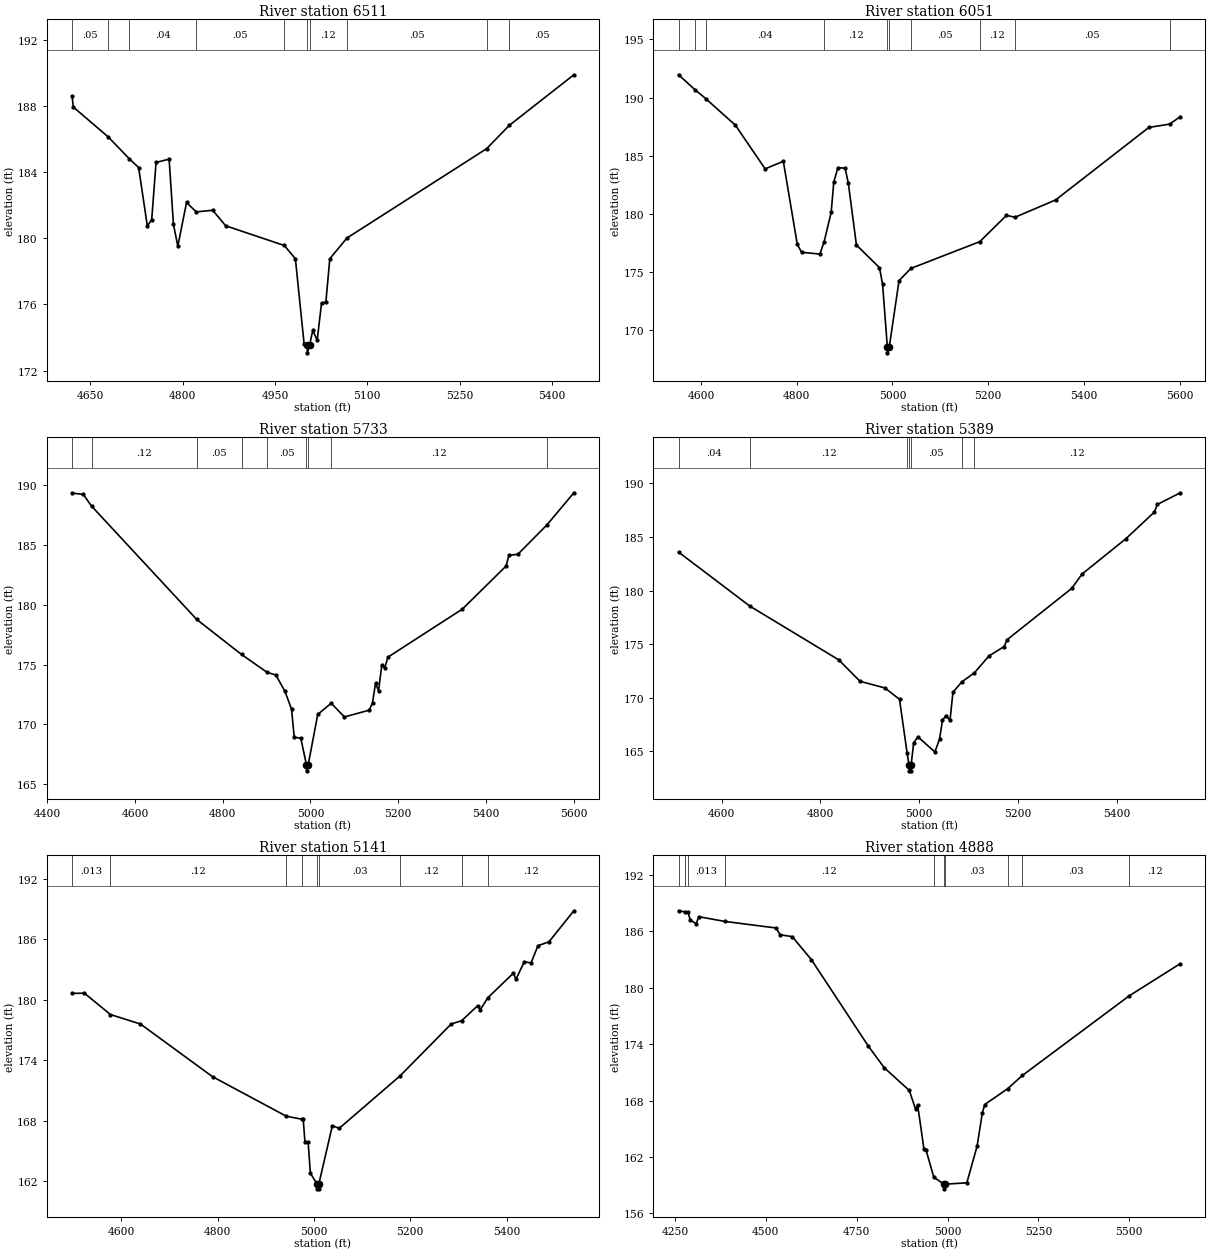
Type RM Length L Ch R = 1,6511,460,460,460
BEGIN DESCRIPTION:
TRIB 13_1 TO GUADALUPE RIVER 14.0
END DESCRIPTION:
XS GIS Cut Line= 3
      2553491.82     13568018.97      2553191.82     13568318.96
      2552941.80     13568618.99
#Sta/Elev= 30
  4620.5  188.60  4622.5  187.93  4679.0  186.13  4713.5  184.80  4728.6  184.27
  4742.7  180.74  4749.8  181.12  4756.9  184.58  4778.1  184.78  4785.1  180.84
  4792.2  179.52  4806.4  182.16  4822.1  181.59  4848.8  181.69  4870.0  180.75
  4965.1  179.56  4983.1  178.76  4997.3  173.61  5002.4  173.57  5002.6  173.07
  5006.4  173.57  5011.4  174.44  5018.5  173.82  5025.6  176.09  5032.6  176.13
  5039.0  178.76  5066.8  180.01  5293.6  185.41  5330.4  186.82  5435.3  189.88
#Mann=10,-1,0
  4620.5    0.05       0  4679.0    0.12       0  4713.5    0.04       0
  4822.1    0.05       0  4965.1    0.12       0  5002.4    0.05       0
  5006.4    0.12       0  5066.8    0.05       0  5293.6    0.03       0
  5330.4    0.05       0
Bank Sta=5002.4,5006.4
Exp/Cntr=0.3,0.1

Type RM Length L Ch R = 1,6051,318,318,318
BEGIN DESCRIPTION:
Mapping XS 35bdccab
END DESCRIPTION:
XS GIS Cut Line= 3
      2553411.44     13567774.38      2553025.14     13567938.56
      2552740.23     13568498.72
#Sta/Elev= 30
  4553.1  191.96  4587.3  190.68  4609.6  189.92  4672.0  187.62  4734.0  183.87
  4772.0  184.52  4801.1  177.39  4810.0  176.70  4848.4  176.54  4857.3  177.61
  4872.0  180.14  4877.4  182.75  4886.1  183.97  4901.1  183.93  4907.8  182.63
  4924.7  177.32  4972.8  175.38  4979.3  173.97  4989.3  168.55  4989.5  168.05
  4993.3  168.55  5013.7  174.26  5038.5  175.31  5182.4  177.61  5238.1  179.87
  5256.1  179.71  5340.9  181.20  5535.5  187.43  5579.0  187.72  5601.3  188.36
#Mann=10,-1,0
  4553.1    0.12       0  4587.3    0.05       0  4609.6    0.04       0
  4857.3    0.12       0  4989.3    0.05       0  4993.3    0.12       0
  5038.5    0.05       0  5182.4    0.12       0  5256.1    0.05       0
  5579.0    0.12       0
Bank Sta=4989.3,4993.3
Exp/Cntr=0.3,0.1

Type RM Length L Ch R = 1,5733,344,344,344
BEGIN DESCRIPTION:
Mapping XS 12ddb53d
END DESCRIPTION:
XS GIS Cut Line= 3
      2553199.01     13567494.29      2552735.41     13567813.01
      2552305.64     13568204.15
#Sta/Elev= 30
  4456.6  189.35  4482.0  189.25  4500.9  188.27  4740.7  178.78  4842.8  175.85
  4901.3  174.35  4921.1  174.13  4942.0  172.75  4956.9  171.26  4963.0  168.91
  4977.9  168.85  4990.8  166.61  4991.0  166.11  4994.8  166.61  5016.5  170.83
  5047.2  171.77  5077.4  170.62  5134.1  171.19  5141.4  171.81  5148.3  173.45
  5155.1  172.80  5162.5  174.94  5169.3  174.74  5176.7  175.63  5346.3  179.65
  5445.6  183.24  5452.4  184.15  5472.7  184.23  5539.6  186.72  5600.3  189.38
#Mann=9,-1,0
  4456.6    0.04       0  4500.9    0.12       0  4740.7    0.05       0
  4842.8    0.12       0  4901.3    0.05       0  4990.8    0.05       0
  4994.8    0.05       0  5047.2    0.12       0  5539.6    0.05       0
Bank Sta=4990.8,4994.8
Exp/Cntr=0.3,0.1

Type RM Length L Ch R = 1,5389,248,248,248
BEGIN DESCRIPTION:
Mapping XS c456faf0
END DESCRIPTION:
XS GIS Cut Line= 3
      2552943.03     13567320.48      2552522.94     13567571.57
      2552242.86     13568015.84
#Sta/Elev= 30
  4513.1  183.59  4657.3  178.55  4837.0  173.54  4880.1  171.54  4930.2  170.92
  4959.9  169.86  4975.1  164.90  4979.3  163.69  4979.5  163.19  4983.0  163.19
  4983.3  163.69  4988.5  165.79  4996.9  166.37  5031.4  164.95  5040.8  166.14
  5046.7  167.89  5053.8  168.35  5062.0  167.89  5067.9  170.51  5085.5  171.47
  5111.3  172.33  5140.9  173.91  5171.5  174.78  5177.4  175.42  5308.0  180.20
  5329.2  181.55  5417.5  184.83  5475.2  187.32  5481.1  188.03  5527.7  189.12
#Mann=7,-1,0
  4513.1    0.04       0  4657.3    0.12       0  4975.1    0.05       0
  4979.3    0.05       0  4983.3    0.05       0  5085.5    0.03       0
  5111.3    0.12       0
Bank Sta=4979.3,4983.3
Exp/Cntr=0.3,0.1

Type RM Length L Ch R = 1,5141,253,253,253
BEGIN DESCRIPTION:
Mapping XS ac498b87
END DESCRIPTION:
XS GIS Cut Line= 3
      2552754.70     13567108.03      2552353.93     13567383.25
      2552117.33     13567885.43
#Sta/Elev= 30
  4498.2  180.61  4523.8  180.63  4577.9  178.51  4640.2  177.57  4789.7  172.35
  4942.8  168.43  4975.4  168.13  4977.8  168.17  4981.5  165.85  4988.1  165.85
  4992.7  162.78  5006.4  161.73  5006.7  161.23  5010.2  161.23  5010.4  161.73
  5038.3  167.49  5052.6  167.23  5179.3  172.45  5284.8  177.57  5306.6  177.90
  5340.0  179.39  5345.5  179.00  5360.6  180.16  5413.9  182.61  5419.4  182.01
  5436.7  183.76  5450.6  183.62  5465.0  185.34  5487.8  185.72  5539.5  188.80
#Mann=9,-1,0
  4498.2   0.013       0  4577.9    0.12       0  4942.8    0.05       0
  4975.4    0.03       0  5006.4    0.03       0  5010.4    0.03       0
  5179.3    0.12       0  5306.6    0.03       0  5360.6    0.12       0
Bank Sta=5006.4,5010.4
Exp/Cntr=0.3,0.1

Type RM Length L Ch R = 1,4888,111,111,111
BEGIN DESCRIPTION:
Mapping XS f5d4ea79
END DESCRIPTION:
XS GIS Cut Line= 3
      2552909.26     13566876.22      2552204.24     13567199.75
      2551793.76     13567644.04
#Sta/Elev= 30
  4259.8  188.20  4277.4  188.09  4285.6  188.04  4292.4  187.19  4308.5  186.83
  4315.4  187.57  4387.0  187.07  4527.8  186.37  4539.6  185.64  4572.6  185.45
  4625.3  183.00  4781.6  173.82  4825.7  171.50  4894.7  169.08  4912.2  167.06
  4917.7  167.52  4935.2  162.80  4940.7  162.74  4962.2  159.84  4990.2  159.11
  4990.4  158.61  4994.2  159.11  5053.0  159.25  5081.3  163.16  5095.5  166.67
  5102.3  167.58  5165.4  169.27  5206.0  170.68  5499.5  179.14  5640.4  182.58
#Mann=10,-1,0
  4259.8   0.013       0  4277.4    0.12       0  4285.6   0.013       0
  4387.0    0.12       0  4962.2    0.03       0  4990.2    0.03       0
  4994.2    0.03       0  5165.4    0.05       0  5206.0    0.03       0
  5499.5    0.12       0
Bank Sta=4990.2,4994.2
Exp/Cntr=0.3,0.1

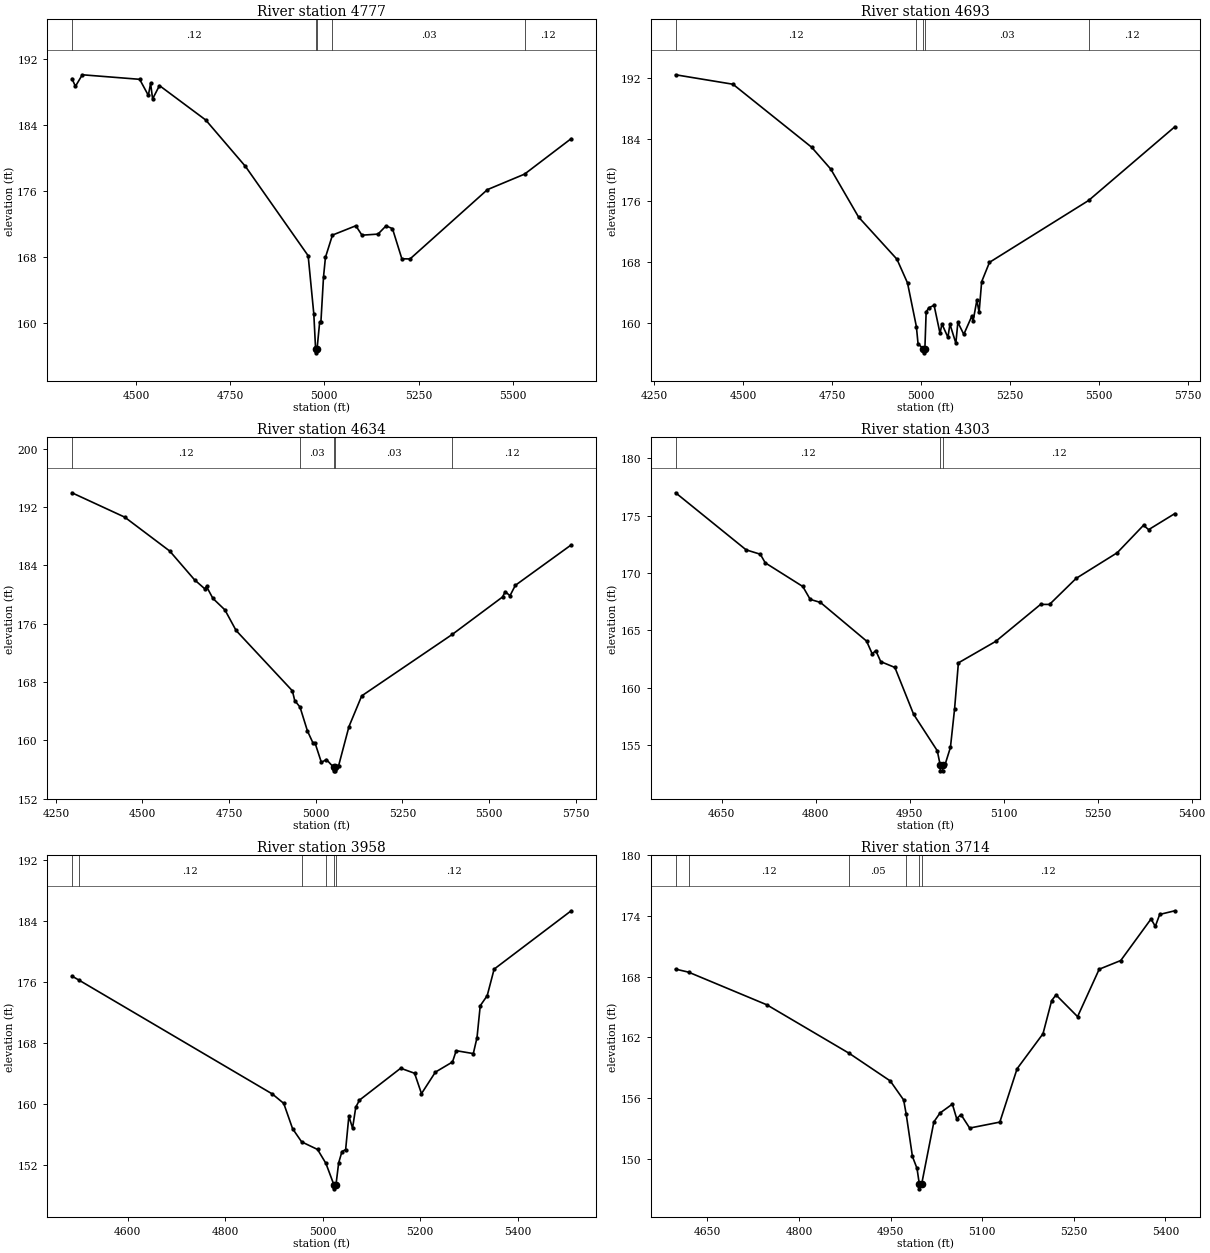
Type RM Length L Ch R = 1,4777,84,84,84
BEGIN DESCRIPTION:
Mapping XS 0da7769a
END DESCRIPTION:
XS GIS Cut Line= 6
      2552891.48     13566827.57      2552283.88     13567087.97
      2552217.91     13567101.86      2552190.13     13567114.01
      2552125.90     13567174.77      2551769.10     13567493.46
#Sta/Elev= 30
  4329.8  189.56  4339.1  188.63  4357.3  190.03  4509.6  189.48  4532.7  187.53
  4538.6  188.99  4544.0  187.11  4562.2  188.72  4685.0  184.55  4790.6  178.92
  4957.0  168.10  4972.0  161.05  4976.7  156.83  4977.0  156.33  4980.7  156.83
  4987.5  160.02  4990.8  160.02  4997.8  165.54  5002.9  167.90  5021.5  170.60
  5083.6  171.73  5099.9  170.59  5142.4  170.72  5163.8  171.72  5180.9  171.38
  5205.8  167.73  5227.5  167.71  5433.0  176.11  5531.6  177.99  5655.4  182.29
#Mann=5,-1,0
  4329.8    0.12       0  4976.7    0.05       0  4980.7    0.12       0
  5021.5    0.03       0  5531.6    0.12       0
Bank Sta=4976.7,4980.7
Exp/Cntr=0.3,0.1

Type RM Length L Ch R = 1,4693,59,59,59
BEGIN DESCRIPTION:
Mapping XS 386c9c28
END DESCRIPTION:
XS GIS Cut Line= 4
      2552865.45     13566768.54      2552230.06     13567022.00
      2552092.91     13567091.44      2551640.18     13567430.13
#Sta/Elev= 30
  4310.2  192.48  4471.4  191.24  4692.4  182.99  4746.3  180.12  4824.5  173.83
  4932.3  168.31  4962.0  165.20  4986.9  159.49  4991.6  157.24  5006.8  156.54
  5007.0  156.04  5010.8  156.54  5014.4  161.41  5022.4  161.96  5036.7  162.27
  5053.3  158.61  5058.9  159.81  5075.6  158.07  5081.2  159.80  5097.9  157.30
  5103.5  160.04  5120.2  158.46  5142.4  160.81  5146.4  160.23  5157.0  162.95
  5163.2  161.35  5170.4  165.36  5192.4  167.90  5471.1  176.01  5713.4  185.67
#Mann=5,-1,0
  4310.2    0.12       0  4986.9    0.03       0  5006.8    0.03       0
  5010.8    0.03       0  5471.1    0.12       0
Bank Sta=5006.8,5010.8
Exp/Cntr=0.3,0.1

Type RM Length L Ch R = 1,4634,331,331,331
BEGIN DESCRIPTION:
Mapping XS 17c4c1c1
END DESCRIPTION:
XS GIS Cut Line= 3
      2552831.99     13566712.04      2552160.78     13566992.12
      2551552.39     13567363.91
#Sta/Elev= 30
  4296.5  193.93  4448.7  190.59  4578.6  185.94  4650.1  182.00  4679.3  180.78
  4684.7  181.08  4703.1  179.45  4737.8  177.87  4770.0  175.05  4932.5  166.77
  4939.2  165.44  4954.5  164.54  4975.9  161.27  4992.2  159.59  4997.7  159.64
  5016.1  156.96  5030.6  157.35  5051.1  156.30  5051.4  155.80  5054.9  155.80
  5055.1  156.30  5065.7  156.48  5095.7  161.87  5132.5  166.08  5393.8  174.51
  5539.0  179.65  5546.2  180.37  5560.3  179.82  5575.7  181.24  5736.8  186.78
#Mann=5,-1,0
  4296.5    0.12       0  4954.5    0.03       0  5051.1    0.03       0
  5055.1    0.03       0  5393.8    0.12       0
Bank Sta=5051.1,5055.1
Exp/Cntr=0.3,0.1

Type RM Length L Ch R = 1,4303,345,345,345
BEGIN DESCRIPTION:
Mapping XS f2d785f6
END DESCRIPTION:
XS GIS Cut Line= 3
      2552334.57     13566562.37      2551967.63     13566755.50
      2551750.34     13567069.36
#Sta/Elev= 30
  4576.7  176.99  4689.2  172.02  4711.8  171.64  4719.7  170.89  4779.6  168.83
  4791.4  167.71  4807.8  167.44  4881.3  164.08  4890.3  162.97  4896.0  163.25
  4903.9  162.29  4926.5  161.78  4956.4  157.70  4994.1  154.53  4998.8  153.28
  4999.1  152.78  5002.6  152.78  5002.8  153.28  5006.9  153.39  5015.1  154.82
  5021.7  158.16  5027.8  162.18  5087.3  164.05  5158.9  167.27  5173.2  167.27
  5215.7  169.54  5281.2  171.77  5323.1  174.16  5331.3  173.78  5373.1  175.18
#Mann=3,-1,0
  4576.7    0.12       0  4998.8    0.05       0  5002.8    0.12       0
Bank Sta=4998.8,5002.8
Exp/Cntr=0.3,0.1

Type RM Length L Ch R = 1,3958,244,244,244
BEGIN DESCRIPTION:
Mapping XS fd21d9f5
END DESCRIPTION:
XS GIS Cut Line= 3
      2552233.20     13566320.92      2551769.65     13566518.89
      2551426.79     13566910.04
#Sta/Elev= 30
  4485.5  176.83  4499.4  176.32  4896.7  161.37  4920.0  160.14  4938.1  156.83
  4956.7  155.10  4989.4  154.10  5006.5  152.28  5023.1  149.44  5023.4  148.94
  5027.1  149.44  5032.7  152.35  5039.4  153.82  5047.0  154.09  5053.6  158.46
  5061.2  156.90  5067.8  159.65  5075.4  160.57  5159.9  164.75  5188.4  164.09
  5202.6  161.42  5231.1  164.24  5266.2  165.57  5273.8  167.05  5308.9  166.67
  5316.5  168.76  5323.1  172.94  5337.4  174.26  5351.6  177.74  5509.7  185.39
#Mann=6,-1,0
  4485.5    0.05       0  4499.4    0.12       0  4956.7    0.05       0
  5006.5    0.12       0  5023.1    0.05       0  5027.1    0.12       0
Bank Sta=5023.1,5027.1
Exp/Cntr=0.3,0.1

Type RM Length L Ch R = 1,3714,292,292,292
BEGIN DESCRIPTION:
Mapping XS fb06e2ec
END DESCRIPTION:
XS GIS Cut Line= 3
      2551996.56     13566151.92      2551610.30     13566359.54
      2551344.74     13566629.92
#Sta/Elev= 30
  4598.0  168.75  4619.2  168.45  4747.4  165.22  4882.3  160.42  4949.5  157.69
  4971.4  155.81  4975.6  154.40  4985.8  150.22  4993.3  149.04  4997.0  147.52
  4997.3  147.02  5001.0  147.52  5020.9  153.64  5031.0  154.52  5051.2  155.40
  5058.2  153.97  5065.3  154.36  5079.5  153.03  5128.9  153.62  5157.2  158.90
  5199.6  162.36  5213.8  165.64  5220.9  166.20  5256.2  164.05  5291.6  168.74
  5326.9  169.60  5376.5  173.71  5383.5  172.98  5390.7  174.16  5415.5  174.52
#Mann=6,-1,0
  4598.0    0.05       0  4619.2    0.12       0  4882.3    0.05       0
  4975.6    0.12       0  4997.0    0.05       0  5001.0    0.12       0
Bank Sta=4997,5001
Exp/Cntr=0.3,0.1

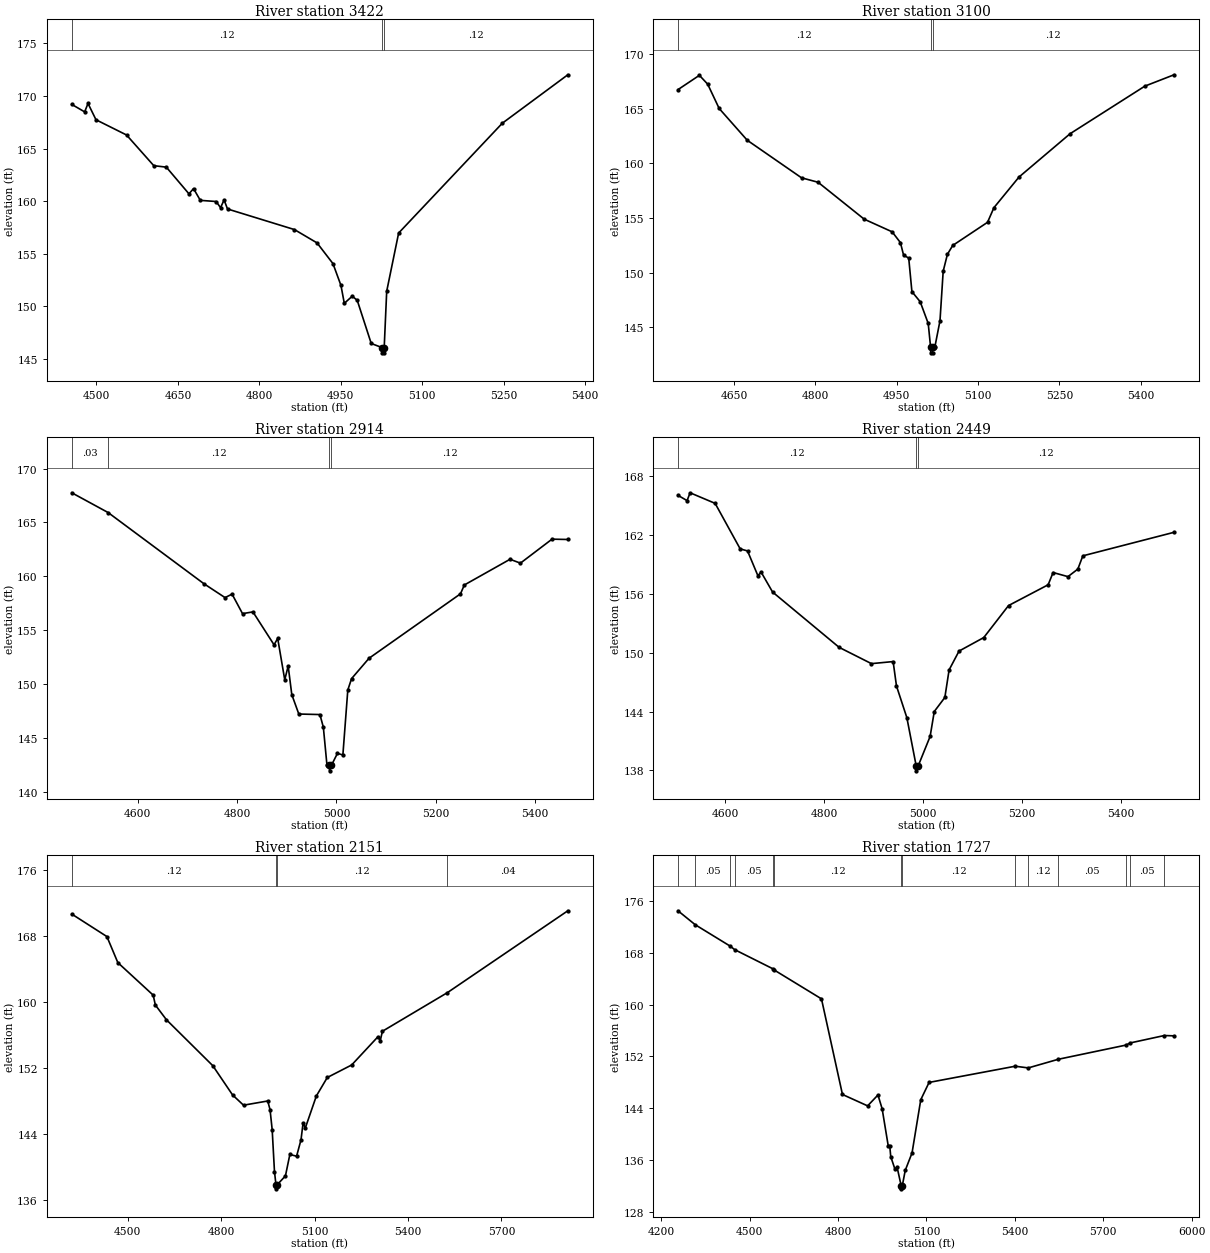
Type RM Length L Ch R = 1,3422,322,322,322
BEGIN DESCRIPTION:
Mapping XS fa5e6873
END DESCRIPTION:
XS GIS Cut Line= 3
      2551716.53     13565804.23      2551407.49     13566224.33
      2551109.23     13566479.29
#Sta/Elev= 30
  4454.5  169.20  4478.2  168.49  4484.4  169.29  4499.1  167.74  4555.4  166.29
  4605.6  163.37  4628.7  163.23  4670.4  160.69  4678.8  161.19  4691.3  160.07
  4720.5  159.96  4728.6  159.37  4735.1  160.11  4741.4  159.25  4864.7  157.29
  4906.4  156.02  4935.7  154.05  4950.4  151.98  4956.6  150.27  4971.2  150.95
  4980.4  150.56  5006.2  146.45  5026.1  146.06  5026.4  145.56  5029.9  145.56
  5030.1  146.06  5034.7  151.42  5056.7  156.96  5247.7  167.41  5368.4  172.02
#Mann=3,-1,0
  4454.5    0.12       0  5026.1    0.05       0  5030.1    0.12       0
Bank Sta=5026.1,5030.1
Exp/Cntr=0.3,0.1

Type RM Length L Ch R = 1,3100,186,186,186
BEGIN DESCRIPTION:
Mapping XS 7e154ee3
END DESCRIPTION:
XS GIS Cut Line= 3
      2551595.77     13565770.45      2551166.04     13566040.84
      2550953.56     13566388.54
#Sta/Elev= 30
  4546.4  166.76  4585.9  168.07  4601.2  167.26  4622.4  165.03  4674.2  162.12
  4774.3  158.68  4804.9  158.27  4889.9  154.89  4941.5  153.73  4956.8  152.74
  4962.7  151.58  4972.1  151.33  4978.0  148.25  4993.3  147.32  5008.1  145.33
  5012.5  143.14  5012.7  142.64  5016.2  142.64  5016.5  143.14  5020.4  143.19
  5029.8  145.58  5035.7  150.12  5043.5  151.67  5053.3  152.48  5117.5  154.60
  5129.3  155.94  5175.6  158.75  5269.9  162.72  5407.8  167.08  5461.6  168.12
#Mann=3,-1,0
  4546.4    0.12       0  5012.5    0.05       0  5016.5    0.12       0
Bank Sta=5012.5,5016.5
Exp/Cntr=0.3,0.1

Type RM Length L Ch R = 1,2914,465,465,465
BEGIN DESCRIPTION:
Mapping XS bd48c207
END DESCRIPTION:
XS GIS Cut Line= 3
      2551470.23     13565514.53      2551074.30     13565886.32
      2550774.91     13566229.17
#Sta/Elev= 30
  4467.4  167.76  4540.6  165.92  4733.3  159.31  4775.8  158.02  4790.0  158.34
  4811.0  156.53  4832.0  156.69  4874.5  153.63  4881.8  154.23  4896.0  150.38
  4902.9  151.66  4910.2  149.00  4924.3  147.20  4966.8  147.15  4973.7  145.97
  4981.0  142.43  4985.8  142.42  4986.1  141.92  4989.8  142.42  5002.0  143.54
  5013.0  143.40  5022.9  149.43  5030.5  150.49  5065.6  152.38  5249.7  158.37
  5257.4  159.19  5349.4  161.58  5370.3  161.22  5433.9  163.45  5465.7  163.42
#Mann=4,-1,0
  4467.4    0.03       0  4540.6    0.12       0  4985.8    0.05       0
  4989.8    0.12       0
Bank Sta=4985.8,4989.8
Exp/Cntr=0.3,0.1

Type RM Length L Ch R = 1,2449,298,298,298
BEGIN DESCRIPTION:
Mapping XS 0550c1e5
END DESCRIPTION:
XS GIS Cut Line= 3
      2551011.55     13565316.48      2550721.79     13565736.63
      2550687.99     13566229.20
#Sta/Elev= 30
  4504.1  166.05  4522.5  165.51  4528.6  166.31  4579.3  165.23  4630.0  160.59
  4644.9  160.38  4665.8  157.86  4672.4  158.22  4695.6  156.19  4830.3  150.55
  4895.7  148.89  4939.6  149.10  4946.4  146.61  4967.4  143.38  4986.3  138.46
  4986.6  137.96  4990.3  138.46  5014.5  141.47  5022.9  144.01  5044.3  145.44
  5052.9  148.25  5073.0  150.17  5123.1  151.55  5173.2  154.81  5253.4  156.93
  5263.4  158.18  5293.5  157.76  5313.5  158.53  5323.6  159.88  5508.2  162.28
#Mann=3,-1,0
  4504.1    0.12       0  4986.3    0.05       0  4990.3    0.12       0
Bank Sta=4986.3,4990.3
Exp/Cntr=0.3,0.1

Type RM Length L Ch R = 1,2151,424,424,424
BEGIN DESCRIPTION:
Mapping XS fa9b87aa
END DESCRIPTION:
XS GIS Cut Line= 3
      2550992.17     13565133.05      2550461.04     13565611.08
      2549813.98     13566205.02
#Sta/Elev= 30
  4320.4  170.68  4433.2  167.95  4468.3  164.79  4581.9  160.84  4588.7  159.65
  4624.5  157.85  4773.3  152.28  4836.8  148.73  4871.9  147.49  4949.7  148.00
  4957.1  146.94  4963.9  144.53  4971.3  139.43  4976.1  137.84  4976.3  137.34
  4980.1  137.84  5006.5  138.91  5020.7  141.51  5042.3  141.30  5056.5  143.29
  5063.2  145.34  5070.3  144.72  5105.8  148.61  5140.9  150.85  5219.2  152.37
  5303.7  155.80  5311.1  155.33  5317.9  156.46  5526.7  161.15  5913.3  171.08
#Mann=4,-1,0
  4320.4    0.12       0  4976.1    0.05       0  4980.1    0.12       0
  5526.7    0.04       0
Bank Sta=4976.1,4980.1
Exp/Cntr=0.3,0.1

Type RM Length L Ch R = 1,1727,383,383,383
BEGIN DESCRIPTION:
Mapping XS 78198c74
END DESCRIPTION:
XS GIS Cut Line= 3
      2550731.43     13564833.65      2550190.63     13565306.86
      2549355.25     13565789.73
#Sta/Elev= 30
  4256.7  174.47  4315.1  172.32  4433.9  169.01  4449.1  168.47  4579.0  165.51
  4583.1  165.33  4743.7  160.87  4814.9  146.11  4900.3  144.35  4935.4  146.03
  4949.6  143.90  4970.1  138.22  4975.3  138.22  4978.8  136.51  4993.4  134.53
  5000.3  134.89  5014.1  132.04  5014.4  131.54  5018.1  132.04  5028.0  134.39
  5051.1  137.09  5080.7  145.30  5108.9  147.97  5401.1  150.47  5445.5  150.21
  5548.0  151.55  5776.8  153.73  5791.9  154.07  5907.3  155.21  5940.2  155.16
#Mann=14,-1,0
  4256.7   0.013       0  4315.1    0.05       0  4433.9   0.013       0
  4449.1    0.05       0  4579.0   0.013       0  4583.1    0.12       0
  5014.1    0.05       0  5018.1    0.12       0  5401.1   0.013       0
  5445.5    0.12       0  5548.0    0.05       0  5776.8    0.12       0
  5791.9    0.05       0  5907.3    0.12       0
Bank Sta=5014.1,5018.1
Exp/Cntr=0.3,0.1

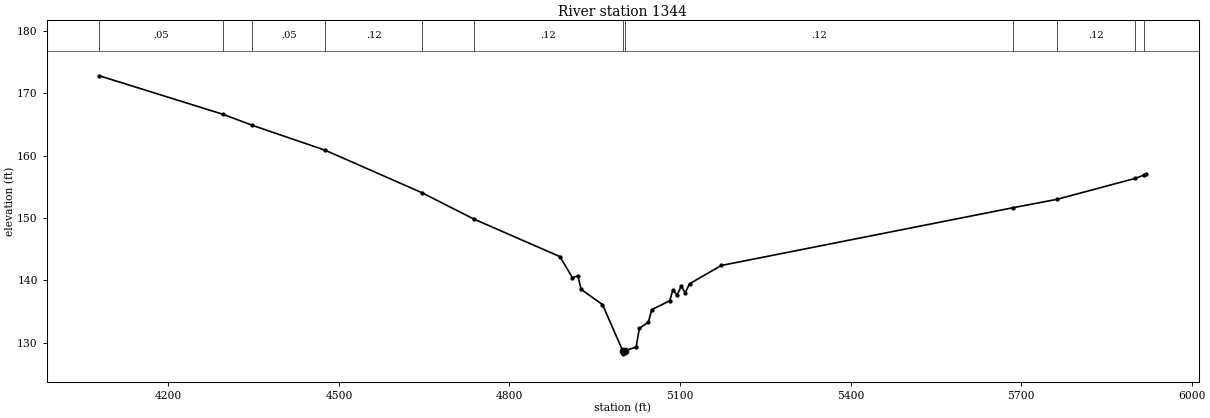
Type RM Length L Ch R = 1,1344,0,0,0
BEGIN DESCRIPTION:
Mapping XS 0f1c53a7
END DESCRIPTION:
XS GIS Cut Line= 3
      2550649.38     13564693.59      2549770.52     13565190.97
      2549229.82     13565823.39
#Sta/Elev= 30
  4078.5  172.78  4296.0  166.61  4347.5  164.85  4476.0  160.85  4645.8  154.06
  4737.2  149.84  4888.5  143.83  4910.8  140.44  4920.3  140.77  4926.0  138.58
  4963.6  136.14  4999.1  128.75  4999.3  128.25  5003.1  128.75  5022.7  129.33
  5028.5  132.33  5044.4  133.34  5050.1  135.32  5081.9  136.75  5087.4  138.48
  5094.7  137.65  5102.4  139.12  5109.0  137.98  5116.7  139.47  5172.6  142.40
  5686.2  151.66  5762.5  152.98  5901.1  156.36  5916.4  156.89  5920.4  157.11
#Mann=12,-1,0
  4078.5    0.05       0  4296.0    0.12       0  4347.5    0.05       0
  4476.0    0.12       0  4645.8    0.05       0  4737.2    0.12       0
  4999.1    0.05       0  5003.1    0.12       0  5686.2    0.05       0
  5762.5    0.12       0  5901.1    0.05       0  5916.4    0.12       0
Bank Sta=4999.1,5003.1
Exp/Cntr=0.3,0.1

Chan Stop Cuts=-1