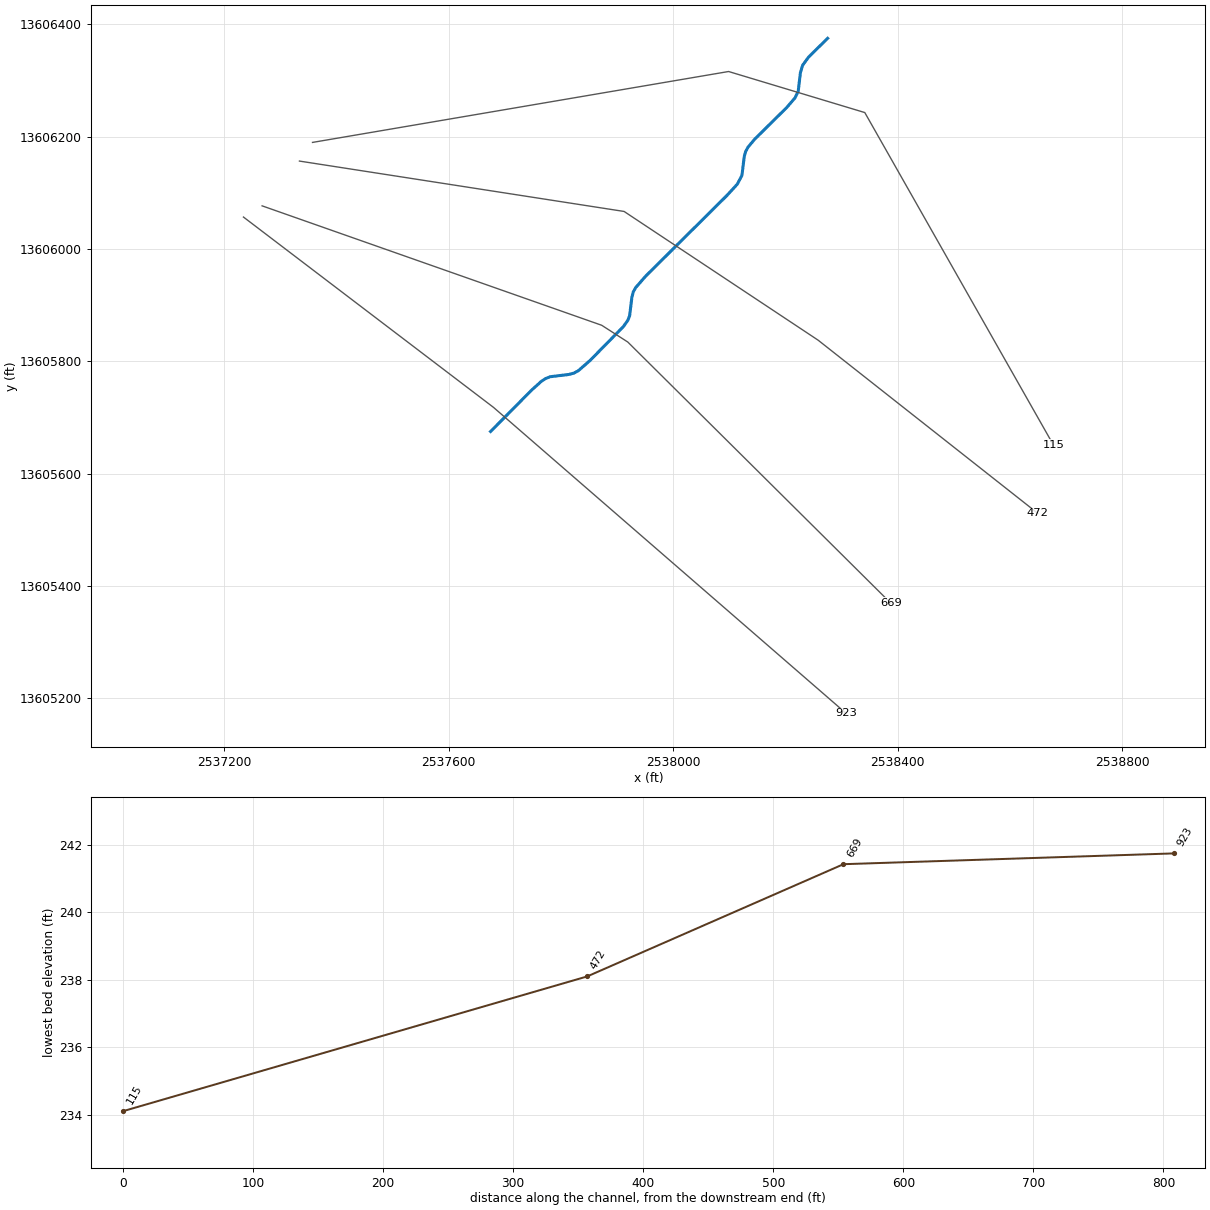
--- TRIB 13_1 TO IRISH CREEK.prj (project) ---

Proj Title=TRIB 13_1 TO IRISH CREEK Base Level Engineering
Current Plan=p01
Default Exp/Contr=0.3,0.1
English Units
Geom File=g01
Flow File=f01
Plan File=p01
Y Axis Title=Elevation
X Axis Title(PF)=Main Channel Distance
X Axis Title(XS)=Station
BEGIN DESCRIPTION:
TRIB 13_1 TO IRISH CREEK
END DESCRIPTION:
DSS Export Rating Curves= 0
DSS Export Rating Curve Sorted= 0
DSS Export Volume Flow Curves= 0
DXF OffsetX= 0
DXF OffsetY= 0
DXF ScaleX= 1
DXF ScaleY= 10

--- TRIB 13_1 TO IRISH CREEK.p01 (plan) ---

Plan Title=Multiple Run
Short Identifier=Multiple
Geom File=g01
Flow File=f01
Subcritical Flow
K Sum by GR= 0
Std Step Tol= 0.01
Critical Tol= 0.01
Num of Std Step Trials= 20
Max Error Tol= 0.3
Flow Tol Ratio= 0.001
Split Flow NTrial= 30
Split Flow Tol= 0.02
Split Flow Ratio= 0.02
Log Output Level= 0
Friction Slope Method= 1
Unsteady Friction Slope Method= 2
Unsteady Bridges Friction Slope Method= 1
Parabolic Critical Depth
Global Vel Dist=  1 , 1 , 1
Global Log Level= 0
CheckData=True
Encroach Param= -1, 0, 0, 0
BEGIN DESCRIPTION:
Multiple Run
END DESCRIPTION:

--- TRIB 13_1 TO IRISH CREEK.f01 (steady flow) ---

Flow Title=Multiple
Number of Profiles=7
Profile Names=10-year,25-year,50-year,1pct_min,100-year,1pct_plu,500-year
River Rch & RM= TRIB 13_1 TO IRI,Reach-1,923
     435     685     907     584    1165    2325    1898
Boundary for River Rch & Prof#=TRIB 13_1 TO IRI,Reach-1,1
Up Type=0
Dn Type=3
Dn Slope=0.005
Boundary for River Rch & Prof#=TRIB 13_1 TO IRI,Reach-1,2
Up Type=0
Dn Type=3
Dn Slope=0.005
Boundary for River Rch & Prof#=TRIB 13_1 TO IRI,Reach-1,3
Up Type=0
Dn Type=3
Dn Slope=0.005
Boundary for River Rch & Prof#=TRIB 13_1 TO IRI,Reach-1,4
Up Type=0
Dn Type=3
Dn Slope=0.005
Boundary for River Rch & Prof#=TRIB 13_1 TO IRI,Reach-1,5
Up Type=0
Dn Type=3
Dn Slope=0.005
Boundary for River Rch & Prof#=TRIB 13_1 TO IRI,Reach-1,6
Up Type=0
Dn Type=3
Dn Slope=0.005
Boundary for River Rch & Prof#=TRIB 13_1 TO IRI,Reach-1,7
Up Type=0
Dn Type=3
Dn Slope=0.005

--- TRIB 13_1 TO IRISH CREEK.g01 (geometry) ---

Geom Title=Existing Conditions

River Reach=TRIB 13_1 TO IRI,Reach-1
Reach XY= 30
      2537675.00     13605675.00      2537748.14     13605748.80
      2537765.30     13605764.28      2537772.70     13605769.18
      2537781.05     13605772.48      2537814.37     13605776.53
      2537823.37     13605778.96      2537831.07     13605783.14
      2537851.88     13605801.27      2537911.38     13605861.76
      2537919.15     13605872.70      2537922.47     13605881.04
      2537926.55     13605914.36      2537928.98     13605923.35
      2537933.16     13605931.05      2537951.30     13605951.82
      2538095.38     13606094.84      2538114.22     13606115.32
      2538122.47     13606131.05      2538126.55     13606164.36
      2538128.99     13606173.35      2538133.18     13606181.04
      2538144.83     13606195.07      2538201.95     13606251.55
      2538216.93     13606268.92      2538222.65     13606280.97
      2538226.65     13606314.32      2538230.70     13606327.35
      2538241.42     13606341.92      2538275.00     13606375.00

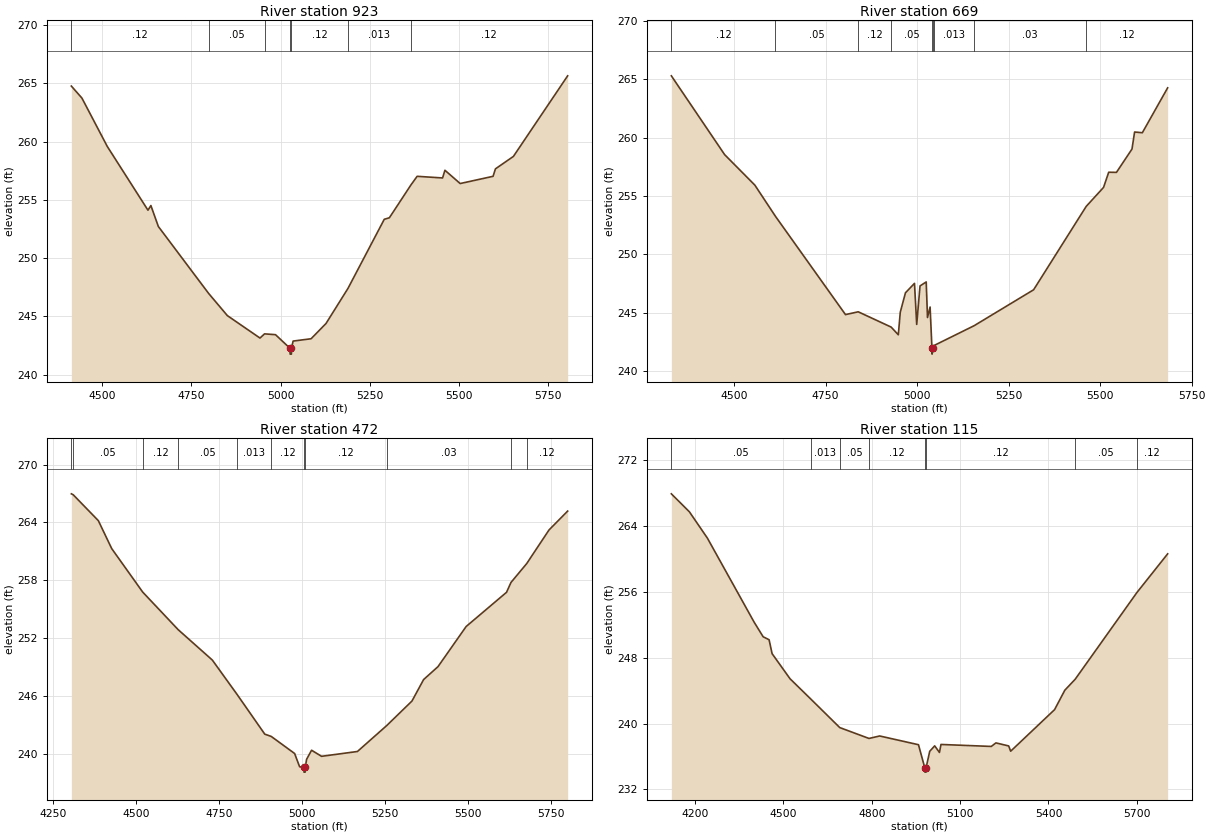
Type RM Length L Ch R = 1,923,254,254,254
BEGIN DESCRIPTION:
LGII4229
END DESCRIPTION:
XS GIS Cut Line= 3
      2537234.92     13606056.80      2537680.09     13605717.94
      2538307.99     13605173.09
#Sta/Elev= 30
  4413.8  264.77  4443.4  263.74  4514.4  259.59  4628.5  254.11  4636.7  254.51
  4657.6  252.71  4798.3  246.97  4850.9  245.06  4942.4  243.13  4955.2  243.49
  4985.9  243.42  5026.6  242.25  5026.9  241.75  5030.4  241.75  5030.6  242.25
  5035.2  242.87  5085.6  243.07  5127.4  244.38  5188.9  247.39  5290.7  253.33
  5305.0  253.46  5365.2  256.27  5382.8  257.02  5454.1  256.88  5460.7  257.54
  5503.4  256.40  5595.6  257.02  5602.2  257.66  5652.6  258.73  5804.6  265.65
#Mann=7,-1,0
  4413.8    0.12       0  4798.3    0.05       0  4955.2    0.12       0
  5026.6    0.05       0  5030.6    0.12       0  5188.9   0.013       0
  5365.2    0.12       0
Bank Sta=5026.6,5030.6
Exp/Cntr=0.3,0.1

Type RM Length L Ch R = 1,669,197,197,197
BEGIN DESCRIPTION:
LGII4228
END DESCRIPTION:
XS GIS Cut Line= 4
      2537268.13     13606076.74      2537872.78     13605864.11
      2537919.29     13605834.21      2538387.25     13605369.57
#Sta/Elev= 30
  4328.7  265.30  4474.3  258.54  4556.7  255.93  4613.1  253.25  4804.4  244.82
  4839.2  245.06  4929.1  243.75  4948.7  243.09  4954.0  245.02  4968.2  246.69
  4992.9  247.50  4998.9  243.98  5008.0  247.28  5024.9  247.62  5028.4  244.57
  5035.5  245.47  5040.6  241.93  5040.8  241.43  5044.6  241.93  5046.4  242.17
  5155.9  243.87  5318.3  246.95  5461.9  254.10  5509.3  255.73  5523.4  257.03
  5544.6  257.02  5587.0  259.02  5594.1  260.48  5615.3  260.42  5684.4  264.27
#Mann=9,-1,0
  4328.7    0.12       0  4613.1    0.05       0  4839.2    0.12       0
  4929.1    0.05       0  5040.6    0.05       0  5044.6    0.05       0
  5046.4   0.013       0  5155.9    0.03       0  5461.9    0.12       0
Bank Sta=5040.6,5044.6
Exp/Cntr=0.3,0.1

Type RM Length L Ch R = 1,472,357,357,357
BEGIN DESCRIPTION:
LGII4227
END DESCRIPTION:
XS GIS Cut Line= 4
      2537334.60     13606156.46      2537912.64     13606066.77
      2538258.15     13605837.54      2538649.20     13605529.33
#Sta/Elev= 30
  4303.9  266.96  4309.6  266.86  4385.3  264.18  4425.7  261.28  4519.2  256.77
  4626.0  252.88  4729.3  249.72  4804.1  246.15  4887.5  242.04  4907.1  241.80
  4977.6  240.03  4992.6  238.66  5005.7  238.60  5005.9  238.10  5009.4  238.10
  5009.7  238.60  5013.7  239.43  5028.7  240.37  5058.8  239.74  5167.1  240.24
  5255.5  242.93  5331.6  245.47  5366.8  247.70  5410.2  249.04  5495.1  253.20
  5617.0  256.75  5630.4  257.77  5677.7  259.72  5745.1  263.21  5801.4  265.17
#Mann=11,-1,0
  4303.9    0.12       0  4309.6    0.05       0  4519.2    0.12       0
  4626.0    0.05       0  4804.1   0.013       0  4907.1    0.12       0
  5005.7    0.05       0  5009.7    0.12       0  5255.5    0.03       0
  5630.4    0.05       0  5677.7    0.12       0
Bank Sta=5005.7,5009.7
Exp/Cntr=0.3,0.1

Type RM Length L Ch R = 1,115,0,0,0
BEGIN DESCRIPTION:
LGII4226
END DESCRIPTION:
XS GIS Cut Line= 4
      2537357.87     13606189.69      2538098.69     13606315.93
      2538341.21     13606242.84      2538676.75     13605651.49
#Sta/Elev= 30
  4119.8  267.90  4181.2  265.71  4242.2  262.52  4400.9  252.31  4431.4  250.54
  4451.6  250.18  4461.8  248.49  4522.7  245.44  4592.2  243.01  4691.5  239.51
  4790.8  238.19  4827.0  238.49  4958.7  237.43  4980.3  234.60  4980.6  234.10
  4984.1  234.10  4984.3  234.60  4996.9  236.63  5013.7  237.29  5029.9  236.49
  5035.1  237.46  5205.8  237.22  5221.6  237.65  5264.9  237.28  5271.6  236.64
  5420.7  241.69  5455.5  244.05  5490.6  245.38  5700.3  255.92  5804.5  260.61
#Mann=8,-1,0
  4119.8    0.05       0  4592.2   0.013       0  4691.5    0.05       0
  4790.8    0.12       0  4980.3    0.05       0  4984.3    0.12       0
  5490.6    0.05       0  5700.3    0.12       0
Bank Sta=4980.3,4984.3
Exp/Cntr=0.3,0.1

Chan Stop Cuts=-1