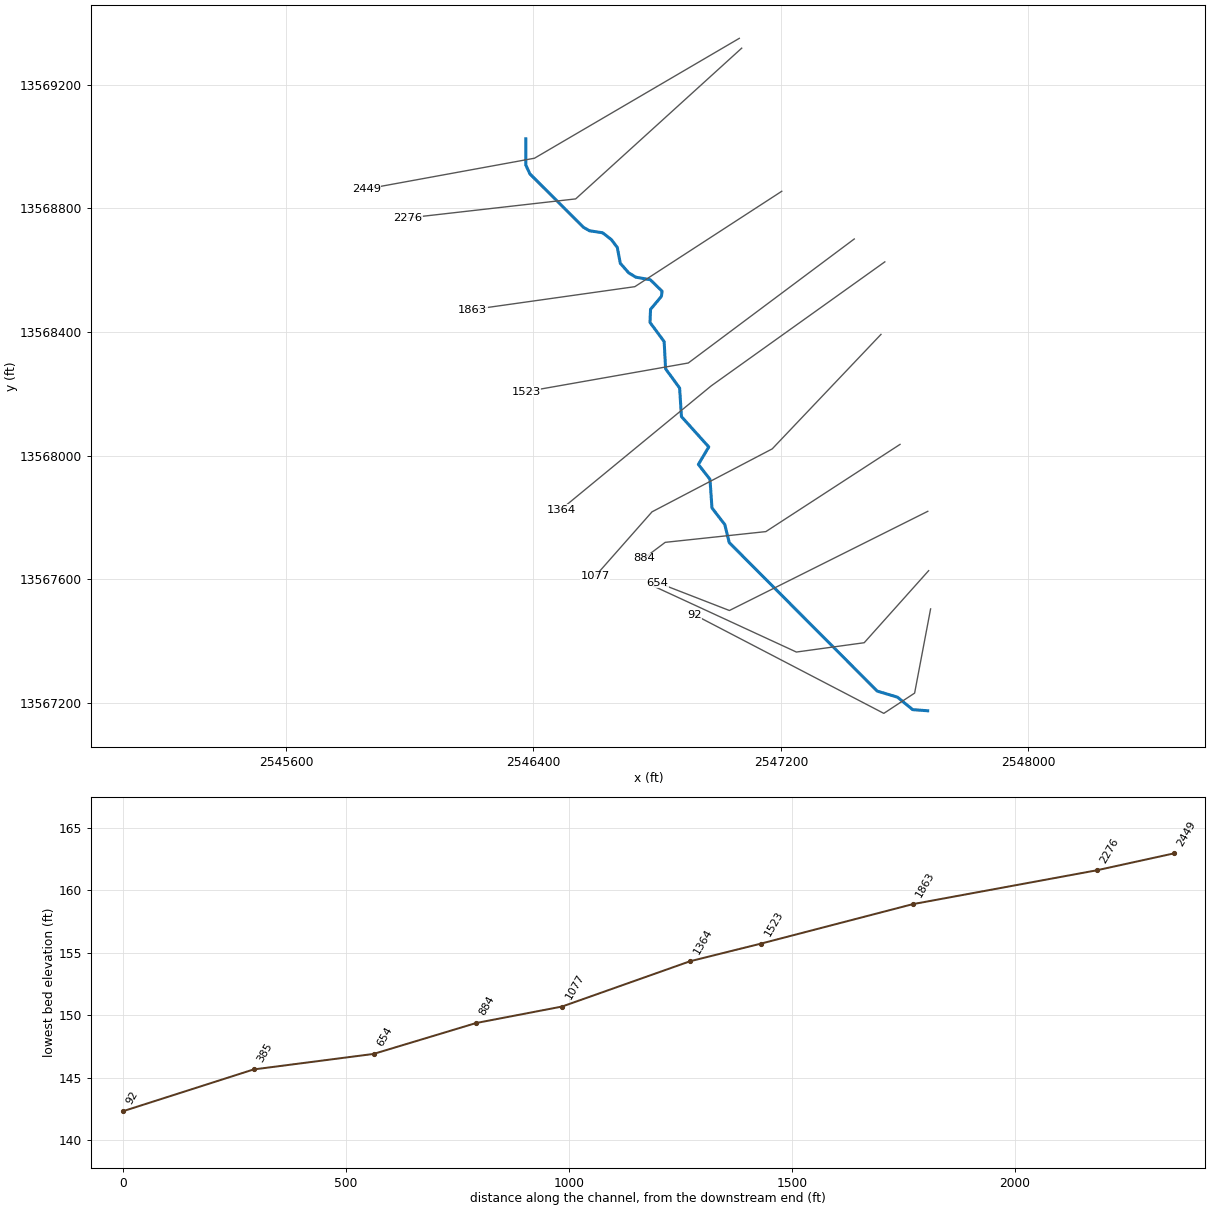
--- TRIB 13_2 TO GUADALUPE RIVER.prj (project) ---

Proj Title=TRIB 13_2 TO GUADALUPE RIVER Base Level Engineering
Current Plan=p01
Default Exp/Contr=0.3,0.1
English Units
Geom File=g01
Flow File=f01
Plan File=p01
Y Axis Title=Elevation
X Axis Title(PF)=Main Channel Distance
X Axis Title(XS)=Station
BEGIN DESCRIPTION:
TRIB 13_2 TO GUADALUPE RIVER
END DESCRIPTION:
DSS Export Rating Curves= 0
DSS Export Rating Curve Sorted= 0
DSS Export Volume Flow Curves= 0
DXF OffsetX= 0
DXF OffsetY= 0
DXF ScaleX= 1
DXF ScaleY= 10

--- TRIB 13_2 TO GUADALUPE RIVER.p01 (plan) ---

Plan Title=Multiple Run
Short Identifier=Multiple
Geom File=g01
Flow File=f01
Subcritical Flow
K Sum by GR= 0
Std Step Tol= 0.01
Critical Tol= 0.01
Num of Std Step Trials= 20
Max Error Tol= 0.3
Flow Tol Ratio= 0.001
Split Flow NTrial= 30
Split Flow Tol= 0.02
Split Flow Ratio= 0.02
Log Output Level= 0
Friction Slope Method= 1
Unsteady Friction Slope Method= 2
Unsteady Bridges Friction Slope Method= 1
Parabolic Critical Depth
Global Vel Dist=  1 , 1 , 1
Global Log Level= 0
CheckData=True
Encroach Param= -1, 0, 0, 0
BEGIN DESCRIPTION:
Multiple Run
END DESCRIPTION:

--- TRIB 13_2 TO GUADALUPE RIVER.f01 (steady flow) ---

Flow Title=Multiple
Number of Profiles=7
Profile Names=10-year,25-year,50-year,1pct_min,100-year,1pct_plu,500-year
River Rch & RM= TRIB 13_2 TO GUA,Reach-1,2449
     419     653     858     547    1092    2178    1746
Boundary for River Rch & Prof#=TRIB 13_2 TO GUA,Reach-1,1
Up Type=0
Dn Type=3
Dn Slope=0.005
Boundary for River Rch & Prof#=TRIB 13_2 TO GUA,Reach-1,2
Up Type=0
Dn Type=3
Dn Slope=0.005
Boundary for River Rch & Prof#=TRIB 13_2 TO GUA,Reach-1,3
Up Type=0
Dn Type=3
Dn Slope=0.005
Boundary for River Rch & Prof#=TRIB 13_2 TO GUA,Reach-1,4
Up Type=0
Dn Type=3
Dn Slope=0.005
Boundary for River Rch & Prof#=TRIB 13_2 TO GUA,Reach-1,5
Up Type=0
Dn Type=3
Dn Slope=0.005
Boundary for River Rch & Prof#=TRIB 13_2 TO GUA,Reach-1,6
Up Type=0
Dn Type=3
Dn Slope=0.005
Boundary for River Rch & Prof#=TRIB 13_2 TO GUA,Reach-1,7
Up Type=0
Dn Type=3
Dn Slope=0.005

--- TRIB 13_2 TO GUADALUPE RIVER.g01 (geometry) ---

Geom Title=Existing Conditions

River Reach=TRIB 13_2 TO GUA,Reach-1
Reach XY= 30
      2546375.00     13569025.00      2546375.12     13568940.05
      2546388.35     13568911.67      2546561.80     13568738.64
      2546581.09     13568727.55      2546623.57     13568721.11
      2546652.14     13568698.83      2546671.10     13568673.54
      2546680.77     13568622.49      2546707.97     13568591.50
      2546730.95     13568577.46      2546777.82     13568569.14
      2546815.97     13568532.01      2546813.67     13568515.26
      2546778.62     13568473.38      2546776.86     13568431.14
      2546822.62     13568369.03      2546827.35     13568280.97
      2546872.64     13568219.02      2546878.64     13568126.50
      2546966.99     13568028.33      2546933.29     13567971.78
      2546970.92     13567923.50      2546977.33     13567830.97
      2547018.86     13567777.17      2547033.14     13567718.94
      2547511.78     13567238.61      2547577.24     13567219.03
      2547626.49     13567178.60      2547675.00     13567175.00

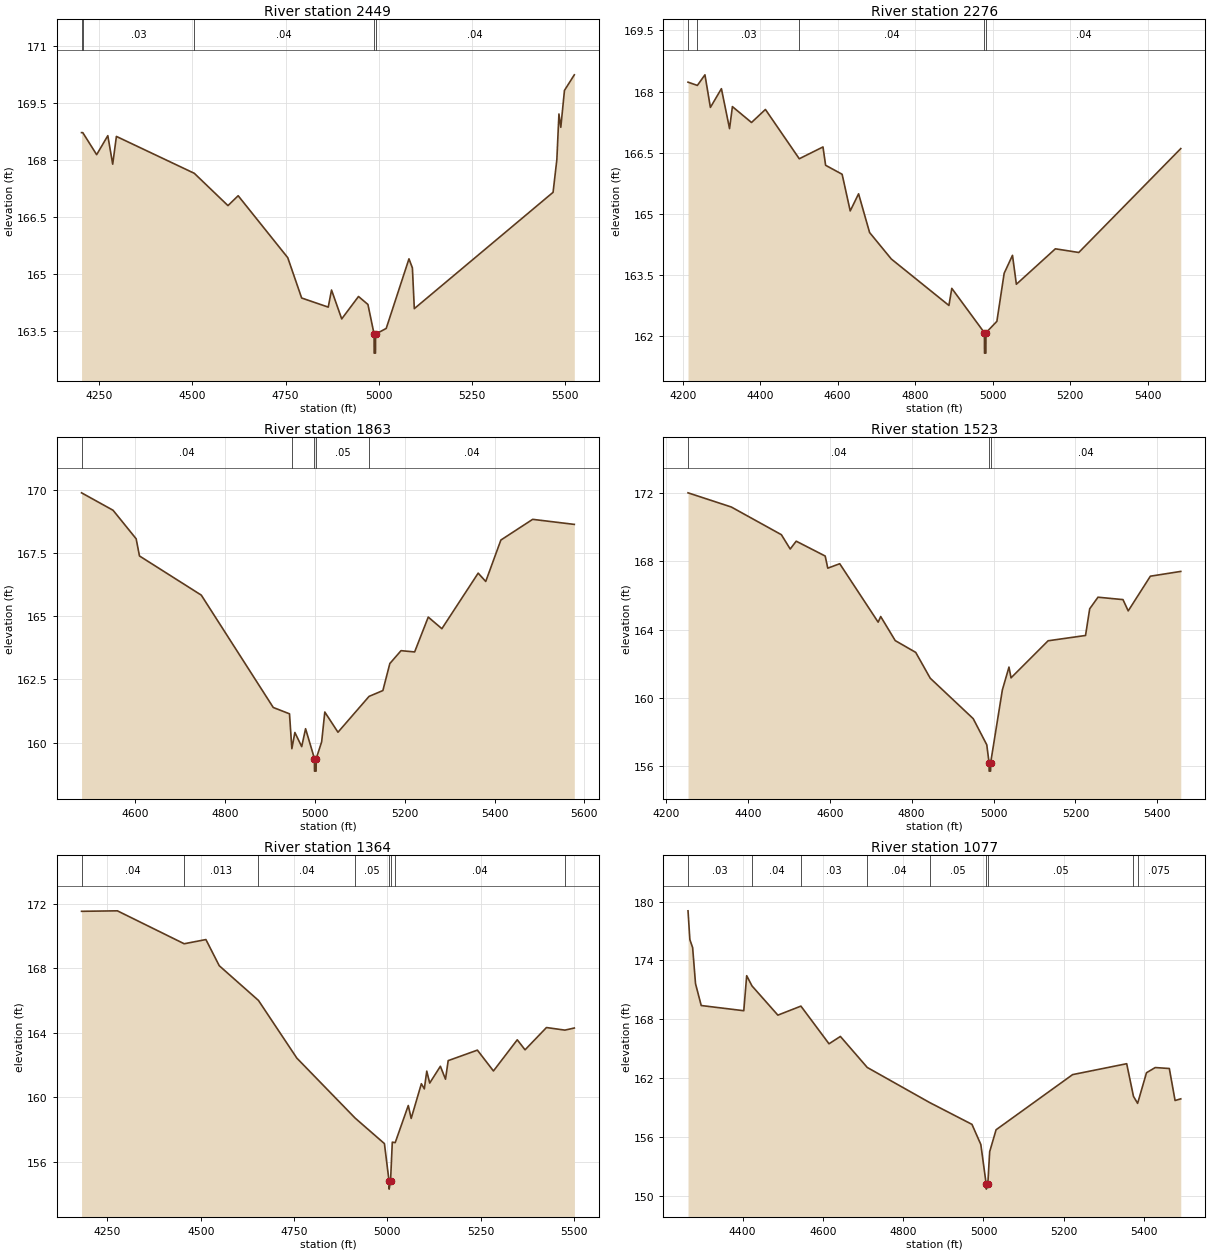
Type RM Length L Ch R = 1,2449,173,173,173
BEGIN DESCRIPTION:
TRIB 13 TO GUADALUPE RIVER 14.0
END DESCRIPTION:
XS GIS Cut Line= 3
      2547065.74     13569350.00      2546403.14     13568962.19
      2545859.01     13568862.66
#Sta/Elev= 30
  4202.9  168.73  4206.2  168.73  4243.4  168.15  4273.3  168.65  4286.4  167.90
  4296.3  168.63  4505.1  167.66  4595.4  166.81  4622.7  167.07  4755.7  165.44
  4792.9  164.38  4864.2  164.14  4873.0  164.59  4900.3  163.83  4945.3  164.42
  4970.6  164.21  4987.1  163.43  4987.3  162.93  4990.8  162.93  4991.1  163.43
  5019.6  163.58  5080.6  165.41  5089.8  165.17  5094.9  164.10  5466.9  167.16
  5477.0  168.02  5482.6  169.22  5487.6  168.87  5497.4  169.84  5523.8  170.25
#Mann=5,-1,0
  4202.9    0.04       0  4206.2    0.03       0  4505.1    0.04       0
  4987.1    0.04       0  4991.1    0.04       0
Bank Sta=4987.1,4991.1
Exp/Cntr=0.3,0.1

Type RM Length L Ch R = 1,2276,413,413,413
BEGIN DESCRIPTION:
Mapping XS 655c9ffa
END DESCRIPTION:
XS GIS Cut Line= 3
      2547073.49     13569318.28      2546536.49     13568830.66
      2545993.35     13568768.94
#Sta/Elev= 30
  4213.9  168.23  4238.0  168.15  4257.6  168.41  4271.7  167.61  4300.1  168.07
  4321.1  167.09  4328.5  167.63  4377.8  167.24  4413.7  167.56  4501.1  166.35
  4562.3  166.64  4569.1  166.19  4611.7  165.97  4632.6  165.07  4654.2  165.49
  4682.6  164.54  4738.7  163.89  4887.4  162.75  4894.8  163.17  4979.0  162.08
  4979.3  161.58  4982.8  161.58  4983.0  162.08  5011.2  162.36  5030.0  163.54
  5051.5  163.98  5061.5  163.27  5162.2  164.14  5222.6  164.05  5485.9  166.60
#Mann=5,-1,0
  4213.9    0.04       0  4238.0    0.03       0  4501.1    0.04       0
  4979.0    0.04       0  4983.0    0.04       0
Bank Sta=4979,4983
Exp/Cntr=0.3,0.1

Type RM Length L Ch R = 1,1863,340,340,340
BEGIN DESCRIPTION:
Mapping XS b622f480
END DESCRIPTION:
XS GIS Cut Line= 3
      2547203.09     13568855.35      2546727.83     13568546.74
      2546203.20     13568472.67
#Sta/Elev= 30
  4481.1  169.89  4551.2  169.20  4602.6  168.07  4610.0  167.39  4747.5  165.84
  4907.7  161.39  4943.8  161.14  4949.1  159.76  4955.8  160.40  4971.0  159.84
  4979.6  160.55  4999.3  159.37  4999.5  158.87  5003.0  158.87  5003.3  159.37
  5015.4  160.03  5022.4  161.21  5051.7  160.41  5120.9  161.83  5151.6  162.06
  5167.1  163.13  5192.0  163.64  5222.3  163.59  5252.6  164.97  5282.9  164.51
  5363.7  166.71  5380.5  166.38  5414.2  168.02  5484.9  168.84  5577.6  168.64
#Mann=5,-1,0
  4481.1    0.04       0  4949.1    0.05       0  4999.3    0.05       0
  5003.3    0.05       0  5120.9    0.04       0
Bank Sta=4999.3,5003.3
Exp/Cntr=0.3,0.1

Type RM Length L Ch R = 1,1523,159,159,159
BEGIN DESCRIPTION:
Mapping XS 8e8f750d
END DESCRIPTION:
XS GIS Cut Line= 3
      2547437.60     13568701.02      2546900.65     13568299.85
      2546376.02     13568207.27
#Sta/Elev= 30
  4254.1  172.01  4359.8  171.18  4482.0  169.56  4503.6  168.72  4518.2  169.18
  4589.0  168.31  4595.3  167.60  4624.5  167.86  4718.3  164.44  4724.5  164.77
  4760.0  163.36  4810.0  162.67  4845.4  161.16  4950.4  158.79  4983.5  157.26
  4989.0  156.22  4989.3  155.72  4992.8  155.72  4993.0  156.22  5021.5  160.47
  5037.7  161.81  5042.7  161.18  5133.2  163.35  5224.6  163.66  5234.7  165.22
  5255.0  165.90  5316.0  165.76  5328.8  165.10  5382.9  167.13  5457.1  167.41
#Mann=3,-1,0
  4254.1    0.04       0  4989.0    0.04       0  4993.0    0.04       0
Bank Sta=4989,4993
Exp/Cntr=0.3,0.1

Type RM Length L Ch R = 1,1364,287,287,287
BEGIN DESCRIPTION:
Mapping XS 6a29c6fc
END DESCRIPTION:
XS GIS Cut Line= 3
      2547536.41     13568626.99      2546974.72     13568225.78
      2546488.58     13567825.79
#Sta/Elev= 30
  4180.9  171.52  4276.9  171.55  4455.8  169.51  4514.0  169.77  4549.7  168.15
  4654.7  166.00  4757.4  162.43  4913.7  158.71  4992.1  157.13  5004.5  154.81
  5004.7  154.31  5008.5  154.81  5013.2  157.22  5021.0  157.19  5056.0  159.49
  5063.8  158.69  5091.1  160.84  5099.0  160.52  5105.5  161.62  5113.4  160.88
  5142.0  161.92  5155.7  161.12  5162.9  162.27  5241.1  162.92  5284.1  161.63
  5347.9  163.56  5368.8  162.94  5426.1  164.32  5475.5  164.16  5500.7  164.29
#Mann=8,-1,0
  4180.9    0.04       0  4455.8   0.013       0  4654.7    0.04       0
  4913.7    0.05       0  5004.5    0.05       0  5008.5    0.05       0
  5021.0    0.04       0  5475.5   0.013       0
Bank Sta=5004.5,5008.5
Exp/Cntr=0.3,0.1

Type RM Length L Ch R = 1,1077,193,193,193
BEGIN DESCRIPTION:
Mapping XS 03ee743b
END DESCRIPTION:
XS GIS Cut Line= 4
      2547524.02     13568392.40      2547172.23     13568022.10
      2546783.38     13567818.42      2546599.73     13567610.28
#Sta/Elev= 30
  4264.1  179.05  4268.7  176.12  4275.6  175.30  4282.8  171.62  4297.0  169.40
  4403.0  168.87  4410.2  172.44  4423.4  171.40  4487.9  168.42  4545.3  169.34
  4615.3  165.50  4643.6  166.25  4710.5  163.09  4865.6  159.52  4971.3  157.29
  4993.4  155.24  5006.8  151.19  5007.1  150.69  5010.8  151.19  5015.4  154.50
  5031.4  156.74  5222.0  162.36  5356.7  163.47  5373.6  160.14  5383.9  159.43
  5406.0  162.55  5427.8  163.08  5462.9  162.98  5477.2  159.72  5491.4  159.89
#Mann=9,-1,0
  4264.1    0.03       0  4423.4    0.04       0  4545.3    0.03       0
  4710.5    0.04       0  4865.6    0.05       0  5006.8    0.05       0
  5010.8    0.05       0  5373.6   0.013       0  5383.9   0.075       0
Bank Sta=5006.8,5010.8
Exp/Cntr=0.3,0.1

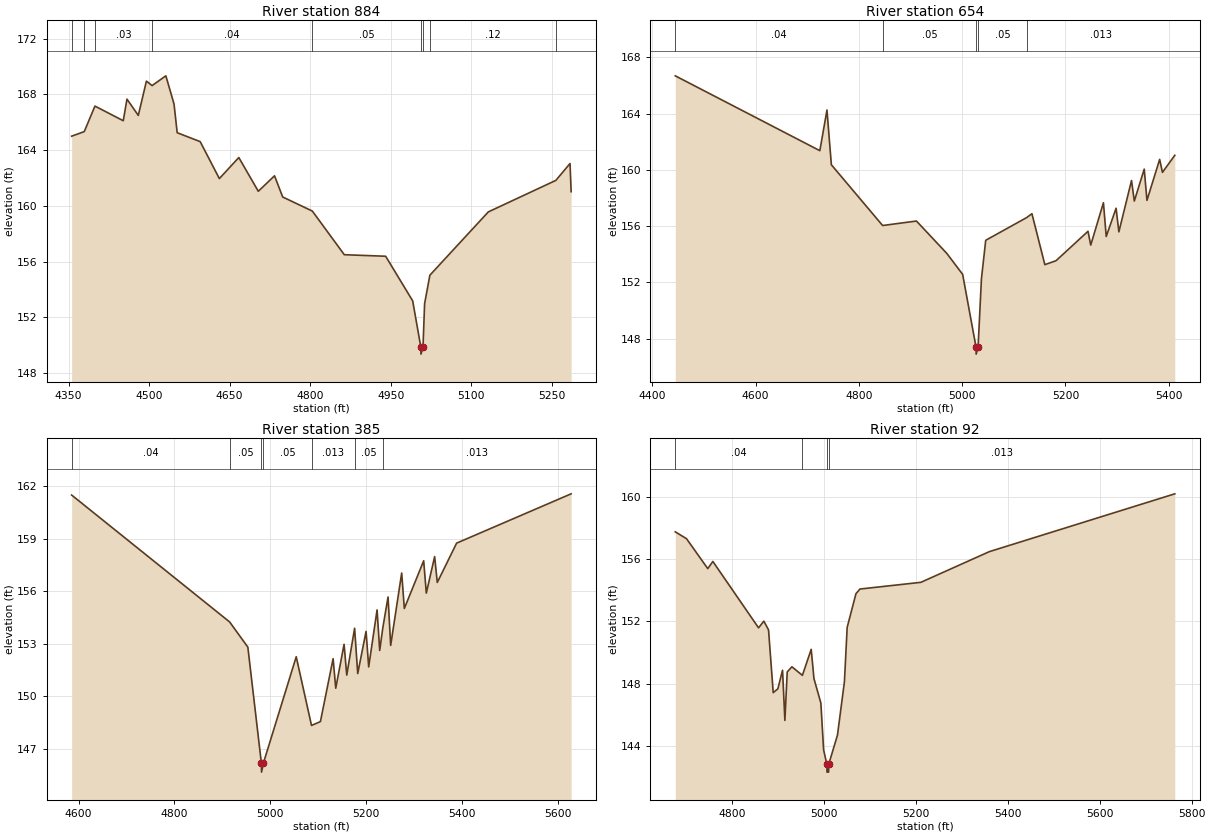
Type RM Length L Ch R = 1,884,230,230,230
BEGIN DESCRIPTION:
Mapping XS 24aef3fd
END DESCRIPTION:
XS GIS Cut Line= 4
      2547585.60     13568036.58      2547151.61     13567754.49
      2546826.09     13567719.77      2546758.15     13567668.81
#Sta/Elev= 30
  4355.8  165.00  4379.3  165.33  4399.2  167.16  4451.9  166.11  4458.8  167.66
  4479.9  166.49  4495.0  168.95  4505.6  168.63  4531.2  169.33  4546.4  167.31
  4552.3  165.25  4595.1  164.61  4630.8  161.96  4667.0  163.47  4703.3  161.05
  4733.5  162.16  4748.7  160.64  4803.9  159.63  4863.4  156.50  4940.4  156.39
  4990.7  153.19  5005.9  149.87  5006.1  149.37  5009.9  149.87  5012.9  152.99
  5022.7  155.03  5131.5  159.57  5257.2  161.83  5283.6  163.04  5285.7  161.02
#Mann=9,-1,0
  4355.8    0.03       0  4379.3    0.04       0  4399.2    0.03       0
  4505.6    0.04       0  4803.9    0.05       0  5005.9    0.05       0
  5009.9    0.05       0  5022.7    0.12       0  5257.2   0.013       0
Bank Sta=5005.9,5009.9
Exp/Cntr=0.3,0.1

Type RM Length L Ch R = 1,654,269,269,269
BEGIN DESCRIPTION:
LGII3595
END DESCRIPTION:
XS GIS Cut Line= 3
      2547675.40     13567820.13      2547033.73     13567499.29
      2546800.60     13567589.80
#Sta/Elev= 30
  4444.3  166.68  4724.3  161.36  4738.1  164.25  4746.6  160.36  4845.9  156.04
  4911.4  156.36  4970.2  154.06  5000.9  152.57  5026.8  147.40  5027.1  146.90
  5030.8  147.40  5037.3  152.26  5045.6  154.99  5125.1  156.61  5135.1  156.88
  5160.1  153.26  5181.8  153.54  5243.7  155.63  5249.0  154.65  5273.6  157.66
  5279.0  155.26  5298.1  157.27  5303.5  155.59  5328.0  159.24  5333.4  157.78
  5352.6  160.05  5357.9  157.83  5382.5  160.74  5387.9  159.82  5411.8  161.03
#Mann=5,-1,0
  4444.3    0.04       0  4845.9    0.05       0  5026.8    0.05       0
  5030.8    0.05       0  5125.1   0.013       0
Bank Sta=5026.8,5030.8
Exp/Cntr=0.3,0.1

Type RM Length L Ch R = 1,385,293,293,293
BEGIN DESCRIPTION:
LGII3594
END DESCRIPTION:
XS GIS Cut Line= 4
      2547678.17     13567628.17      2547469.76     13567395.08
      2547250.37     13567364.92      2546788.42     13567578.12
#Sta/Elev= 30
  4585.4  161.51  4915.3  154.25  4953.3  152.81  4981.6  146.16  4981.9  145.66
  4985.6  146.16  5054.3  152.26  5086.2  148.33  5104.8  148.55  5131.3  152.15
  5136.8  150.46  5154.2  152.97  5159.8  151.21  5176.2  153.89  5182.7  151.30
  5200.1  153.71  5205.6  151.68  5223.1  154.94  5228.6  152.62  5234.9  153.88
  5246.0  155.68  5251.5  152.91  5274.5  157.05  5280.0  155.02  5320.4  157.75
  5325.9  155.90  5343.3  157.99  5348.8  156.51  5389.2  158.76  5628.3  161.58
#Mann=7,-1,0
  4585.4    0.04       0  4915.3    0.05       0  4981.6    0.05       0
  4985.6    0.05       0  5086.2   0.013       0  5176.2    0.05       0
  5234.9   0.013       0
Bank Sta=4981.6,4985.6
Exp/Cntr=0.3,0.1

Type RM Length L Ch R = 1,92,0,0,0
BEGIN DESCRIPTION:
4820
END DESCRIPTION:
XS GIS Cut Line= 4
      2547684.49     13567504.45      2547632.80     13567232.11
      2547533.17     13567166.54      2546920.31     13567485.58
#Sta/Elev= 30
  4675.9  157.74  4700.4  157.30  4746.6  155.38  4757.7  155.84  4857.2  151.58
  4868.7  152.01  4878.9  151.45  4889.1  147.42  4899.3  147.67  4909.4  148.86
  4914.5  145.64  4919.6  148.75  4929.8  149.08  4952.6  148.53  4971.8  150.20
  4977.8  148.32  4992.8  146.76  4998.8  143.75  5005.9  142.82  5006.2  142.32
  5009.7  142.32  5009.9  142.82  5029.0  144.70  5044.1  148.12  5050.1  151.61
  5069.2  153.77  5077.9  154.07  5210.5  154.50  5359.6  156.47  5763.3  160.18
#Mann=4,-1,0
  4675.9    0.04       0  4952.6   0.013       0  5005.9    0.03       0
  5009.9   0.013       0
Bank Sta=5005.9,5009.9
Exp/Cntr=0.3,0.1

Chan Stop Cuts=-1