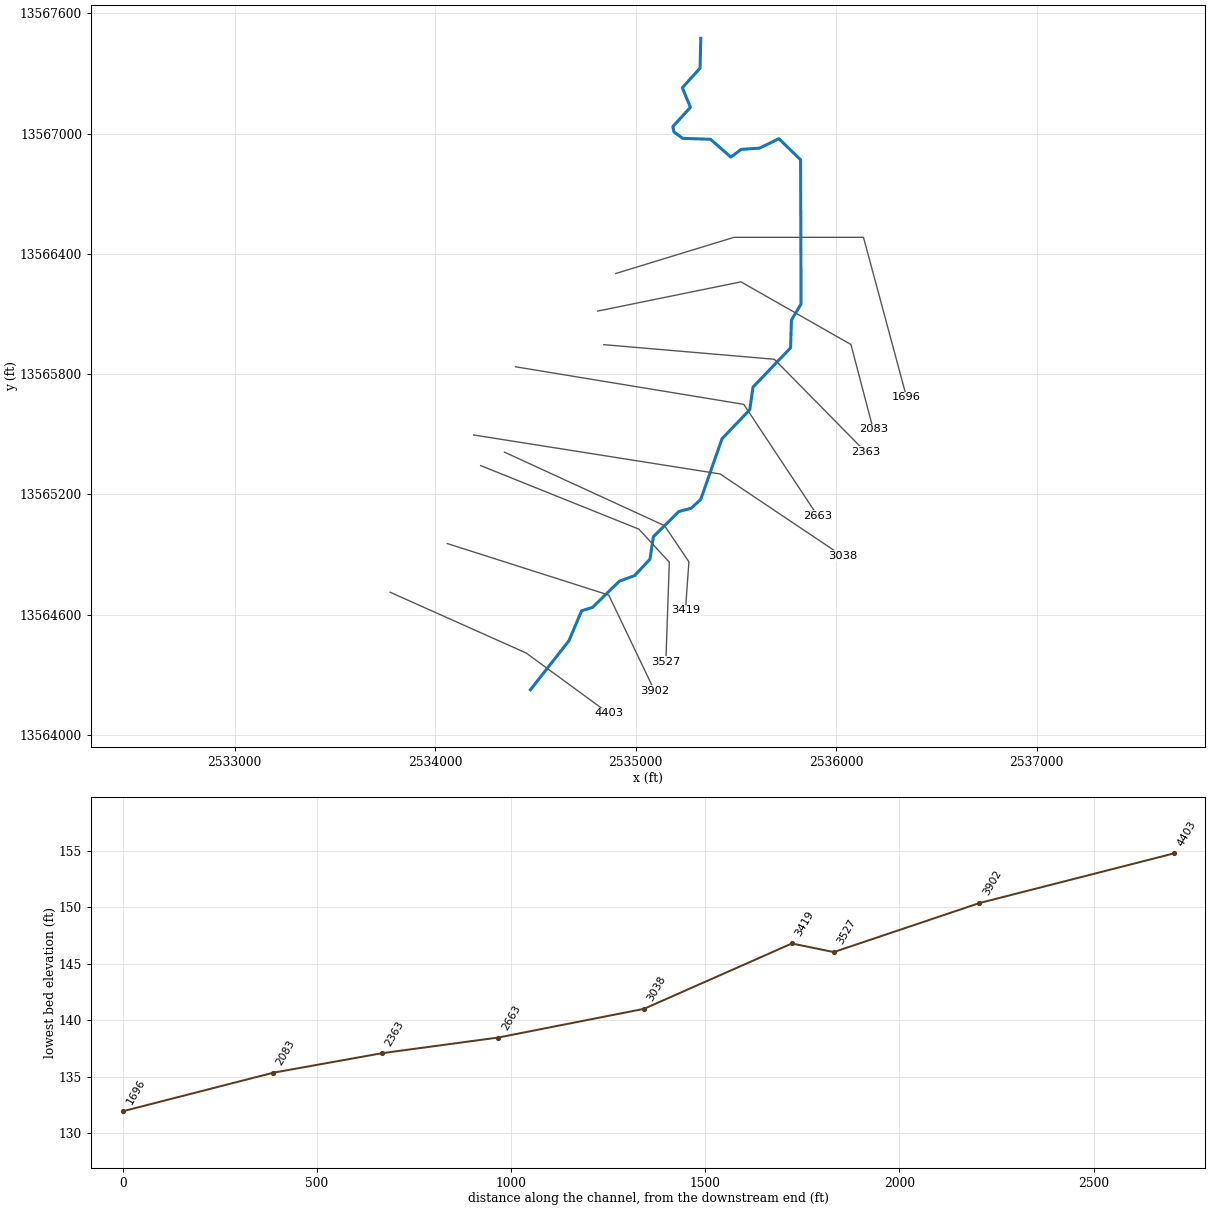
--- TRIB 14 TO GUADALUPE RIVER.prj (project) ---

Proj Title=TRIB 14 TO GUADALUPE RIVER Base Level Engineering
Current Plan=p01
Default Exp/Contr=0.3,0.1
English Units
Geom File=g01
Flow File=f01
Plan File=p01
Y Axis Title=Elevation
X Axis Title(PF)=Main Channel Distance
X Axis Title(XS)=Station
BEGIN DESCRIPTION:
TRIB 14 TO GUADALUPE RIVER
END DESCRIPTION:
DSS Export Rating Curves= 0
DSS Export Rating Curve Sorted= 0
DSS Export Volume Flow Curves= 0
DXF OffsetX= 0
DXF OffsetY= 0
DXF ScaleX= 1
DXF ScaleY= 10

--- TRIB 14 TO GUADALUPE RIVER.p01 (plan) ---

Plan Title=Multiple Run
Short Identifier=Multiple
Geom File=g01
Flow File=f01
Subcritical Flow
K Sum by GR= 0
Std Step Tol= 0.01
Critical Tol= 0.01
Num of Std Step Trials= 20
Max Error Tol= 0.3
Flow Tol Ratio= 0.001
Split Flow NTrial= 30
Split Flow Tol= 0.02
Split Flow Ratio= 0.02
Log Output Level= 0
Friction Slope Method= 1
Unsteady Friction Slope Method= 2
Unsteady Bridges Friction Slope Method= 1
Parabolic Critical Depth
Global Vel Dist=  1 , 1 , 1
Global Log Level= 0
CheckData=True
Encroach Param= -1, 0, 0, 0
BEGIN DESCRIPTION:
Multiple Run
END DESCRIPTION:

--- TRIB 14 TO GUADALUPE RIVER.f01 (steady flow) ---

Flow Title=Multiple
Number of Profiles=7
Profile Names=10-year,25-year,50-year,1pct_min,100-year,1pct_plu,500-year
River Rch & RM= TRIB 14 TO GUADA,Reach-1,4403
     460     728     965     622    1240    2474    2024
River Rch & RM= TRIB 14 TO GUADA,Reach-1,3902
     502     799    1064     687    1372    2737    2255
River Rch & RM= TRIB 14 TO GUADA,Reach-1,3038
     780    1274    1727    1134    2263    4515    3846
Boundary for River Rch & Prof#=TRIB 14 TO GUADA,Reach-1,1
Up Type=0
Dn Type=3
Dn Slope=0.005
Boundary for River Rch & Prof#=TRIB 14 TO GUADA,Reach-1,2
Up Type=0
Dn Type=3
Dn Slope=0.005
Boundary for River Rch & Prof#=TRIB 14 TO GUADA,Reach-1,3
Up Type=0
Dn Type=3
Dn Slope=0.005
Boundary for River Rch & Prof#=TRIB 14 TO GUADA,Reach-1,4
Up Type=0
Dn Type=3
Dn Slope=0.005
Boundary for River Rch & Prof#=TRIB 14 TO GUADA,Reach-1,5
Up Type=0
Dn Type=3
Dn Slope=0.005
Boundary for River Rch & Prof#=TRIB 14 TO GUADA,Reach-1,6
Up Type=0
Dn Type=3
Dn Slope=0.005
Boundary for River Rch & Prof#=TRIB 14 TO GUADA,Reach-1,7
Up Type=0
Dn Type=3
Dn Slope=0.005

--- TRIB 14 TO GUADALUPE RIVER.g01 (geometry) ---

Geom Title=Existing Conditions

River Reach=TRIB 14 TO GUADA,Reach-1
Reach XY= 30
      2534475.00     13564225.00      2534666.84     13564468.95
      2534730.59     13564619.39      2534784.41     13564635.89
      2534918.95     13564766.84      2534995.13     13564794.77
      2535071.39     13564876.49      2535088.40     13564988.30
      2535215.29     13565114.30      2535277.35     13565130.71
      2535325.00     13565175.00      2535430.83     13565477.30
      2535569.48     13565622.57      2535585.52     13565734.79
      2535772.93     13565930.86      2535777.27     13566069.06
      2535825.20     13566149.92      2535822.95     13566869.16
      2535714.39     13566974.41      2535619.03     13566927.38
      2535526.50     13566920.90      2535474.90     13566882.33
      2535373.53     13566971.43      2535235.10     13566976.06
      2535191.00     13567007.87      2535185.92     13567034.85
      2535273.32     13567131.05      2535232.83     13567228.40
      2535321.48     13567326.45      2535325.00     13567475.00

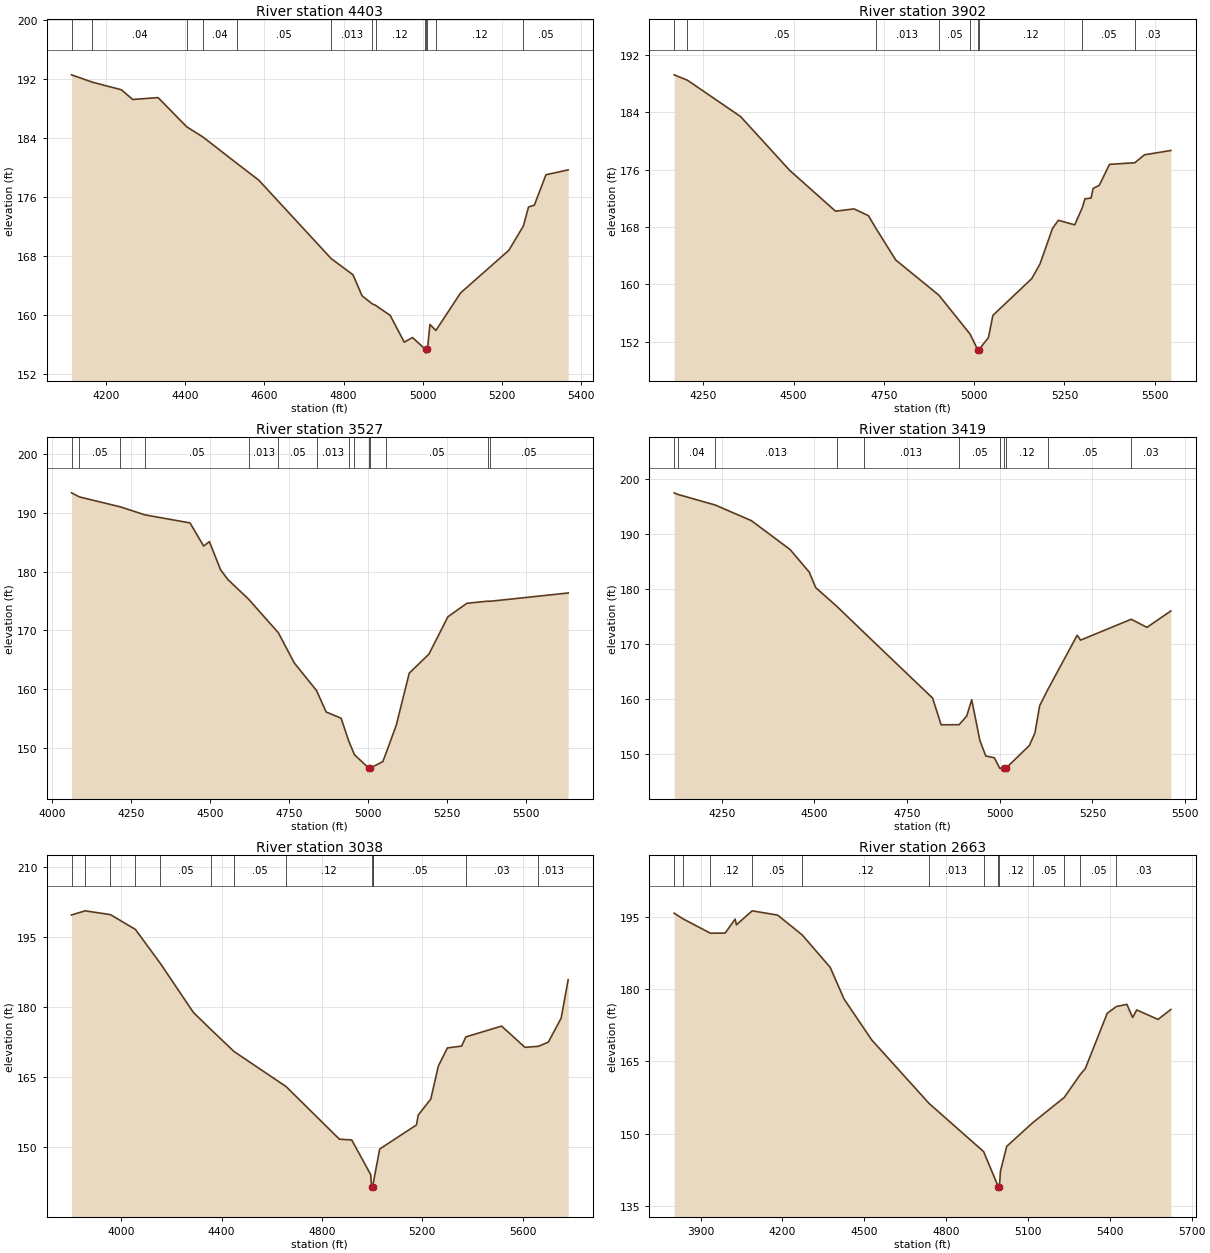
Type RM Length L Ch R = 1,4403,501,501,501
BEGIN DESCRIPTION:
Mapping XS e912737f
END DESCRIPTION:
XS GIS Cut Line= 3
      2533775.55     13564711.47      2534453.77     13564408.47
      2534865.82     13564107.32
#Sta/Elev= 30
  4113.6  192.58  4166.4  191.58  4239.4  190.55  4268.1  189.23  4332.0  189.49
  4404.1  185.53  4445.4  184.13  4530.5  180.57  4586.2  178.27  4768.6  167.63
  4823.8  165.42  4846.8  162.56  4872.2  161.48  4880.7  161.28  4917.7  159.90
  4953.2  156.27  4974.0  156.90  5005.1  155.36  5007.6  155.28  5007.8  154.78
  5011.6  155.28  5018.0  158.67  5033.0  157.86  5095.3  162.96  5217.1  168.75
  5253.8  172.05  5266.7  174.63  5281.4  174.88  5310.7  179.01  5366.8  179.67
#Mann=13,-1,0
  4113.6    0.05       0  4166.4    0.04       0  4404.1    0.05       0
  4445.4    0.04       0  4530.5    0.05       0  4768.6   0.013       0
  4872.2    0.05       0  4880.7    0.12       0  5005.1    0.05       0
  5007.6    0.05       0  5011.6    0.05       0  5033.0    0.12       0
  5253.8    0.05       0
Bank Sta=5007.6,5011.6
Exp/Cntr=0.3,0.1

Type RM Length L Ch R = 1,3902,375,375,375
BEGIN DESCRIPTION:
Mapping XS a0ae0a71
END DESCRIPTION:
XS GIS Cut Line= 3
      2534060.27     13564954.53      2534865.86     13564697.57
      2535094.62     13564219.24
#Sta/Elev= 30
  4169.0  189.26  4205.7  188.51  4353.0  183.43  4488.9  175.92  4615.9  170.21
  4667.3  170.53  4707.2  169.58  4727.9  167.81  4782.8  163.39  4902.4  158.47
  4988.9  153.02  5009.5  150.88  5009.8  150.38  5013.5  150.88  5039.6  152.56
  5051.8  155.65  5159.6  160.80  5182.3  162.84  5217.0  167.80  5233.2  168.94
  5278.5  168.30  5299.9  170.76  5306.7  171.93  5323.9  172.05  5329.4  173.39
  5346.5  173.82  5374.8  176.75  5445.0  176.98  5471.9  178.09  5544.8  178.69
#Mann=9,-1,0
  4169.0   0.013       0  4205.7    0.05       0  4727.9   0.013       0
  4902.4    0.05       0  4988.9    0.12       0  5009.5    0.05       0
  5013.5    0.12       0  5299.9    0.05       0  5445.0    0.03       0
Bank Sta=5009.5,5013.5
Exp/Cntr=0.3,0.1

Type RM Length L Ch R = 1,3527,108,108,108
BEGIN DESCRIPTION:
Mapping XS 808125ba
END DESCRIPTION:
XS GIS Cut Line= 4
      2534226.95     13565343.41      2535016.17     13565026.40
      2535168.08     13564861.47      2535150.72     13564364.51
#Sta/Elev= 30
  4061.5  193.42  4086.7  192.72  4216.2  191.03  4293.7  189.67  4436.6  188.30
  4479.7  184.36  4497.9  185.11  4533.6  180.29  4557.0  178.63  4622.6  175.28
  4716.1  169.60  4766.7  164.45  4837.0  159.76  4867.6  156.10  4914.8  155.05
  4939.1  151.15  4957.0  148.84  5002.3  146.54  5002.5  146.04  5006.3  146.54
  5046.8  147.66  5057.0  149.11  5089.3  153.85  5130.4  162.72  5192.7  165.96
  5252.8  172.32  5312.8  174.61  5380.0  174.98  5387.3  174.96  5633.5  176.37
#Mann=14,-1,0
  4061.5    0.04       0  4086.7    0.05       0  4216.2    0.04       0
  4293.7    0.05       0  4622.6   0.013       0  4716.1    0.05       0
  4837.0   0.013       0  4939.1    0.05       0  4957.0    0.12       0
  5002.3    0.05       0  5006.3    0.12       0  5057.0    0.05       0
  5380.0    0.03       0  5387.3    0.05       0
Bank Sta=5002.3,5006.3
Exp/Cntr=0.3,0.1

Type RM Length L Ch R = 1,3419,381,381,381
BEGIN DESCRIPTION:
Mapping XS 64d7e6c1
END DESCRIPTION:
XS GIS Cut Line= 4
      2534345.61     13565410.51      2535144.21     13565043.76
      2535265.74     13564863.64      2535248.38     13564620.63
#Sta/Elev= 30
  4121.7  197.56  4131.3  197.28  4232.3  195.34  4330.1  192.48  4434.5  187.21
  4486.0  183.10  4503.5  180.27  4561.3  176.80  4632.6  172.16  4818.8  160.12
  4841.8  155.25  4890.2  155.27  4910.7  156.84  4924.3  159.83  4946.3  152.39
  4962.2  149.56  4985.2  149.24  4999.8  147.33  5012.0  147.30  5012.2  146.80
  5016.0  147.30  5079.9  151.49  5094.8  153.76  5107.6  158.75  5128.7  161.57
  5208.8  171.59  5217.8  170.69  5354.5  174.50  5396.9  173.02  5461.4  176.02
#Mann=11,-1,0
  4121.7    0.05       0  4131.3    0.04       0  4232.3   0.013       0
  4561.3    0.05       0  4632.6   0.013       0  4890.2    0.05       0
  4999.8    0.12       0  5012.0    0.05       0  5016.0    0.12       0
  5128.7    0.05       0  5354.5    0.03       0
Bank Sta=5012,5016
Exp/Cntr=0.3,0.1

Type RM Length L Ch R = 1,3038,375,375,375
BEGIN DESCRIPTION:
Mapping XS 088118dc
END DESCRIPTION:
XS GIS Cut Line= 3
      2534192.25     13565496.18      2535421.41     13565301.74
      2536031.28     13564892.85
#Sta/Elev= 30
  3802.4  199.79  3856.8  200.68  3957.7  199.86  4056.9  196.70  4156.9  189.36
  4288.0  178.89  4356.9  175.28  4450.0  170.51  4656.9  163.02  4869.6  151.72
  4918.9  151.55  4994.4  144.11  4997.9  141.51  4998.1  141.01  5001.9  141.51
  5003.3  141.94  5030.2  149.61  5176.6  154.77  5183.6  156.89  5233.7  160.32
  5263.7  167.38  5299.7  171.28  5356.7  171.68  5373.1  173.64  5515.8  175.97
  5608.8  171.41  5662.5  171.63  5701.9  172.53  5752.9  177.65  5781.1  185.92
#Mann=13,-1,0
  3802.4   0.013       0  3856.8    0.05       0  3957.7    0.04       0
  4056.9   0.013       0  4156.9    0.05       0  4356.9    0.12       0
  4450.0    0.05       0  4656.9    0.12       0  4997.9    0.05       0
  5001.9    0.12       0  5003.3    0.05       0  5373.1    0.03       0
  5662.5   0.013       0
Bank Sta=4997.9,5001.9
Exp/Cntr=0.3,0.1

Type RM Length L Ch R = 1,2663,300,300,300
BEGIN DESCRIPTION:
Mapping XS 4c385219
END DESCRIPTION:
XS GIS Cut Line= 3
      2534400.63     13565836.45      2535539.47     13565648.96
      2535907.53     13565093.39
#Sta/Elev= 30
  3803.2  195.77  3836.1  194.58  3936.2  191.61  3990.1  191.64  4026.6  194.54
  4031.6  193.36  4089.0  196.26  4182.6  195.37  4272.6  191.25  4375.2  184.52
  4425.8  177.96  4527.2  169.46  4737.3  156.28  4937.6  146.25  4991.3  138.97
  4991.6  138.47  4995.3  138.97  4999.3  142.21  5022.1  147.35  5117.0  152.24
  5233.0  157.51  5292.5  162.34  5310.0  163.47  5390.4  174.97  5424.1  176.39
  5462.6  176.84  5483.7  174.11  5498.7  175.68  5576.9  173.71  5623.8  175.78
#Mann=13,-1,0
  3803.2    0.04       0  3836.1    0.05       0  3936.2    0.12       0
  4089.0    0.05       0  4272.6    0.12       0  4737.3   0.013       0
  4937.6    0.12       0  4991.3    0.05       0  4995.3    0.12       0
  5117.0    0.05       0  5233.0    0.03       0  5292.5    0.05       0
  5424.1    0.03       0
Bank Sta=4991.3,4995.3
Exp/Cntr=0.3,0.1

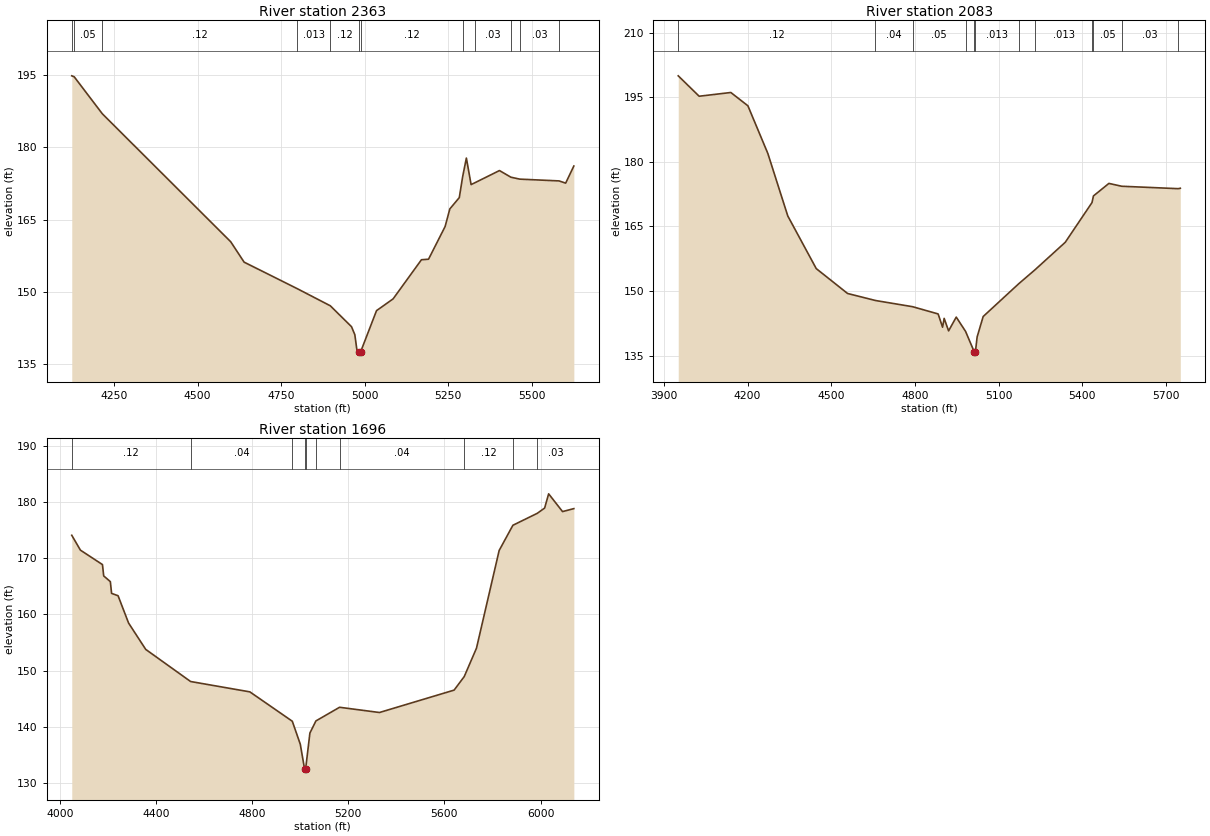
Type RM Length L Ch R = 1,2363,280,280,280
BEGIN DESCRIPTION:
Mapping XS e83f0cce
END DESCRIPTION:
XS GIS Cut Line= 3
      2534841.27     13565946.82      2535691.95     13565873.91
      2536146.81     13565412.11
#Sta/Elev= 30
  4123.5  194.81  4130.9  194.60  4214.9  186.94  4599.0  160.39  4639.1  156.16
  4798.0  150.66  4896.9  147.11  4960.3  142.78  4970.3  141.11  4976.3  138.06
  4983.8  137.58  4984.0  137.08  4987.8  137.58  5035.2  146.10  5084.8  148.54
  5169.6  156.66  5190.8  156.77  5240.4  163.55  5254.5  167.20  5282.8  169.55
  5292.9  173.90  5304.0  177.75  5318.1  172.25  5329.2  172.62  5403.0  175.16
  5437.2  173.78  5463.8  173.38  5581.4  173.01  5601.0  172.55  5625.5  176.10
#Mann=12,-1,0
  4123.5    0.12       0  4130.9    0.05       0  4214.9    0.12       0
  4798.0   0.013       0  4896.9    0.12       0  4983.8    0.05       0
  4987.8    0.12       0  5292.9    0.05       0  5329.2    0.03       0
  5437.2   0.013       0  5463.8    0.03       0  5581.4   0.013       0
Bank Sta=4983.8,4987.8
Exp/Cntr=0.3,0.1

Type RM Length L Ch R = 1,2083,387,387,387
BEGIN DESCRIPTION:
Mapping XS f1b4c6f0
END DESCRIPTION:
XS GIS Cut Line= 4
      2534810.33     13566114.24      2535525.58     13566260.07
      2536074.19     13565947.57      2536185.31     13565523.93
#Sta/Elev= 30
  3951.5  199.97  4026.5  195.23  4140.0  196.10  4201.2  193.01  4272.6  181.95
  4344.1  167.43  4446.1  155.21  4558.4  149.43  4658.4  147.80  4791.5  146.36
  4882.9  144.68  4898.8  141.60  4904.5  143.65  4920.4  140.75  4947.8  143.95
  4981.2  140.63  5012.5  135.85  5012.8  135.35  5016.5  135.85  5022.7  139.35
  5044.3  144.08  5171.0  151.65  5230.0  154.93  5338.5  161.32  5434.4  170.55
  5439.5  172.08  5494.9  174.99  5540.7  174.33  5742.9  173.77  5750.8  173.86
#Mann=12,-1,0
  3951.5    0.12       0  4658.4    0.04       0  4791.5    0.05       0
  4981.2   0.013       0  5012.5    0.03       0  5016.5   0.013       0
  5171.0    0.12       0  5230.0   0.013       0  5434.4    0.12       0
  5439.5    0.05       0  5540.7    0.03       0  5742.9   0.013       0
Bank Sta=5012.5,5016.5
Exp/Cntr=0.3,0.1

Type RM Length L Ch R = 1,1696,0,0,0
BEGIN DESCRIPTION:
Mapping XS 8f82c58d
END DESCRIPTION:
XS GIS Cut Line= 4
      2534900.61     13566301.75      2535490.86     13566482.29
      2536136.69     13566482.29      2536351.97     13565683.68
#Sta/Elev= 30
  4048.6  174.05  4084.6  171.41  4176.4  168.84  4181.6  166.82  4209.2  165.81
  4214.4  163.72  4241.4  163.30  4285.2  158.44  4356.5  153.76  4543.3  148.05
  4790.0  146.21  4966.7  140.99  5000.0  136.90  5018.0  132.44  5018.2  131.94
  5022.0  132.44  5040.0  138.89  5065.0  141.04  5163.4  143.47  5329.6  142.54
  5640.3  146.52  5682.5  148.93  5733.5  153.98  5827.9  171.35  5885.1  175.83
  5986.4  177.95  6017.2  178.89  6033.9  181.42  6091.8  178.26  6138.8  178.79
#Mann=10,-1,0
  4048.6    0.12       0  4543.3    0.04       0  4966.7    0.05       0
  5018.0    0.05       0  5022.0    0.05       0  5065.0   0.013       0
  5163.4    0.04       0  5682.5    0.12       0  5885.1    0.05       0
  5986.4    0.03       0
Bank Sta=5018,5022
Exp/Cntr=0.3,0.1

Chan Stop Cuts=-1