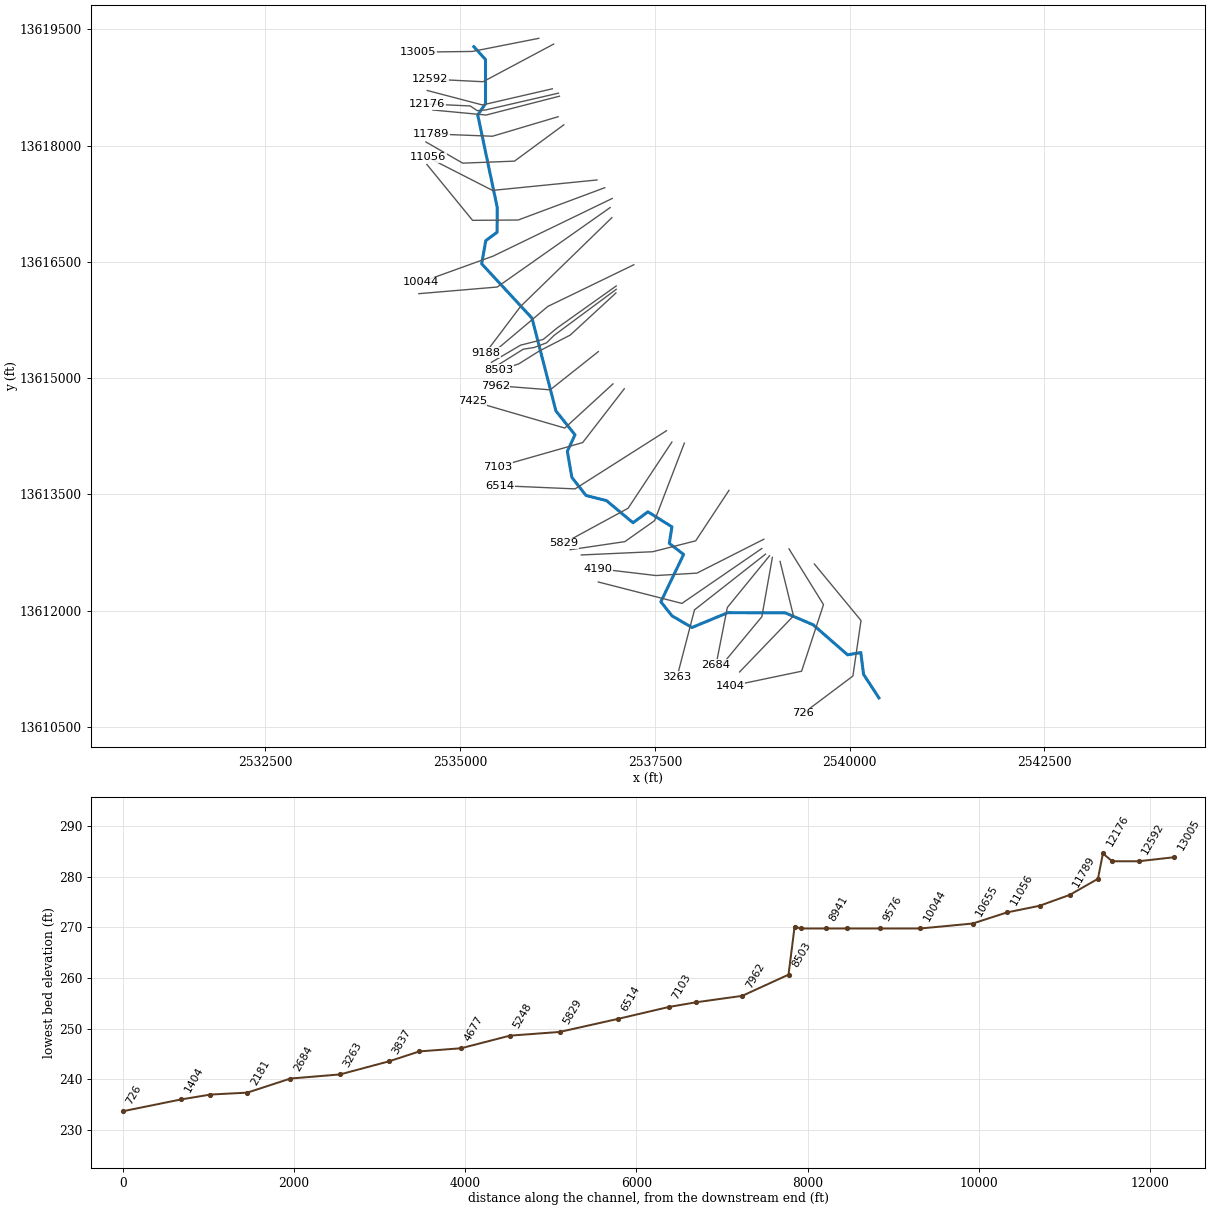
--- TRIB 14 TO IRISH CREEK.prj (project) ---

Proj Title=TRIB 14 TO IRISH CREEK Base Level Engineering
Current Plan=p01
Default Exp/Contr=0.3,0.1
English Units
Geom File=g01
Flow File=f01
Plan File=p01
Y Axis Title=Elevation
X Axis Title(PF)=Main Channel Distance
X Axis Title(XS)=Station
BEGIN DESCRIPTION:
TRIB 14 TO IRISH CREEK
END DESCRIPTION:
DSS Export Rating Curves= 0
DSS Export Rating Curve Sorted= 0
DSS Export Volume Flow Curves= 0
DXF OffsetX= 0
DXF OffsetY= 0
DXF ScaleX= 1
DXF ScaleY= 10

--- TRIB 14 TO IRISH CREEK.p01 (plan) ---

Plan Title=Multiple Run
Short Identifier=Multiple
Geom File=g01
Flow File=f01
Subcritical Flow
K Sum by GR= 0
Std Step Tol= 0.01
Critical Tol= 0.01
Num of Std Step Trials= 20
Max Error Tol= 0.3
Flow Tol Ratio= 0.001
Split Flow NTrial= 30
Split Flow Tol= 0.02
Split Flow Ratio= 0.02
Log Output Level= 0
Friction Slope Method= 1
Unsteady Friction Slope Method= 2
Unsteady Bridges Friction Slope Method= 1
Parabolic Critical Depth
Global Vel Dist=  1 , 1 , 1
Global Log Level= 0
CheckData=True
Encroach Param= -1, 0, 0, 0
BEGIN DESCRIPTION:
Multiple Run
END DESCRIPTION:

--- TRIB 14 TO IRISH CREEK.f01 (steady flow) ---

Flow Title=Multiple
Number of Profiles=7
Profile Names=10-year,25-year,50-year,1pct_min,100-year,1pct_plu,500-year
River Rch & RM= TRIB 14 TO IRISH,Reach-1,13005
     582     929    1240     802    1601    3194    2639
River Rch & RM= TRIB 14 TO IRISH,Reach-1,9576
     884    1446    1962    1289    2573    5133    4376
River Rch & RM= TRIB 14 TO IRISH,Reach-1,8645
    1104    1825    2495    1650    3292    6568    5673
River Rch & RM= TRIB 14 TO IRISH,Reach-1,6514
    1155    1910    2610    1724    3441    6865    5921
River Rch & RM= TRIB 14 TO IRISH,Reach-1,3263
    1469    2457    3382    2249    4487    8954    7826
Boundary for River Rch & Prof#=TRIB 14 TO IRISH,Reach-1,1
Up Type=0
Dn Type=3
Dn Slope=0.005
Boundary for River Rch & Prof#=TRIB 14 TO IRISH,Reach-1,2
Up Type=0
Dn Type=3
Dn Slope=0.005
Boundary for River Rch & Prof#=TRIB 14 TO IRISH,Reach-1,3
Up Type=0
Dn Type=3
Dn Slope=0.005
Boundary for River Rch & Prof#=TRIB 14 TO IRISH,Reach-1,4
Up Type=0
Dn Type=3
Dn Slope=0.005
Boundary for River Rch & Prof#=TRIB 14 TO IRISH,Reach-1,5
Up Type=0
Dn Type=3
Dn Slope=0.005
Boundary for River Rch & Prof#=TRIB 14 TO IRISH,Reach-1,6
Up Type=0
Dn Type=3
Dn Slope=0.005
Boundary for River Rch & Prof#=TRIB 14 TO IRISH,Reach-1,7
Up Type=0
Dn Type=3
Dn Slope=0.005

--- TRIB 14 TO IRISH CREEK.g01 (geometry) ---

Geom Title=Existing Conditions

River Reach=TRIB 14 TO IRISH,Reach-1
Reach XY= 30
      2535175.00     13619275.00      2535324.48     13619109.79
      2535324.61     13618540.16      2535224.87     13618395.47
      2535475.20     13617200.08      2535473.02     13616880.67
      2535328.07     13616773.57      2535275.00     13616475.00
      2535921.24     13615773.44      2536228.61     13614576.50
      2536473.21     13614268.89      2536375.06     13614054.97
      2536433.14     13613718.94      2536614.90     13613485.39
      2536877.42     13613419.46      2537218.33     13613133.95
      2537409.64     13613275.11      2537717.63     13613081.37
      2537684.17     13612868.05      2537867.92     13612725.02
      2537575.55     13612114.36      2537718.79     13611932.76
      2537975.00     13611782.50      2538435.54     13611973.92
      2539173.44     13611971.26      2539531.17     13611817.14
      2539972.71     13611430.11      2540142.14     13611458.97
      2540178.55     13611176.47      2540375.00     13610875.00

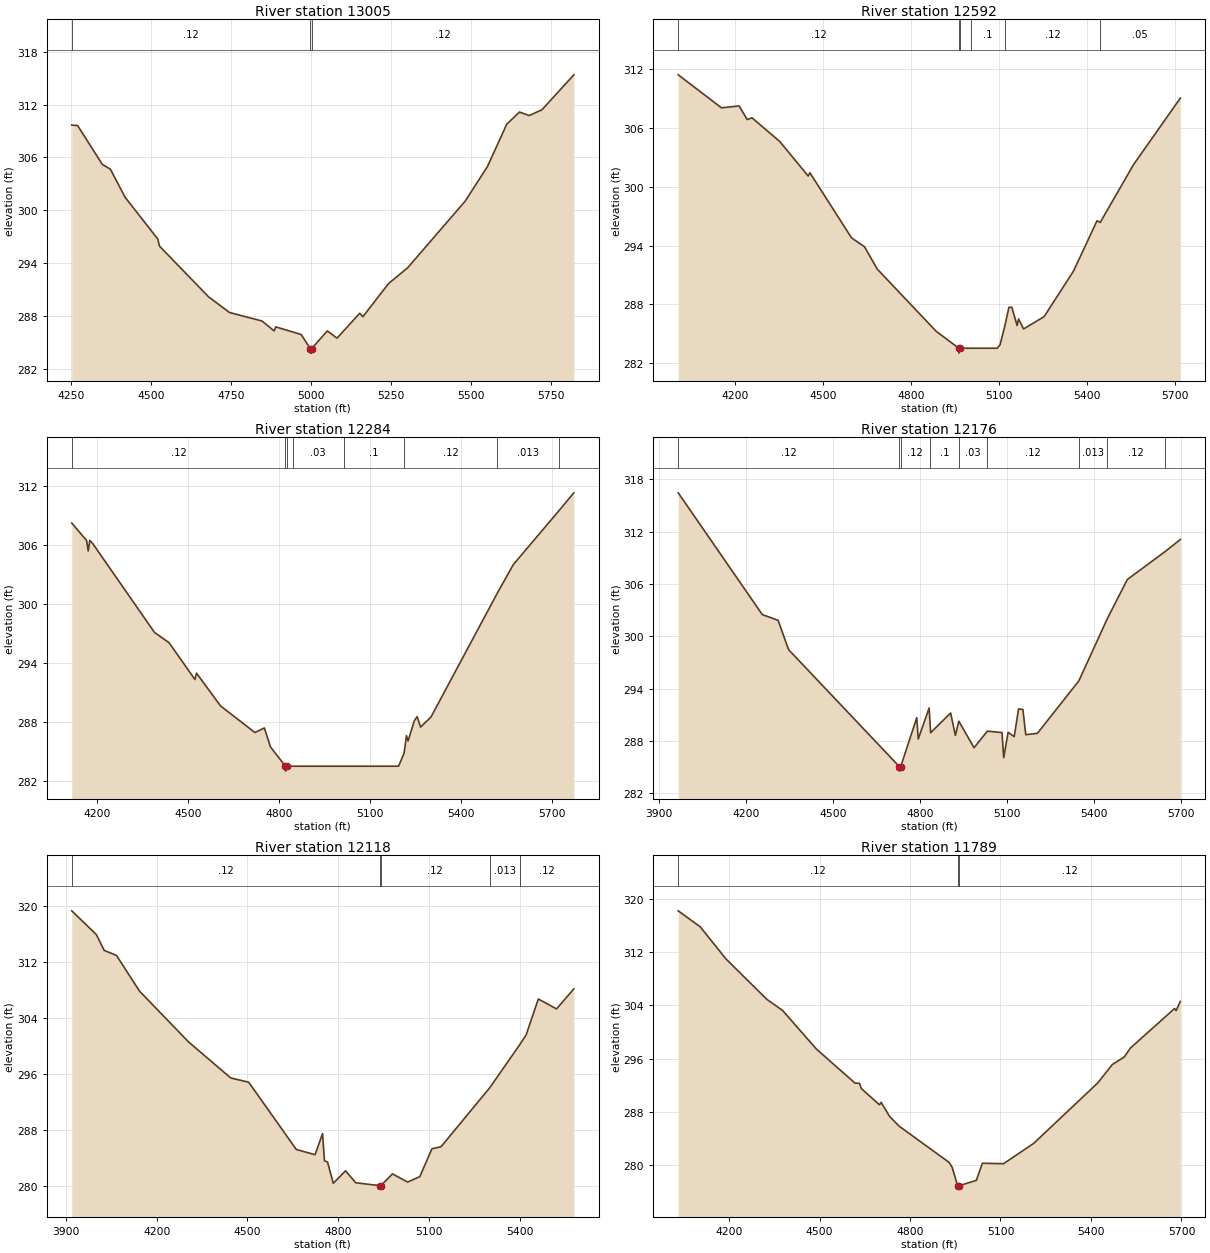
Type RM Length L Ch R = 1,13005,413,413,413
BEGIN DESCRIPTION:
Mapping XS 75ad1874
END DESCRIPTION:
XS GIS Cut Line= 3
      2536009.00     13619383.33      2535153.98     13619214.07
      2534455.14     13619205.39
#Sta/Elev= 30
  4252.1  309.67  4270.4  309.62  4347.9  305.20  4372.8  304.67  4419.0  301.48
  4521.2  296.74  4526.5  295.94  4680.2  290.18  4745.5  288.41  4847.4  287.44
  4885.1  286.32  4890.2  286.78  4969.8  285.91  4998.3  284.30  4998.6  283.80
  5002.1  283.80  5002.3  284.30  5051.3  286.32  5081.9  285.50  5152.7  288.32
  5162.7  287.93  5242.7  291.68  5302.7  293.48  5482.7  301.04  5552.7  304.99
  5612.7  309.77  5652.7  311.15  5682.7  310.75  5722.7  311.40  5822.6  315.37
#Mann=3,-1,0
  4252.1    0.12       0  4998.3    0.05       0  5002.3    0.12       0
Bank Sta=4998.3,5002.3
Exp/Cntr=0.3,0.1

Type RM Length L Ch R = 1,12592,308,308,308
BEGIN DESCRIPTION:
Mapping XS a742f06f
END DESCRIPTION:
XS GIS Cut Line= 3
      2536200.00     13619309.56      2535292.86     13618823.44
      2534611.42     13618858.16
#Sta/Elev= 30
  4007.3  311.44  4154.7  308.07  4214.8  308.26  4242.4  306.87  4258.7  307.05
  4353.3  304.63  4450.4  301.10  4456.0  301.44  4598.2  294.78  4642.1  293.88
  4685.9  291.59  4886.6  285.24  4964.0  283.51  4964.2  283.01  4968.0  283.51
  5003.6  283.51  5094.4  283.51  5104.4  283.87  5120.8  285.81  5134.5  287.68
  5144.5  287.70  5162.4  285.83  5167.4  286.50  5184.5  285.48  5254.6  286.74
  5354.7  291.39  5434.9  296.53  5445.8  296.36  5559.2  302.26  5718.8  309.06
#Mann=6,-1,0
  4007.3    0.12       0  4964.0    0.05       0  4968.0    0.12       0
  5003.6     0.1       0  5120.8    0.12       0  5445.8    0.05       0
Bank Sta=4964,4968
Exp/Cntr=0.3,0.1

Type RM Length L Ch R = 1,12284,108,108,108
BEGIN DESCRIPTION:
Mapping XS ac3e5c55
END DESCRIPTION:
XS GIS Cut Line= 3
      2536182.62     13618732.30      2535284.18     13618523.96
      2534576.76     13618710.58
#Sta/Elev= 30
  4118.0  308.25  4166.9  306.48  4172.2  305.41  4177.4  306.49  4187.4  306.15
  4390.7  297.12  4438.5  296.08  4523.8  292.33  4528.9  292.98  4608.3  289.64
  4721.2  286.94  4752.5  287.40  4772.5  285.48  4821.9  283.51  4822.1  283.01
  4825.9  283.51  4846.9  283.51  5013.3  283.51  5194.6  283.51  5212.6  284.83
  5220.6  286.62  5225.8  286.08  5246.3  288.13  5255.7  288.55  5267.0  287.49
  5301.2  288.51  5520.1  301.14  5572.8  304.04  5722.2  309.49  5771.9  311.33
#Mann=8,-1,0
  4118.0    0.12       0  4821.9    0.03       0  4825.9    0.12       0
  4846.9    0.03       0  5013.3     0.1       0  5212.6    0.12       0
  5520.1   0.013       0  5722.2    0.05       0
Bank Sta=4821.9,4825.9
Exp/Cntr=0.3,0.1

Type RM Length L Ch R = 1,12176,58,58,58
BEGIN DESCRIPTION:
Mapping XS 2c18f123
END DESCRIPTION:
XS GIS Cut Line= 5
      2536260.76     13618675.88      2535323.25     13618458.86
      2535219.08     13618450.18      2535127.93     13618510.94
      2534572.42     13618536.98
#Sta/Elev= 30
  3966.6  316.44  4256.7  302.49  4311.2  301.84  4347.3  298.48  4730.1  285.06
  4730.3  284.56  4734.1  285.06  4789.7  290.68  4794.8  288.24  4832.4  291.80
  4834.6  290.57  4837.5  288.96  4906.6  291.22  4922.9  288.65  4934.8  290.28
  4987.4  287.24  5033.3  289.14  5083.8  288.98  5089.8  286.10  5104.8  289.01
  5125.9  288.51  5140.9  291.69  5155.9  291.62  5165.9  288.73  5206.0  288.89
  5349.0  294.90  5447.6  302.05  5516.3  306.51  5644.9  309.67  5699.1  311.09
#Mann=9,-1,0
  3966.6    0.12       0  4730.1    0.03       0  4734.1    0.12       0
  4834.6     0.1       0  4934.8    0.03       0  5033.3    0.12       0
  5349.0   0.013       0  5447.6    0.12       0  5644.9    0.05       0
Bank Sta=4730.1,4734.1
Exp/Cntr=0.3,0.1

Type RM Length L Ch R = 1,12118,329,329,329
BEGIN DESCRIPTION:
Mapping XS 34308622
END DESCRIPTION:
XS GIS Cut Line= 3
      2536273.76     13618636.81      2535331.93     13618393.75
      2534648.09     13618458.68
#Sta/Elev= 30
  3919.5  319.30  4000.8  315.91  4026.7  313.65  4067.4  312.93  4143.6  307.82
  4306.2  300.55  4444.9  295.43  4504.4  294.82  4661.8  285.21  4723.8  284.47
  4748.4  287.49  4754.8  283.61  4765.1  283.40  4783.9  280.38  4824.5  282.17
  4858.0  280.46  4937.3  280.05  4937.6  279.55  4941.3  280.05  4979.5  281.73
  5029.7  280.56  5069.9  281.33  5110.1  285.32  5140.2  285.61  5301.3  294.04
  5400.4  300.19  5421.5  301.59  5461.7  306.71  5521.9  305.29  5579.1  308.15
#Mann=5,-1,0
  3919.5    0.12       0  4937.3    0.05       0  4941.3    0.12       0
  5301.3   0.013       0  5400.4    0.12       0
Bank Sta=4937.3,4941.3
Exp/Cntr=0.3,0.1

Type RM Length L Ch R = 1,11789,353,353,353
BEGIN DESCRIPTION:
Mapping XS 1f36e360
END DESCRIPTION:
XS GIS Cut Line= 3
      2536256.40     13618372.05      2535414.39     13618120.32
      2534629.41     13618150.67
#Sta/Elev= 30
  4031.7  318.21  4104.8  315.80  4189.7  310.99  4325.4  304.91  4377.6  303.24
  4489.9  297.43  4617.6  292.32  4632.8  292.28  4638.5  291.50  4699.0  289.05
  4704.3  289.43  4732.2  287.32  4763.8  285.85  4929.9  280.39  4939.9  279.64
  4958.0  276.88  4958.2  276.38  4961.7  276.38  4962.0  276.88  5020.0  277.70
  5040.0  280.27  5110.1  280.20  5210.1  283.26  5422.6  292.35  5470.3  295.09
  5510.4  296.25  5530.4  297.57  5677.1  303.53  5682.1  303.21  5696.1  304.59
#Mann=3,-1,0
  4031.7    0.12       0  4958.0    0.05       0  4962.0    0.12       0
Bank Sta=4958,4962
Exp/Cntr=0.3,0.1

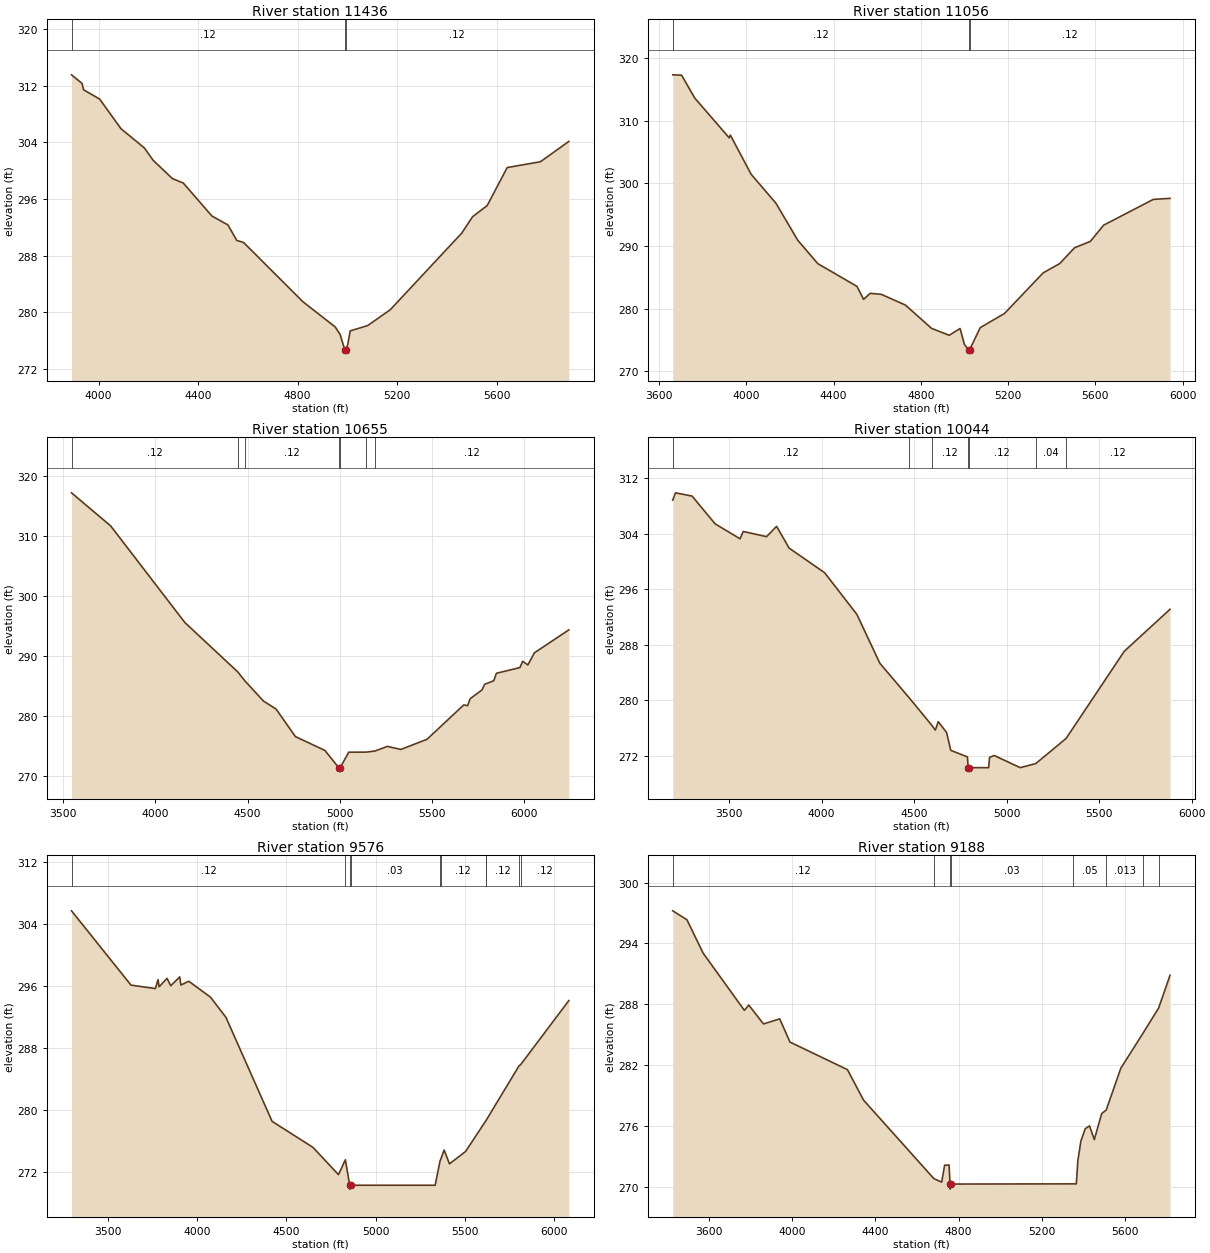
Type RM Length L Ch R = 1,11436,380,380,380
BEGIN DESCRIPTION:
Mapping XS 2eaffc09
END DESCRIPTION:
XS GIS Cut Line= 4
      2536330.19     13618267.88      2535696.51     13617799.14
      2535032.45     13617773.09      2534559.71     13618046.33
#Sta/Elev= 30
  3891.1  313.55  3933.3  312.34  3939.5  311.44  4004.3  310.12  4089.8  305.94
  4183.6  303.23  4219.3  301.47  4296.5  298.89  4340.3  298.26  4455.2  293.61
  4519.5  292.35  4555.4  290.15  4582.4  289.87  4820.9  281.50  4951.0  277.93
  4971.0  276.84  4989.1  274.73  4989.3  274.23  4992.8  274.23  4993.1  274.73
  5001.1  275.40  5011.1  277.37  5081.1  278.12  5171.9  280.35  5459.9  291.20
  5503.0  293.50  5561.8  295.08  5642.2  300.45  5775.7  301.27  5889.9  304.14
#Mann=3,-1,0
  3891.1    0.12       0  4989.1    0.05       0  4993.1    0.12       0
Bank Sta=4989.1,4993.1
Exp/Cntr=0.3,0.1

Type RM Length L Ch R = 1,11056,401,401,401
BEGIN DESCRIPTION:
Mapping XS 6389b5c5
END DESCRIPTION:
XS GIS Cut Line= 3
      2536755.50     13617556.08      2535414.39     13617421.53
      2534585.38     13617846.89
#Sta/Elev= 30
  3662.8  317.33  3703.5  317.27  3763.8  313.62  3921.8  307.27  3926.8  307.72
  4022.1  301.47  4135.7  296.85  4236.2  290.92  4328.2  287.19  4507.5  283.57
  4537.7  281.50  4567.8  282.46  4618.1  282.31  4729.5  280.59  4849.2  276.87
  4930.2  275.77  4979.9  276.85  5000.0  274.30  5019.2  273.42  5019.4  272.92
  5023.2  273.42  5072.4  276.99  5183.3  279.24  5360.9  285.73  5437.1  287.22
  5504.5  289.73  5577.2  290.75  5638.1  293.34  5865.7  297.45  5942.4  297.62
#Mann=3,-1,0
  3662.8    0.12       0  5019.2    0.05       0  5023.2    0.12       0
Bank Sta=5019.2,5023.2
Exp/Cntr=0.3,0.1

Type RM Length L Ch R = 1,10655,611,611,611
BEGIN DESCRIPTION:
Mapping XS 84cab484
END DESCRIPTION:
XS GIS Cut Line= 4
      2536855.37     13617456.26      2535744.25     13617039.59
      2535158.32     13617035.25      2534572.37     13617755.74
#Sta/Elev= 30
  3544.1  317.17  3757.0  311.64  4159.3  295.54  4447.4  287.28  4485.6  285.80
  4586.5  282.43  4655.2  281.09  4760.0  276.50  4920.0  274.19  4998.0  271.23
  4998.3  270.73  5002.0  271.23  5050.0  273.89  5145.2  273.90  5192.6  274.09
  5260.0  274.86  5332.8  274.35  5475.0  276.04  5674.7  281.78  5695.5  281.65
  5709.9  282.83  5773.8  284.28  5788.2  285.22  5837.8  285.82  5852.1  287.06
  5980.0  288.01  5994.3  289.06  6023.1  288.45  6058.3  290.47  6245.4  294.30
#Mann=7,-1,0
  3544.1    0.12       0  4447.4    0.05       0  4485.6    0.12       0
  4998.0    0.05       0  5002.0    0.12       0  5145.2     0.1       0
  5192.6    0.12       0
Bank Sta=4998,5002
Exp/Cntr=0.3,0.1

Type RM Length L Ch R = 1,10044,468,468,468
BEGIN DESCRIPTION:
TRIB 14 TO IRISH CREEK 19.0
END DESCRIPTION:
XS GIS Cut Line= 3
      2536950.89     13617317.38      2535425.00     13616575.00
      2534494.29     13616236.65
#Sta/Elev= 30
  3195.9  308.82  3210.4  309.88  3300.6  309.41  3424.9  305.41  3559.8  303.25
  3576.7  304.31  3702.9  303.56  3757.1  305.05  3824.8  301.91  4016.3  298.37
  4191.1  292.35  4315.0  285.31  4473.7  280.32  4596.8  276.33  4614.8  275.66
  4630.7  276.88  4675.8  275.32  4698.3  272.75  4788.5  271.80  4792.1  270.25
  4792.4  269.75  4796.1  270.25  4902.8  270.25  4908.1  271.74  4933.4  272.00
  5073.7  270.25  5157.7  270.84  5321.5  274.46  5635.7  287.03  5883.1  293.09
#Mann=7,-1,0
  3195.9    0.12       0  4473.7    0.05       0  4596.8    0.12       0
  4792.1    0.05       0  4796.1    0.12       0  5157.7    0.04       0
  5321.5    0.12       0
Bank Sta=4792.1,4796.1
Exp/Cntr=0.3,0.1

Type RM Length L Ch R = 1,9576,388,388,388
BEGIN DESCRIPTION:
TRIB 14 TO IRISH CREEK 18.0
END DESCRIPTION:
XS GIS Cut Line= 3
      2536924.85     13617200.20      2535475.00     13616175.00
      2534469.15     13616089.15
#Sta/Elev= 30
  3296.2  305.68  3629.2  296.09  3765.9  295.64  3780.7  296.79  3786.8  295.88
  3831.1  296.96  3852.0  296.01  3902.5  297.15  3908.6  296.10  3953.0  296.59
  4074.8  294.53  4161.0  291.93  4419.5  278.50  4648.5  275.14  4791.2  271.62
  4829.9  273.54  4854.3  270.25  4854.6  269.75  4858.7  270.25  5332.8  270.25
  5360.0  273.38  5363.4  273.56  5383.0  274.80  5413.1  273.01  5503.5  274.62
  5617.0  278.59  5619.9  278.69  5802.1  285.65  5812.5  285.85  6081.4  294.09
#Mann=10,-1,0
  3296.2    0.12       0  4829.9    0.03       0  4854.3    0.03       0
  4858.7    0.03       0  5360.0    0.04       0  5363.4    0.12       0
  5617.0    0.04       0  5619.9    0.12       0  5802.1    0.05       0
  5812.5    0.12       0
Bank Sta=4854.3,4858.7
Exp/Cntr=0.3,0.1

Type RM Length L Ch R = 1,9188,247,247,247
BEGIN DESCRIPTION:
TRIB 14 TO IRISH CREEK 17.0
END DESCRIPTION:
XS GIS Cut Line= 3
      2536946.49     13617069.94      2535775.00     13615925.00
      2535324.98     13615324.98
#Sta/Elev= 30
  3427.5  297.21  3495.7  296.33  3573.4  293.04  3771.5  287.39  3792.8  287.91
  3863.3  286.05  3941.2  286.55  3990.6  284.26  4266.5  281.54  4344.3  278.52
  4681.4  270.79  4719.0  270.44  4733.2  272.11  4754.5  272.13  4759.2  270.25
  4759.6  269.75  4763.7  270.25  5350.3  270.27  5365.6  270.27  5372.9  272.55
  5387.4  274.48  5408.3  275.71  5429.1  275.99  5452.0  274.64  5487.4  277.20
  5509.3  277.56  5579.1  281.67  5686.6  285.16  5760.9  287.62  5815.6  290.85
#Mann=8,-1,0
  3427.5    0.12       0  4681.4    0.03       0  4759.2    0.03       0
  4763.7    0.03       0  5350.3    0.05       0  5509.3   0.013       0
  5686.6    0.04       0  5760.9   0.013       0
Bank Sta=4759.2,4763.7
Exp/Cntr=0.3,0.1

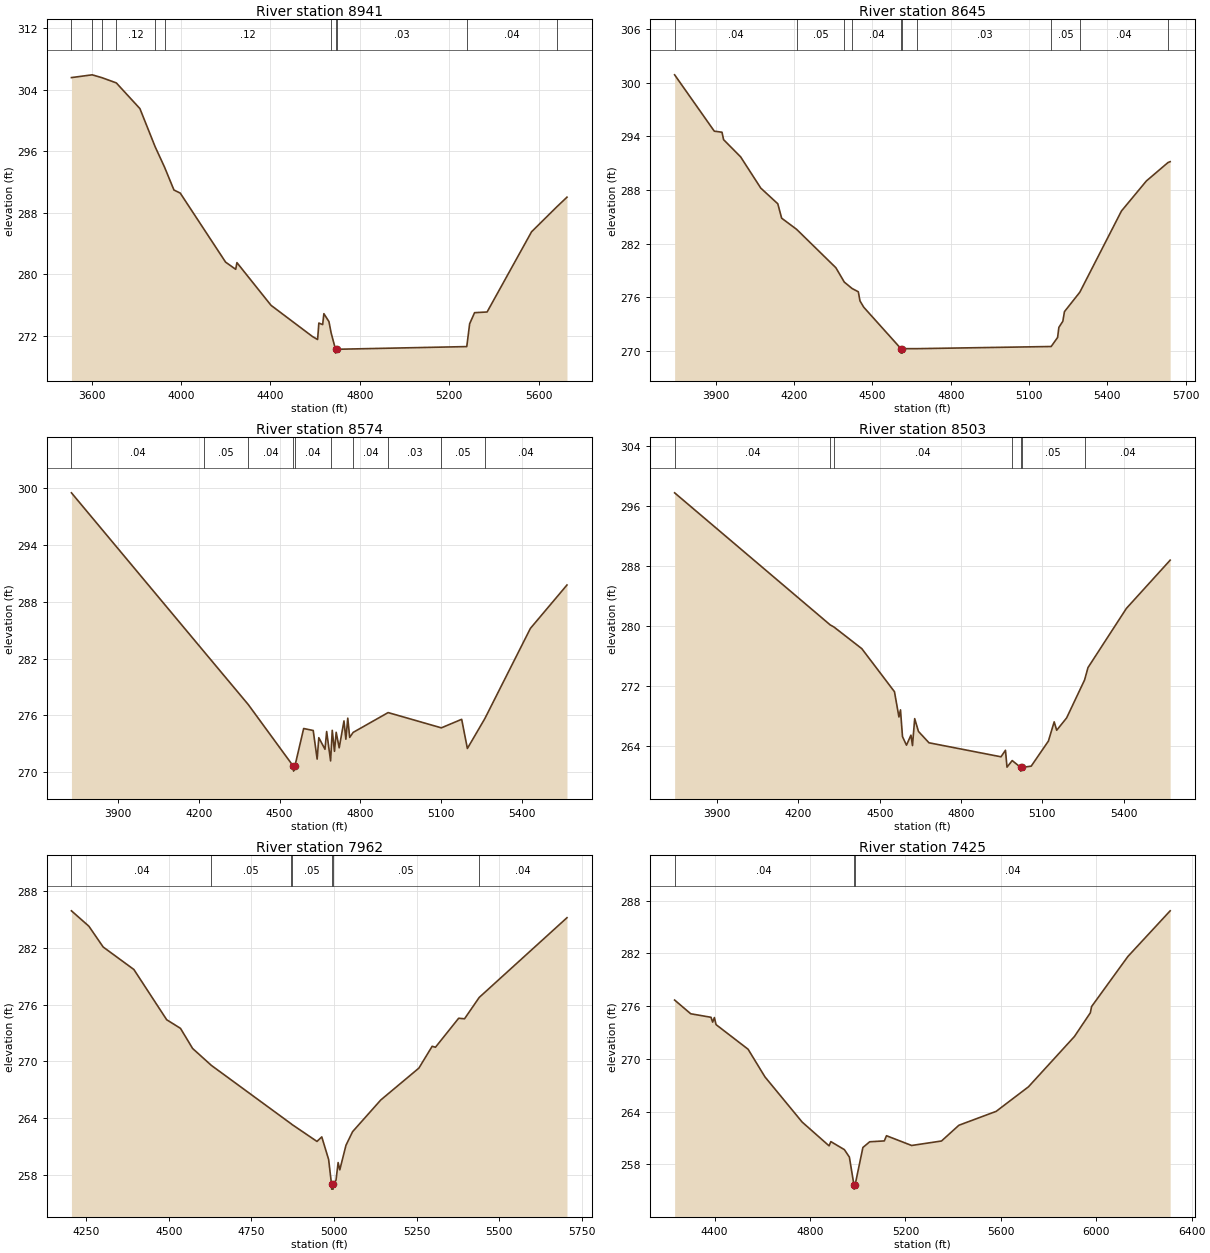
Type RM Length L Ch R = 1,8941,296,296,296
BEGIN DESCRIPTION:
TRIB 14 TO IRISH CREEK 16.0
END DESCRIPTION:
XS GIS Cut Line= 3
      2537228.64     13616462.34      2536125.00     13615925.00
      2535370.98     13615286.10
#Sta/Elev= 30
  3510.2  305.58  3602.8  305.94  3645.5  305.58  3710.8  304.89  3816.3  301.55
  3884.3  296.60  3926.7  293.92  3968.6  290.96  3996.7  290.56  4199.6  281.58
  4244.7  280.65  4250.2  281.52  4402.5  275.97  4588.4  271.90  4610.9  271.52
  4616.5  273.66  4633.5  273.46  4639.0  274.88  4661.6  273.85  4671.4  272.38
  4691.0  270.25  4691.3  269.75  4695.5  270.25  5277.9  270.60  5290.8  273.57
  5312.8  275.01  5368.8  275.10  5567.6  285.53  5680.7  288.78  5726.0  290.03
#Mann=11,-1,0
  3510.2    0.05       0  3602.8   0.013       0  3645.5    0.05       0
  3710.8    0.12       0  3884.3    0.05       0  3926.7    0.12       0
  4671.4    0.03       0  4691.0    0.03       0  4695.5    0.03       0
  5277.9    0.04       0  5680.7   0.013       0
Bank Sta=4691,4695.5
Exp/Cntr=0.3,0.1

Type RM Length L Ch R = 1,8645,71,71,71
BEGIN DESCRIPTION:
Mapping XS 5bcb041e
END DESCRIPTION:
XS GIS Cut Line= 5
      2537002.93     13616188.89      2536243.39     13615646.36
      2536065.43     13615498.79      2535774.64     13615425.00
      2535401.34     13615203.63
#Sta/Elev= 30
  3742.0  300.87  3894.0  294.57  3923.5  294.45  3929.6  293.62  3994.8  291.70
  4072.2  288.20  4137.3  286.45  4152.1  284.84  4209.5  283.59  4359.8  279.30
  4392.2  277.69  4422.2  276.97  4445.8  276.61  4452.2  275.59  4466.7  274.88
  4609.1  270.25  4609.5  269.75  4613.8  269.75  4614.2  270.25  4672.4  270.25
  5184.7  270.49  5209.3  271.50  5214.2  272.63  5229.4  273.31  5235.6  274.39
  5294.4  276.56  5453.9  285.64  5549.4  289.00  5632.2  291.06  5640.6  291.16
#Mann=10,-1,0
  3742.0    0.04       0  4209.5    0.05       0  4392.2    0.12       0
  4422.2    0.04       0  4609.1    0.03       0  4614.2    0.04       0
  4672.4    0.03       0  5184.7    0.05       0  5294.4    0.04       0
  5632.2   0.013       0
Bank Sta=4609.1,4614.2
Exp/Cntr=0.3,0.1

Type RM Length L Ch R = 1,8574,71,71,71
BEGIN DESCRIPTION:
Mapping XS e933f4cb
END DESCRIPTION:
XS GIS Cut Line= 6
      2537002.92     13616145.48      2536204.32     13615550.87
      2536108.84     13615455.39      2535948.25     13615394.62
      2535809.36     13615372.92      2535470.79     13615160.23
#Sta/Elev= 30
  3725.8  299.50  4217.5  282.78  4383.3  277.15  4551.4  270.62  4551.8  270.12
  4556.5  270.62  4589.4  274.62  4624.9  274.41  4639.5  271.39  4645.7  273.65
  4668.6  272.43  4674.9  274.30  4689.5  271.20  4692.1  272.55  4695.7  274.43
  4704.0  272.21  4710.3  274.22  4721.5  272.58  4739.3  275.42  4746.3  273.49
  4753.4  275.71  4760.5  273.68  4773.5  274.21  4903.5  276.30  5101.4  274.69
  5177.0  275.59  5198.2  272.51  5263.4  275.68  5432.6  285.19  5568.6  289.77
#Mann=10,-1,0
  3725.8    0.04       0  4217.5    0.05       0  4383.3    0.04       0
  4551.4    0.03       0  4556.5    0.04       0  4692.1    0.03       0
  4773.5    0.04       0  4903.5    0.03       0  5101.4    0.05       0
  5263.4    0.04       0
Bank Sta=4551.4,4556.5
Exp/Cntr=0.3,0.1

Type RM Length L Ch R = 1,8503,541,541,541
BEGIN DESCRIPTION:
Mapping XS b1cf1a67
END DESCRIPTION:
XS GIS Cut Line= 5
      2536998.58     13616097.73      2536412.66     13615555.21
      2536017.69     13615351.22      2535748.59     13615181.95
      2535492.51     13615103.82
#Sta/Elev= 30
  3743.1  297.75  4317.2  280.14  4331.0  279.86  4433.9  276.97  4554.4  271.23
  4570.9  267.86  4576.6  268.81  4584.0  265.24  4598.7  264.10  4615.2  265.44
  4620.9  264.05  4629.0  267.64  4643.0  265.93  4681.7  264.42  4947.5  262.55
  4964.0  263.42  4969.7  261.17  4988.9  262.05  5019.9  261.14  5020.3  260.64
  5025.0  261.14  5058.9  261.30  5122.5  264.65  5143.8  267.21  5153.1  266.09
  5189.6  267.73  5255.9  272.79  5268.6  274.45  5410.3  282.34  5571.8  288.77
#Mann=7,-1,0
  3743.1    0.04       0  4317.2    0.05       0  4331.0    0.04       0
  4988.9    0.05       0  5019.9    0.05       0  5025.0    0.05       0
  5255.9    0.04       0
Bank Sta=5019.9,5025
Exp/Cntr=0.3,0.1

Type RM Length L Ch R = 1,7962,537,537,537
BEGIN DESCRIPTION:
Mapping XS 77970c8d
END DESCRIPTION:
XS GIS Cut Line= 3
      2536772.87     13615341.64      2536154.84     13614848.62
      2535448.30     13614904.03
#Sta/Elev= 30
  4205.6  285.92  4258.4  284.29  4301.6  282.09  4394.5  279.71  4493.8  274.39
  4535.5  273.48  4572.2  271.35  4628.9  269.56  4870.2  263.38  4872.6  263.31
  4948.5  261.51  4963.0  261.99  4983.8  259.59  4992.5  256.96  4992.9  256.46
  4997.3  256.46  4997.7  256.96  5006.1  257.41  5012.5  259.27  5017.5  258.50
  5036.2  261.10  5056.2  262.54  5141.6  265.90  5256.8  269.27  5297.0  271.58
  5307.0  271.48  5377.2  274.55  5394.9  274.49  5439.3  276.75  5704.9  285.19
#Mann=7,-1,0
  4205.6    0.04       0  4628.9    0.05       0  4870.2    0.04       0
  4872.6    0.05       0  4992.5    0.05       0  4997.7    0.05       0
  5439.3    0.04       0
Bank Sta=4992.5,4997.7
Exp/Cntr=0.3,0.1

Type RM Length L Ch R = 1,7425,322,322,322
BEGIN DESCRIPTION:
Mapping XS ec13c32d
END DESCRIPTION:
XS GIS Cut Line= 3
      2536960.43     13614925.04      2536342.34     13614355.56
      2535154.81     13614702.79
#Sta/Elev= 30
  4232.2  276.69  4299.7  275.13  4384.8  274.73  4391.6  274.18  4399.0  274.70
  4405.8  273.90  4540.2  271.10  4611.1  267.95  4767.0  262.82  4879.8  260.12
  4887.2  260.60  4943.9  259.69  4964.9  258.84  4983.9  255.70  4984.3  255.20
  4989.1  255.70  5021.6  259.93  5050.0  260.58  5111.5  260.68  5120.4  261.27
  5226.0  260.16  5351.2  260.67  5424.1  262.46  5580.4  264.04  5715.8  266.83
  5908.3  272.54  5975.2  275.24  5980.4  275.95  6132.6  281.64  6309.9  286.83
#Mann=3,-1,0
  4232.2    0.04       0  4983.9    0.04       0  4989.1    0.04       0
Bank Sta=4983.9,4989.1
Exp/Cntr=0.3,0.1

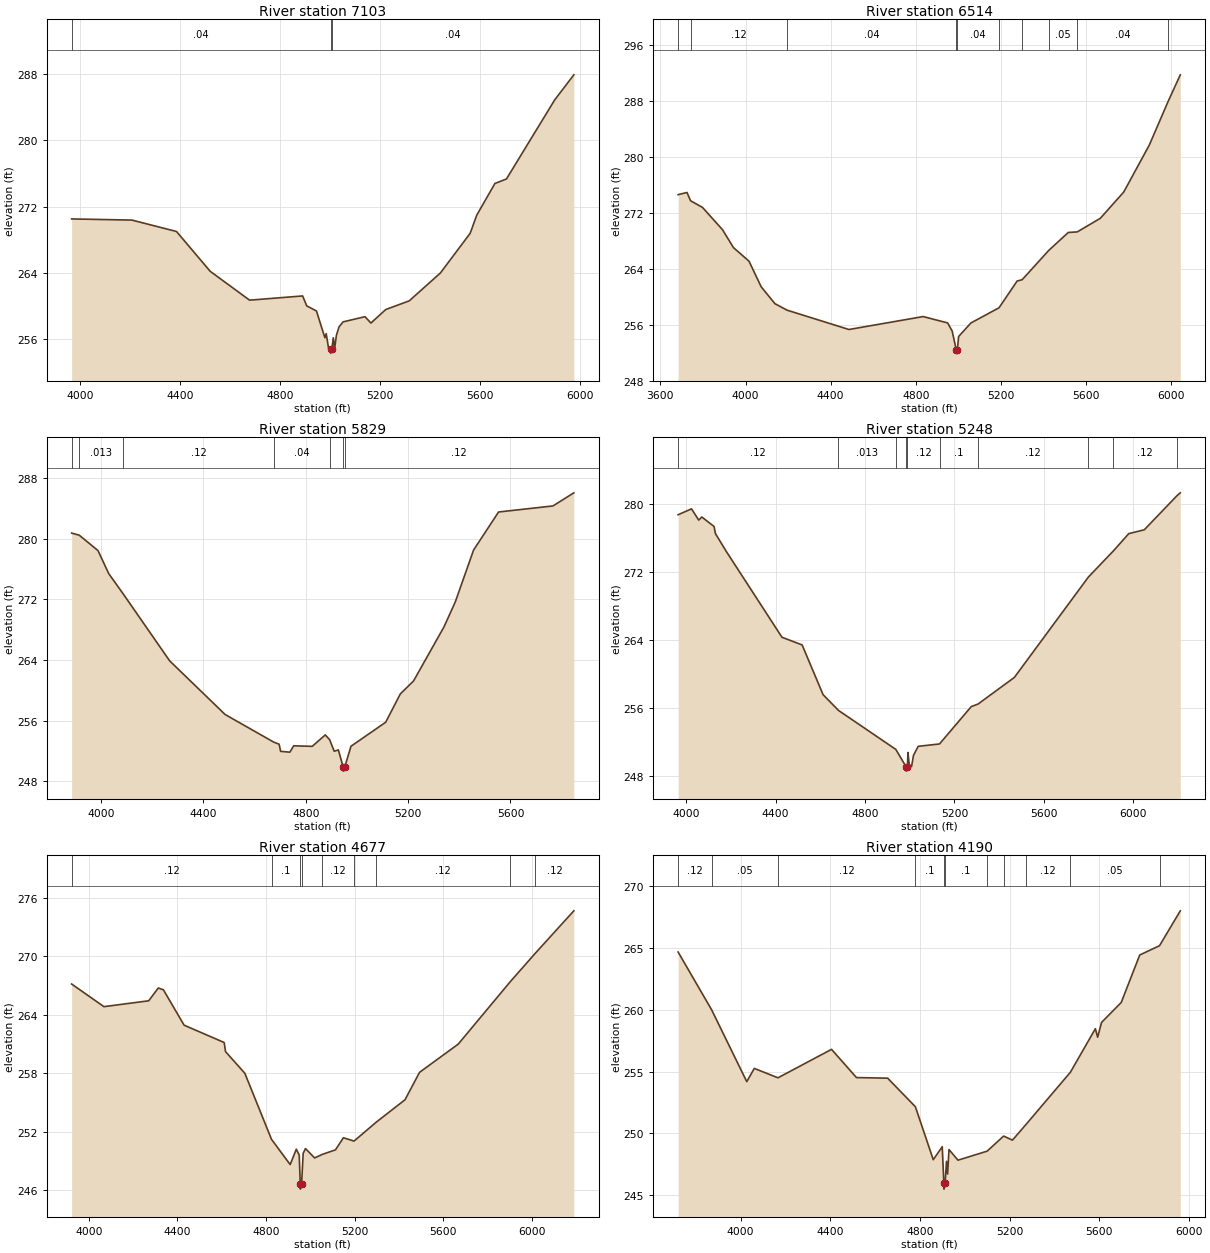
Type RM Length L Ch R = 1,7103,589,589,589
BEGIN DESCRIPTION:
Mapping XS ec9d027b
END DESCRIPTION:
XS GIS Cut Line= 3
      2537106.21     13614862.47      2536571.51     13614168.06
      2535481.23     13613855.56
#Sta/Elev= 30
  3965.7  270.50  4207.0  270.36  4385.5  268.98  4520.5  264.16  4678.1  260.67
  4890.5  261.18  4906.9  259.98  4945.8  259.36  4979.6  256.12  4984.8  256.62
  4994.5  254.83  5002.3  254.76  5002.7  254.26  5007.5  254.76  5013.3  256.12
  5018.5  254.81  5025.7  256.41  5036.1  257.43  5052.3  258.04  5140.2  258.67
  5163.9  257.90  5223.4  259.54  5317.0  260.58  5441.8  263.95  5561.2  268.76
  5587.5  270.95  5660.3  274.79  5706.6  275.34  5899.6  284.90  5976.3  287.94
#Mann=3,-1,0
  3965.7    0.04       0  5002.3    0.04       0  5007.5    0.04       0
Bank Sta=5002.3,5007.5
Exp/Cntr=0.3,0.1

Type RM Length L Ch R = 1,6514,685,685,685
BEGIN DESCRIPTION:
Mapping XS 365de282
END DESCRIPTION:
XS GIS Cut Line= 3
      2537647.88     13614320.82      2536474.29     13613570.84
      2535509.55     13613612.48
#Sta/Elev= 30
  3683.5  274.60  3725.3  274.91  3741.9  273.73  3798.1  272.77  3891.9  269.59
  3943.5  267.02  4016.3  265.09  4073.8  261.41  4137.9  259.01  4194.8  258.08
  4485.8  255.31  4834.3  257.16  4949.3  256.25  4970.5  255.09  4989.6  252.43
  4990.0  251.93  4995.0  252.43  5000.9  254.31  5058.4  256.24  5190.7  258.42
  5275.7  262.25  5299.2  262.43  5424.0  266.62  5515.8  269.19  5557.9  269.27
  5666.1  271.21  5776.2  274.97  5896.3  281.69  5984.2  287.90  6041.9  291.74
#Mann=10,-1,0
  3683.5   0.013       0  3741.9    0.12       0  4194.8    0.04       0
  4989.6    0.04       0  4995.0    0.04       0  5190.7    0.05       0
  5299.2    0.04       0  5424.0    0.05       0  5557.9    0.04       0
  5984.2    0.05       0
Bank Sta=4989.6,4995
Exp/Cntr=0.3,0.1

Type RM Length L Ch R = 1,5829,581,581,581
BEGIN DESCRIPTION:
Mapping XS 65d44b98
END DESCRIPTION:
XS GIS Cut Line= 3
      2537717.33     13614174.99      2537154.84     13613320.84
      2536329.73     13612870.15
#Sta/Elev= 30
  3884.9  280.75  3914.7  280.47  3987.9  278.44  4030.0  275.39  4086.3  272.73
  4268.0  263.89  4484.8  256.81  4675.2  253.16  4695.7  252.90  4701.7  251.95
  4737.8  251.84  4752.9  252.68  4825.2  252.61  4876.4  254.12  4893.4  253.48
  4911.3  251.96  4927.4  252.14  4946.5  249.84  4946.9  249.34  4952.0  249.84
  4976.7  252.62  5112.4  255.79  5169.5  259.52  5221.5  261.25  5340.4  268.38
  5384.7  271.69  5455.9  278.51  5553.6  283.53  5766.2  284.33  5847.8  286.06
#Mann=7,-1,0
  3884.9    0.12       0  3914.7   0.013       0  4086.3    0.12       0
  4675.2    0.04       0  4893.4    0.12       0  4946.5    0.05       0
  4952.0    0.12       0
Bank Sta=4946.5,4952
Exp/Cntr=0.3,0.1

Type RM Length L Ch R = 1,5248,571,571,571
BEGIN DESCRIPTION:
Mapping XS 8f26ede1
END DESCRIPTION:
XS GIS Cut Line= 4
      2537877.08     13614161.16      2537495.12     13613161.12
      2537113.18     13612890.28      2536411.80     13612786.12
#Sta/Elev= 30
  3963.3  278.70  4023.4  279.39  4055.5  278.07  4069.4  278.43  4124.2  277.32
  4130.5  276.48  4179.0  274.39  4428.2  264.32  4518.4  263.42  4612.2  257.58
  4680.9  255.74  4937.7  251.16  4983.9  249.11  4984.4  248.61  4989.6  249.11
  4992.1  250.80  4997.5  249.41  5008.2  249.14  5016.9  250.47  5037.9  251.52
  5133.3  251.80  5275.4  256.18  5306.3  256.49  5468.5  259.61  5799.5  271.38
  5911.5  274.45  5980.4  276.48  6049.8  276.93  6197.2  280.96  6211.1  281.27
#Mann=10,-1,0
  3963.3    0.12       0  4680.9   0.013       0  4937.7    0.12       0
  4983.9    0.05       0  4989.6    0.12       0  5133.3     0.1       0
  5306.3    0.12       0  5799.5    0.05       0  5911.5    0.12       0
  6197.2    0.05       0
Bank Sta=4983.9,4989.6
Exp/Cntr=0.3,0.1

Type RM Length L Ch R = 1,4677,487,487,487
BEGIN DESCRIPTION:
Mapping XS 836167ec
END DESCRIPTION:
XS GIS Cut Line= 4
      2538450.00     13613551.76      2538022.90     13612900.70
      2537470.82     13612760.07      2536554.12     13612718.41
#Sta/Elev= 30
  3922.6  267.16  4068.3  264.84  4270.3  265.44  4313.4  266.75  4336.6  266.57
  4430.0  262.94  4610.9  261.16  4616.9  260.23  4704.2  258.00  4824.4  251.23
  4908.6  248.64  4936.4  250.22  4949.5  249.60  4954.2  246.62  4954.6  246.12
  4960.0  246.62  4967.4  249.80  4977.7  250.28  5019.0  249.32  5054.4  249.69
  5113.1  250.15  5148.8  251.39  5196.8  251.05  5297.0  252.99  5426.9  255.29
  5492.4  258.10  5667.2  261.00  5900.6  267.37  6014.4  270.31  6188.6  274.67
#Mann=9,-1,0
  3922.6    0.12       0  4824.4     0.1       0  4954.2    0.05       0
  4960.0     0.1       0  5054.4    0.12       0  5196.8   0.013       0
  5297.0    0.12       0  5900.6    0.05       0  6014.4    0.12       0
Bank Sta=4954.2,4960
Exp/Cntr=0.3,0.1

Type RM Length L Ch R = 1,4190,353,353,353
BEGIN DESCRIPTION:
Mapping XS 6e015f15
END DESCRIPTION:
XS GIS Cut Line= 4
      2538897.88     13612921.52      2538038.52     13612484.03
      2537512.48     13612452.78      2536768.89     13612541.18
#Sta/Elev= 30
  3721.3  264.67  3871.3  259.98  4027.5  254.19  4061.2  255.26  4166.7  254.50
  4405.7  256.80  4516.9  254.52  4656.0  254.47  4779.7  252.16  4859.4  247.88
  4899.5  248.93  4906.6  246.00  4907.1  245.50  4912.4  246.00  4918.4  247.75
  4923.4  246.72  4929.6  248.70  4969.6  247.84  5099.7  248.57  5173.3  249.79
  5212.6  249.46  5272.3  250.71  5471.1  254.95  5582.6  258.47  5592.7  257.78
  5610.2  258.98  5697.9  260.59  5780.5  264.43  5868.7  265.18  5961.4  268.00
#Mann=11,-1,0
  3721.3    0.12       0  3871.3    0.05       0  4166.7    0.12       0
  4779.7     0.1       0  4906.6    0.05       0  4912.4     0.1       0
  5099.7    0.12       0  5173.3   0.013       0  5272.3    0.12       0
  5471.1    0.05       0  5868.7    0.12       0
Bank Sta=4906.6,4912.4
Exp/Cntr=0.3,0.1

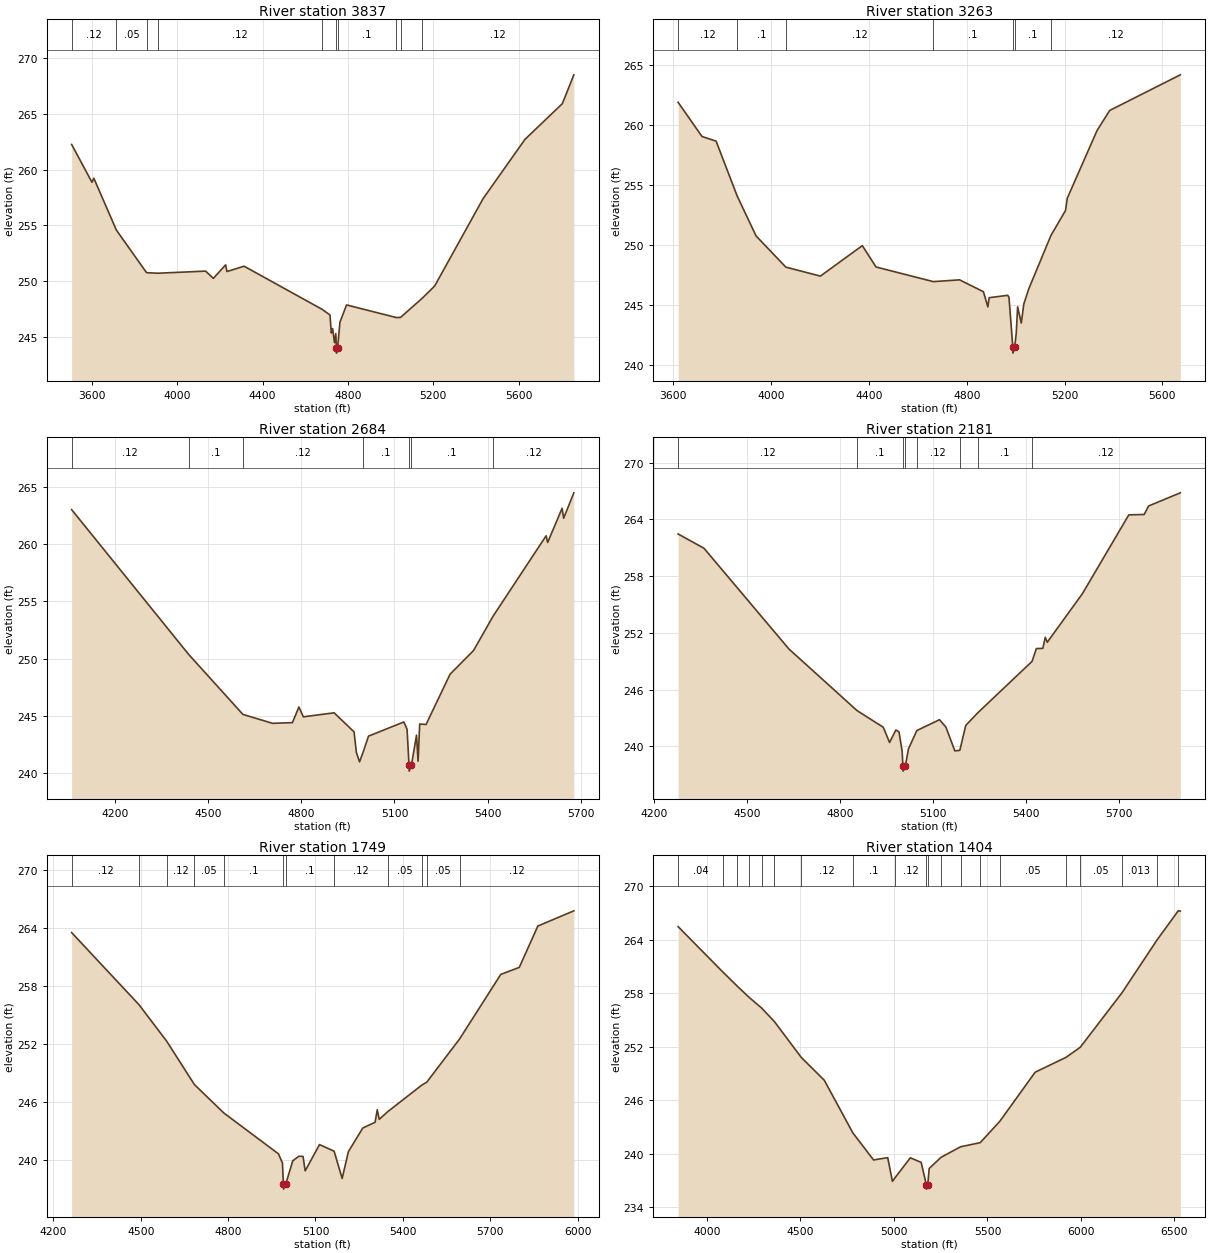
Type RM Length L Ch R = 1,3837,574,574,574
BEGIN DESCRIPTION:
Mapping XS 9e3d90d2
END DESCRIPTION:
XS GIS Cut Line= 3
      2538871.87     13612801.75      2537845.82     13612093.41
      2536772.87     13612369.46
#Sta/Elev= 30
  3504.3  262.25  3599.6  258.86  3608.4  259.22  3714.2  254.57  3855.6  250.76
  3908.1  250.71  4132.4  250.90  4168.8  250.25  4226.3  251.46  4232.4  250.86
  4312.8  251.34  4678.3  247.48  4715.6  246.97  4721.8  245.36  4727.9  245.75
  4736.7  244.49  4742.8  245.30  4745.6  244.05  4746.1  243.55  4751.5  244.05
  4762.3  246.32  4793.3  247.87  5026.4  246.74  5046.4  246.75  5148.8  248.48
  5206.3  249.56  5433.4  257.39  5629.6  262.70  5805.2  265.91  5859.0  268.49
#Mann=10,-1,0
  3504.3    0.12       0  3714.2    0.05       0  3855.6     0.1       0
  3908.1    0.12       0  4678.3     0.1       0  4745.6    0.05       0
  4751.5     0.1       0  5026.4    0.05       0  5046.4   0.013       0
  5148.8    0.12       0
Bank Sta=4745.6,4751.5
Exp/Cntr=0.3,0.1

Type RM Length L Ch R = 1,3263,579,579,579
BEGIN DESCRIPTION:
Mapping XS dc6e0db8
END DESCRIPTION:
XS GIS Cut Line= 3
      2538918.73     13612728.82      2538007.27     13612010.07
      2537783.31     13611145.47
#Sta/Elev= 30
  3619.6  261.87  3717.2  259.02  3775.0  258.63  3861.5  254.04  3938.5  250.73
  4060.1  248.13  4201.4  247.38  4373.0  249.92  4429.1  248.14  4663.6  246.92
  4770.6  247.07  4868.2  246.08  4886.4  244.81  4891.6  245.58  4967.6  245.78
  4972.8  245.61  4988.5  241.46  4989.0  240.96  4996.0  241.46  5002.5  242.62
  5008.2  244.82  5023.2  243.47  5033.5  245.06  5054.2  246.34  5144.7  250.78
  5204.0  252.85  5211.2  253.87  5333.1  259.52  5384.7  261.19  5673.5  264.16
#Mann=7,-1,0
  3619.6    0.12       0  3861.5     0.1       0  4060.1    0.12       0
  4663.6     0.1       0  4988.5    0.05       0  4996.0     0.1       0
  5144.7    0.12       0
Bank Sta=4988.5,4996
Exp/Cntr=0.3,0.1

Type RM Length L Ch R = 1,2684,503,503,503
BEGIN DESCRIPTION:
Mapping XS a5488d50
END DESCRIPTION:
XS GIS Cut Line= 3
      2538970.80     13612707.97      2538429.15     13612041.32
      2538283.66     13611298.28
#Sta/Elev= 30
  4061.2  263.02  4437.7  250.36  4612.4  245.11  4707.7  244.33  4771.7  244.39
  4792.5  245.76  4806.8  244.90  4906.0  245.25  4970.1  243.58  4977.5  241.78
  4987.7  240.96  4999.8  241.86  5016.5  243.21  5130.4  244.45  5140.6  243.81
  5147.0  240.65  5147.5  240.15  5154.5  240.65  5171.0  243.29  5176.1  241.02
  5181.3  244.27  5201.7  244.23  5279.1  248.63  5354.6  250.70  5417.4  253.70
  5588.0  260.73  5593.1  260.15  5639.5  263.14  5644.6  262.27  5677.3  264.49
#Mann=7,-1,0
  4061.2    0.12       0  4437.7     0.1       0  4612.4    0.12       0
  4999.8     0.1       0  5147.0    0.05       0  5154.5     0.1       0
  5417.4    0.12       0
Bank Sta=5147,5154.5
Exp/Cntr=0.3,0.1

Type RM Length L Ch R = 1,2181,432,432,432
BEGIN DESCRIPTION:
Mapping XS 5daa47a9
END DESCRIPTION:
XS GIS Cut Line= 3
      2539007.27     13612687.13      2538871.86     13611921.53
      2538335.38     13611270.47
#Sta/Elev= 30
  4277.2  262.45  4360.6  260.94  4634.8  250.29  4854.5  243.78  4939.5  242.01
  4959.8  240.40  4980.1  241.72  4990.2  241.52  5000.4  239.49  5002.9  237.87
  5003.4  237.37  5010.6  237.87  5020.7  239.72  5047.8  241.66  5121.0  242.81
  5141.8  242.02  5170.5  239.51  5186.6  239.57  5205.7  242.20  5244.3  243.53
  5419.8  248.98  5433.7  250.33  5454.5  250.35  5462.4  251.52  5468.9  251.00
  5582.2  256.13  5732.1  264.47  5781.6  264.51  5796.0  265.41  5898.3  266.80
#Mann=8,-1,0
  4277.2    0.12       0  4854.5     0.1       0  5002.9    0.05       0
  5010.6     0.1       0  5047.8    0.12       0  5186.6    0.05       0
  5244.3     0.1       0  5419.8    0.12       0
Bank Sta=5002.9,5010.6
Exp/Cntr=0.3,0.1

Type RM Length L Ch R = 1,1749,345,345,345
BEGIN DESCRIPTION:
Mapping XS a699c865
END DESCRIPTION:
XS GIS Cut Line= 3
      2539106.22     13612635.12      2539278.11     13611931.95
      2538586.34     13611208.97
#Sta/Elev= 30
  4262.8  263.49  4494.5  256.03  4589.0  252.28  4684.4  247.79  4785.2  244.86
  4973.2  240.63  4986.7  239.68  4990.0  237.49  4990.5  236.99  4997.7  237.49
  5022.2  239.92  5043.3  240.39  5057.4  240.37  5064.7  238.88  5114.0  241.59
  5164.1  240.91  5191.7  238.09  5213.1  240.86  5262.5  243.30  5304.9  243.90
  5312.2  245.19  5319.1  244.20  5347.7  244.98  5465.0  247.73  5482.3  248.04
  5594.9  252.50  5736.4  259.17  5800.0  259.90  5863.8  264.17  5987.3  265.74
#Mann=12,-1,0
  4262.8    0.12       0  4494.5    0.05       0  4589.0    0.12       0
  4684.4    0.05       0  4785.2     0.1       0  4990.0    0.05       0
  4997.7     0.1       0  5164.1    0.12       0  5347.7    0.05       0
  5465.0    0.12       0  5482.3    0.05       0  5594.9    0.12       0
Bank Sta=4990,4997.7
Exp/Cntr=0.3,0.1

Type RM Length L Ch R = 1,1404,678,678,678
BEGIN DESCRIPTION:
Mapping XS 28c83f63
END DESCRIPTION:
XS GIS Cut Line= 4
      2539220.81     13612796.54      2539663.52     13612077.78
      2539382.27     13611218.41      2538465.60     13611025.70
#Sta/Elev= 30
  3846.0  265.45  4083.8  260.39  4163.5  258.75  4226.6  257.50  4292.0  256.33
  4360.7  254.81  4504.7  250.78  4627.5  248.23  4780.1  242.33  4891.1  239.29
  4966.7  239.55  4991.9  236.89  5006.8  237.32  5087.5  239.53  5145.5  239.02
  5173.2  236.52  5173.7  236.02  5180.9  236.52  5188.3  238.33  5252.0  239.59
  5356.6  240.77  5461.3  241.23  5565.9  243.62  5755.1  249.13  5919.7  250.79
  5996.5  251.93  6219.5  258.04  6406.3  263.94  6520.0  267.22  6531.1  267.19
#Mann=20,-1,0
  3846.0    0.04       0  4083.8    0.05       0  4163.5    0.04       0
  4226.6    0.05       0  4292.0    0.12       0  4360.7    0.05       0
  4504.7    0.12       0  4780.1     0.1       0  5006.8    0.12       0
  5173.2    0.05       0  5180.9     0.1       0  5252.0   0.013       0
  5356.6     0.1       0  5461.3    0.12       0  5565.9    0.05       0
  5919.7    0.12       0  5996.5    0.05       0  6219.5   0.013       0
  6406.3    0.12       0  6520.0    0.05       0
Bank Sta=5173.2,5180.9
Exp/Cntr=0.3,0.1

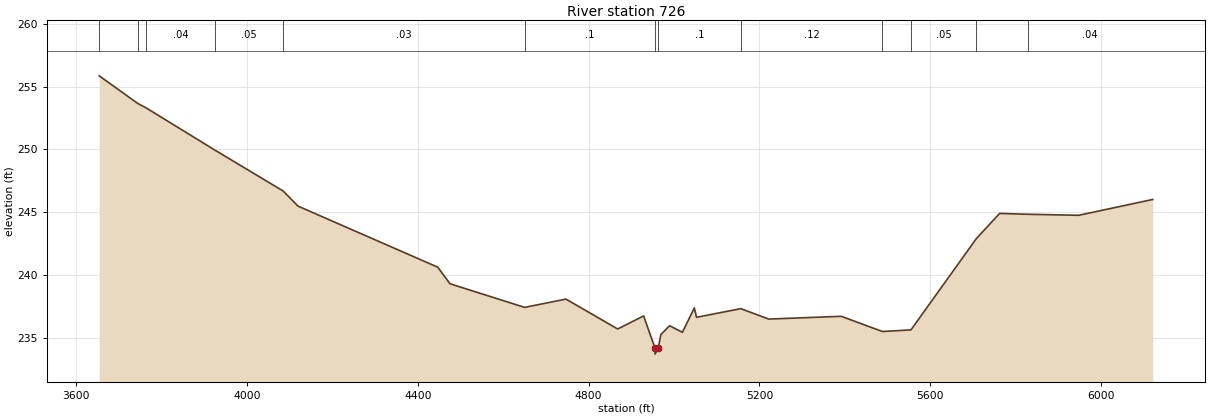
Type RM Length L Ch R = 1,726,0,0,0
BEGIN DESCRIPTION:
LGII4281
END DESCRIPTION:
XS GIS Cut Line= 4
      2539546.18     13612601.75      2540145.14     13611872.58
      2540040.97     13611156.44      2539402.95     13610674.66
#Sta/Elev= 30
  3654.1  255.85  3744.0  253.66  3763.9  253.30  3924.4  249.95  4084.9  246.68
  4119.6  245.48  4446.8  240.62  4475.5  239.30  4650.2  237.42  4746.9  238.08
  4868.1  235.70  4928.8  236.74  4955.2  234.20  4955.7  233.70  4963.0  234.20
  4969.2  235.25  4989.4  235.96  5019.7  235.44  5047.6  237.38  5052.7  236.63
  5156.3  237.32  5221.8  236.49  5391.5  236.71  5488.0  235.50  5554.8  235.63
  5707.8  242.89  5762.4  244.90  5828.0  244.83  5947.6  244.75  6120.9  246.01
#Mann=13,-1,0
  3654.1    0.04       0  3744.0    0.05       0  3763.9    0.04       0
  3924.4    0.05       0  4084.9    0.03       0  4650.2     0.1       0
  4955.2    0.05       0  4963.0     0.1       0  5156.3    0.12       0
  5488.0     0.1       0  5554.8    0.05       0  5707.8    0.12       0
  5828.0    0.04       0
Bank Sta=4955.2,4963
Exp/Cntr=0.3,0.1

Chan Stop Cuts=-1