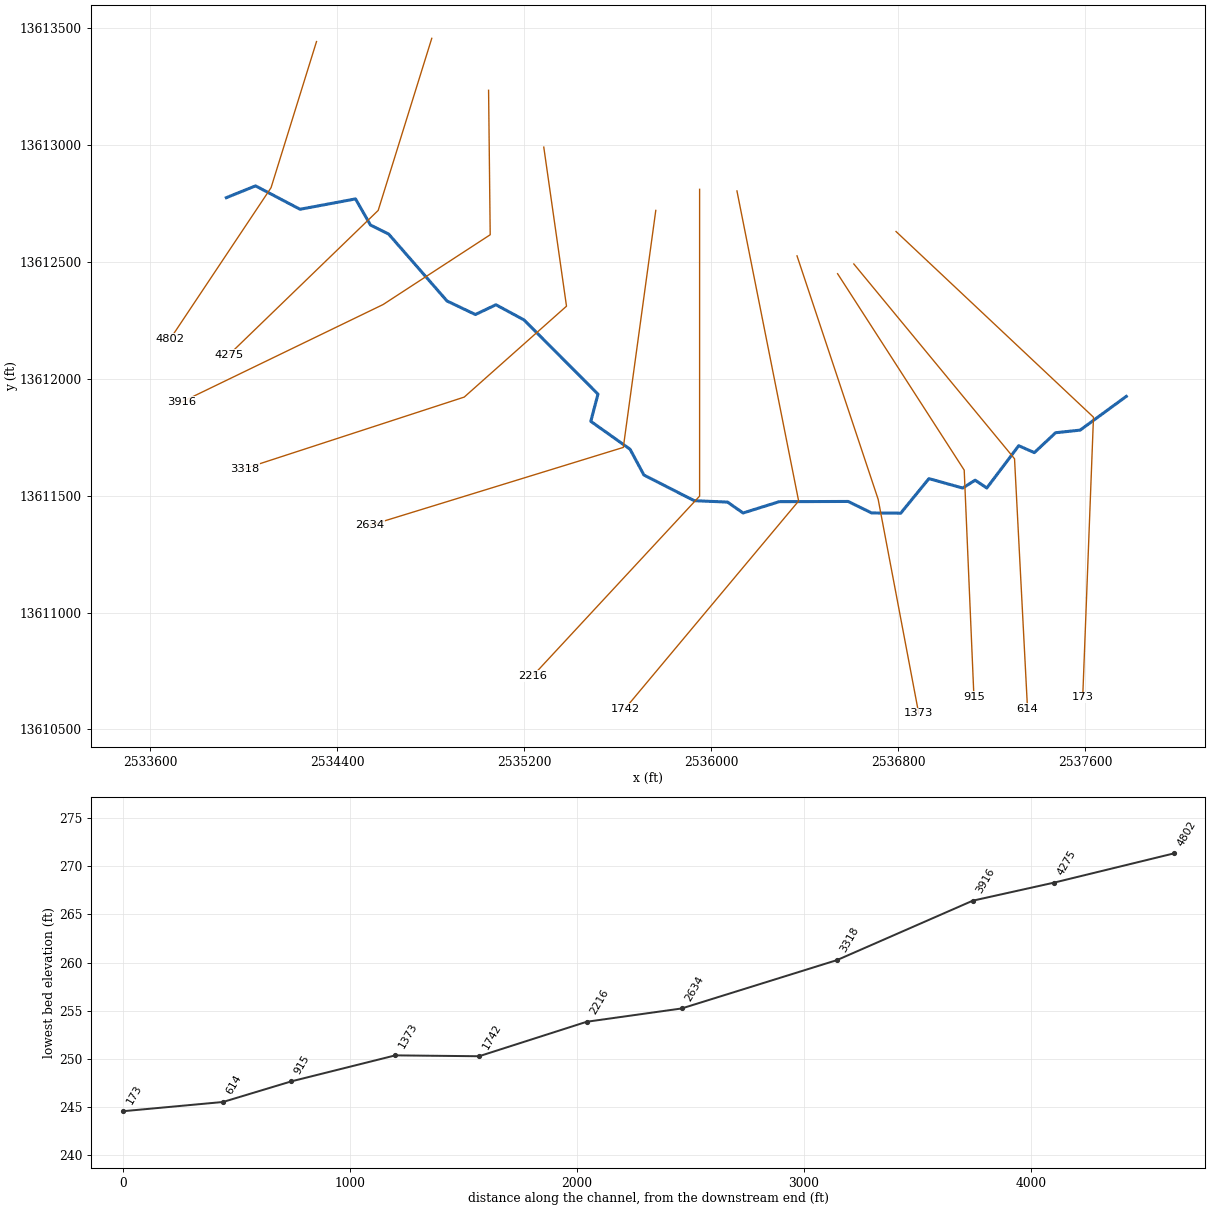
--- TRIB 14_1 TO IRISH CREEK.prj (project) ---

Proj Title=TRIB 14_1 TO IRISH CREEK Base Level Engineering
Current Plan=p01
Default Exp/Contr=0.3,0.1
English Units
Geom File=g01
Flow File=f01
Plan File=p01
Y Axis Title=Elevation
X Axis Title(PF)=Main Channel Distance
X Axis Title(XS)=Station
BEGIN DESCRIPTION:
TRIB 14_1 TO IRISH CREEK
END DESCRIPTION:
DSS Export Rating Curves= 0
DSS Export Rating Curve Sorted= 0
DSS Export Volume Flow Curves= 0
DXF OffsetX= 0
DXF OffsetY= 0
DXF ScaleX= 1
DXF ScaleY= 10

--- TRIB 14_1 TO IRISH CREEK.p01 (plan) ---

Plan Title=Multiple Run
Short Identifier=Multiple
Geom File=g01
Flow File=f01
Subcritical Flow
K Sum by GR= 0
Std Step Tol= 0.01
Critical Tol= 0.01
Num of Std Step Trials= 20
Max Error Tol= 0.3
Flow Tol Ratio= 0.001
Split Flow NTrial= 30
Split Flow Tol= 0.02
Split Flow Ratio= 0.02
Log Output Level= 0
Friction Slope Method= 1
Unsteady Friction Slope Method= 2
Unsteady Bridges Friction Slope Method= 1
Parabolic Critical Depth
Global Vel Dist=  1 , 1 , 1
Global Log Level= 0
CheckData=True
Encroach Param= -1, 0, 0, 0
BEGIN DESCRIPTION:
Multiple Run
END DESCRIPTION:

--- TRIB 14_1 TO IRISH CREEK.f01 (steady flow) ---

Flow Title=Multiple
Number of Profiles=7
Profile Names=10-year,25-year,50-year,1pct_min,100-year,1pct_plu,500-year
River Rch & RM= TRIB 14_1 TO IRI,Reach-1,4802
     572     920    1234     804    1603    3199    2677
River Rch & RM= TRIB 14_1 TO IRI,Reach-1,1373
     599     963    1292     841    1678    3348    2800
Boundary for River Rch & Prof#=TRIB 14_1 TO IRI,Reach-1,1
Up Type=0
Dn Type=3
Dn Slope=0.005
Boundary for River Rch & Prof#=TRIB 14_1 TO IRI,Reach-1,2
Up Type=0
Dn Type=3
Dn Slope=0.005
Boundary for River Rch & Prof#=TRIB 14_1 TO IRI,Reach-1,3
Up Type=0
Dn Type=3
Dn Slope=0.005
Boundary for River Rch & Prof#=TRIB 14_1 TO IRI,Reach-1,4
Up Type=0
Dn Type=3
Dn Slope=0.005
Boundary for River Rch & Prof#=TRIB 14_1 TO IRI,Reach-1,5
Up Type=0
Dn Type=3
Dn Slope=0.005
Boundary for River Rch & Prof#=TRIB 14_1 TO IRI,Reach-1,6
Up Type=0
Dn Type=3
Dn Slope=0.005
Boundary for River Rch & Prof#=TRIB 14_1 TO IRI,Reach-1,7
Up Type=0
Dn Type=3
Dn Slope=0.005

--- TRIB 14_1 TO IRISH CREEK.g01 (geometry) ---

Geom Title=Existing Conditions

River Reach=TRIB 14_1 TO IRI,Reach-1
Reach XY= 30
      2533925.00     13612775.00      2534050.01     13612825.48
      2534240.27     13612725.37      2534477.67     13612769.70
      2534541.58     13612658.00      2534619.35     13612619.37
      2534868.94     13612333.14      2534990.41     13612275.14
      2535078.31     13612316.93      2535198.47     13612252.00
      2535514.80     13611934.68      2535484.14     13611818.25
      2535652.14     13611698.83      2535711.44     13611588.48
      2535926.56     13611478.76      2536069.06     13611472.73
      2536135.55     13611426.10      2536290.22     13611474.48
      2536585.19     13611475.45      2536685.51     13611426.21
      2536809.96     13611425.31      2536930.71     13611573.11
      2537075.10     13611532.79      2537128.34     13611566.43
      2537178.35     13611532.98      2537314.68     13611713.89
      2537381.65     13611684.33      2537472.57     13611769.45
      2537577.42     13611780.54      2537775.00     13611925.00

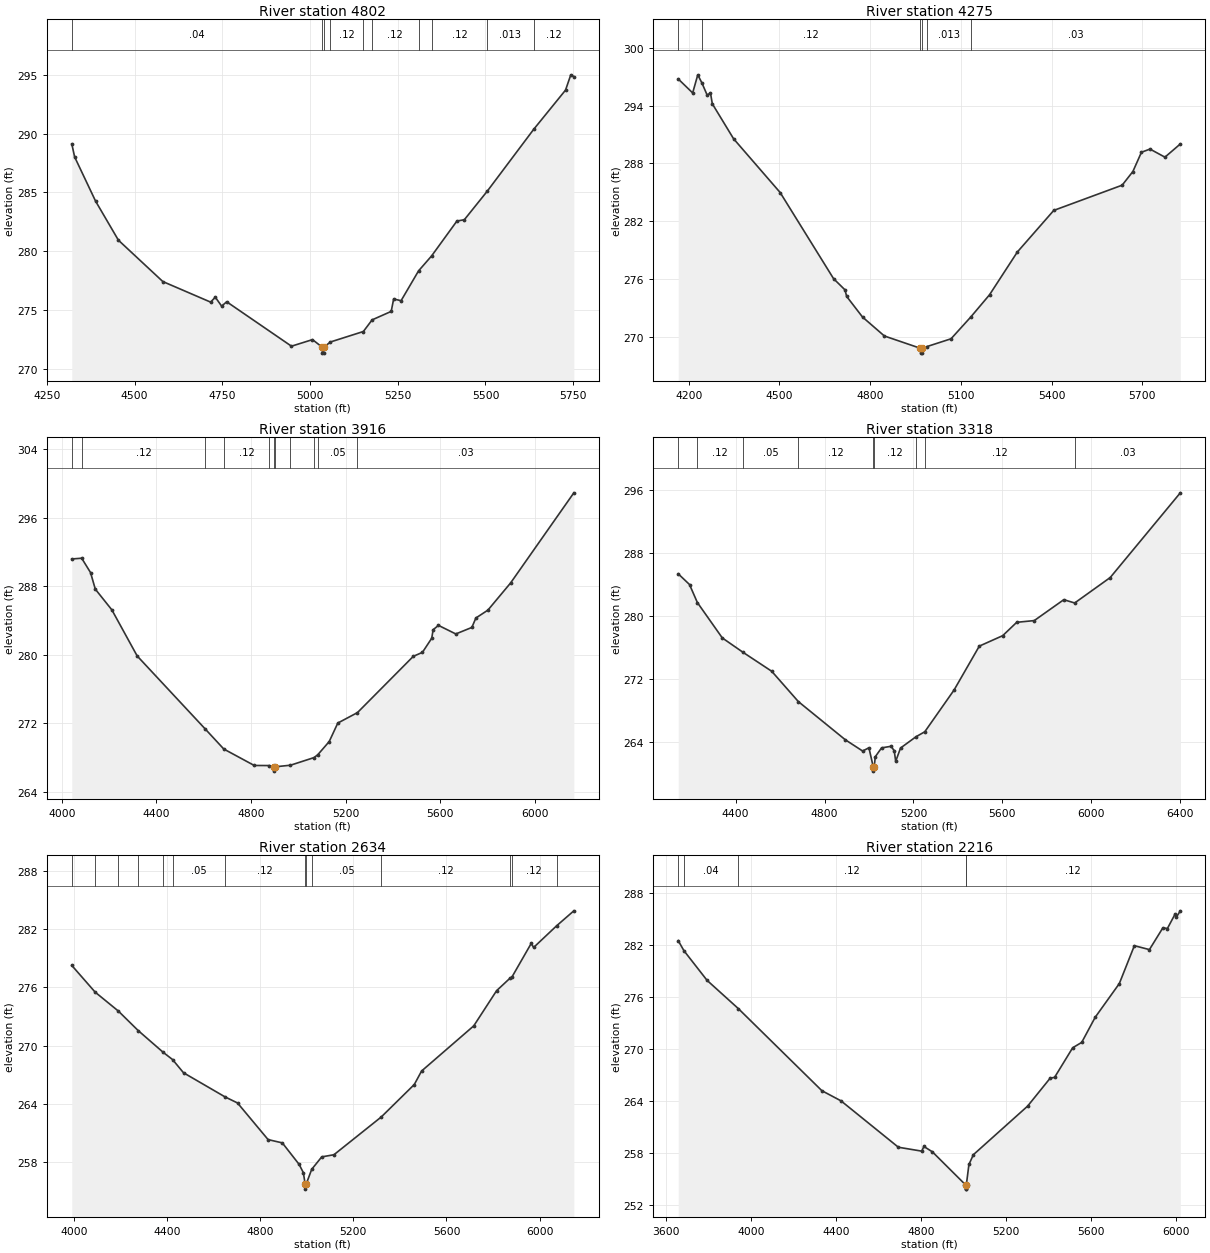
Type RM Length L Ch R = 1,4802,527,527,527
BEGIN DESCRIPTION:
Mapping XS 5a3271f4
END DESCRIPTION:
XS GIS Cut Line= 3
      2534310.77     13613442.81      2534116.32     13612817.76
      2533685.75     13612171.92
#Sta/Elev= 30
  4321.1  289.14  4329.3  288.02  4389.0  284.26  4454.0  280.94  4580.6  277.42
  4716.8  275.67  4730.1  276.09  4748.2  275.33  4762.6  275.70  4947.2  271.92
  5007.1  272.48  5035.1  271.83  5035.4  271.33  5038.9  271.33  5039.1  271.83
  5058.4  272.28  5152.1  273.17  5177.0  274.16  5231.4  274.88  5238.4  275.94
  5259.5  275.79  5309.4  278.33  5346.5  279.60  5418.7  282.57  5439.8  282.68
  5504.9  285.10  5637.4  290.37  5728.2  293.71  5743.2  295.01  5751.9  294.86
#Mann=10,-1,0
  4321.1    0.04       0  5035.1    0.04       0  5039.1    0.04       0
  5058.4    0.12       0  5152.1   0.013       0  5177.0    0.12       0
  5309.4   0.013       0  5346.5    0.12       0  5504.9   0.013       0
  5637.4    0.12       0
Bank Sta=5035.1,5039.1
Exp/Cntr=0.3,0.1

Type RM Length L Ch R = 1,4275,359,359,359
BEGIN DESCRIPTION:
Mapping XS b2f0fee2
END DESCRIPTION:
XS GIS Cut Line= 3
      2534803.82     13613456.65      2534574.65     13612720.54
      2533935.75     13612102.47
#Sta/Elev= 30
  4165.5  296.77  4213.2  295.32  4230.1  297.20  4243.6  296.37  4261.5  295.07
  4272.0  295.34  4278.2  294.19  4348.5  290.56  4502.4  284.98  4679.1  276.03
  4716.8  274.87  4722.3  274.19  4774.7  272.05  4847.0  270.08  4966.4  268.80
  4966.6  268.30  4970.1  268.30  4970.4  268.80  4986.7  268.97  5067.4  269.79
  5132.6  272.05  5194.7  274.36  5286.6  278.80  5407.0  283.12  5633.1  285.74
  5668.6  287.16  5696.9  289.16  5725.2  289.49  5774.6  288.65  5825.4  290.02
#Mann=6,-1,0
  4165.5    0.04       0  4243.6    0.12       0  4966.4    0.03       0
  4970.4    0.12       0  4986.7   0.013       0  5132.6    0.03       0
Bank Sta=4966.4,4970.4
Exp/Cntr=0.3,0.1

Type RM Length L Ch R = 1,3916,598,598,598
BEGIN DESCRIPTION:
Mapping XS d7db7dcc
END DESCRIPTION:
XS GIS Cut Line= 4
      2535046.87     13613234.43      2535053.82     13612616.37
      2534595.48     13612317.76      2533734.41     13611901.11
#Sta/Elev= 30
  4042.1  291.18  4084.0  291.27  4121.5  289.59  4141.5  287.66  4211.5  285.24
  4318.5  279.86  4605.7  271.35  4684.5  269.00  4813.2  267.08  4877.1  267.07
  4895.6  266.92  4895.8  266.42  4899.6  266.92  4966.3  267.11  5065.8  268.00
  5081.6  268.33  5130.0  269.87  5166.3  272.03  5249.4  273.25  5485.5  279.82
  5523.9  280.28  5563.3  281.93  5569.1  282.92  5591.7  283.43  5665.0  282.43
  5732.8  283.19  5749.8  284.29  5800.6  285.21  5896.5  288.38  6163.8  298.90
#Mann=11,-1,0
  4042.1    0.03       0  4084.0    0.12       0  4605.7    0.05       0
  4684.5    0.12       0  4877.1   0.013       0  4895.6    0.05       0
  4899.6   0.013       0  4966.3    0.05       0  5065.8    0.12       0
  5081.6    0.05       0  5249.4    0.03       0
Bank Sta=4895.6,4899.6
Exp/Cntr=0.3,0.1

Type RM Length L Ch R = 1,3318,684,684,684
BEGIN DESCRIPTION:
Mapping XS 63234193
END DESCRIPTION:
XS GIS Cut Line= 4
      2535282.99     13612991.35      2535380.20     13612310.82
      2534942.70     13611921.93      2534005.24     13611616.38
#Sta/Elev= 30
  4141.9  285.36  4192.6  284.00  4227.9  281.71  4340.2  277.20  4433.5  275.37
  4562.5  272.96  4682.3  269.10  4893.6  264.24  4971.4  262.81  4999.8  263.22
  5019.6  260.75  5019.8  260.25  5023.6  260.75  5028.3  262.08  5056.7  263.21
  5099.4  263.41  5113.6  262.85  5120.3  261.50  5142.0  263.19  5211.8  264.63
  5251.1  265.26  5382.8  270.57  5496.4  276.16  5601.6  277.49  5664.7  279.19
  5743.6  279.41  5876.5  282.07  5925.5  281.65  6085.4  284.89  6400.7  295.67
#Mann=9,-1,0
  4141.9    0.04       0  4227.9    0.12       0  4433.5    0.05       0
  4682.3    0.12       0  5019.6    0.05       0  5023.6    0.12       0
  5211.8   0.013       0  5251.1    0.12       0  5925.5    0.03       0
Bank Sta=5019.6,5023.6
Exp/Cntr=0.3,0.1

Type RM Length L Ch R = 1,2634,418,418,418
BEGIN DESCRIPTION:
Mapping XS 58016900
END DESCRIPTION:
XS GIS Cut Line= 3
      2535762.15     13612720.53      2535623.26     13611706.65
      2534539.93     13611373.32
#Sta/Elev= 30
  3990.5  278.26  4090.9  275.51  4190.7  273.56  4275.5  271.56  4383.9  269.30
  4423.4  268.57  4470.5  267.21  4649.3  264.72  4702.6  264.10  4833.8  260.33
  4895.0  259.99  4967.1  257.78  4985.2  256.93  4993.3  255.73  4993.6  255.23
  4997.3  255.73  5021.2  257.27  5064.3  258.55  5116.7  258.77  5320.1  262.66
  5461.9  266.00  5493.3  267.39  5717.4  272.04  5815.5  275.66  5874.2  276.97
  5880.5  277.03  5964.1  280.52  5974.6  280.11  6073.8  282.35  6147.3  283.88
#Mann=14,-1,0
  3990.5    0.05       0  4090.9    0.04       0  4190.7    0.12       0
  4275.5    0.05       0  4383.9    0.12       0  4423.4    0.05       0
  4649.3    0.12       0  4993.3    0.05       0  4997.3    0.12       0
  5021.2    0.05       0  5320.1    0.12       0  5874.2    0.05       0
  5880.5    0.12       0  6073.8    0.05       0
Bank Sta=4993.3,4997.3
Exp/Cntr=0.3,0.1

Type RM Length L Ch R = 1,2216,474,474,474
BEGIN DESCRIPTION:
Mapping XS 8b5e201a
END DESCRIPTION:
XS GIS Cut Line= 3
      2535949.65     13612810.77      2535949.65     13611498.32
      2535235.55     13610728.75
#Sta/Elev= 30
  3659.1  282.50  3686.0  281.34  3794.9  277.92  3941.7  274.67  4334.9  265.20
  4424.9  264.03  4694.9  258.68  4804.9  258.23  4814.9  258.77  4854.9  258.15
  5010.7  254.35  5010.9  253.85  5014.4  253.85  5014.7  254.35  5026.8  256.69
  5047.8  257.82  5302.9  263.42  5408.9  266.64  5429.9  266.74  5515.0  270.15
  5557.5  270.77  5621.0  273.67  5734.4  277.55  5805.2  281.92  5876.1  281.47
  5939.6  283.99  5960.6  283.90  5996.3  285.54  6003.1  285.22  6021.4  285.94
#Mann=5,-1,0
  3659.1    0.05       0  3686.0    0.04       0  3941.7    0.12       0
  5010.7    0.05       0  5014.7    0.12       0
Bank Sta=5010.7,5014.7
Exp/Cntr=0.3,0.1

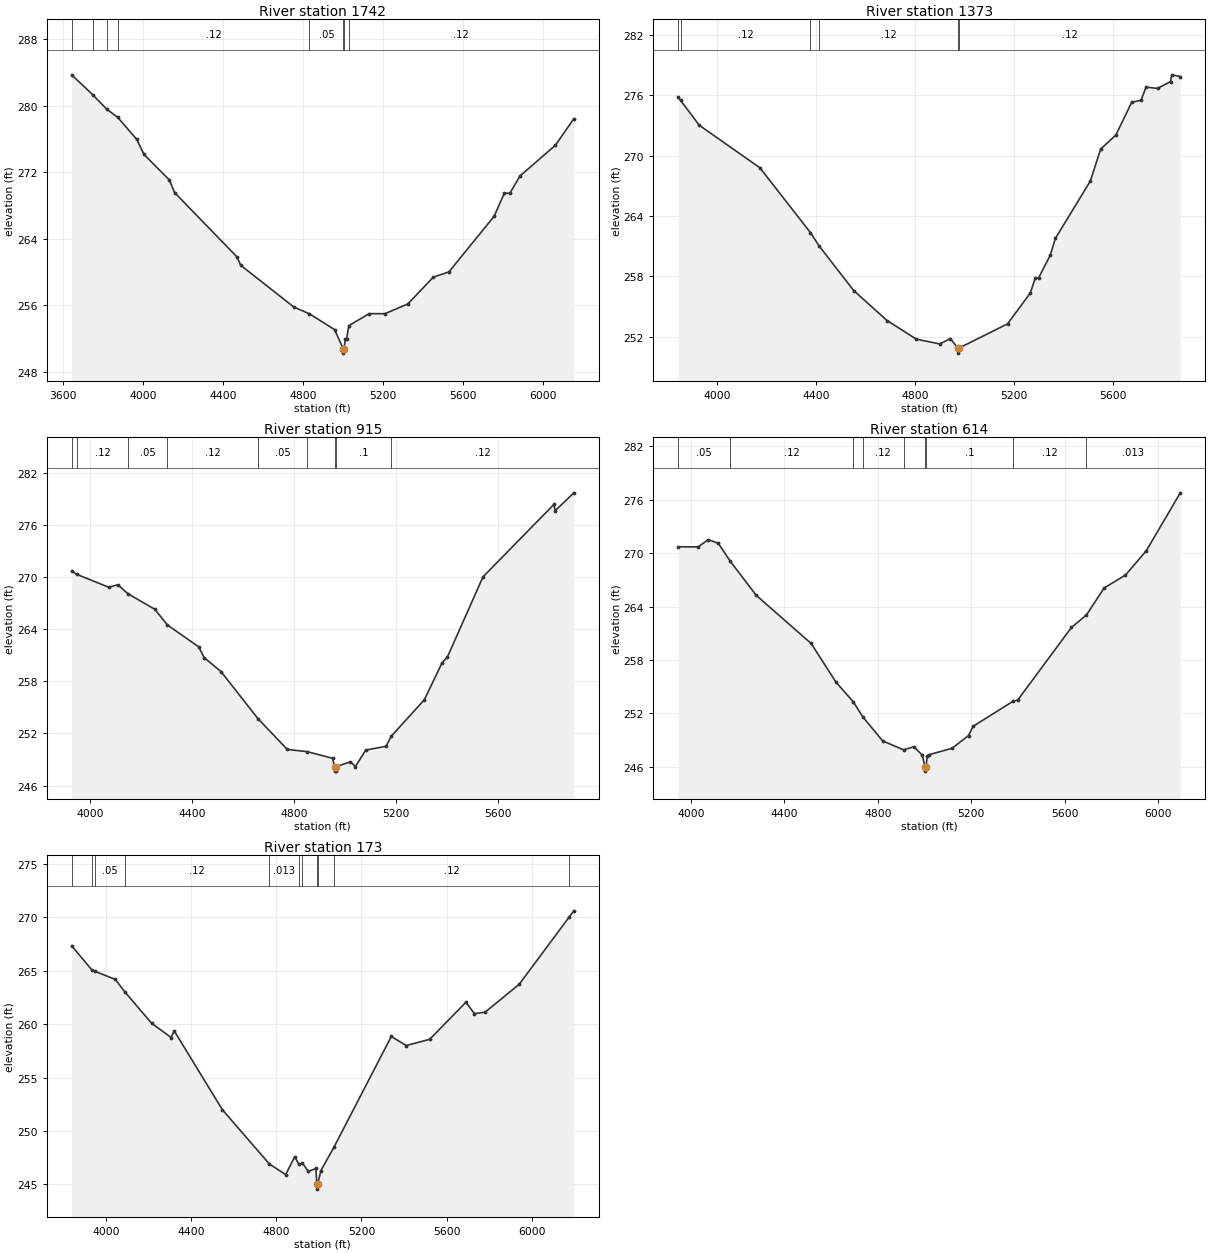
Type RM Length L Ch R = 1,1742,369,369,369
BEGIN DESCRIPTION:
Mapping XS 92d2e58a
END DESCRIPTION:
XS GIS Cut Line= 3
      2536109.37     13612803.88      2536373.26     13611477.48
      2535630.81     13610589.32
#Sta/Elev= 30
  3644.5  283.75  3751.0  281.33  3819.6  279.62  3875.5  278.62  3969.6  275.99
  4005.9  274.18  4132.8  271.10  4159.2  269.58  4471.0  261.84  4489.6  260.84
  4754.7  255.82  4833.2  255.00  4958.6  253.10  5002.3  250.77  5002.6  250.27
  5006.3  250.77  5012.1  251.97  5018.6  251.99  5030.1  253.58  5131.8  255.02
  5209.9  255.01  5324.4  256.18  5452.0  259.41  5530.0  260.04  5756.5  266.75
  5807.2  269.51  5834.6  269.50  5885.3  271.58  6062.3  275.28  6154.5  278.47
#Mann=8,-1,0
  3644.5    0.05       0  3751.0    0.04       0  3819.6    0.05       0
  3875.5    0.12       0  4833.2    0.05       0  5002.3    0.05       0
  5006.3    0.05       0  5030.1    0.12       0
Bank Sta=5002.3,5006.3
Exp/Cntr=0.3,0.1

Type RM Length L Ch R = 1,1373,458,458,458
BEGIN DESCRIPTION:
Mapping XS 51e98b85
END DESCRIPTION:
XS GIS Cut Line= 3
      2536366.30     13612526.14      2536713.54     13611484.43
      2536886.94     13610568.86
#Sta/Elev= 30
  3841.0  275.81  3850.9  275.48  3926.5  273.01  4171.6  268.78  4375.8  262.34
  4411.9  260.98  4551.1  256.57  4685.5  253.60  4804.0  251.75  4898.9  251.27
  4941.3  251.81  4971.9  250.86  4972.2  250.36  4975.9  250.86  5172.6  253.27
  5264.2  256.32  5284.5  257.81  5298.0  257.83  5345.2  260.09  5365.9  261.76
  5507.3  267.47  5549.1  270.65  5610.2  272.03  5674.4  275.29  5712.0  275.49
  5732.3  276.80  5779.0  276.67  5831.3  277.35  5836.4  278.02  5870.9  277.85
#Mann=6,-1,0
  3841.0    0.05       0  3850.9    0.12       0  4375.8    0.05       0
  4411.9    0.12       0  4971.9    0.05       0  4975.9    0.12       0
Bank Sta=4971.9,4975.9
Exp/Cntr=0.3,0.1

Type RM Length L Ch R = 1,915,301,301,301
BEGIN DESCRIPTION:
Mapping XS 88ad41cd
END DESCRIPTION:
XS GIS Cut Line= 3
      2536539.95     13612449.68      2537081.59     13611609.43
      2537123.20     13610638.62
#Sta/Elev= 30
  3927.4  270.69  3948.6  270.29  4072.5  268.82  4108.8  269.10  4148.4  268.07
  4254.0  266.28  4303.3  264.48  4426.3  261.96  4447.4  260.73  4514.1  259.10
  4658.8  253.70  4774.1  250.15  4852.5  249.90  4951.5  249.14  4959.6  248.16
  4959.8  247.66  4963.3  247.66  4963.6  248.16  5021.6  248.73  5041.6  248.19
  5081.7  250.08  5161.7  250.52  5181.9  251.67  5311.9  255.87  5381.9  260.14
  5402.0  260.76  5542.1  270.01  5820.7  278.35  5825.7  277.63  5898.8  279.68
#Mann=9,-1,0
  3927.4    0.05       0  3948.6    0.12       0  4148.4    0.05       0
  4303.3    0.12       0  4658.8    0.05       0  4852.5     0.1       0
  4959.6    0.05       0  4963.6     0.1       0  5181.9    0.12       0
Bank Sta=4959.6,4963.6
Exp/Cntr=0.3,0.1

Type RM Length L Ch R = 1,614,441,441,441
BEGIN DESCRIPTION:
Mapping XS 21245eef
END DESCRIPTION:
XS GIS Cut Line= 3
      2536609.36     13612491.39      2537296.87     13611658.04
      2537352.39     13610589.32
#Sta/Elev= 30
  3945.0  270.71  4031.1  270.70  4074.1  271.52  4117.1  271.10  4168.8  269.07
  4279.9  265.25  4514.5  259.86  4621.3  255.50  4695.3  253.30  4735.7  251.62
  4820.7  248.92  4910.4  247.91  4954.8  248.26  4990.4  247.32  5002.3  246.02
  5002.6  245.52  5006.3  246.02  5012.2  247.19  5018.7  247.36  5118.5  248.09
  5188.6  249.52  5208.6  250.56  5379.6  253.37  5398.9  253.49  5629.2  261.65
  5693.7  263.06  5769.4  266.09  5860.6  267.53  5949.6  270.26  6095.5  276.77
#Mann=9,-1,0
  3945.0    0.05       0  4168.8    0.12       0  4695.3    0.05       0
  4735.7    0.12       0  4910.4     0.1       0  5002.3    0.05       0
  5006.3     0.1       0  5379.6    0.12       0  5693.7   0.013       0
Bank Sta=5002.3,5006.3
Exp/Cntr=0.3,0.1

Type RM Length L Ch R = 1,173,0,0,0
BEGIN DESCRIPTION:
TRIB 14_1 TO IRISH CREEK 1.0
END DESCRIPTION:
XS GIS Cut Line= 3
      2536789.94     13612630.24      2537634.63     13611835.89
      2537588.59     13610638.60
#Sta/Elev= 30
  3839.4  267.33  3935.6  265.03  3950.6  264.92  4044.8  264.17  4090.2  262.98
  4214.7  260.08  4306.5  258.74  4320.7  259.37  4546.9  251.99  4767.8  246.91
  4844.3  245.92  4886.7  247.59  4906.5  246.87  4922.9  246.99  4950.3  246.22
  4985.7  246.49  4990.7  245.06  4991.0  244.56  4994.7  245.06  5009.8  246.30
  5072.1  248.53  5340.1  258.84  5410.1  257.99  5520.2  258.57  5690.3  262.04
  5730.4  260.98  5780.4  261.11  5940.5  263.72  6176.4  270.04  6197.1  270.59
#Mann=11,-1,0
  3839.4    0.05       0  3935.6    0.12       0  3950.6    0.05       0
  4090.2    0.12       0  4767.8   0.013       0  4906.5    0.05       0
  4922.9     0.1       0  4990.7    0.05       0  4994.7     0.1       0
  5072.1    0.12       0  6176.4    0.03       0
Bank Sta=4990.7,4994.7
Exp/Cntr=0.3,0.1

Chan Stop Cuts=-1