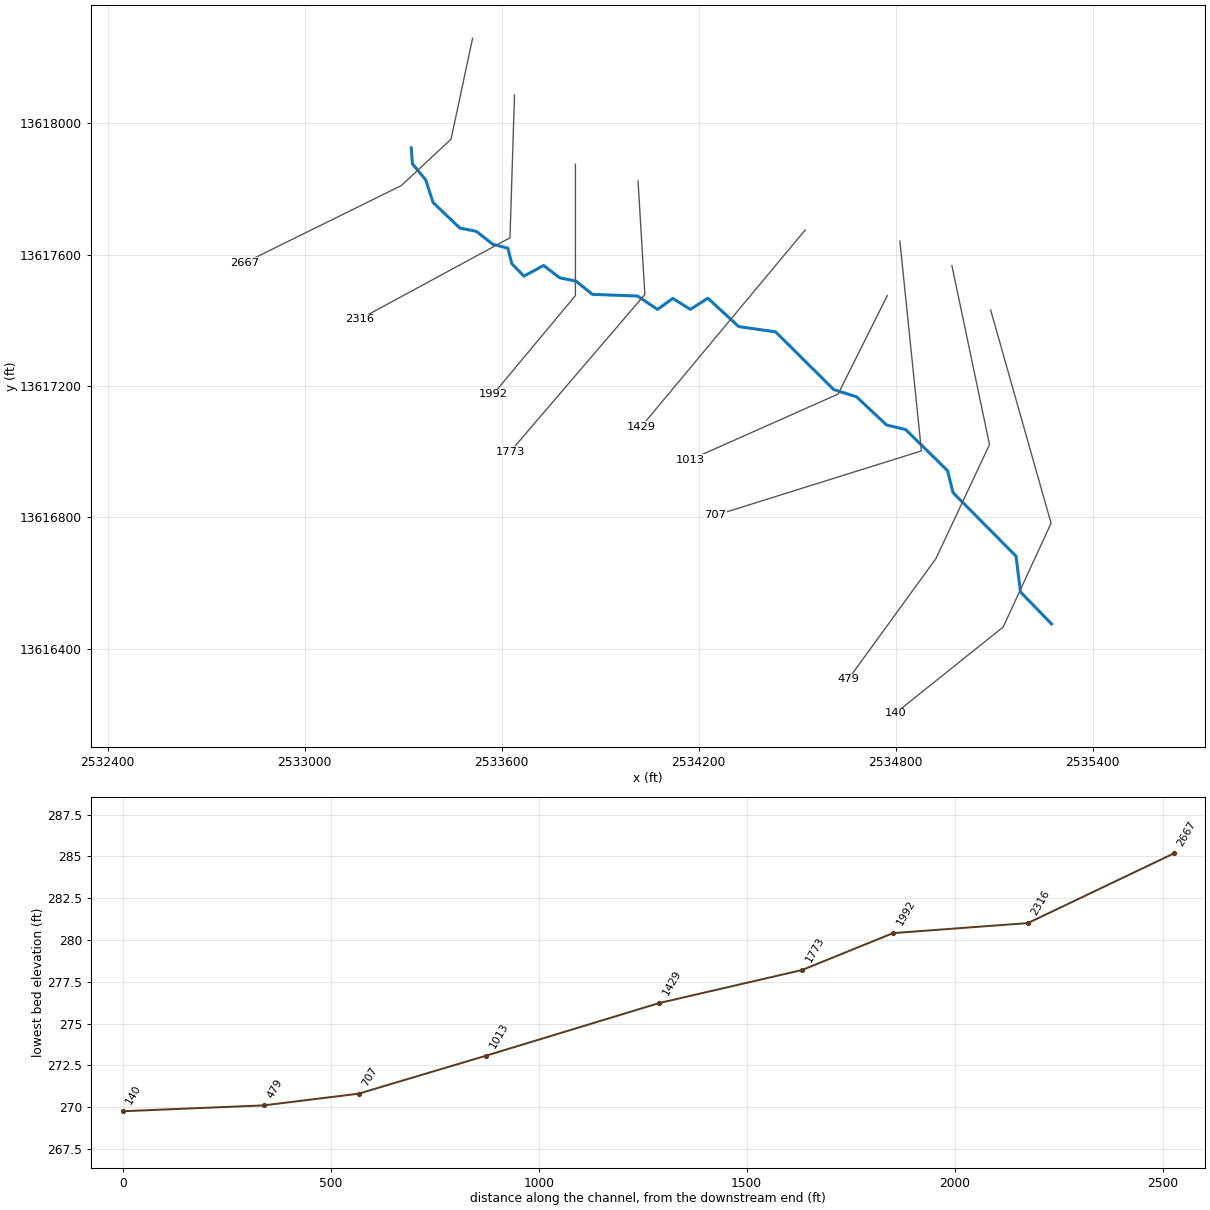
--- TRIB 14_2 TO IRISH CREEK.prj (project) ---

Proj Title=TRIB 14_2 TO IRISH CREEK Base Level Engineering
Current Plan=p01
Default Exp/Contr=0.3,0.1
English Units
Geom File=g01
Flow File=f01
Plan File=p01
Y Axis Title=Elevation
X Axis Title(PF)=Main Channel Distance
X Axis Title(XS)=Station
BEGIN DESCRIPTION:
TRIB 14_2 TO IRISH CREEK
END DESCRIPTION:
DSS Export Rating Curves= 0
DSS Export Rating Curve Sorted= 0
DSS Export Volume Flow Curves= 0
DXF OffsetX= 0
DXF OffsetY= 0
DXF ScaleX= 1
DXF ScaleY= 10

--- TRIB 14_2 TO IRISH CREEK.p01 (plan) ---

Plan Title=Multiple Run
Short Identifier=Multiple
Geom File=g01
Flow File=f01
Subcritical Flow
K Sum by GR= 0
Std Step Tol= 0.01
Critical Tol= 0.01
Num of Std Step Trials= 20
Max Error Tol= 0.3
Flow Tol Ratio= 0.001
Split Flow NTrial= 30
Split Flow Tol= 0.02
Split Flow Ratio= 0.02
Log Output Level= 0
Friction Slope Method= 1
Unsteady Friction Slope Method= 2
Unsteady Bridges Friction Slope Method= 1
Parabolic Critical Depth
Global Vel Dist=  1 , 1 , 1
Global Log Level= 0
CheckData=True
Encroach Param= -1, 0, 0, 0
BEGIN DESCRIPTION:
Multiple Run
END DESCRIPTION:

--- TRIB 14_2 TO IRISH CREEK.f01 (steady flow) ---

Flow Title=Multiple
Number of Profiles=7
Profile Names=10-year,25-year,50-year,1pct_min,100-year,1pct_plu,500-year
River Rch & RM= TRIB 14_2 TO IRI,Reach-1,2667
     343     528     688     435     868    1733    1367
River Rch & RM= TRIB 14_2 TO IRI,Reach-1,479
     415     647     850     542    1081    2157    1728
Boundary for River Rch & Prof#=TRIB 14_2 TO IRI,Reach-1,1
Up Type=0
Dn Type=3
Dn Slope=0.005
Boundary for River Rch & Prof#=TRIB 14_2 TO IRI,Reach-1,2
Up Type=0
Dn Type=3
Dn Slope=0.005
Boundary for River Rch & Prof#=TRIB 14_2 TO IRI,Reach-1,3
Up Type=0
Dn Type=3
Dn Slope=0.005
Boundary for River Rch & Prof#=TRIB 14_2 TO IRI,Reach-1,4
Up Type=0
Dn Type=3
Dn Slope=0.005
Boundary for River Rch & Prof#=TRIB 14_2 TO IRI,Reach-1,5
Up Type=0
Dn Type=3
Dn Slope=0.005
Boundary for River Rch & Prof#=TRIB 14_2 TO IRI,Reach-1,6
Up Type=0
Dn Type=3
Dn Slope=0.005
Boundary for River Rch & Prof#=TRIB 14_2 TO IRI,Reach-1,7
Up Type=0
Dn Type=3
Dn Slope=0.005

--- TRIB 14_2 TO IRISH CREEK.g01 (geometry) ---

Geom Title=Existing Conditions

River Reach=TRIB 14_2 TO IRI,Reach-1
Reach XY= 30
      2533325.00     13617925.00      2533328.60     13617876.49
      2533369.02     13617827.24      2533391.62     13617758.29
      2533472.69     13617680.83      2533523.29     13617670.82
      2533573.15     13617631.24      2533619.39     13617619.34
      2533630.99     13617572.50      2533668.07     13617534.22
      2533728.22     13617566.75      2533776.63     13617529.41
      2533827.17     13617518.91      2533876.56     13617478.76
      2534014.56     13617473.61      2534075.10     13617432.78
      2534121.67     13617466.46      2534175.00     13617433.03
      2534228.33     13617467.00      2534322.57     13617380.55
      2534434.79     13617364.48      2534611.79     13617188.63
      2534681.04     13617166.82      2534772.72     13617080.87
      2534831.05     13617066.84      2534958.42     13616941.70
      2534975.00     13616875.00      2535167.14     13616681.17
      2535180.46     13616572.55      2535275.00     13616475.00

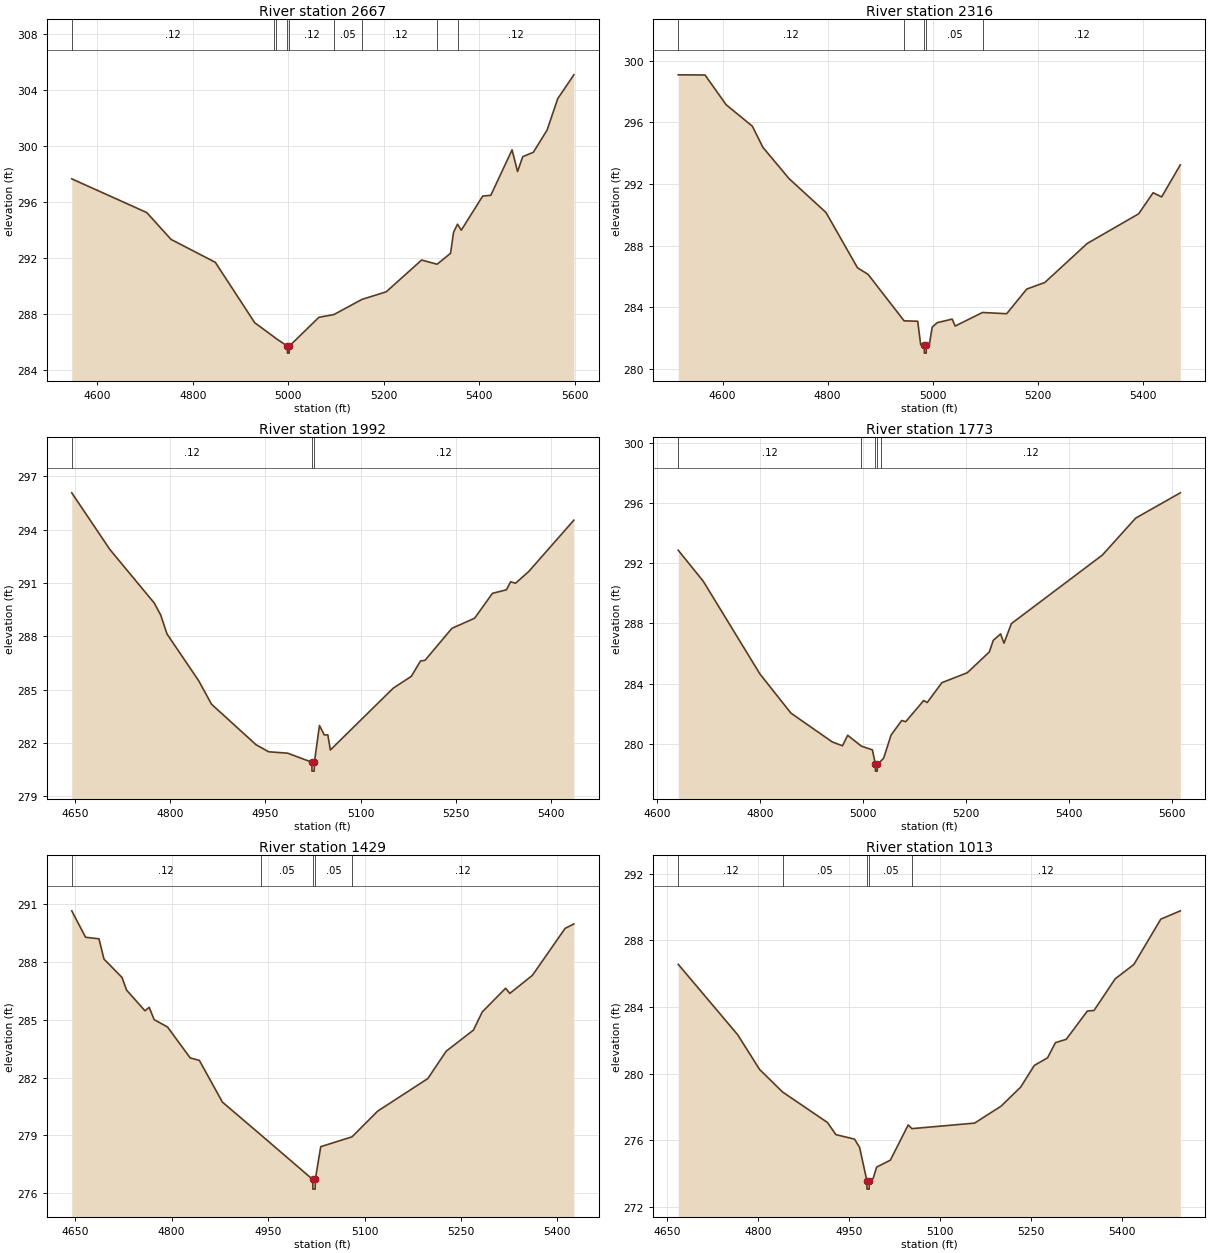
Type RM Length L Ch R = 1,2667,351,351,351
BEGIN DESCRIPTION:
Mapping XS e104c72a
END DESCRIPTION:
XS GIS Cut Line= 4
      2533511.77     13618258.53      2533446.19     13617951.33
      2533294.29     13617809.79      2532818.91     13617575.55
#Sta/Elev= 30
  4546.5  297.63  4703.6  295.22  4754.6  293.30  4847.1  291.67  4929.8  287.35
  4970.1  286.34  4973.6  286.24  4998.2  285.68  4998.4  285.18  5001.9  285.18
  5002.2  285.68  5064.2  287.74  5095.4  287.93  5154.5  289.02  5205.2  289.56
  5279.3  291.83  5311.8  291.53  5339.9  292.31  5346.2  293.81  5354.5  294.39
  5362.4  293.96  5407.3  296.40  5424.2  296.45  5468.8  299.70  5480.3  298.15
  5491.1  299.21  5513.4  299.53  5542.1  301.11  5564.5  303.36  5598.2  305.06
#Mann=9,-1,0
  4546.5    0.12       0  4970.1    0.05       0  4973.6    0.12       0
  4998.2    0.05       0  5002.2    0.12       0  5095.4    0.05       0
  5154.5    0.12       0  5311.8    0.05       0  5354.5    0.12       0
Bank Sta=4998.2,5002.2
Exp/Cntr=0.3,0.1

Type RM Length L Ch R = 1,2316,324,324,324
BEGIN DESCRIPTION:
Mapping XS 16926859
END DESCRIPTION:
XS GIS Cut Line= 3
      2533639.51     13618086.01      2533625.70     13617650.99
      2533168.26     13617403.36
#Sta/Elev= 30
  4515.7  299.09  4566.7  299.08  4606.8  297.15  4656.8  295.75  4676.8  294.38
  4726.8  292.34  4796.8  290.15  4856.9  286.55  4876.9  286.13  4945.5  283.11
  4971.4  283.08  4977.1  281.55  4983.8  281.51  4984.1  281.01  4987.6  281.01
  4987.8  281.51  4993.3  281.52  4999.0  282.70  5008.6  282.99  5037.0  283.22
  5042.7  282.77  5094.7  283.65  5140.7  283.57  5178.8  285.17  5213.3  285.60
  5293.8  288.13  5391.8  290.06  5419.4  291.43  5435.6  291.16  5471.1  293.24
#Mann=5,-1,0
  4515.7    0.12       0  4945.5    0.05       0  4983.8    0.05       0
  4987.8    0.05       0  5094.7    0.12       0
Bank Sta=4983.8,4987.8
Exp/Cntr=0.3,0.1

Type RM Length L Ch R = 1,1992,219,219,219
BEGIN DESCRIPTION:
TRIB 14_2 TO IRISH CREEK 4.0
END DESCRIPTION:
XS GIS Cut Line= 3
      2533825.00     13617874.98      2533825.00     13617475.00
      2533574.99     13617174.99
#Sta/Elev= 30
  4645.0  296.08  4705.0  292.89  4775.0  289.87  4785.0  289.20  4795.0  288.13
  4845.0  285.49  4865.0  284.18  4935.0  281.90  4955.0  281.50  4985.0  281.42
  5023.0  280.91  5023.2  280.41  5026.7  280.41  5027.0  280.91  5035.0  282.98
  5042.5  282.45  5048.2  282.45  5052.1  281.60  5151.1  285.08  5179.7  285.75
  5194.0  286.61  5201.2  286.65  5243.5  288.45  5279.3  289.02  5307.3  290.42
  5329.4  290.62  5335.9  291.07  5343.7  290.99  5364.5  291.65  5435.5  294.54
#Mann=3,-1,0
  4645.0    0.12       0  5023.0    0.05       0  5027.0    0.12       0
Bank Sta=5023,5027
Exp/Cntr=0.3,0.1

Type RM Length L Ch R = 1,1773,344,344,344
BEGIN DESCRIPTION:
Mapping XS 012ef53d
END DESCRIPTION:
XS GIS Cut Line= 3
      2534015.80     13617823.64      2534036.51     13617478.38
      2533626.98     13617000.02
#Sta/Elev= 30
  4641.2  292.86  4689.9  290.80  4800.1  284.64  4860.2  282.05  4940.4  280.14
  4960.4  279.88  4970.4  280.58  4997.0  279.86  5018.5  279.61  5024.1  278.70
  5024.4  278.20  5027.9  278.20  5028.1  278.70  5034.4  278.85  5040.4  279.06
  5054.7  280.59  5075.5  281.56  5083.2  281.48  5118.3  282.89  5124.9  282.75
  5153.5  284.07  5202.9  284.73  5245.7  286.11  5253.4  286.88  5267.6  287.31
  5274.2  286.69  5288.5  287.99  5465.4  292.54  5530.0  294.99  5616.8  296.67
#Mann=5,-1,0
  4641.2    0.12       0  4997.0    0.05       0  5024.1    0.05       0
  5028.1    0.05       0  5034.4    0.12       0
Bank Sta=5024.1,5028.1
Exp/Cntr=0.3,0.1

Type RM Length L Ch R = 1,1429,416,416,416
BEGIN DESCRIPTION:
TRIB 14_2 TO IRISH CREEK 3.0
END DESCRIPTION:
XS GIS Cut Line= 3
      2534525.00     13617675.00      2534275.00     13617375.00
      2534025.02     13617075.02
#Sta/Elev= 30
  4644.6  290.64  4666.1  289.27  4686.9  289.19  4694.7  288.14  4722.7  287.19
  4729.9  286.53  4758.5  285.46  4765.0  285.64  4772.8  285.00  4793.6  284.62
  4828.8  283.02  4843.1  282.89  4878.9  280.73  4938.4  279.04  5019.4  276.72
  5019.7  276.22  5023.2  276.22  5023.4  276.72  5031.9  278.42  5080.6  278.93
  5120.4  280.26  5198.5  281.95  5227.1  283.37  5269.4  284.46  5283.1  285.40
  5319.5  286.63  5326.0  286.36  5361.2  287.30  5412.0  289.73  5425.6  289.96
#Mann=5,-1,0
  4644.6    0.12       0  4938.4    0.05       0  5019.4    0.05       0
  5023.4    0.05       0  5080.6    0.12       0
Bank Sta=5019.4,5023.4
Exp/Cntr=0.3,0.1

Type RM Length L Ch R = 1,1013,306,306,306
BEGIN DESCRIPTION:
TRIB 14_2 TO IRISH CREEK 2.0
END DESCRIPTION:
XS GIS Cut Line= 3
      2534775.01     13617475.02      2534625.00     13617175.00
      2534174.98     13616974.99
#Sta/Elev= 30
  4668.9  286.56  4766.8  282.34  4803.1  280.25  4840.9  278.90  4914.9  277.07
  4928.9  276.34  4959.6  276.07  4968.0  275.57  4980.0  273.57  4980.2  273.07
  4983.7  273.07  4984.0  273.57  4990.4  273.72  4996.0  274.39  5018.7  274.81
  5048.1  276.92  5054.2  276.70  5157.5  277.03  5201.3  278.05  5233.5  279.19
  5256.0  280.49  5277.9  280.95  5290.9  281.86  5308.7  282.06  5343.6  283.76
  5354.5  283.79  5389.4  285.69  5420.2  286.55  5464.6  289.27  5496.8  289.77
#Mann=5,-1,0
  4668.9    0.12       0  4840.9    0.05       0  4980.0    0.05       0
  4984.0    0.05       0  5054.2    0.12       0
Bank Sta=4980,4984
Exp/Cntr=0.3,0.1

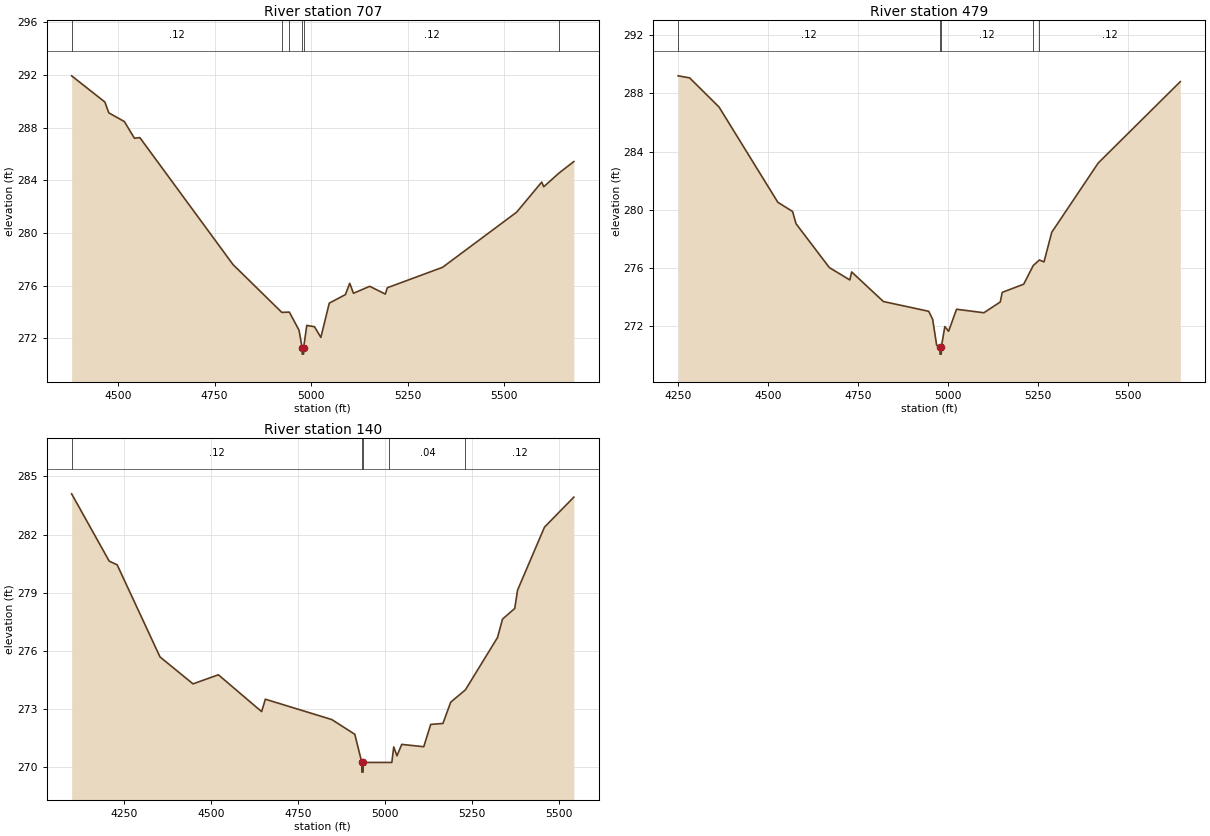
Type RM Length L Ch R = 1,707,228,228,228
BEGIN DESCRIPTION:
Mapping XS 6d63de3b
END DESCRIPTION:
XS GIS Cut Line= 3
      2534813.25     13617640.68      2534878.85     13617001.98
      2534250.51     13616805.19
#Sta/Elev= 30
  4379.8  291.93  4465.9  289.94  4476.0  289.12  4516.2  288.46  4542.5  287.19
  4556.4  287.24  4797.7  277.60  4924.0  273.97  4943.6  273.99  4968.6  272.62
  4976.6  271.30  4976.9  270.80  4980.4  270.80  4980.6  271.30  4988.7  272.98
  5008.8  272.88  5025.2  272.07  5046.9  274.67  5088.8  275.32  5099.9  276.18
  5109.7  275.42  5151.6  275.95  5192.1  275.36  5197.3  275.84  5340.3  277.39
  5532.3  281.58  5597.1  283.86  5602.4  283.51  5642.4  284.56  5680.3  285.42
#Mann=6,-1,0
  4379.8    0.12       0  4924.0    0.05       0  4943.6    0.12       0
  4976.6    0.05       0  4980.6    0.12       0  5642.4   0.013       0
Bank Sta=4976.6,4980.6
Exp/Cntr=0.3,0.1

Type RM Length L Ch R = 1,479,339,339,339
BEGIN DESCRIPTION:
4822
END DESCRIPTION:
XS GIS Cut Line= 4
      2534971.67     13617566.28      2535086.25     13617021.18
      2534923.06     13616673.96      2534655.69     13616305.89
#Sta/Elev= 30
  4249.5  289.20  4281.5  289.06  4363.2  287.06  4526.7  280.52  4567.6  279.89
  4577.2  279.05  4669.8  276.04  4726.7  275.19  4731.8  275.74  4820.0  273.71
  4945.9  273.04  4956.9  272.49  4968.0  270.71  4977.1  270.60  4977.3  270.10
  4980.8  270.10  4981.1  270.60  4990.7  271.99  5001.2  271.67  5023.3  273.18
  5099.2  272.94  5144.8  273.68  5150.3  274.34  5209.9  274.90  5236.4  276.18
  5253.4  276.56  5266.3  276.43  5287.8  278.46  5417.1  283.22  5645.1  288.80
#Mann=5,-1,0
  4249.5    0.12       0  4977.1    0.05       0  4981.1    0.12       0
  5236.4    0.04       0  5253.4    0.12       0
Bank Sta=4977.1,4981.1
Exp/Cntr=0.3,0.1

Type RM Length L Ch R = 1,140,0,0,0
BEGIN DESCRIPTION:
4821
END DESCRIPTION:
XS GIS Cut Line= 4
      2535089.72     13617430.91      2535273.75     13616781.60
      2535127.92     13616465.63      2534799.01     13616202.50
#Sta/Elev= 30
  4098.6  284.10  4206.6  280.63  4229.5  280.44  4352.7  275.69  4447.7  274.30
  4520.5  274.77  4644.9  272.87  4655.6  273.51  4846.8  272.46  4912.9  271.70
  4932.9  270.25  4933.2  269.75  4936.7  269.75  4936.9  270.25  5012.1  270.25
  5019.3  270.25  5024.8  271.05  5034.1  270.59  5047.8  271.18  5111.1  271.06
  5131.1  272.21  5166.3  272.26  5188.7  273.36  5230.8  273.99  5323.2  276.69
  5337.6  277.64  5372.8  278.19  5380.8  279.13  5458.2  282.38  5542.7  283.93
#Mann=5,-1,0
  4098.6    0.12       0  4932.9    0.05       0  4936.9    0.12       0
  5012.1    0.04       0  5230.8    0.12       0
Bank Sta=4932.9,4936.9
Exp/Cntr=0.3,0.1

Chan Stop Cuts=-1