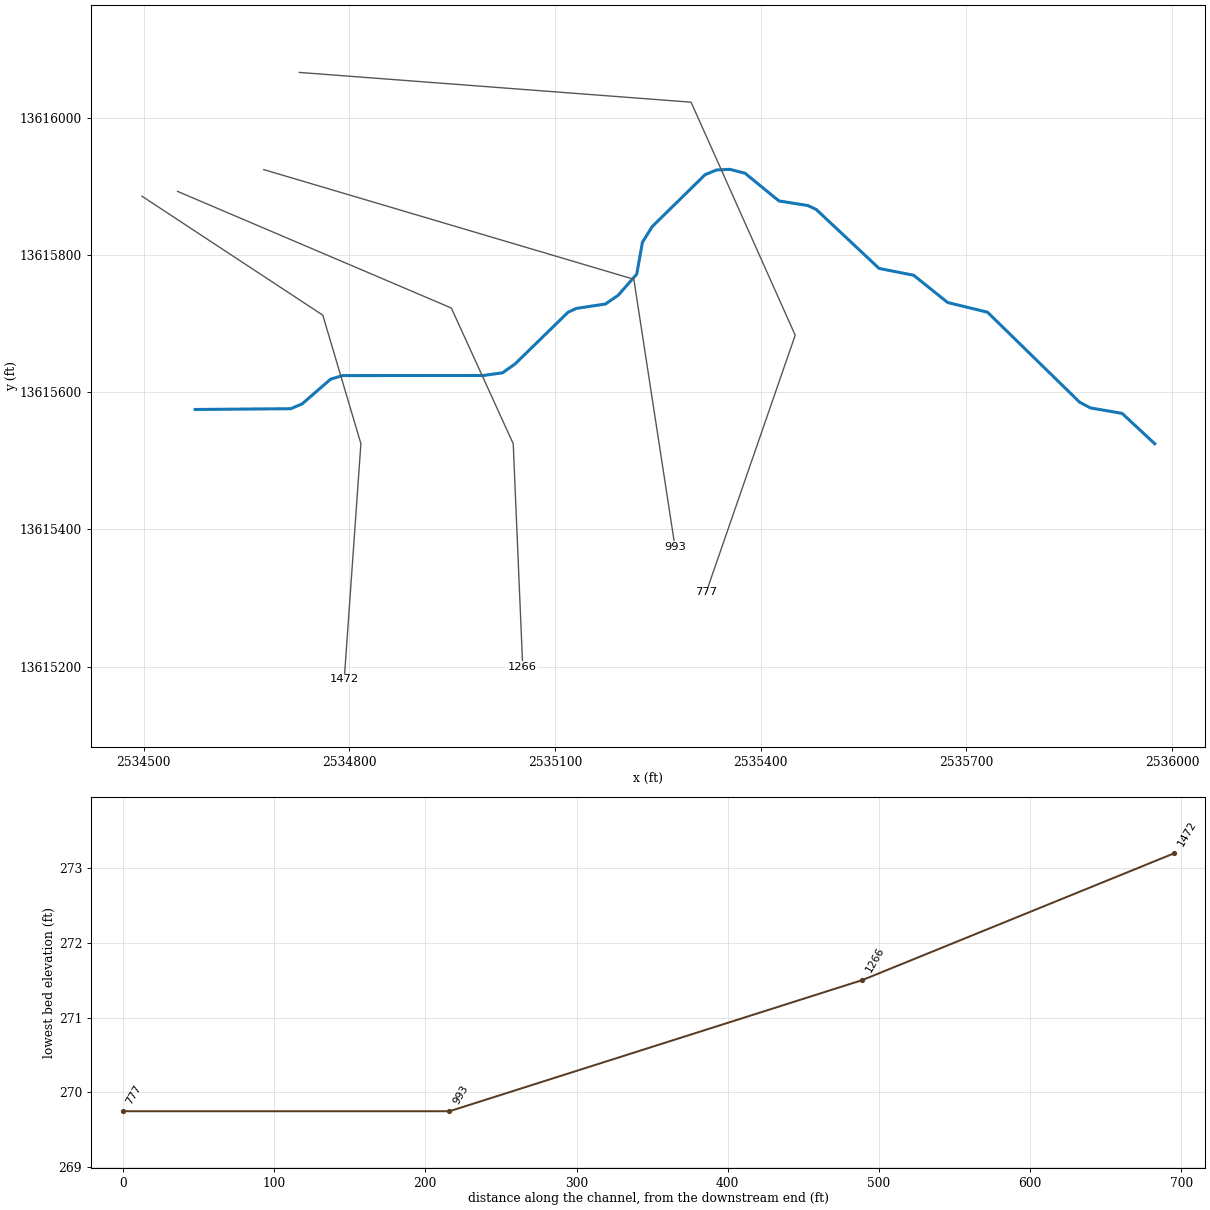
--- TRIB 14_2_1 TO IRISH CREEK.prj (project) ---

Proj Title=TRIB 14_2_1 TO IRISH CREEK Base Level Engineering
Current Plan=p01
Default Exp/Contr=0.3,0.1
English Units
Geom File=g01
Flow File=f01
Plan File=p01
Y Axis Title=Elevation
X Axis Title(PF)=Main Channel Distance
X Axis Title(XS)=Station
BEGIN DESCRIPTION:
TRIB 14_2_1 TO IRISH CREEK
END DESCRIPTION:
DSS Export Rating Curves= 0
DSS Export Rating Curve Sorted= 0
DSS Export Volume Flow Curves= 0
DXF OffsetX= 0
DXF OffsetY= 0
DXF ScaleX= 1
DXF ScaleY= 10

--- TRIB 14_2_1 TO IRISH CREEK.p01 (plan) ---

Plan Title=Multiple Run
Short Identifier=Multiple
Geom File=g01
Flow File=f01
Subcritical Flow
K Sum by GR= 0
Std Step Tol= 0.01
Critical Tol= 0.01
Num of Std Step Trials= 20
Max Error Tol= 0.3
Flow Tol Ratio= 0.001
Split Flow NTrial= 30
Split Flow Tol= 0.02
Split Flow Ratio= 0.02
Log Output Level= 0
Friction Slope Method= 1
Unsteady Friction Slope Method= 2
Unsteady Bridges Friction Slope Method= 1
Parabolic Critical Depth
Global Vel Dist=  1 , 1 , 1
Global Log Level= 0
CheckData=True
Encroach Param= -1, 0, 0, 0
BEGIN DESCRIPTION:
Multiple Run
END DESCRIPTION:

--- TRIB 14_2_1 TO IRISH CREEK.f01 (steady flow) ---

Flow Title=Multiple
Number of Profiles=7
Profile Names=10-year,25-year,50-year,1pct_min,100-year,1pct_plu,500-year
River Rch & RM= TRIB 14_2_1 TO I,Reach-1,1472
     276     421     546     344     687    1371    1073
Boundary for River Rch & Prof#=TRIB 14_2_1 TO I,Reach-1,1
Up Type=0
Dn Type=3
Dn Slope=0.005
Boundary for River Rch & Prof#=TRIB 14_2_1 TO I,Reach-1,2
Up Type=0
Dn Type=3
Dn Slope=0.005
Boundary for River Rch & Prof#=TRIB 14_2_1 TO I,Reach-1,3
Up Type=0
Dn Type=3
Dn Slope=0.005
Boundary for River Rch & Prof#=TRIB 14_2_1 TO I,Reach-1,4
Up Type=0
Dn Type=3
Dn Slope=0.005
Boundary for River Rch & Prof#=TRIB 14_2_1 TO I,Reach-1,5
Up Type=0
Dn Type=3
Dn Slope=0.005
Boundary for River Rch & Prof#=TRIB 14_2_1 TO I,Reach-1,6
Up Type=0
Dn Type=3
Dn Slope=0.005
Boundary for River Rch & Prof#=TRIB 14_2_1 TO I,Reach-1,7
Up Type=0
Dn Type=3
Dn Slope=0.005

--- TRIB 14_2_1 TO IRISH CREEK.g01 (geometry) ---

Geom Title=Existing Conditions

River Reach=TRIB 14_2_1 TO I,Reach-1
Reach XY= 30
      2534575.00     13615575.00      2534714.52     13615576.17
      2534731.06     13615583.13      2534772.66     13615619.26
      2534790.22     13615624.48      2534995.18     13615624.57
      2535023.53     13615628.55      2535041.75     13615641.46
      2535118.98     13615716.81      2535131.09     13615722.44
      2535173.57     13615728.89      2535192.05     13615741.50
      2535219.25     13615772.46      2535227.55     13615818.92
      2535241.64     13615841.70      2535318.93     13615917.53
      2535335.62     13615924.41      2535354.79     13615925.37
      2535377.19     13615919.69      2535426.73     13615879.25
      2535468.96     13615872.50      2535481.05     13615866.85
      2535572.71     13615780.85      2535623.27     13615770.81
      2535672.81     13615731.10      2535731.06     13615716.86
      2535865.29     13615585.70      2535880.97     13615577.34
      2535927.35     13615569.29      2535975.00     13615525.00

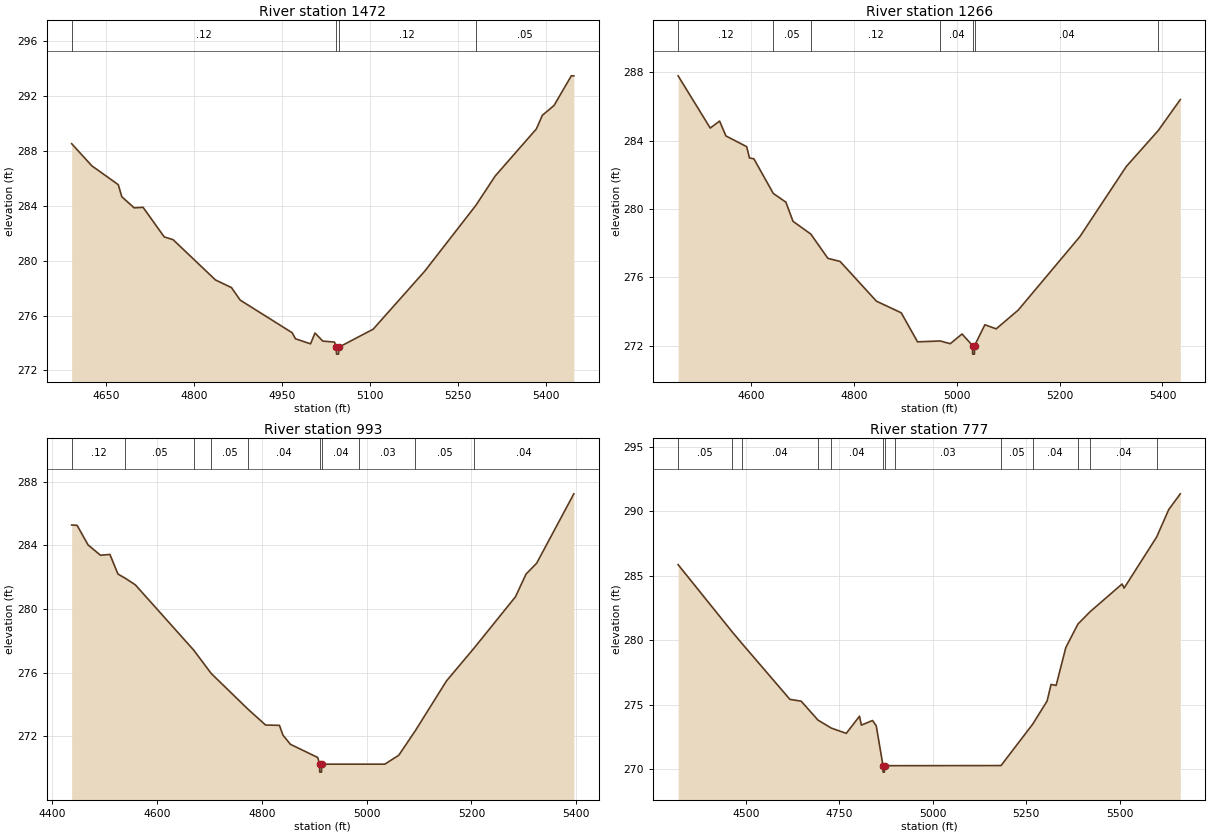
Type RM Length L Ch R = 1,1472,206,206,206
BEGIN DESCRIPTION:
Mapping XS 472b12a8
END DESCRIPTION:
XS GIS Cut Line= 4
      2534497.37     13615886.21      2534761.25     13615712.60
      2534816.81     13615525.10      2534792.51     13615181.39
#Sta/Elev= 30
  4591.8  288.54  4626.1  286.93  4671.3  285.55  4677.3  284.67  4698.4  283.86
  4713.5  283.90  4749.6  281.74  4764.7  281.54  4837.0  278.60  4864.3  278.04
  4879.1  277.13  4967.7  274.75  4973.3  274.31  4999.0  273.94  5006.6  274.73
  5019.9  274.14  5039.8  274.07  5043.0  273.69  5043.3  273.19  5046.8  273.19
  5047.0  273.69  5105.8  275.01  5193.6  279.24  5280.6  284.03  5313.9  286.19
  5384.0  289.62  5394.1  290.61  5414.1  291.33  5443.5  293.49  5447.8  293.49
#Mann=4,-1,0
  4591.8    0.12       0  5043.0    0.05       0  5047.0    0.12       0
  5280.6    0.05       0
Bank Sta=5043,5047
Exp/Cntr=0.3,0.1

Type RM Length L Ch R = 1,1266,273,273,273
BEGIN DESCRIPTION:
Mapping XS 6d5a17c0
END DESCRIPTION:
XS GIS Cut Line= 4
      2534549.40     13615893.17      2534948.75     13615723.02
      2535039.03     13615525.10      2535052.87     13615200.02
#Sta/Elev= 30
  4457.7  287.80  4520.2  284.74  4538.4  285.15  4550.7  284.28  4591.1  283.65
  4596.5  282.99  4605.1  282.94  4642.9  280.91  4667.4  280.40  4681.2  279.28
  4715.9  278.53  4749.1  277.11  4772.8  276.93  4843.6  274.60  4891.8  273.92
  4923.5  272.22  4967.9  272.27  4987.1  272.11  5010.1  272.68  5030.5  272.00
  5030.7  271.50  5034.2  271.50  5034.5  272.00  5054.5  273.22  5076.5  272.98
  5119.4  274.08  5239.5  278.39  5329.6  282.49  5391.9  284.60  5434.7  286.41
#Mann=7,-1,0
  4457.7    0.12       0  4642.9    0.05       0  4715.9    0.12       0
  4967.9    0.04       0  5030.5    0.04       0  5034.5    0.04       0
  5391.9    0.05       0
Bank Sta=5030.5,5034.5
Exp/Cntr=0.3,0.1

Type RM Length L Ch R = 1,993,216,216,216
BEGIN DESCRIPTION:
TRIB 14_2-1 TO IRISH CREEK 1.0
END DESCRIPTION:
XS GIS Cut Line= 3
      2534675.04     13615924.99      2535215.02     13615764.97
      2535275.01     13615374.95
#Sta/Elev= 30
  4437.4  285.28  4447.8  285.26  4468.7  284.03  4492.4  283.38  4510.4  283.43
  4525.7  282.20  4539.9  281.93  4558.9  281.52  4670.4  277.41  4703.6  275.95
  4773.9  273.70  4807.3  272.71  4833.7  272.69  4840.5  272.07  4854.6  271.50
  4906.7  270.67  4910.2  270.25  4910.5  269.75  4914.0  269.75  4914.2  270.25
  4985.7  270.25  5034.7  270.25  5061.3  270.81  5093.2  272.37  5152.3  275.48
  5205.3  277.56  5283.9  280.77  5304.1  282.20  5324.3  282.88  5395.2  287.24
#Mann=10,-1,0
  4437.4    0.12       0  4539.9    0.05       0  4670.4    0.04       0
  4703.6    0.05       0  4773.9    0.04       0  4910.2    0.03       0
  4914.2    0.04       0  4985.7    0.03       0  5093.2    0.05       0
  5205.3    0.04       0
Bank Sta=4910.2,4914.2
Exp/Cntr=0.3,0.1

Type RM Length L Ch R = 1,777,0,0,0
BEGIN DESCRIPTION:
LGII4282
END DESCRIPTION:
XS GIS Cut Line= 4
      2534727.03     13616066.74      2535298.50     13616023.34
      2535450.41     13615683.35      2535320.68     13615308.57
#Sta/Elev= 30
  4319.4  285.86  4463.4  280.66  4489.7  279.75  4618.2  275.40  4648.3  275.26
  4693.2  273.79  4728.7  273.17  4768.7  272.76  4804.2  274.09  4809.2  273.40
  4838.9  273.76  4848.9  273.35  4867.0  270.25  4867.2  269.75  4870.7  269.75
  4871.0  270.25  4899.2  270.25  5182.4  270.26  5267.1  273.48  5305.5  275.27
  5316.1  276.56  5329.6  276.48  5355.5  279.42  5387.7  281.24  5420.9  282.22
  5506.0  284.36  5511.3  284.04  5598.3  288.01  5630.6  290.14  5661.5  291.36
#Mann=13,-1,0
  4319.4    0.05       0  4463.4    0.12       0  4489.7    0.04       0
  4693.2    0.12       0  4728.7    0.04       0  4867.0    0.03       0
  4871.0    0.04       0  4899.2    0.03       0  5182.4    0.05       0
  5267.1    0.04       0  5387.7   0.013       0  5420.9    0.04       0
  5598.3   0.013       0
Bank Sta=4867,4871
Exp/Cntr=0.3,0.1

Chan Stop Cuts=-1