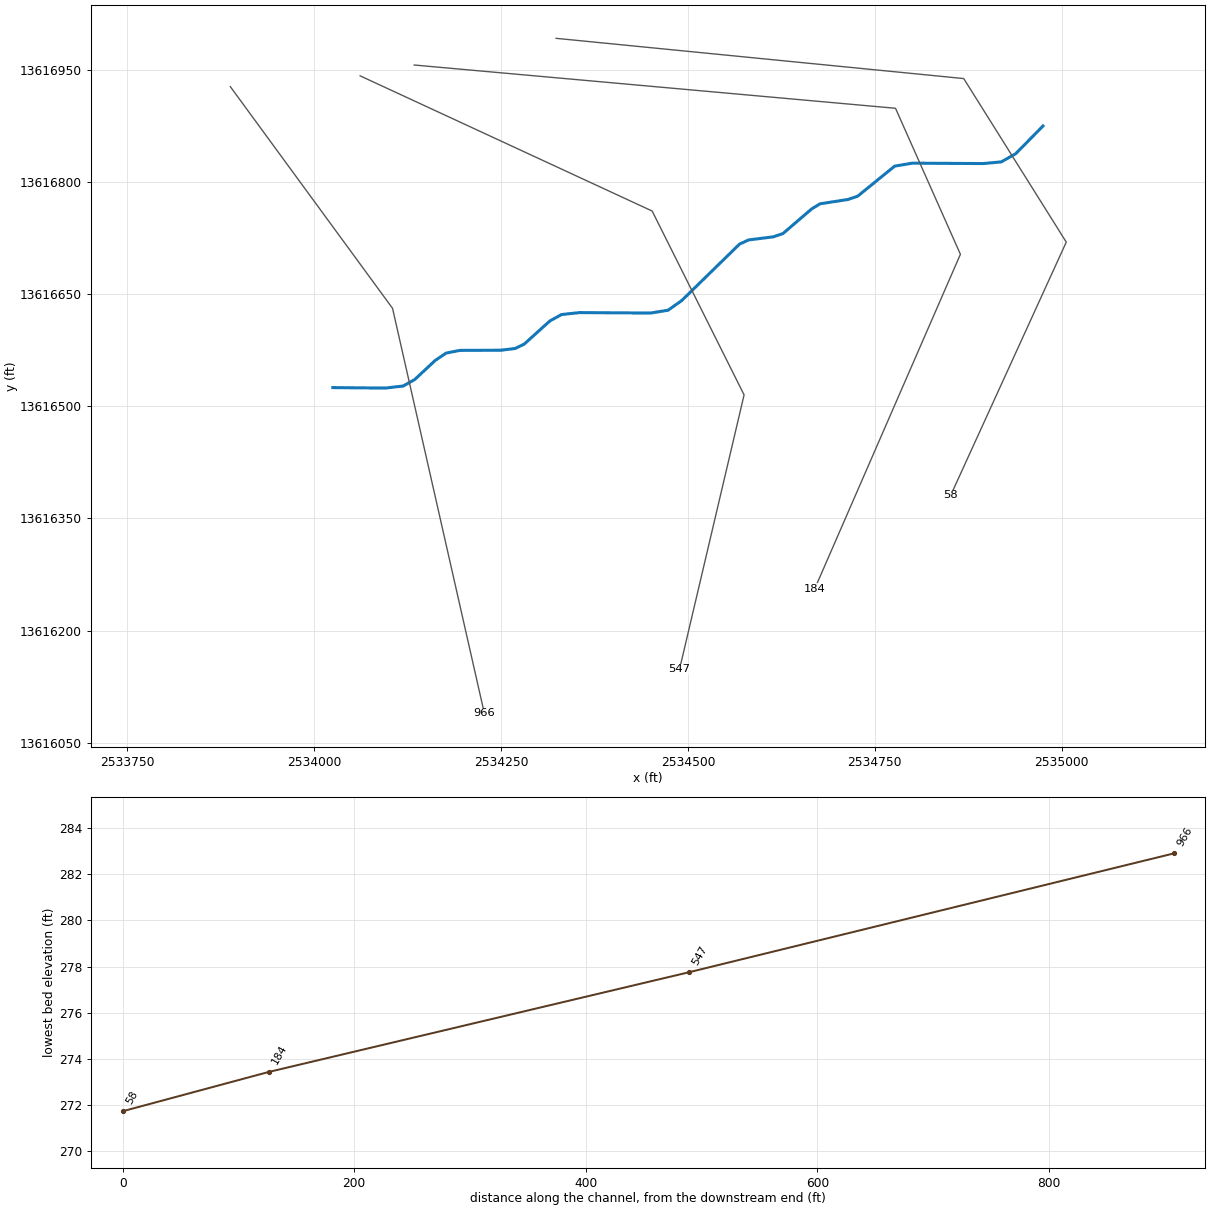
--- TRIB 14_2_2 TO IRISH CREEK.prj (project) ---

Proj Title=TRIB 14_2_2 TO IRISH CREEK Base Level Engineering
Current Plan=p01
Default Exp/Contr=0.3,0.1
English Units
Geom File=g01
Flow File=f01
Plan File=p01
Y Axis Title=Elevation
X Axis Title(PF)=Main Channel Distance
X Axis Title(XS)=Station
BEGIN DESCRIPTION:
TRIB 14_2_2 TO IRISH CREEK
END DESCRIPTION:
DSS Export Rating Curves= 0
DSS Export Rating Curve Sorted= 0
DSS Export Volume Flow Curves= 0
DXF OffsetX= 0
DXF OffsetY= 0
DXF ScaleX= 1
DXF ScaleY= 10

--- TRIB 14_2_2 TO IRISH CREEK.p01 (plan) ---

Plan Title=Multiple Run
Short Identifier=Multiple
Geom File=g01
Flow File=f01
Subcritical Flow
K Sum by GR= 0
Std Step Tol= 0.01
Critical Tol= 0.01
Num of Std Step Trials= 20
Max Error Tol= 0.3
Flow Tol Ratio= 0.001
Split Flow NTrial= 30
Split Flow Tol= 0.02
Split Flow Ratio= 0.02
Log Output Level= 0
Friction Slope Method= 1
Unsteady Friction Slope Method= 2
Unsteady Bridges Friction Slope Method= 1
Parabolic Critical Depth
Global Vel Dist=  1 , 1 , 1
Global Log Level= 0
CheckData=True
Encroach Param= -1, 0, 0, 0
BEGIN DESCRIPTION:
Multiple Run
END DESCRIPTION:

--- TRIB 14_2_2 TO IRISH CREEK.f01 (steady flow) ---

Flow Title=Multiple
Number of Profiles=7
Profile Names=10-year,25-year,50-year,1pct_min,100-year,1pct_plu,500-year
River Rch & RM= TRIB 14_2_2 TO I,Reach-1,966
     151     219     276     169     337     673     498
Boundary for River Rch & Prof#=TRIB 14_2_2 TO I,Reach-1,1
Up Type=0
Dn Type=3
Dn Slope=0.005
Boundary for River Rch & Prof#=TRIB 14_2_2 TO I,Reach-1,2
Up Type=0
Dn Type=3
Dn Slope=0.005
Boundary for River Rch & Prof#=TRIB 14_2_2 TO I,Reach-1,3
Up Type=0
Dn Type=3
Dn Slope=0.005
Boundary for River Rch & Prof#=TRIB 14_2_2 TO I,Reach-1,4
Up Type=0
Dn Type=3
Dn Slope=0.005
Boundary for River Rch & Prof#=TRIB 14_2_2 TO I,Reach-1,5
Up Type=0
Dn Type=3
Dn Slope=0.005
Boundary for River Rch & Prof#=TRIB 14_2_2 TO I,Reach-1,6
Up Type=0
Dn Type=3
Dn Slope=0.005
Boundary for River Rch & Prof#=TRIB 14_2_2 TO I,Reach-1,7
Up Type=0
Dn Type=3
Dn Slope=0.005

--- TRIB 14_2_2 TO IRISH CREEK.g01 (geometry) ---

Geom Title=Existing Conditions

River Reach=TRIB 14_2_2 TO I,Reach-1
Reach XY= 30
      2534025.00     13616525.00      2534095.26     13616524.36
      2534119.13     13616527.10      2534134.65     13616535.85
      2534161.85     13616561.23      2534176.58     13616571.17
      2534195.10     13616574.77      2534250.00     13616575.00
      2534269.02     13616577.35      2534281.03     13616583.19
      2534315.35     13616614.15      2534330.94     13616622.73
      2534354.87     13616625.32      2534450.11     13616624.73
      2534473.53     13616628.55      2534491.75     13616641.46
      2534568.95     13616716.84      2534581.04     13616722.49
      2534614.30     13616726.70      2534627.19     13616731.10
      2534665.45     13616763.92      2534676.72     13616770.84
      2534714.31     13616776.67      2534727.18     13616781.12
      2534776.56     13616821.25      2534799.92     13616825.19
      2534895.13     13616824.68      2534919.21     13616826.91
      2534938.50     13616837.92      2534975.00     13616875.00

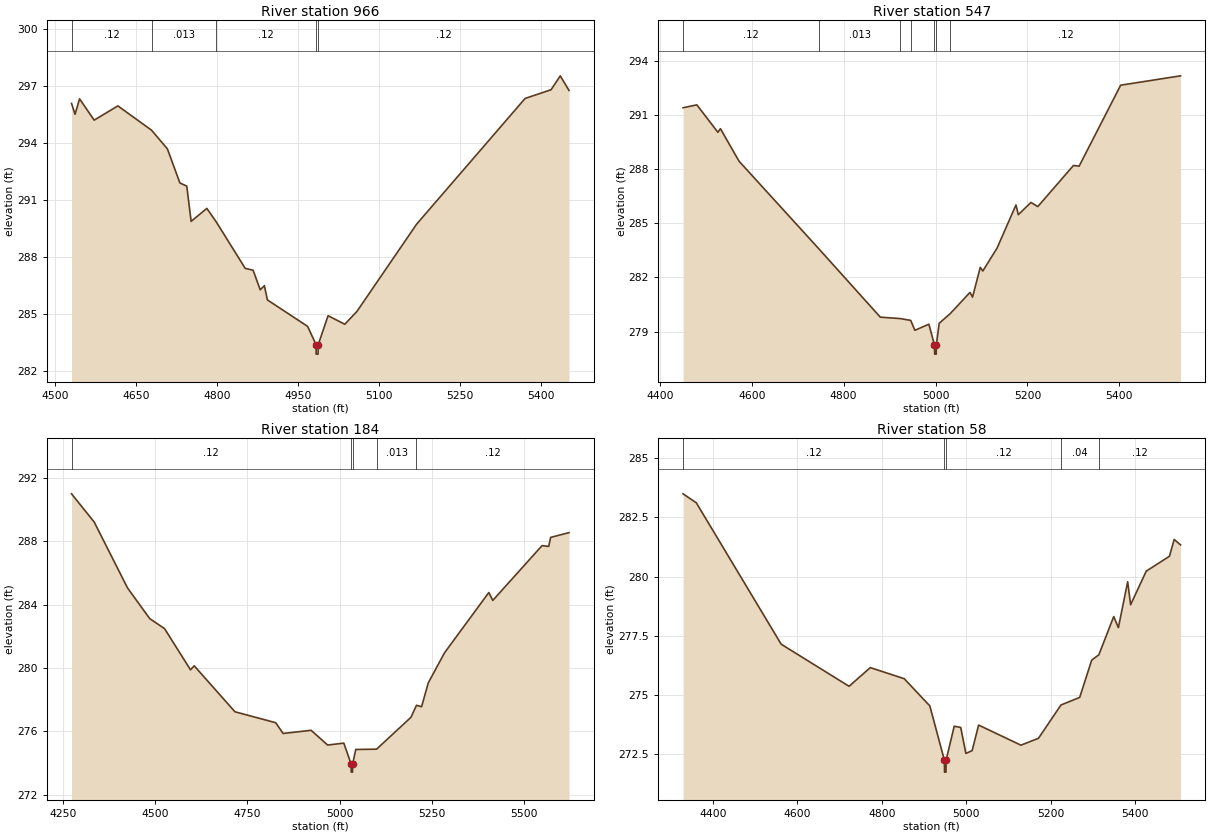
Type RM Length L Ch R = 1,966,419,419,419
BEGIN DESCRIPTION:
LGII4285
END DESCRIPTION:
XS GIS Cut Line= 3
      2533887.89     13616927.58      2534104.92     13616630.98
      2534227.71     13616089.24
#Sta/Elev= 30
  4529.8  296.08  4536.3  295.51  4544.7  296.32  4571.8  295.20  4615.8  295.95
  4678.3  294.67  4707.7  293.69  4730.8  291.90  4743.6  291.73  4751.7  289.88
  4780.8  290.56  4797.9  289.87  4852.0  287.41  4866.7  287.31  4879.9  286.28
  4887.6  286.50  4893.2  285.75  4967.8  284.36  4983.5  283.40  4983.7  282.90
  4987.2  282.90  4987.5  283.40  5005.8  284.92  5036.7  284.47  5059.2  285.14
  5170.0  289.73  5371.3  296.34  5419.6  296.80  5436.6  297.53  5452.8  296.76
#Mann=5,-1,0
  4529.8    0.12       0  4678.3   0.013       0  4797.9    0.12       0
  4983.5    0.05       0  4987.5    0.12       0
Bank Sta=4983.5,4987.5
Exp/Cntr=0.3,0.1

Type RM Length L Ch R = 1,547,363,363,363
BEGIN DESCRIPTION:
LGII4284
END DESCRIPTION:
XS GIS Cut Line= 4
      2534061.55     13616942.01      2534452.14     13616761.18
      2534575.12     13616515.23      2534488.75     13616148.16
#Sta/Elev= 30
  4450.6  291.41  4480.6  291.57  4526.4  290.05  4531.9  290.25  4572.3  288.45
  4746.4  283.58  4879.8  279.80  4923.5  279.72  4946.0  279.62  4955.0  279.07
  4985.5  279.41  4997.7  278.25  4998.0  277.75  5001.5  277.75  5001.7  278.25
  5007.9  279.46  5032.1  280.00  5074.9  281.17  5080.5  280.91  5097.3  282.56
  5102.9  282.36  5133.9  283.63  5175.0  286.02  5180.1  285.48  5207.6  286.16
  5222.5  285.93  5300.1  288.21  5312.4  288.17  5402.8  292.66  5533.1  293.18
#Mann=7,-1,0
  4450.6    0.12       0  4746.4   0.013       0  4923.5    0.12       0
  4946.0   0.013       0  4997.7    0.03       0  5001.7   0.013       0
  5032.1    0.12       0
Bank Sta=4997.7,5001.7
Exp/Cntr=0.3,0.1

Type RM Length L Ch R = 1,184,126,126,126
BEGIN DESCRIPTION:
LGII4283
END DESCRIPTION:
XS GIS Cut Line= 4
      2534133.88     13616956.49      2534777.66     13616898.63
      2534864.47     13616703.31      2534669.59     13616255.81
#Sta/Elev= 30
  4273.5  291.00  4334.9  289.22  4425.2  285.06  4485.5  283.12  4525.6  282.49
  4595.9  279.89  4606.0  280.14  4716.4  277.24  4826.8  276.55  4846.9  275.87
  4922.8  276.07  4967.6  275.14  5011.4  275.26  5031.3  273.93  5031.5  273.43
  5035.0  273.43  5035.3  273.93  5043.7  274.86  5100.2  274.88  5193.3  276.89
  5208.3  277.65  5222.2  277.56  5240.2  279.06  5284.5  280.97  5404.4  284.77
  5415.1  284.27  5548.6  287.73  5566.6  287.68  5572.0  288.25  5621.7  288.55
#Mann=5,-1,0
  4273.5    0.12       0  5031.3    0.05       0  5035.3    0.12       0
  5100.2   0.013       0  5208.3    0.12       0
Bank Sta=5031.3,5035.3
Exp/Cntr=0.3,0.1

Type RM Length L Ch R = 1,58,0,0,0
BEGIN DESCRIPTION:
4823
END DESCRIPTION:
XS GIS Cut Line= 4
      2534323.76     13616992.18      2534868.92     13616938.36
      2535006.08     13616719.61      2534851.58     13616381.11
#Sta/Elev= 30
  4329.5  283.50  4360.9  283.12  4561.9  277.14  4722.6  275.36  4772.9  276.15
  4853.3  275.68  4913.9  274.53  4948.4  272.23  4948.7  271.73  4952.2  271.73
  4952.4  272.23  4971.6  273.67  4987.0  273.62  4999.3  272.52  5014.1  272.64
  5029.4  273.72  5129.6  272.87  5171.1  273.16  5224.5  274.57  5268.8  274.89
  5297.3  276.47  5314.1  276.69  5349.4  278.31  5360.4  277.84  5382.4  279.78
  5389.4  278.81  5426.4  280.23  5481.3  280.86  5492.6  281.57  5507.6  281.34
#Mann=5,-1,0
  4329.5    0.12       0  4948.4    0.05       0  4952.4    0.12       0
  5224.5    0.04       0  5314.1    0.12       0
Bank Sta=4948.4,4952.4
Exp/Cntr=0.3,0.1

Chan Stop Cuts=-1