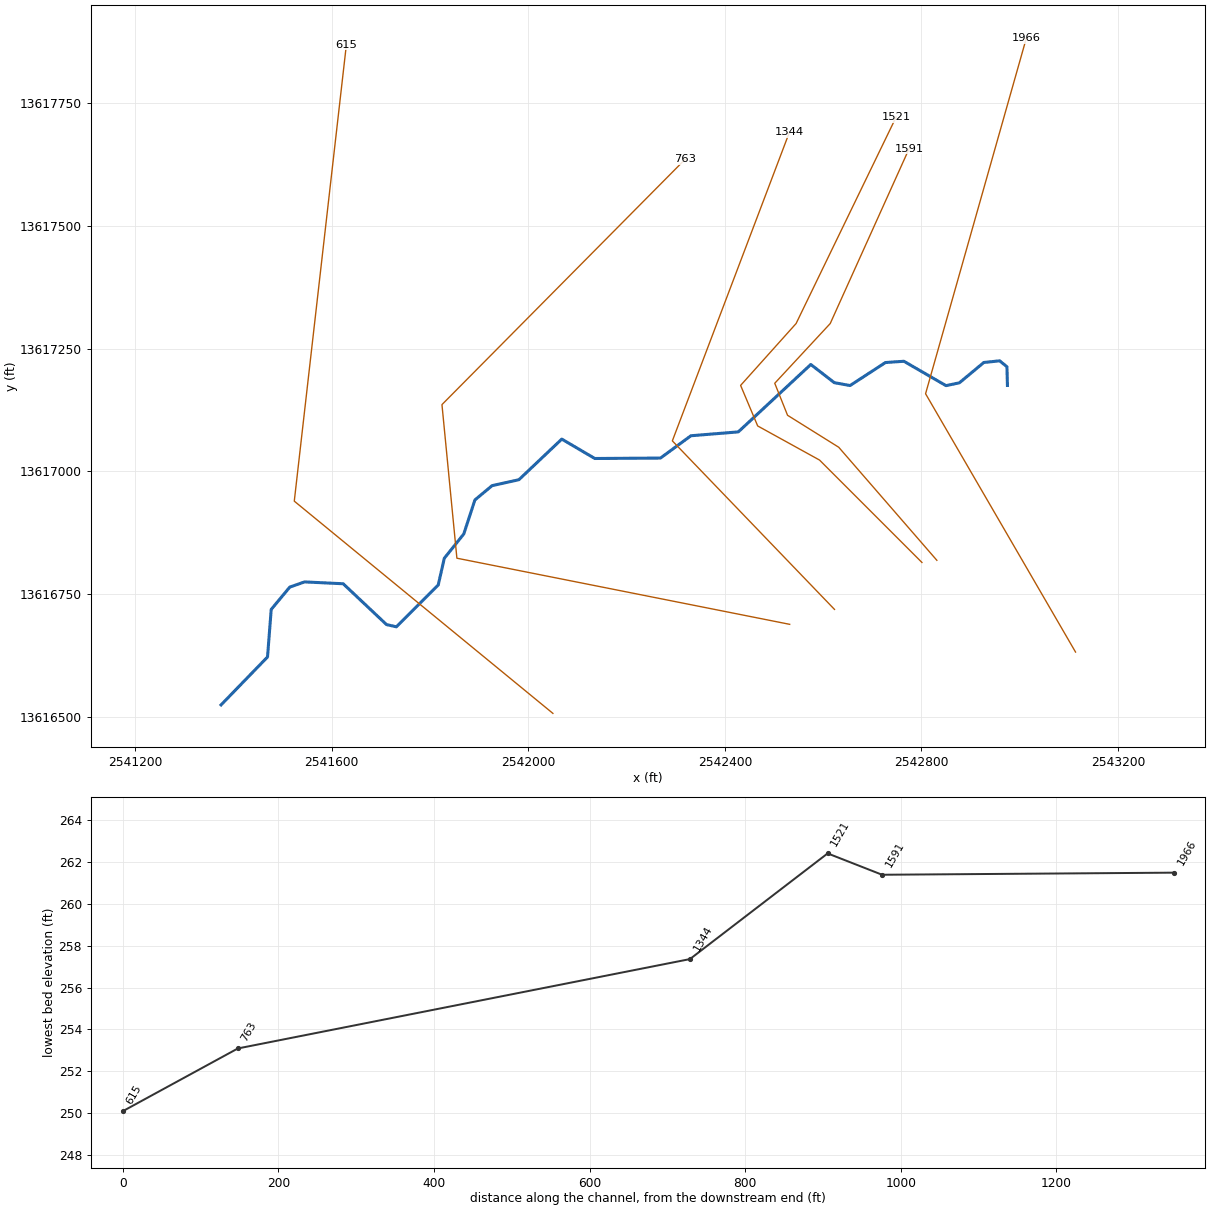
--- TRIB 15 TO IRISH CREEK.prj (project) ---

Proj Title=TRIB 15 TO IRISH CREEK Base Level Engineering
Current Plan=p01
Default Exp/Contr=0.3,0.1
English Units
Geom File=g01
Flow File=f01
Plan File=p01
Y Axis Title=Elevation
X Axis Title(PF)=Main Channel Distance
X Axis Title(XS)=Station
BEGIN DESCRIPTION:
TRIB 15 TO IRISH CREEK
END DESCRIPTION:
DSS Export Rating Curves= 0
DSS Export Rating Curve Sorted= 0
DSS Export Volume Flow Curves= 0
DXF OffsetX= 0
DXF OffsetY= 0
DXF ScaleX= 1
DXF ScaleY= 10

--- TRIB 15 TO IRISH CREEK.p01 (plan) ---

Plan Title=Multiple Run
Short Identifier=Multiple
Geom File=g01
Flow File=f01
Subcritical Flow
K Sum by GR= 0
Std Step Tol= 0.01
Critical Tol= 0.01
Num of Std Step Trials= 20
Max Error Tol= 0.3
Flow Tol Ratio= 0.001
Split Flow NTrial= 30
Split Flow Tol= 0.02
Split Flow Ratio= 0.02
Log Output Level= 0
Friction Slope Method= 1
Unsteady Friction Slope Method= 2
Unsteady Bridges Friction Slope Method= 1
Parabolic Critical Depth
Global Vel Dist=  1 , 1 , 1
Global Log Level= 0
CheckData=True
Encroach Param= -1, 0, 0, 0
BEGIN DESCRIPTION:
Multiple Run
END DESCRIPTION:

--- TRIB 15 TO IRISH CREEK.f01 (steady flow) ---

Flow Title=Multiple
Number of Profiles=7
Profile Names=10-year,25-year,50-year,1pct_min,100-year,1pct_plu,500-year
River Rch & RM= TRIB 15 TO IRISH,Reach-1,1966
     491     773    1024     658    1313    2620    2134
Boundary for River Rch & Prof#=TRIB 15 TO IRISH,Reach-1,1
Up Type=0
Dn Type=3
Dn Slope=0.005
Boundary for River Rch & Prof#=TRIB 15 TO IRISH,Reach-1,2
Up Type=0
Dn Type=3
Dn Slope=0.005
Boundary for River Rch & Prof#=TRIB 15 TO IRISH,Reach-1,3
Up Type=0
Dn Type=3
Dn Slope=0.005
Boundary for River Rch & Prof#=TRIB 15 TO IRISH,Reach-1,4
Up Type=0
Dn Type=3
Dn Slope=0.005
Boundary for River Rch & Prof#=TRIB 15 TO IRISH,Reach-1,5
Up Type=0
Dn Type=3
Dn Slope=0.005
Boundary for River Rch & Prof#=TRIB 15 TO IRISH,Reach-1,6
Up Type=0
Dn Type=3
Dn Slope=0.005
Boundary for River Rch & Prof#=TRIB 15 TO IRISH,Reach-1,7
Up Type=0
Dn Type=3
Dn Slope=0.005

--- TRIB 15 TO IRISH CREEK.g01 (geometry) ---

Geom Title=Existing Conditions

River Reach=TRIB 15 TO IRISH,Reach-1
Reach XY= 30
      2542975.00     13617175.00      2542973.96     13617213.05
      2542959.09     13617225.09      2542926.91     13617221.70
      2542877.23     13617180.37      2542850.01     13617174.60
      2542764.31     13617224.21      2542726.72     13617221.59
      2542654.80     13617174.81      2542622.70     13617180.67
      2542574.91     13617217.65      2542427.43     13617080.52
      2542330.98     13617072.64      2542269.06     13617027.25
      2542135.44     13617026.38      2542068.27     13617065.85
      2541981.03     13616983.20      2541926.43     13616971.12
      2541891.49     13616942.05      2541868.89     13616872.84
      2541829.19     13616823.26      2541816.86     13616768.91
      2541731.69     13616683.95      2541711.68     13616688.43
      2541623.50     13616771.52      2541544.94     13616775.27
      2541514.84     13616764.72      2541477.07     13616719.32
      2541469.54     13616622.55      2541375.00     13616525.00

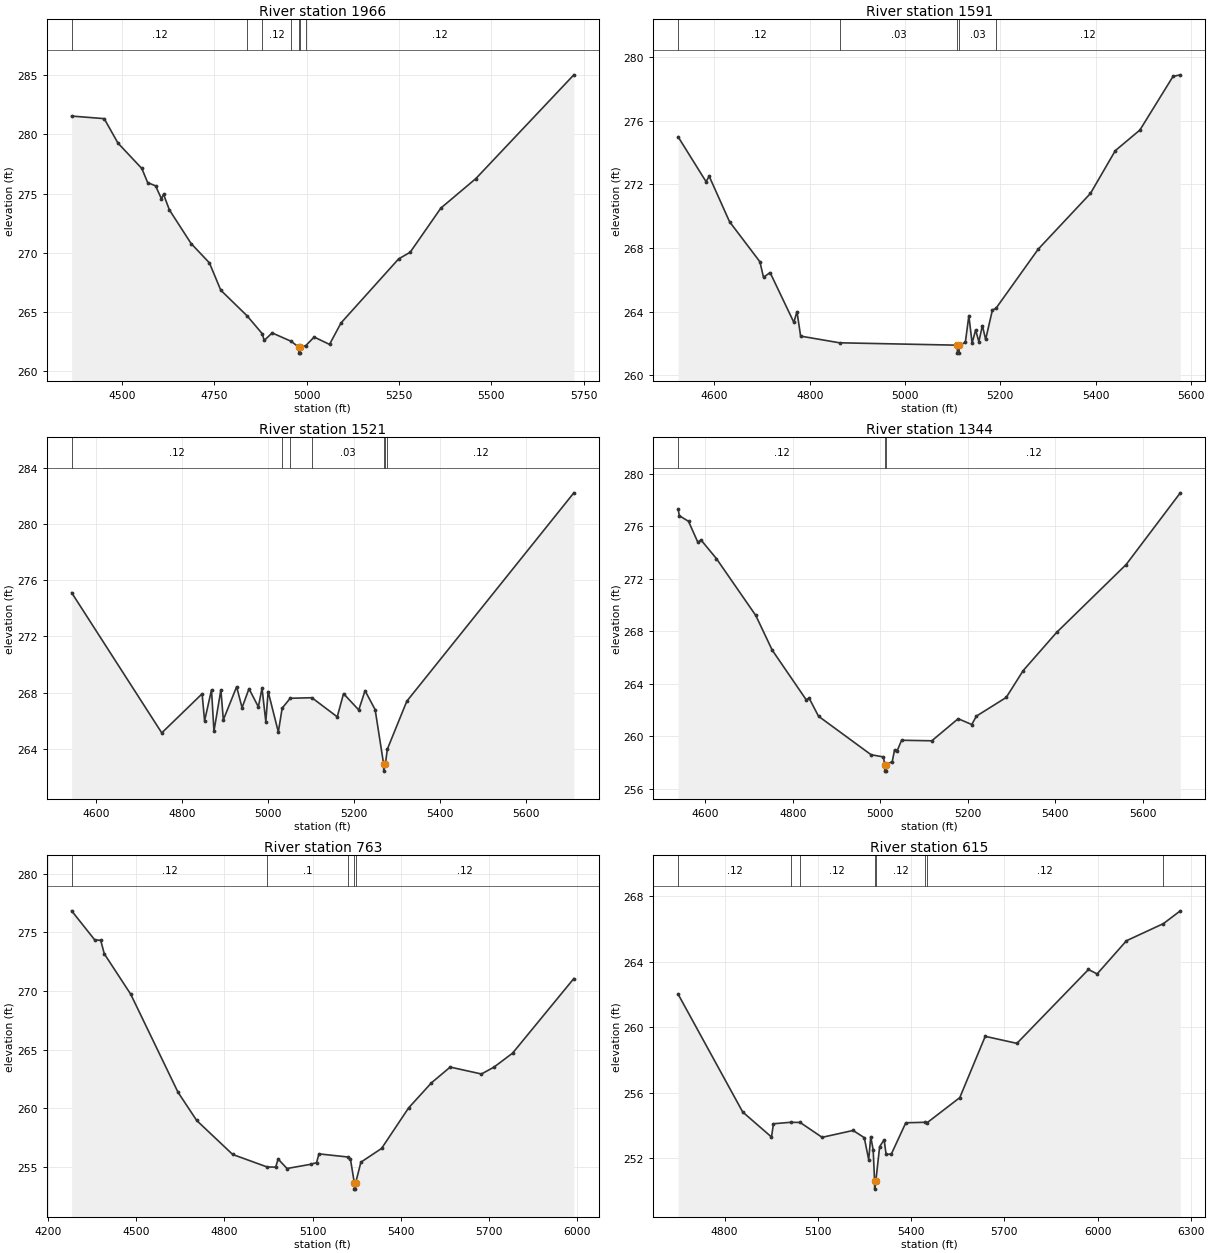
Type RM Length L Ch R = 1,1966,375,375,375
BEGIN DESCRIPTION:
TRIB 15 TO IRISH CREEK 3.0
END DESCRIPTION:
XS GIS Cut Line= 3
      2543113.53     13616632.55      2542808.42     13617158.11
      2543013.34     13617881.23
#Sta/Elev= 30
  4364.2  281.56  4452.3  281.34  4489.6  279.27  4554.2  277.12  4569.9  275.93
  4591.4  275.65  4607.2  274.56  4612.9  274.94  4628.7  273.62  4687.5  270.77
  4737.1  269.13  4767.8  266.82  4839.3  264.64  4880.2  263.13  4885.3  262.56
  4906.9  263.20  4958.5  262.49  4979.0  261.99  4979.2  261.49  4982.7  261.49
  4983.0  261.99  4998.0  262.13  5020.6  262.85  5062.2  262.23  5093.4  264.05
  5249.3  269.47  5280.5  270.03  5363.6  273.77  5458.4  276.27  5723.5  285.05
#Mann=7,-1,0
  4364.2    0.12       0  4839.3    0.03       0  4880.2    0.12       0
  4958.5    0.03       0  4979.0    0.05       0  4983.0    0.03       0
  4998.0    0.12       0
Bank Sta=4979,4983
Exp/Cntr=0.3,0.1

Type RM Length L Ch R = 1,1591,70,70,70
BEGIN DESCRIPTION:
Mapping XS 7bb3d7dc
END DESCRIPTION:
XS GIS Cut Line= 6
      2542831.39     13616819.21      2542631.77     13617049.21
      2542527.60     13617114.31      2542501.56     13617179.42
      2542614.40     13617300.94      2542774.99     13617656.84
#Sta/Elev= 30
  4523.8  275.00  4582.4  272.18  4589.0  272.52  4631.7  269.66  4695.4  267.14
  4703.0  266.16  4716.8  266.46  4766.6  263.33  4773.2  264.00  4780.9  262.46
  4862.5  262.04  5109.6  261.89  5109.9  261.39  5113.4  261.39  5113.6  261.89
  5126.5  262.06  5133.9  263.75  5140.7  262.02  5148.1  262.85  5154.9  262.11
  5162.3  263.12  5169.1  262.25  5183.3  264.10  5190.8  264.21  5279.4  267.93
  5389.1  271.44  5441.2  274.13  5492.9  275.43  5562.3  278.80  5577.6  278.90
#Mann=5,-1,0
  4523.8    0.12       0  4862.5    0.03       0  5109.6    0.03       0
  5113.6    0.03       0  5190.8    0.12       0
Bank Sta=5109.6,5113.6
Exp/Cntr=0.3,0.1

Type RM Length L Ch R = 1,1521,177,177,177
BEGIN DESCRIPTION:
Mapping XS 0b7eb95b
END DESCRIPTION:
XS GIS Cut Line= 6
      2542801.03     13616814.84      2542592.70     13617023.17
      2542466.83     13617092.61      2542432.11     13617175.08
      2542544.96     13617300.94      2542748.48     13617720.98
#Sta/Elev= 30
  4543.6  275.10  4753.0  265.13  4846.8  267.91  4852.5  265.98  4868.6  268.19
  4874.3  265.25  4890.4  268.19  4896.1  266.06  4927.0  268.41  4939.6  266.92
  4955.7  268.27  4977.5  266.98  4986.0  268.31  4994.8  265.93  5000.2  268.07
  5023.9  265.19  5032.8  266.89  5051.5  267.59  5101.9  267.63  5160.8  266.27
  5175.4  267.92  5210.8  266.76  5225.4  268.13  5248.9  266.78  5268.6  262.91
  5268.8  262.41  5272.6  262.91  5277.2  263.97  5322.4  267.38  5710.6  282.20
#Mann=7,-1,0
  4543.6    0.12       0  5032.8    0.03       0  5051.5    0.12       0
  5101.9    0.03       0  5268.6    0.05       0  5272.6    0.03       0
  5277.2    0.12       0
Bank Sta=5268.6,5272.6
Exp/Cntr=0.3,0.1

Type RM Length L Ch R = 1,1344,581,581,581
BEGIN DESCRIPTION:
Mapping XS dc412fad
END DESCRIPTION:
XS GIS Cut Line= 3
      2542623.11     13616719.32      2542293.22     13617062.23
      2542531.65     13617690.80
#Sta/Elev= 30
  4537.7  277.32  4540.4  276.81  4561.5  276.38  4582.9  274.78  4589.8  274.97
  4625.3  273.54  4715.3  269.21  4752.7  266.58  4830.4  262.80  4837.3  262.91
  4858.7  261.54  4978.8  258.61  5007.1  258.44  5010.0  257.86  5010.2  257.36
  5013.7  257.36  5014.0  257.86  5027.2  258.09  5032.6  258.98  5037.9  258.86
  5048.6  259.71  5117.7  259.67  5177.9  261.35  5209.0  260.91  5219.7  261.55
  5287.8  262.97  5326.7  265.02  5403.0  267.92  5562.0  273.09  5685.8  278.55
#Mann=3,-1,0
  4537.7    0.12       0  5010.0    0.05       0  5014.0    0.12       0
Bank Sta=5010,5014
Exp/Cntr=0.3,0.1

Type RM Length L Ch R = 1,763,148,148,148
BEGIN DESCRIPTION:
Mapping XS ba46f87d
END DESCRIPTION:
XS GIS Cut Line= 4
      2542531.93     13616688.97      2541854.86     13616823.51
      2541824.47     13617136.01      2542319.26     13617635.14
#Sta/Elev= 30
  4280.9  276.85  4359.3  274.37  4379.7  274.33  4391.9  273.18  4481.7  269.73
  4642.5  261.36  4706.0  258.95  4828.3  256.05  4945.5  254.98  4974.5  254.97
  4982.8  255.66  5012.9  254.85  5093.3  255.21  5113.4  255.35  5121.6  256.10
  5221.0  255.83  5228.5  255.67  5242.0  253.59  5242.2  253.09  5245.7  253.09
  5246.0  253.59  5264.1  255.39  5334.3  256.56  5426.2  260.02  5504.1  262.17
  5567.7  263.51  5673.8  262.92  5716.2  263.50  5779.8  264.70  5988.0  271.07
#Mann=5,-1,0
  4280.9    0.12       0  4945.5     0.1       0  5221.0    0.12       0
  5242.0    0.05       0  5246.0    0.12       0
Bank Sta=5242,5246
Exp/Cntr=0.3,0.1

Type RM Length L Ch R = 1,615,0,0,0
BEGIN DESCRIPTION:
TRIB 15 TO IRISH CREEK 1.0
END DESCRIPTION:
XS GIS Cut Line= 3
      2542050.18     13616507.80      2541524.00     13616939.59
      2541630.04     13617868.59
#Sta/Elev= 30
  4650.7  262.02  4858.5  254.81  4951.1  253.28  4957.5  254.09  5013.1  254.18
  5043.3  254.17  5114.0  253.26  5213.6  253.68  5249.6  253.24  5263.9  251.89
  5270.4  253.30  5278.3  252.49  5282.8  250.59  5283.0  250.09  5286.8  250.59
  5299.1  252.69  5313.5  253.11  5319.9  252.21  5336.8  252.24  5383.2  254.15
  5445.2  254.18  5450.9  254.14  5556.9  255.69  5638.8  259.44  5740.7  259.01
  5970.9  263.53  5998.8  263.26  6093.2  265.29  6212.3  266.34  6266.4  267.12
#Mann=8,-1,0
  4650.7    0.12       0  5013.1     0.1       0  5043.3    0.12       0
  5282.8    0.05       0  5286.8    0.12       0  5445.2     0.1       0
  5450.9    0.12       0  6212.3    0.05       0
Bank Sta=5282.8,5286.8
Exp/Cntr=0.3,0.1

Chan Stop Cuts=-1