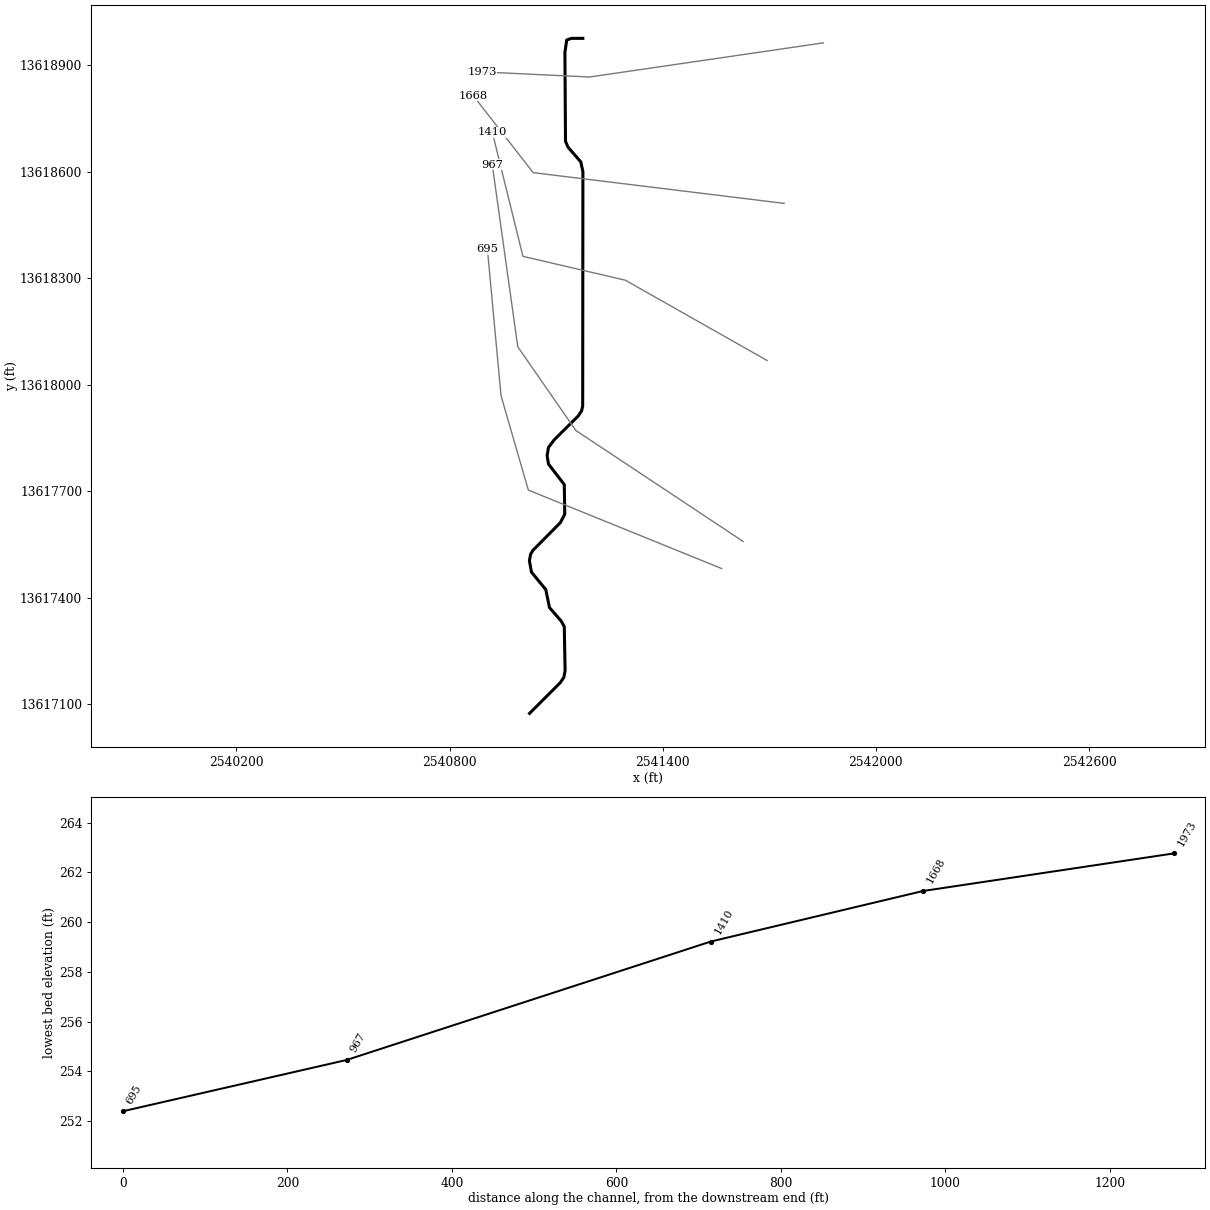
--- TRIB 16 TO IRISH CREEK.prj (project) ---

Proj Title=TRIB 16 TO IRISH CREEK Base Level Engineering
Current Plan=p01
Default Exp/Contr=0.3,0.1
English Units
Geom File=g01
Flow File=f01
Plan File=p01
Y Axis Title=Elevation
X Axis Title(PF)=Main Channel Distance
X Axis Title(XS)=Station
BEGIN DESCRIPTION:
TRIB 16 TO IRISH CREEK
END DESCRIPTION:
DSS Export Rating Curves= 0
DSS Export Rating Curve Sorted= 0
DSS Export Volume Flow Curves= 0
DXF OffsetX= 0
DXF OffsetY= 0
DXF ScaleX= 1
DXF ScaleY= 10

--- TRIB 16 TO IRISH CREEK.p01 (plan) ---

Plan Title=Multiple Run
Short Identifier=Multiple
Geom File=g01
Flow File=f01
Subcritical Flow
K Sum by GR= 0
Std Step Tol= 0.01
Critical Tol= 0.01
Num of Std Step Trials= 20
Max Error Tol= 0.3
Flow Tol Ratio= 0.001
Split Flow NTrial= 30
Split Flow Tol= 0.02
Split Flow Ratio= 0.02
Log Output Level= 0
Friction Slope Method= 1
Unsteady Friction Slope Method= 2
Unsteady Bridges Friction Slope Method= 1
Parabolic Critical Depth
Global Vel Dist=  1 , 1 , 1
Global Log Level= 0
CheckData=True
Encroach Param= -1, 0, 0, 0
BEGIN DESCRIPTION:
Multiple Run
END DESCRIPTION:

--- TRIB 16 TO IRISH CREEK.f01 (steady flow) ---

Flow Title=Multiple
Number of Profiles=7
Profile Names=10-year,25-year,50-year,1pct_min,100-year,1pct_plu,500-year
River Rch & RM= TRIB 16 TO IRISH,Reach-1,1973
     238     355     454     283     565    1127     859
Boundary for River Rch & Prof#=TRIB 16 TO IRISH,Reach-1,1
Up Type=0
Dn Type=3
Dn Slope=0.005
Boundary for River Rch & Prof#=TRIB 16 TO IRISH,Reach-1,2
Up Type=0
Dn Type=3
Dn Slope=0.005
Boundary for River Rch & Prof#=TRIB 16 TO IRISH,Reach-1,3
Up Type=0
Dn Type=3
Dn Slope=0.005
Boundary for River Rch & Prof#=TRIB 16 TO IRISH,Reach-1,4
Up Type=0
Dn Type=3
Dn Slope=0.005
Boundary for River Rch & Prof#=TRIB 16 TO IRISH,Reach-1,5
Up Type=0
Dn Type=3
Dn Slope=0.005
Boundary for River Rch & Prof#=TRIB 16 TO IRISH,Reach-1,6
Up Type=0
Dn Type=3
Dn Slope=0.005
Boundary for River Rch & Prof#=TRIB 16 TO IRISH,Reach-1,7
Up Type=0
Dn Type=3
Dn Slope=0.005

--- TRIB 16 TO IRISH CREEK.g01 (geometry) ---

Geom Title=Existing Conditions

River Reach=TRIB 16 TO IRISH,Reach-1
Reach XY= 30
      2541175.00     13618975.00      2541143.04     13618975.11
      2541129.63     13618970.37      2541124.55     13618935.45
      2541126.22     13618685.50      2541133.14     13618668.94
      2541169.25     13618627.33      2541175.20     13618600.08
      2541174.61     13617940.16      2541171.45     13617926.47
      2541161.60     13617911.69      2541094.47     13617845.07
      2541078.14     13617823.36      2541074.51     13617800.04
      2541078.34     13617776.75      2541122.81     13617719.03
      2541124.06     13617635.48      2541111.63     13617611.71
      2541035.21     13617534.67      2541028.14     13617523.36
      2541024.60     13617504.87      2541030.31     13617472.81
      2541070.78     13617423.28      2541081.11     13617372.82
      2541114.21     13617334.67      2541122.77     13617319.07
      2541125.07     13617194.99      2541121.52     13617176.45
      2541111.73     13617161.64      2541025.00     13617075.00

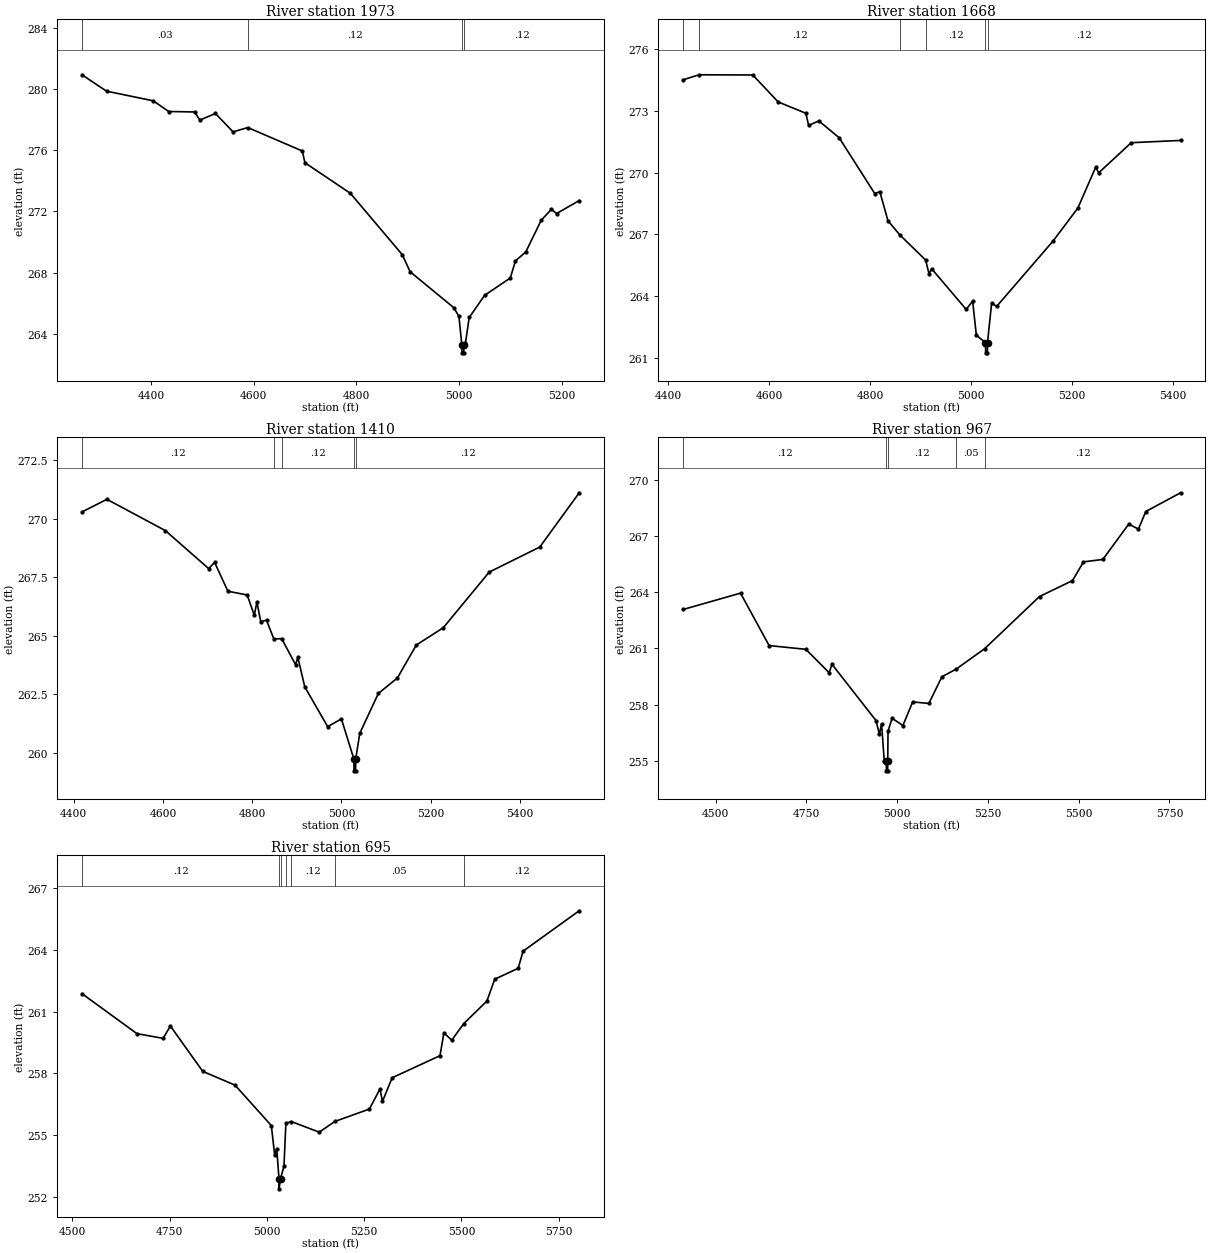
Type RM Length L Ch R = 1,1973,305,305,305
BEGIN DESCRIPTION:
LGII4315
END DESCRIPTION:
XS GIS Cut Line= 3
      2541852.26     13618962.37      2541193.76     13618866.23
      2540890.98     13618880.65
#Sta/Elev= 30
  4265.6  280.93  4313.4  279.86  4404.3  279.23  4434.6  278.53  4484.9  278.50
  4495.3  277.97  4525.6  278.40  4559.9  277.20  4588.7  277.48  4694.8  275.95
  4699.9  275.18  4788.3  273.19  4889.4  269.18  4904.8  268.06  4989.9  265.71
  4999.9  265.14  5005.6  263.26  5005.8  262.76  5009.3  262.76  5009.6  263.26
  5012.6  263.39  5019.9  265.07  5050.0  266.52  5100.0  267.65  5110.0  268.77
  5130.1  269.35  5160.1  271.42  5180.1  272.14  5190.1  271.86  5234.2  272.71
#Mann=4,-1,0
  4265.6    0.03       0  4588.7    0.12       0  5005.6    0.05       0
  5009.6    0.12       0
Bank Sta=5005.6,5009.6
Exp/Cntr=0.3,0.1

Type RM Length L Ch R = 1,1668,258,258,258
BEGIN DESCRIPTION:
LGII4314
END DESCRIPTION:
XS GIS Cut Line= 3
      2541741.69     13618510.56      2541035.15     13618597.07
      2540866.94     13618813.34
#Sta/Elev= 30
  4429.5  274.52  4460.8  274.76  4567.2  274.75  4617.6  273.44  4672.4  272.89
  4678.0  272.30  4698.2  272.52  4738.5  271.70  4809.0  268.99  4819.1  269.08
  4835.2  267.67  4858.7  266.98  4909.9  265.76  4916.7  265.08  4921.7  265.34
  4990.3  263.36  5003.1  263.76  5010.5  262.10  5028.6  261.75  5028.9  261.25
  5032.4  261.25  5032.6  261.75  5040.7  263.65  5050.8  263.51  5161.8  266.66
  5211.6  268.28  5246.9  270.26  5253.2  270.00  5317.5  271.46  5415.3  271.57
#Mann=6,-1,0
  4429.5    0.03       0  4460.8    0.12       0  4858.7    0.05       0
  4909.9    0.12       0  5028.6    0.05       0  5032.6    0.12       0
Bank Sta=5028.6,5032.6
Exp/Cntr=0.3,0.1

Type RM Length L Ch R = 1,1410,443,443,443
BEGIN DESCRIPTION:
LGII4313
END DESCRIPTION:
XS GIS Cut Line= 4
      2541693.67     13618068.34      2541294.70     13618294.27
      2541006.31     13618361.56      2540920.20     13618710.76
#Sta/Elev= 30
  4418.6  270.29  4474.5  270.83  4605.7  269.49  4702.4  267.87  4715.9  268.13
  4745.6  266.90  4788.9  266.74  4804.8  265.87  4810.6  266.44  4819.3  265.60
  4832.2  265.66  4848.6  264.86  4866.2  264.87  4897.3  263.76  4902.4  264.07
  4917.9  262.81  4969.2  261.11  5000.0  261.44  5028.0  259.72  5028.3  259.22
  5031.8  259.22  5032.0  259.72  5041.1  260.82  5082.8  262.53  5125.4  263.19
  5167.9  264.60  5228.3  265.34  5331.3  267.72  5444.6  268.79  5532.9  271.11
#Mann=5,-1,0
  4418.6    0.12       0  4848.6    0.05       0  4866.2    0.12       0
  5028.0    0.05       0  5032.0    0.12       0
Bank Sta=5028,5032
Exp/Cntr=0.3,0.1

Type RM Length L Ch R = 1,967,272,272,272
BEGIN DESCRIPTION:
LGII4312
END DESCRIPTION:
XS GIS Cut Line= 4
      2541626.32     13617558.89      2541155.31     13617871.30
      2540991.89     13618106.81      2540919.97     13618619.84
#Sta/Elev= 30
  4410.7  263.08  4568.3  263.95  4647.1  261.15  4748.3  260.95  4812.5  259.70
  4820.3  260.15  4941.8  257.14  4950.9  256.41  4956.9  256.98  4964.3  254.98
  4969.9  254.96  4970.2  254.46  4973.7  254.46  4973.9  254.96  4974.7  256.58
  4985.9  257.27  5015.6  256.88  5042.6  258.14  5087.2  258.06  5123.0  259.48
  5162.8  259.90  5240.7  260.98  5392.0  263.77  5482.9  264.62  5513.2  265.62
  5566.5  265.75  5637.9  267.64  5664.6  267.37  5684.8  268.31  5780.6  269.31
#Mann=5,-1,0
  4410.7    0.12       0  4969.9    0.05       0  4973.9    0.12       0
  5162.8    0.05       0  5240.7    0.12       0
Bank Sta=4969.9,4973.9
Exp/Cntr=0.3,0.1

Type RM Length L Ch R = 1,695,0,0,0
BEGIN DESCRIPTION:
4824
END DESCRIPTION:
XS GIS Cut Line= 4
      2541565.87     13617482.64      2541021.55     13617703.57
      2540944.71     13617969.32      2540906.40     13618381.16
#Sta/Elev= 30
  4525.0  261.87  4666.2  259.93  4733.5  259.70  4752.2  260.30  4835.3  258.10
  4918.3  257.43  5011.6  255.47  5020.1  254.05  5025.5  254.35  5031.2  252.90
  5031.4  252.40  5035.2  252.90  5044.0  253.49  5049.0  255.59  5063.4  255.66
  5134.7  255.15  5174.9  255.67  5263.5  256.27  5290.9  257.25  5297.1  256.64
  5322.1  257.79  5445.0  258.86  5455.0  259.97  5475.1  259.61  5506.2  260.42
  5565.5  261.51  5585.6  262.57  5645.9  263.10  5658.4  263.93  5802.7  265.89
#Mann=7,-1,0
  4525.0    0.12       0  5031.2    0.05       0  5035.2    0.12       0
  5049.0    0.05       0  5063.4    0.12       0  5174.9    0.05       0
  5506.2    0.12       0
Bank Sta=5031.2,5035.2
Exp/Cntr=0.3,0.1

Chan Stop Cuts=-1