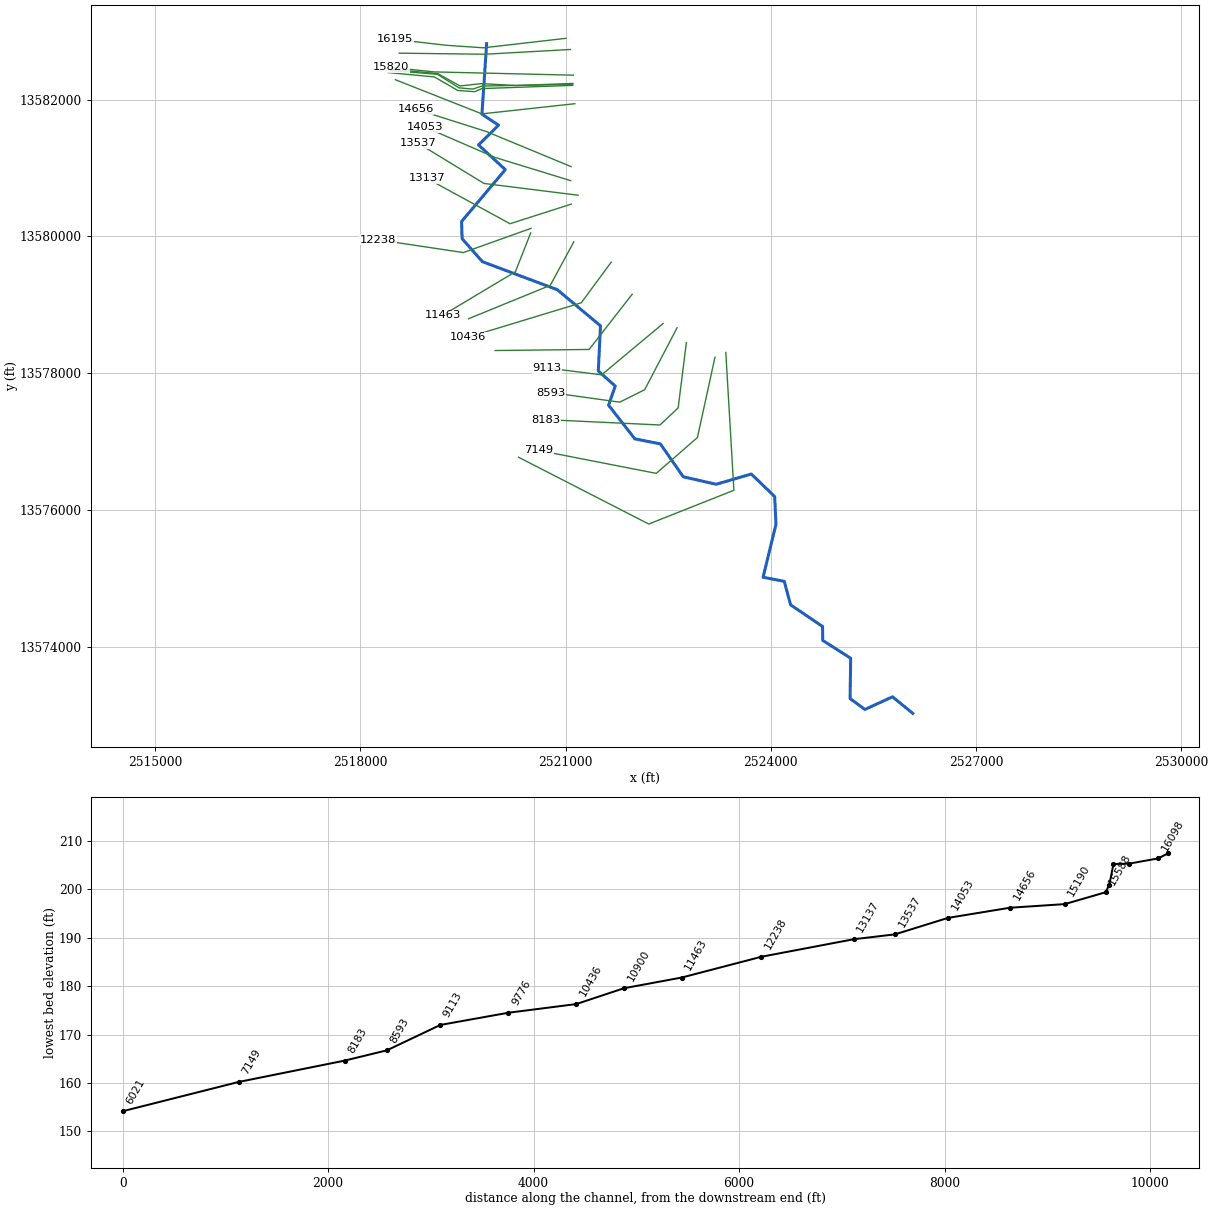
--- TRIB 17 TO GUADALUPE RIVER.prj (project) ---

Proj Title=TRIB 17 TO GUADALUPE RIVER Base Level Engineering
Current Plan=p01
Default Exp/Contr=0.3,0.1
English Units
Geom File=g01
Flow File=f01
Plan File=p01
BEGIN DESCRIPTION:
TRIB 17 TO GUADALUPE RIVER
END DESCRIPTION:

--- TRIB 17 TO GUADALUPE RIVER.p01 (plan) ---

Plan Title=Multiple Run
Short Identifier=Multiple
Geom File=g01
Flow File=f01
Subcritical Flow
K Sum by GR= 0
Std Step Tol= 0.01
Critical Tol= 0.01
Num of Std Step Trials= 20
Max Error Tol= 0.3
Flow Tol Ratio= 0.001
Split Flow NTrial= 30
Split Flow Tol= 0.02
Split Flow Ratio= 0.02
Log Output Level= 0
Friction Slope Method= 1
Unsteady Friction Slope Method= 2
Unsteady Bridges Friction Slope Method= 1
Parabolic Critical Depth
Global Vel Dist=  1 , 1 , 1
Global Log Level= 0
CheckData=True
Encroach Param= -1, 0, 0, 0
BEGIN DESCRIPTION:
Multiple Run
END DESCRIPTION:

--- TRIB 17 TO GUADALUPE RIVER.f01 (steady flow) ---

Flow Title=Multiple
Number of Profiles=7
Profile Names=10-year,25-year,50-year,1pct_min,100-year,1pct_plu,500-year
River Rch & RM= TRIB 17 TO GUADA,Reach-1,16195
     321     491     636     400     798    1592    1241
River Rch & RM= TRIB 17 TO GUADA,Reach-1,10436
     554     879    1167     751    1498    2988    2441
Boundary for River Rch & Prof#=TRIB 17 TO GUADA,Reach-1,1
Up Type=0
Dn Type=3
Dn Slope=0.005
Boundary for River Rch & Prof#=TRIB 17 TO GUADA,Reach-1,2
Up Type=0
Dn Type=3
Dn Slope=0.005
Boundary for River Rch & Prof#=TRIB 17 TO GUADA,Reach-1,3
Up Type=0
Dn Type=3
Dn Slope=0.005
Boundary for River Rch & Prof#=TRIB 17 TO GUADA,Reach-1,4
Up Type=0
Dn Type=3
Dn Slope=0.005
Boundary for River Rch & Prof#=TRIB 17 TO GUADA,Reach-1,5
Up Type=0
Dn Type=3
Dn Slope=0.005
Boundary for River Rch & Prof#=TRIB 17 TO GUADA,Reach-1,6
Up Type=0
Dn Type=3
Dn Slope=0.005
Boundary for River Rch & Prof#=TRIB 17 TO GUADA,Reach-1,7
Up Type=0
Dn Type=3
Dn Slope=0.005

--- TRIB 17 TO GUADALUPE RIVER.g01 (geometry) ---

Geom Title=Existing Conditions

River Reach=TRIB 17 TO GUADA,Reach-1
Reach XY= 30
      2519844.05     13582816.97      2519775.54     13581785.47
      2520018.12     13581624.97      2519725.59     13581335.62
      2520117.50     13580975.00      2519477.69     13580216.49
      2519486.10     13579964.68      2519783.50     13579628.47
      2520877.30     13579219.17      2521508.61     13578691.67
      2521477.06     13578030.85      2521724.82     13577809.91
      2521626.97     13577530.90      2522011.69     13577038.40
      2522385.13     13576964.66      2522718.33     13576484.30
      2523200.12     13576374.71      2523714.38     13576524.40
      2524055.57     13576195.09      2524074.48     13575790.22
      2523886.24     13575014.95      2524195.48     13574955.39
      2524288.37     13574611.68      2524755.95     13574295.39
      2524758.25     13574091.64      2525166.86     13573831.06
      2525157.86     13573241.46      2525374.91     13573082.28
      2525778.23     13573267.16      2526075.00     13573025.00

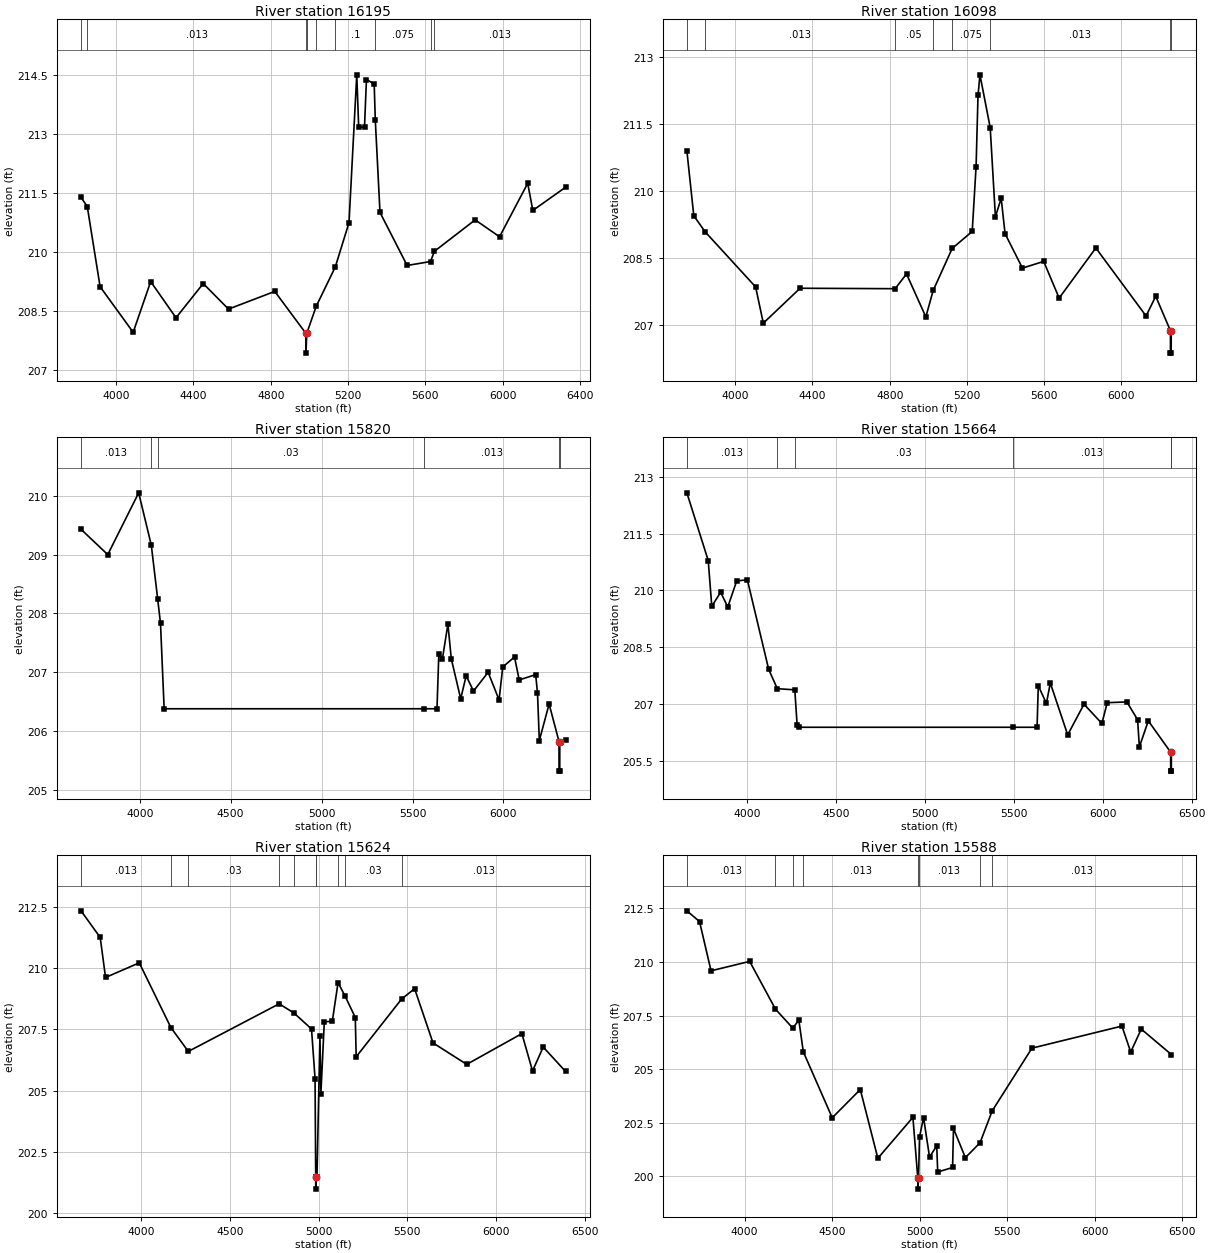
Type RM Length L Ch R = 1,16195,97,97,97
BEGIN DESCRIPTION:
LGII4378
END DESCRIPTION:
XS GIS Cut Line= 4
      2521003.08     13582894.46      2519796.50     13582756.14
      2519257.00     13582792.62      2518510.45     13582879.43
#Sta/Elev= 30
  3818.3  211.38  3850.6  211.15  3917.0  209.11  4088.1  207.95  4178.7  209.24
  4309.6  208.32  4450.5  209.19  4581.3  208.54  4820.6  208.99  4982.0  207.92
  4982.2  207.42  4986.0  207.92  5034.9  208.61  5133.6  209.61  5204.7  210.74
  5244.8  214.50  5254.8  213.17  5284.9  213.17  5294.9  214.38  5335.0  214.27
  5340.7  213.35  5365.0  211.00  5505.4  209.65  5626.5  209.75  5646.4  210.01
  5857.4  210.81  5983.5  210.38  6129.2  211.74  6155.7  211.05  6325.1  211.64
#Mann=9,-1,0
  3818.3   0.075       0  3850.6   0.013       0  4982.0    0.03       0
  4986.0   0.013       0  5034.9    0.05       0  5133.6     0.1       0
  5340.7   0.075       0  5626.5    0.05       0  5646.4   0.013       0
Bank Sta=4982,4986
Exp/Cntr=0.3,0.1

Type RM Length L Ch R = 1,16098,278,278,278
BEGIN DESCRIPTION:
Mapping XS f60d88e1
END DESCRIPTION:
XS GIS Cut Line= 3
      2521070.20     13582731.75      2519824.57     13582662.30
      2518563.73     13582677.49
#Sta/Elev= 30
  3750.0  210.90  3785.8  209.45  3844.8  209.09  4105.8  207.86  4145.8  207.05
  4336.1  207.83  4828.4  207.82  4887.0  208.15  4987.1  207.19  5025.1  207.78
  5123.5  208.72  5227.2  209.10  5247.2  210.55  5257.2  212.14  5267.2  212.60
  5320.3  211.42  5347.2  209.43  5377.2  209.84  5397.2  209.05  5487.2  208.28
  5597.2  208.43  5677.2  207.61  5867.2  208.73  6127.2  207.21  6177.2  207.65
  6253.4  206.88  6253.6  206.38  6257.1  206.38  6257.4  206.88  6258.5  206.88
#Mann=8,-1,0
  3750.0   0.075       0  3844.8   0.013       0  4828.4    0.05       0
  5025.1     0.1       0  5123.5   0.075       0  5320.3   0.013       0
  6253.4    0.05       0  6257.4   0.013       0
Bank Sta=6253.4,6257.4
Exp/Cntr=0.3,0.1

Type RM Length L Ch R = 1,15820,156,156,156
BEGIN DESCRIPTION:
LGII4377
END DESCRIPTION:
XS GIS Cut Line= 3
      2521111.98     13582355.92      2519072.97     13582403.73
      2518451.43     13582469.70
#Sta/Elev= 30
  3677.0  209.43  3824.0  209.00  3994.1  210.05  4063.5  209.16  4098.4  208.25
  4114.1  207.83  4134.1  206.38  5563.2  206.38  5634.5  206.38  5644.5  207.31
  5664.5  207.23  5694.5  207.82  5713.1  207.23  5764.8  206.55  5795.0  206.94
  5835.2  206.68  5915.7  207.00  5976.0  206.53  5996.1  207.09  6060.8  207.26
  6086.6  206.87  6177.1  206.96  6187.2  206.65  6197.2  205.84  6251.1  206.46
  6305.8  205.82  6306.1  205.32  6309.6  205.32  6309.8  205.82  6341.6  205.85
#Mann=6,-1,0
  3677.0   0.013       0  4063.5   0.075       0  4098.4    0.03       0
  5563.2   0.013       0  6305.8    0.03       0  6309.8   0.013       0
Bank Sta=6305.8,6309.8
Exp/Cntr=0.3,0.1

Type RM Length L Ch R = 1,15664,40,40,40
BEGIN DESCRIPTION:
Mapping XS 24d3777a
END DESCRIPTION:
XS GIS Cut Line= 6
      2521104.99     13582234.87      2520279.46     13582204.92
      2519765.14     13582232.27      2519456.33     13582197.87
      2519129.51     13582378.86      2518435.45     13582445.27
#Sta/Elev= 30
  3660.0  212.58  3780.1  210.79  3800.1  209.58  3850.1  209.95  3890.1  209.56
  3940.2  210.25  4000.2  210.28  4120.3  207.91  4168.8  207.40  4267.2  207.37
  4280.4  206.43  4290.4  206.38  5495.5  206.38  5630.3  206.38  5637.0  207.48
  5682.7  207.01  5704.8  207.55  5802.5  206.18  5894.4  206.99  5994.9  206.48
  6025.0  207.03  6135.5  207.05  6195.8  206.58  6205.8  205.86  6256.1  206.55
  6381.9  205.72  6382.1  205.22  6385.6  205.22  6385.9  205.72  6386.2  205.72
#Mann=6,-1,0
  3660.0   0.013       0  4168.8   0.075       0  4267.2    0.03       0
  5495.5   0.013       0  6381.9    0.03       0  6385.9   0.013       0
Bank Sta=6381.9,6385.9
Exp/Cntr=0.3,0.1

Type RM Length L Ch R = 1,15624,36,36,36
BEGIN DESCRIPTION:
LGII4376
END DESCRIPTION:
XS GIS Cut Line= 6
      2521103.07     13582220.55      2519778.84     13582197.01
      2519640.53     13582152.86      2519439.92     13582170.76
      2519126.12     13582368.68      2518439.33     13582423.44
#Sta/Elev= 30
  3660.3  212.36  3768.5  211.27  3798.6  209.63  3988.8  210.23  4167.0  207.58
  4265.3  206.60  4777.5  208.55  4860.3  208.18  4960.1  207.52  4980.1  205.49
  4983.7  201.46  4983.9  200.96  4987.7  201.46  4990.9  201.46  5007.7  207.24
  5012.9  204.87  5032.3  207.82  5077.3  207.83  5109.7  209.42  5149.2  208.87
  5207.0  207.99  5212.0  206.38  5468.5  208.75  5541.6  209.17  5645.1  206.95
  5835.4  206.07  6146.4  207.33  6206.5  205.80  6266.7  206.78  6392.8  205.78
#Mann=10,-1,0
  3660.3   0.013       0  4167.0   0.075       0  4265.3    0.03       0
  4777.5   0.013       0  4860.3    0.03       0  4983.7    0.03       0
  4987.7    0.03       0  5109.7   0.013       0  5149.2    0.03       0
  5468.5   0.013       0
Bank Sta=4983.7,4987.7
Exp/Cntr=0.3,0.1

Type RM Length L Ch R = 1,15588,398,398,398
BEGIN DESCRIPTION:
Mapping XS fc6ef578
END DESCRIPTION:
XS GIS Cut Line= 6
      2521102.41     13582206.69      2519774.27     13582159.81
      2519671.84     13582114.67      2519423.58     13582132.03
      2519079.30     13582330.21      2518403.28     13582394.23
#Sta/Elev= 30
  3669.7  212.39  3742.1  211.89  3807.7  209.59  4028.7  210.03  4176.2  207.80
  4274.7  206.92  4309.9  207.28  4335.3  205.81  4500.7  202.73  4661.1  204.05
  4761.4  200.84  4961.9  202.75  4989.9  199.90  4990.2  199.40  4993.9  199.90
  4999.8  201.84  5022.7  202.74  5056.9  200.90  5098.1  201.42  5103.6  200.20
  5188.8  200.41  5193.8  202.23  5261.8  200.87  5345.4  201.56  5415.0  203.05
  5642.3  205.98  6156.8  207.01  6207.0  205.80  6267.3  206.87  6439.8  205.68
#Mann=8,-1,0
  3669.7   0.013       0  4176.2   0.075       0  4274.7    0.03       0
  4335.3   0.013       0  4989.9    0.03       0  4993.9   0.013       0
  5345.4    0.03       0  5415.0   0.013       0
Bank Sta=4989.9,4993.9
Exp/Cntr=0.3,0.1

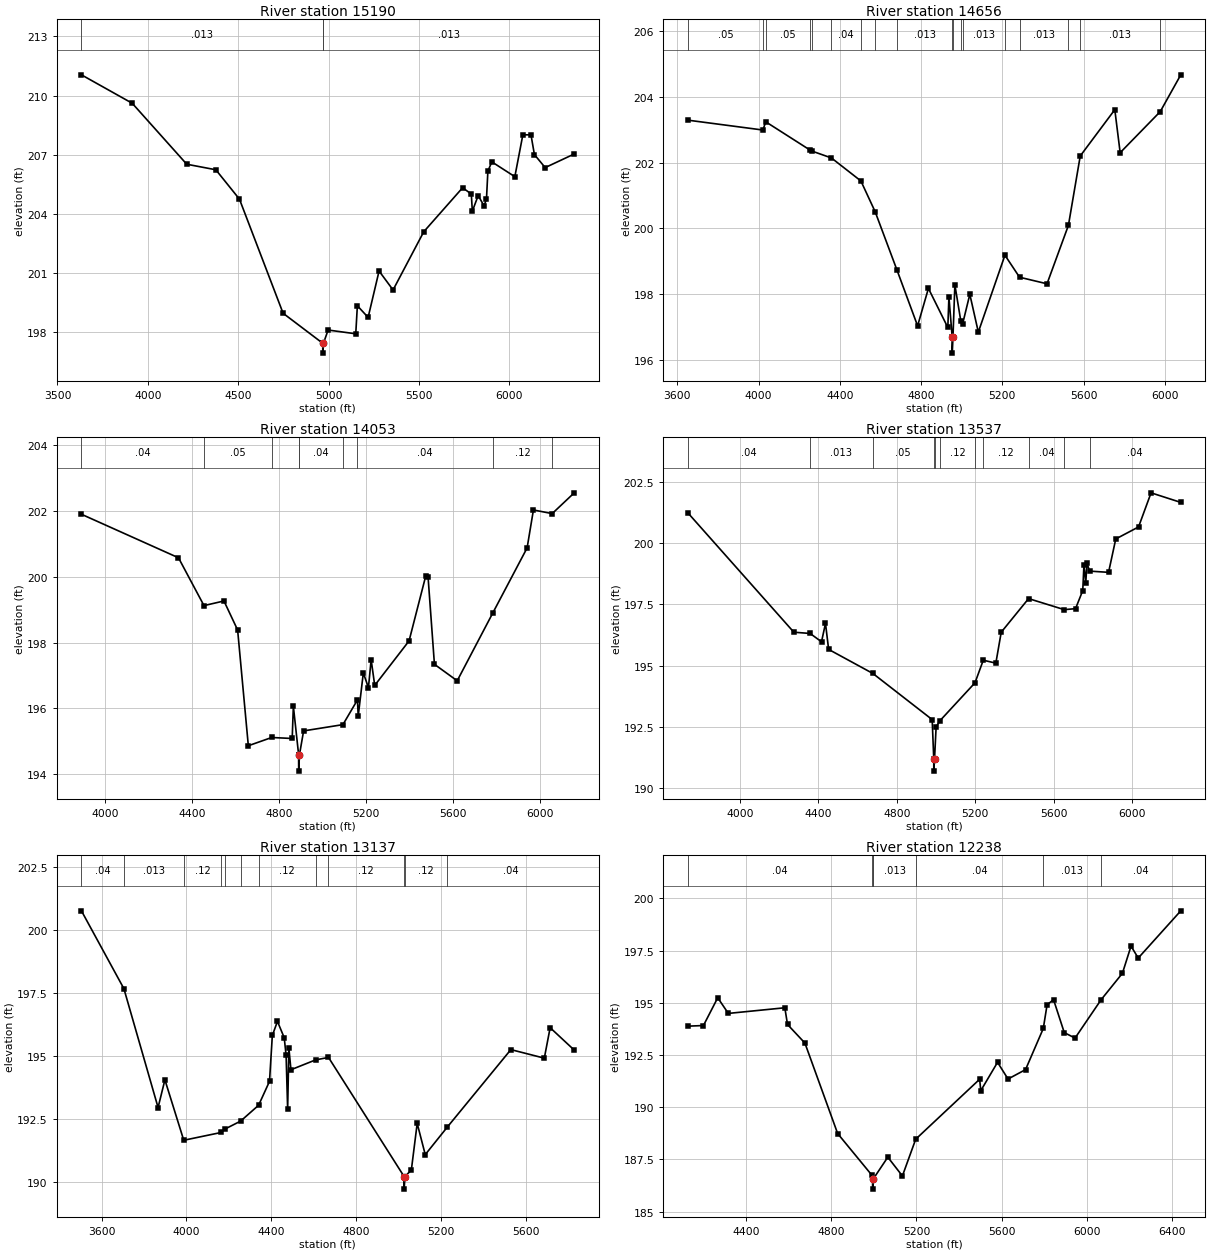
Type RM Length L Ch R = 1,15190,534,534,534
BEGIN DESCRIPTION:
TRIB 17 TO GUADALUPE RIVER 25.0
END DESCRIPTION:
XS GIS Cut Line= 3
      2521134.22     13581938.73      2519774.91     13581790.21
      2518510.48     13582289.14
#Sta/Elev= 30
  3632.6  211.05  3913.5  209.61  4215.3  206.52  4376.2  206.24  4507.0  204.75
  4748.4  198.97  4967.7  197.45  4968.0  196.95  4971.7  197.45  4997.4  198.12
  5150.4  197.93  5159.3  199.35  5218.8  198.76  5279.4  201.11  5356.8  200.15
  5526.7  203.10  5741.7  205.33  5789.8  205.01  5795.4  204.14  5827.7  204.93
  5859.9  204.42  5873.6  204.74  5881.4  206.17  5903.4  206.64  6030.6  205.89
  6074.9  208.01  6119.9  208.01  6138.9  207.01  6198.4  206.35  6359.3  207.04
#Mann=3,-1,0
  3632.6   0.013       0  4967.7    0.03       0  4971.7   0.013       0
Bank Sta=4967.7,4971.7
Exp/Cntr=0.3,0.1

Type RM Length L Ch R = 1,14656,603,603,603
BEGIN DESCRIPTION:
Mapping XS 79fe8651
END DESCRIPTION:
XS GIS Cut Line= 3
      2521078.20     13581019.30      2519844.98     13581529.93
      2518805.60     13581860.36
#Sta/Elev= 30
  3652.7  203.29  4021.4  202.99  4035.6  203.24  4251.0  202.39  4262.6  202.35
  4358.8  202.14  4503.8  201.44  4574.2  200.50  4681.9  198.72  4782.9  197.03
  4836.1  198.17  4931.6  196.98  4937.0  197.91  4953.0  196.70  4953.2  196.20
  4957.0  196.70  4966.3  198.28  4995.7  197.17  5004.4  197.09  5039.9  197.99
  5081.7  196.84  5212.7  199.18  5284.6  198.51  5419.8  198.31  5525.2  200.09
  5583.3  202.20  5753.4  203.61  5779.8  202.30  5977.0  203.55  6078.1  204.67
#Mann=18,-1,0
  3652.7    0.05       0  4021.4    0.04       0  4035.6    0.05       0
  4251.0    0.04       0  4262.6    0.05       0  4358.8    0.04       0
  4503.8    0.05       0  4574.2    0.04       0  4681.9   0.013       0
  4953.0    0.03       0  4957.0   0.013       0  4995.7    0.03       0
  5004.4   0.013       0  5212.7    0.03       0  5284.6   0.013       0
  5525.2    0.12       0  5583.3   0.013       0  5977.0    0.12       0
Bank Sta=4953,4957
Exp/Cntr=0.3,0.1

Type RM Length L Ch R = 1,14053,516,516,516
BEGIN DESCRIPTION:
Mapping XS dd7539dd
END DESCRIPTION:
XS GIS Cut Line= 3
      2521071.56     13580814.43      2519967.41     13581152.97
      2518948.30     13581594.93
#Sta/Elev= 30
  3890.1  201.89  4336.3  200.57  4453.5  199.12  4545.4  199.26  4608.2  198.38
  4657.4  194.87  4764.8  195.12  4859.1  195.09  4864.4  196.07  4888.6  194.60
  4888.9  194.10  4892.6  194.60  4911.5  195.32  5092.3  195.51  5159.1  196.26
  5162.6  195.77  5186.1  197.08  5209.6  196.63  5222.0  197.48  5238.5  196.70
  5396.4  198.05  5472.7  200.01  5483.6  200.00  5513.0  197.34  5617.7  196.84
  5782.4  198.91  5939.1  200.87  5968.1  202.02  6054.4  201.91  6155.8  202.54
#Mann=9,-1,0
  3890.1    0.04       0  4453.5    0.05       0  4764.8    0.04       0
  4888.6    0.04       0  4892.6    0.04       0  5092.3    0.12       0
  5159.1    0.04       0  5782.4    0.12       0  6054.4   0.013       0
Bank Sta=4888.6,4892.6
Exp/Cntr=0.3,0.1

Type RM Length L Ch R = 1,13537,400,400,400
BEGIN DESCRIPTION:
Mapping XS bacbdf81
END DESCRIPTION:
XS GIS Cut Line= 3
      2521180.94     13580600.89      2519805.95     13580772.76
      2518843.48     13581360.65
#Sta/Elev= 30
  3734.6  201.22  4274.7  196.36  4357.6  196.31  4415.8  195.97  4436.0  196.72
  4452.1  195.66  4677.6  194.68  4980.2  192.80  4988.2  191.20  4988.5  190.70
  4992.2  191.20  5000.3  192.50  5020.5  192.76  5198.6  194.30  5240.8  195.22
  5304.9  195.10  5332.3  196.36  5471.9  197.73  5653.8  197.28  5711.4  197.32
  5748.2  198.06  5754.2  199.10  5763.6  198.37  5769.5  199.18  5782.9  198.85
  5879.8  198.80  5916.5  200.16  6032.7  200.65  6096.6  202.04  6248.1  201.65
#Mann=11,-1,0
  3734.6    0.04       0  4357.6   0.013       0  4677.6    0.05       0
  4988.2    0.05       0  4992.2    0.05       0  5020.5    0.12       0
  5198.6    0.04       0  5240.8    0.12       0  5471.9    0.04       0
  5653.8    0.12       0  5782.9    0.04       0
Bank Sta=4988.2,4992.2
Exp/Cntr=0.3,0.1

Type RM Length L Ch R = 1,13137,899,899,899
BEGIN DESCRIPTION:
Mapping XS bc47deac
END DESCRIPTION:
XS GIS Cut Line= 3
      2521082.00     13580470.68      2520186.16     13580184.22
      2518972.65     13580845.67
#Sta/Elev= 30
  3505.0  200.75  3705.1  197.66  3866.2  192.94  3898.4  194.04  3987.2  191.64
  4163.8  191.95  4180.1  192.08  4255.1  192.40  4340.0  193.03  4391.4  193.98
  4404.7  195.80  4428.8  196.36  4460.8  195.71  4469.6  195.01  4476.9  192.87
  4482.6  195.31  4492.4  194.44  4608.2  194.83  4669.4  194.93  5025.7  190.20
  5025.9  189.70  5029.7  190.20  5059.9  190.46  5087.4  192.31  5125.4  191.07
  5230.0  192.17  5528.9  195.24  5686.5  194.90  5714.0  196.11  5827.6  195.22
#Mann=12,-1,0
  3505.0    0.04       0  3705.1   0.013       0  3987.2    0.12       0
  4163.8    0.04       0  4180.1    0.12       0  4255.1    0.04       0
  4340.0    0.12       0  4608.2   0.013       0  4669.4    0.12       0
  5025.7    0.05       0  5029.7    0.12       0  5230.0    0.04       0
Bank Sta=5025.7,5029.7
Exp/Cntr=0.3,0.1

Type RM Length L Ch R = 1,12238,775,775,775
BEGIN DESCRIPTION:
Mapping XS 35bcdd54
END DESCRIPTION:
XS GIS Cut Line= 3
      2520493.42     13580116.50      2519503.87     13579762.35
      2518253.87     13579949.85
#Sta/Elev= 30
  4126.9  193.88  4199.6  193.91  4266.8  195.24  4316.4  194.49  4581.9  194.76
  4594.6  193.96  4676.3  193.07  4830.1  188.74  4990.6  186.75  4994.2  186.58
  4994.4  186.08  4998.2  186.58  5065.7  187.61  5134.2  186.71  5196.8  188.47
  5497.2  191.34  5502.3  190.79  5581.2  192.15  5630.4  191.35  5712.7  191.80
  5796.1  193.77  5813.8  194.90  5844.2  195.15  5894.7  193.57  5945.3  193.31
  6068.0  195.15  6167.7  196.41  6208.2  197.71  6242.1  197.14  6441.9  199.40
#Mann=7,-1,0
  4126.9    0.04       0  4990.6   0.013       0  4994.2    0.03       0
  4998.2   0.013       0  5196.8    0.04       0  5796.1   0.013       0
  6068.0    0.04       0
Bank Sta=4994.2,4998.2
Exp/Cntr=0.3,0.1

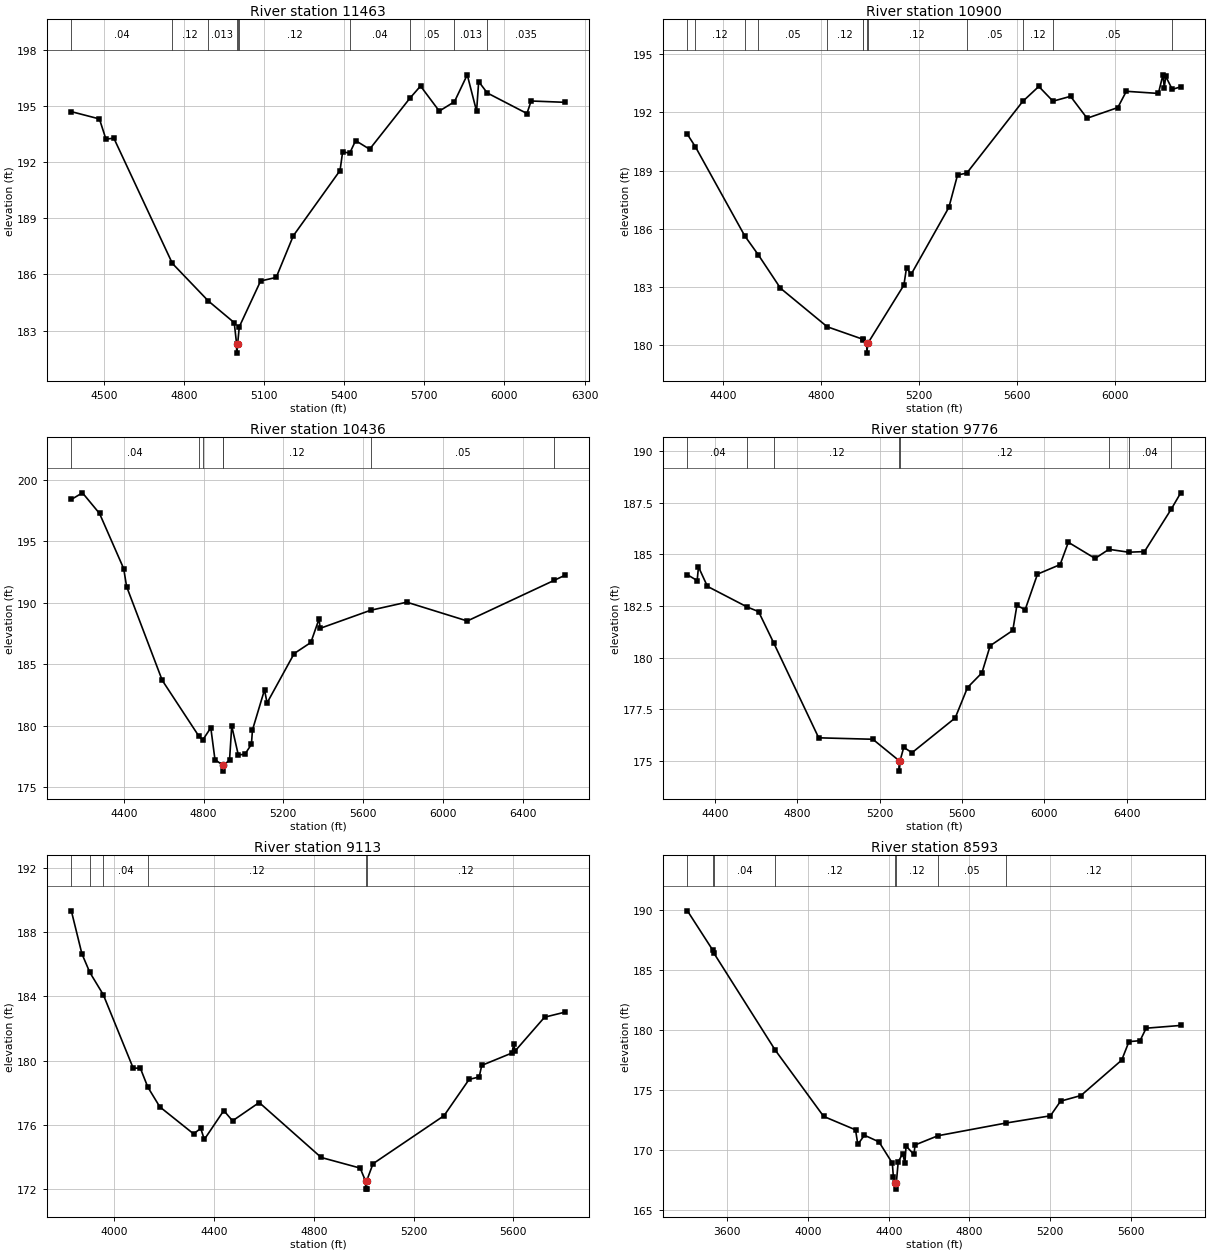
Type RM Length L Ch R = 1,11463,563,563,563
BEGIN DESCRIPTION:
Mapping XS 03144fae
END DESCRIPTION:
XS GIS Cut Line= 3
      2520488.23     13580048.78      2520264.28     13579481.10
      2519201.76     13578845.67
#Sta/Elev= 30
  4377.2  194.71  4482.4  194.32  4506.8  193.24  4536.5  193.29  4755.7  186.59
  4890.5  184.58  4987.5  183.42  4996.3  182.29  4996.5  181.79  5000.3  182.29
  5006.5  183.20  5086.3  185.65  5144.7  185.84  5208.9  188.07  5383.9  191.56
  5393.7  192.56  5420.2  192.49  5442.3  193.16  5494.8  192.70  5645.7  195.43
  5685.5  196.08  5755.7  194.74  5812.5  195.24  5860.5  196.68  5895.5  194.73
  5903.3  196.32  5935.5  195.71  6084.2  194.61  6099.8  195.28  6225.5  195.21
#Mann=10,-1,0
  4377.2    0.04       0  4755.7    0.12       0  4890.5   0.013       0
  4996.3    0.03       0  5000.3   0.013       0  5006.5    0.12       0
  5420.2    0.04       0  5645.7    0.05       0  5812.5   0.013       0
  5935.5   0.035       0
Bank Sta=4996.3,5000.3
Exp/Cntr=0.3,0.1

Type RM Length L Ch R = 1,10900,464,464,464
BEGIN DESCRIPTION:
Mapping XS 046a7342
END DESCRIPTION:
XS GIS Cut Line= 3
      2521118.43     13579918.56      2520774.70     13579283.18
      2519578.36     13578794.24
#Sta/Elev= 30
  4255.0  190.87  4287.9  190.22  4489.2  185.63  4545.2  184.64  4635.0  182.93
  4826.0  180.94  4970.6  180.30  4971.2  180.26  4987.5  180.08  4987.8  179.58
  4991.5  180.08  5139.1  183.09  5149.9  183.99  5168.5  183.64  5322.8  187.10
  5358.2  188.77  5396.0  188.87  5624.6  192.57  5690.1  193.34  5748.0  192.58
  5819.7  192.83  5887.2  191.70  6012.7  192.25  6047.5  193.09  6178.4  192.98
  6197.1  193.94  6202.5  193.28  6208.6  193.86  6235.1  193.19  6269.8  193.32
#Mann=13,-1,0
  4255.0    0.04       0  4287.9    0.12       0  4489.2    0.04       0
  4545.2    0.05       0  4826.0    0.12       0  4970.6   0.013       0
  4971.2    0.12       0  4987.5    0.05       0  4991.5    0.12       0
  5396.0    0.05       0  5624.6    0.12       0  5748.0    0.05       0
  6235.1   0.013       0
Bank Sta=4987.5,4991.5
Exp/Cntr=0.3,0.1

Type RM Length L Ch R = 1,10436,660,660,660
BEGIN DESCRIPTION:
Mapping XS 91651f0a
END DESCRIPTION:
XS GIS Cut Line= 3
      2521665.30     13579621.69      2521227.83     13579027.97
      2519568.15     13578523.31
#Sta/Elev= 30
  4137.5  198.42  4193.2  198.96  4278.8  197.28  4399.9  192.79  4414.5  191.33
  4593.0  183.70  4777.6  179.13  4796.2  178.85  4836.4  179.84  4857.3  177.24
  4896.0  176.81  4896.3  176.31  4900.0  176.81  4930.2  177.19  4941.3  179.98
  4974.2  177.63  5007.1  177.68  5039.9  178.49  5045.2  179.66  5105.6  182.93
  5118.3  181.86  5254.2  185.88  5337.8  186.78  5379.0  188.71  5384.2  187.93
  5636.9  189.40  5818.6  190.06  6121.7  188.53  6557.5  191.84  6609.7  192.24
#Mann=7,-1,0
  4137.5    0.04       0  4777.6   0.013       0  4796.2    0.12       0
  4896.0    0.05       0  4900.0    0.12       0  5636.9    0.05       0
  6557.5   0.013       0
Bank Sta=4896,4900
Exp/Cntr=0.3,0.1

Type RM Length L Ch R = 1,9776,663,663,663
BEGIN DESCRIPTION:
Mapping XS 704ee8e4
END DESCRIPTION:
XS GIS Cut Line= 3
      2521972.63     13579152.99      2521342.41     13578345.68
      2519968.67     13578330.07
#Sta/Elev= 30
  4265.6  184.01  4313.0  183.73  4319.4  184.39  4362.8  183.45  4556.6  182.45
  4611.5  182.23  4684.4  180.73  4903.7  176.13  5166.9  176.06  5295.2  175.02
  5295.4  174.52  5299.2  175.02  5317.2  175.67  5357.2  175.41  5567.2  177.09
  5627.2  178.56  5697.2  179.27  5737.2  180.58  5847.2  181.32  5867.2  182.53
  5907.2  182.32  5967.2  184.04  6077.2  184.50  6117.2  185.58  6247.2  184.80
  6314.5  185.24  6410.1  185.10  6487.3  185.13  6616.7  187.17  6663.6  187.97
#Mann=8,-1,0
  4265.6    0.04       0  4556.6   0.013       0  4684.4    0.12       0
  5295.2    0.05       0  5299.2    0.12       0  6314.5    0.05       0
  6410.1    0.04       0  6616.7    0.05       0
Bank Sta=5295.2,5299.2
Exp/Cntr=0.3,0.1

Type RM Length L Ch R = 1,9113,520,520,520
BEGIN DESCRIPTION:
TRIB 17 TO GUADALUPE RIVER 15.0
END DESCRIPTION:
XS GIS Cut Line= 3
      2522425.02     13578725.01      2521525.00     13577975.00
      2520724.99     13578075.00
#Sta/Elev= 30
  3828.0  189.32  3870.3  186.65  3902.0  185.49  3956.1  184.10  4076.0  179.53
  4104.6  179.53  4134.6  178.35  4182.7  177.12  4318.1  175.44  4346.8  175.78
  4361.1  175.09  4439.2  176.89  4474.3  176.25  4581.1  177.39  4829.7  173.97
  4985.9  173.31  5007.6  172.50  5007.9  172.00  5011.4  172.00  5011.6  172.50
  5037.4  173.58  5322.1  176.57  5422.8  178.83  5463.1  178.98  5473.2  179.70
  5594.2  180.47  5601.7  181.01  5606.7  180.59  5725.2  182.70  5805.8  183.01
#Mann=6,-1,0
  3828.0    0.04       0  3902.0   0.013       0  3956.1    0.04       0
  4134.6    0.12       0  5007.6    0.05       0  5011.6    0.12       0
Bank Sta=5007.6,5011.6
Exp/Cntr=0.3,0.1

Type RM Length L Ch R = 1,8593,410,410,410
BEGIN DESCRIPTION:
Mapping XS 5154f44b
END DESCRIPTION:
XS GIS Cut Line= 4
      2522628.86     13578663.37      2522154.91     13577757.14
      2521790.33     13577574.85      2520785.11     13577715.47
#Sta/Elev= 30
  3402.2  189.95  3528.7  186.65  3532.4  186.45  3837.6  178.34  4077.5  172.82
  4235.5  171.70  4246.8  170.49  4279.7  171.25  4351.6  170.70  4417.8  168.93
  4423.3  167.74  4433.6  167.26  4433.9  166.76  4437.6  167.26  4447.1  169.04
  4469.5  169.72  4480.3  168.92  4485.9  170.35  4525.1  169.65  4530.6  170.44
  4644.2  171.21  4982.0  172.27  5201.4  172.87  5251.9  174.09  5352.8  174.56
  5554.8  177.51  5590.8  179.05  5645.7  179.13  5676.0  180.17  5847.5  180.40
#Mann=8,-1,0
  3402.2    0.04       0  3528.7   0.013       0  3532.4    0.04       0
  3837.6    0.12       0  4433.6    0.05       0  4437.6    0.12       0
  4644.2    0.05       0  4982.0    0.12       0
Bank Sta=4433.6,4437.6
Exp/Cntr=0.3,0.1

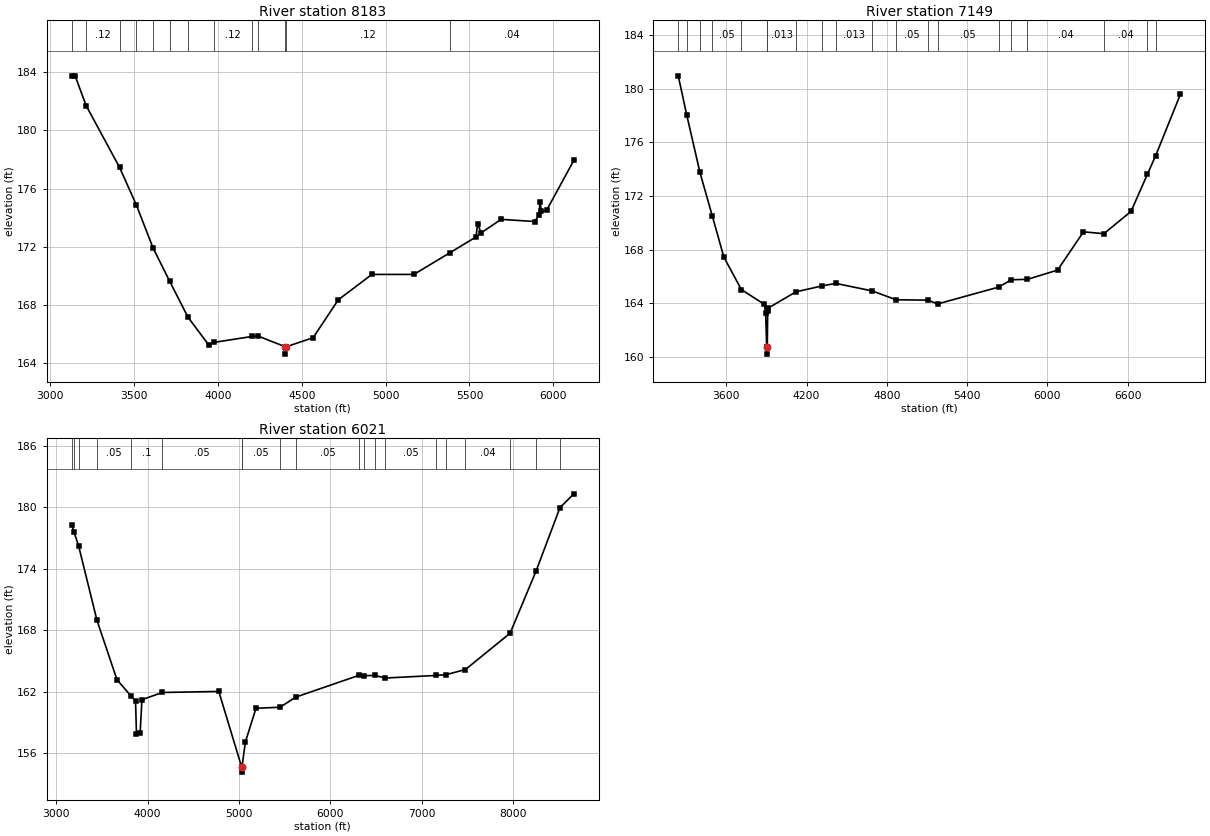
Type RM Length L Ch R = 1,8183,1034,1034,1034
BEGIN DESCRIPTION:
Mapping XS 07f45d26
END DESCRIPTION:
XS GIS Cut Line= 4
      2522764.28     13578444.61      2522644.49     13577491.51
      2522378.87     13577241.51      2520712.16     13577319.64
#Sta/Elev= 30
  3128.5  183.72  3148.3  183.74  3214.4  181.69  3413.8  177.45  3513.4  174.88
  3613.1  171.93  3712.8  169.63  3821.2  167.18  3944.5  165.28  3979.4  165.45
  4202.0  165.85  4239.9  165.88  4402.4  165.14  4402.7  164.64  4406.4  165.14
  4567.9  165.77  4718.0  168.37  4918.2  170.11  5168.5  170.11  5383.7  171.60
  5538.9  172.68  5548.9  173.60  5569.0  172.96  5689.1  173.89  5889.3  173.74
  5915.4  174.20  5920.4  175.07  5929.4  174.43  5959.4  174.50  6122.4  177.94
#Mann=13,-1,0
  3128.5    0.04       0  3214.4    0.12       0  3413.8    0.04       0
  3513.4    0.12       0  3613.1    0.05       0  3712.8    0.12       0
  3821.2    0.05       0  3979.4    0.12       0  4202.0    0.05       0
  4239.9    0.12       0  4402.4    0.05       0  4406.4    0.12       0
  5383.7    0.04       0
Bank Sta=4402.4,4406.4
Exp/Cntr=0.3,0.1

Type RM Length L Ch R = 1,7149,1128,1128,1128
BEGIN DESCRIPTION:
LGII4457
END DESCRIPTION:
XS GIS Cut Line= 4
      2523182.79     13578233.05      2522925.96     13577057.57
      2522323.42     13576534.05      2520604.64     13576869.90
#Sta/Elev= 30
  3241.3  180.95  3304.7  178.04  3403.2  173.77  3496.2  170.50  3582.3  167.45
  3713.0  165.03  3884.2  163.93  3894.4  163.32  3902.6  160.72  3902.9  160.22
  3906.6  160.72  3910.0  163.41  3915.1  163.66  4121.2  164.86  4316.7  165.30
  4418.2  165.49  4689.8  164.93  4870.1  164.27  5106.9  164.24  5180.7  163.96
  5635.3  165.21  5730.9  165.76  5851.2  165.79  6076.6  166.48  6270.2  169.33
  6422.5  169.19  6625.6  170.85  6748.0  173.62  6808.9  174.98  6994.0  179.56
#Mann=20,-1,0
  3241.3    0.12       0  3304.7    0.05       0  3403.2    0.12       0
  3496.2    0.05       0  3713.0   0.013       0  3902.6    0.05       0
  3906.6   0.013       0  4121.2    0.05       0  4316.7    0.12       0
  4418.2   0.013       0  4689.8    0.05       0  4870.1    0.05       0
  5106.9    0.12       0  5180.7    0.05       0  5635.3    0.04       0
  5730.9    0.05       0  5851.2    0.04       0  6422.5    0.04       0
  6748.0   0.013       0  6808.9    0.04       0
Bank Sta=3902.6,3906.6
Exp/Cntr=0.3,0.1

Type RM Length L Ch R = 1,6021,0,0,0
BEGIN DESCRIPTION:
LGII4458
END DESCRIPTION:
XS GIS Cut Line= 4
      2523340.83     13578302.19      2523459.37     13576287.10
      2522214.76     13575793.21      2520310.29     13576770.12
#Sta/Elev= 30
  3169.7  178.31  3194.5  177.59  3243.7  176.28  3445.6  168.99  3664.6  163.20
  3818.2  161.61  3868.1  161.09  3878.1  157.93  3918.2  157.99  3938.2  161.25
  4161.9  161.95  4779.7  162.05  5029.9  154.68  5030.2  154.18  5033.9  154.68
  5070.2  157.10  5186.8  160.41  5450.3  160.51  5622.5  161.50  6320.4  163.64
  6372.2  163.58  6487.1  163.62  6601.5  163.36  7157.1  163.61  7269.3  163.69
  7480.7  164.19  7969.4  167.73  8253.8  173.79  8516.1  179.99  8667.7  181.33
#Mann=20,-1,0
  3169.7    0.12       0  3194.5    0.05       0  3243.7    0.12       0
  3445.6    0.05       0  3818.2     0.1       0  4161.9    0.05       0
  5029.9    0.05       0  5033.9    0.05       0  5450.3    0.12       0
  5622.5    0.05       0  6320.4    0.04       0  6372.2    0.05       0
  6487.1    0.04       0  6601.5    0.05       0  7157.1    0.04       0
  7269.3   0.013       0  7480.7    0.04       0  7969.4    0.04       0
  8253.8    0.05       0  8516.1    0.04       0
Bank Sta=5029.9,5033.9
Exp/Cntr=0.3,0.1

Chan Stop Cuts=-1