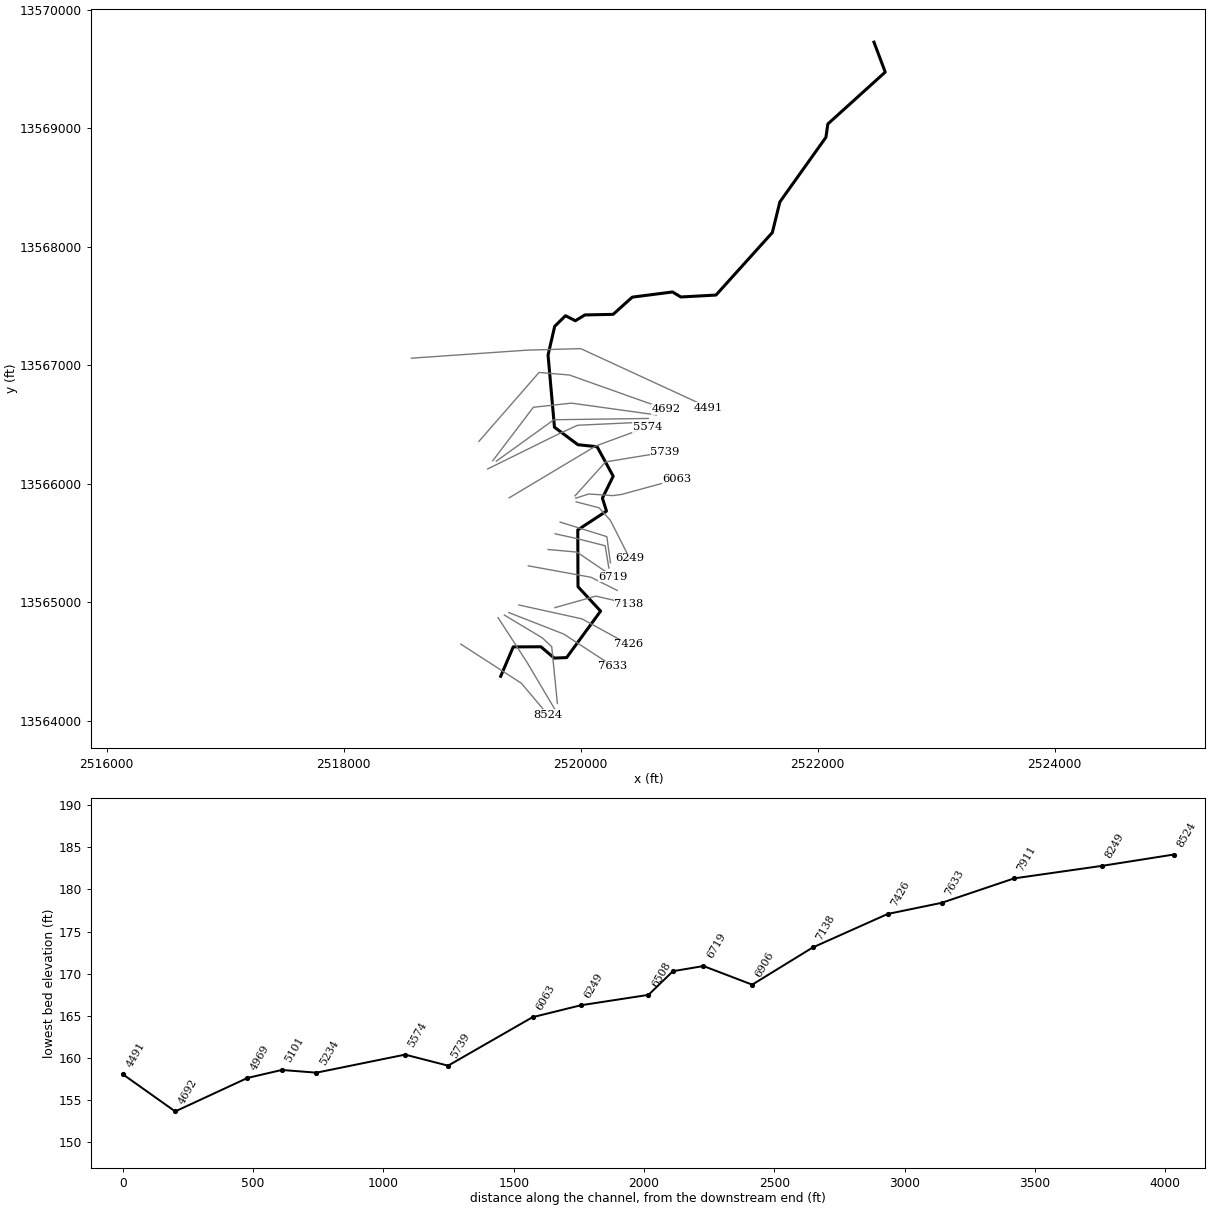
--- TRIB 18 TO GUADALUPE RIVER.prj (project) ---

Proj Title=TRIB 18 TO GUADALUPE RIVER Base Level Engineering
Current Plan=p01
Default Exp/Contr=0.3,0.1
English Units
Geom File=g01
Flow File=f01
Plan File=p01
BEGIN DESCRIPTION:
TRIB 18 TO GUADALUPE RIVER
END DESCRIPTION:

--- TRIB 18 TO GUADALUPE RIVER.p01 (plan) ---

Plan Title=Multiple Run
Short Identifier=Multiple
Geom File=g01
Flow File=f01
Subcritical Flow
K Sum by GR= 0
Std Step Tol= 0.01
Critical Tol= 0.01
Num of Std Step Trials= 20
Max Error Tol= 0.3
Flow Tol Ratio= 0.001
Split Flow NTrial= 30
Split Flow Tol= 0.02
Split Flow Ratio= 0.02
Log Output Level= 0
Friction Slope Method= 1
Unsteady Friction Slope Method= 2
Unsteady Bridges Friction Slope Method= 1
Parabolic Critical Depth
Global Vel Dist=  1 , 1 , 1
Global Log Level= 0
CheckData=True
Encroach Param= -1, 0, 0, 0
BEGIN DESCRIPTION:
Multiple Run
END DESCRIPTION:

--- TRIB 18 TO GUADALUPE RIVER.f01 (steady flow) ---

Flow Title=Multiple
Number of Profiles=7
Profile Names=10-year,25-year,50-year,1pct_min,100-year,1pct_plu,500-year
River Rch & RM= TRIB 18 TO GUADA,Reach-1,8524
     583     935    1252     813    1622    3236    2693
River Rch & RM= TRIB 18 TO GUADA,Reach-1,5739
    1016    1683    2303    1524    3040    6067    5253
Boundary for River Rch & Prof#=TRIB 18 TO GUADA,Reach-1,1
Up Type=0
Dn Type=3
Dn Slope=0.005
Boundary for River Rch & Prof#=TRIB 18 TO GUADA,Reach-1,2
Up Type=0
Dn Type=3
Dn Slope=0.005
Boundary for River Rch & Prof#=TRIB 18 TO GUADA,Reach-1,3
Up Type=0
Dn Type=3
Dn Slope=0.005
Boundary for River Rch & Prof#=TRIB 18 TO GUADA,Reach-1,4
Up Type=0
Dn Type=3
Dn Slope=0.005
Boundary for River Rch & Prof#=TRIB 18 TO GUADA,Reach-1,5
Up Type=0
Dn Type=3
Dn Slope=0.005
Boundary for River Rch & Prof#=TRIB 18 TO GUADA,Reach-1,6
Up Type=0
Dn Type=3
Dn Slope=0.005
Boundary for River Rch & Prof#=TRIB 18 TO GUADA,Reach-1,7
Up Type=0
Dn Type=3
Dn Slope=0.005

--- TRIB 18 TO GUADALUPE RIVER.g01 (geometry) ---

Geom Title=Existing Conditions

River Reach=TRIB 18 TO GUADA,Reach-1
Reach XY= 30
      2519325.00     13564375.00      2519430.65     13564623.03
      2519664.56     13564623.94      2519776.50     13564528.47
      2519881.17     13564532.76      2520167.92     13564925.00
      2519977.06     13565130.85      2519975.33     13565609.97
      2520217.62     13565768.67      2520183.05     13565878.31
      2520274.19     13566063.06      2520138.67     13566311.77
      2519976.56     13566328.76      2519778.54     13566476.46
      2519724.55     13567085.19      2519780.47     13567327.48
      2519871.58     13567417.19      2519954.79     13567374.79
      2520035.50     13567423.76      2520273.54     13567428.54
      2520435.43     13567573.95      2520775.00     13567617.44
      2520844.98     13567575.18      2521141.76     13567591.43
      2521617.18     13568118.81      2521680.83     13568377.30
      2522069.48     13568922.57      2522085.52     13569034.79
      2522569.94     13569472.71      2522475.00     13569725.00

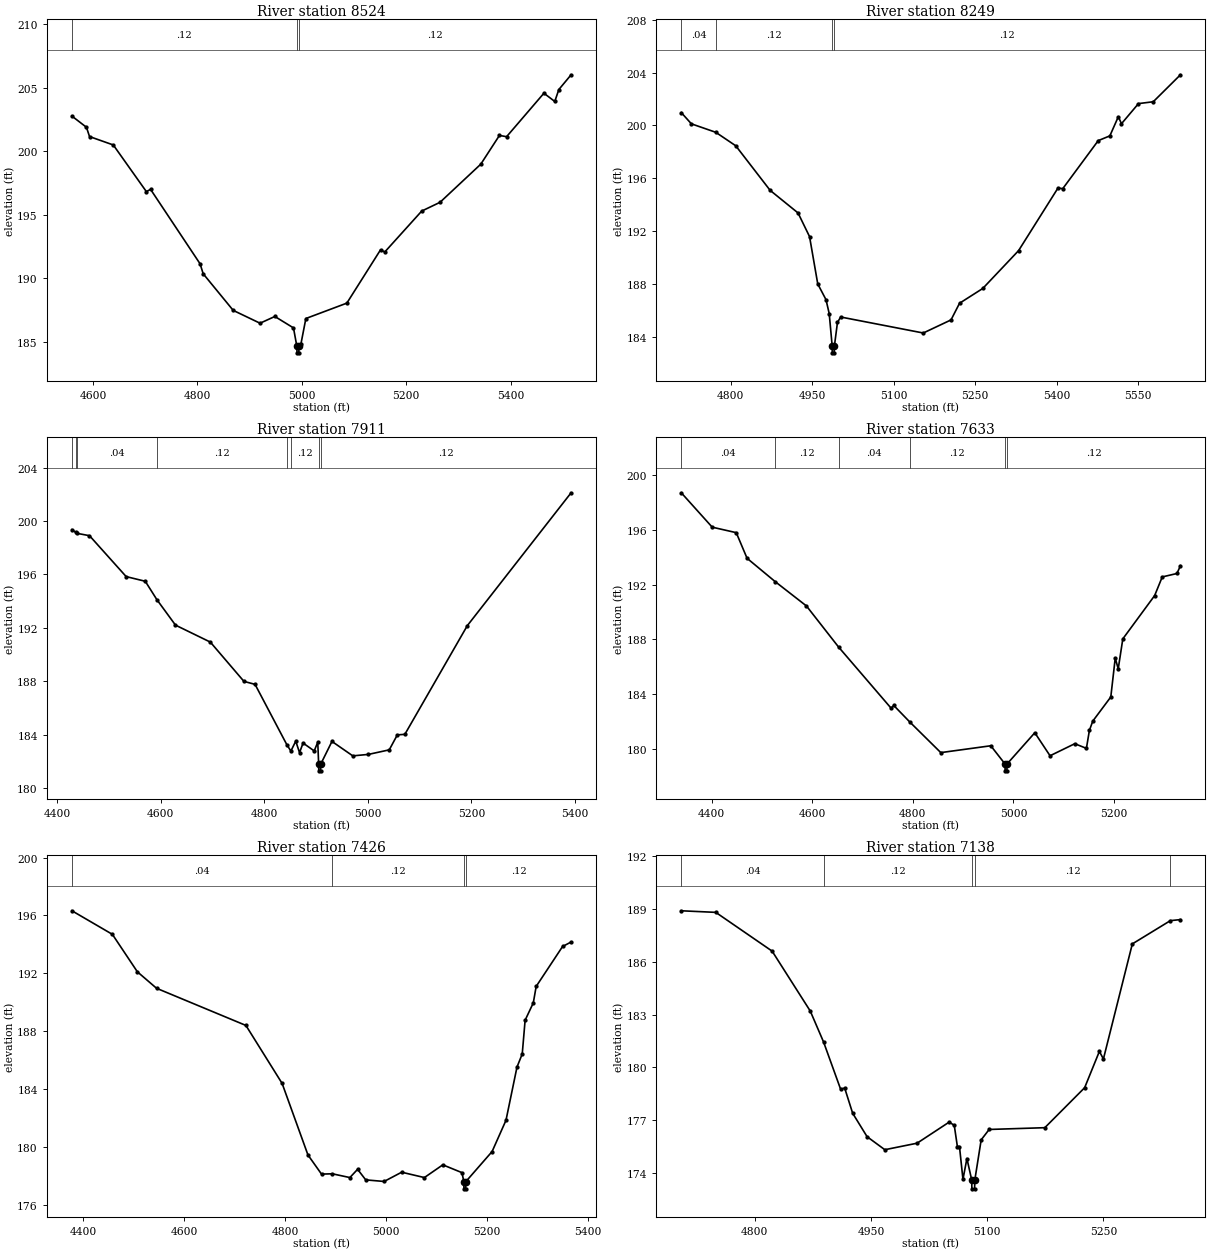
Type RM Length L Ch R = 1,8524,275,275,275
BEGIN DESCRIPTION:
LGII4511
END DESCRIPTION:
XS GIS Cut Line= 3
      2518988.48     13564646.22      2519499.74     13564316.04
      2519723.31     13564049.89
#Sta/Elev= 30
  4559.7  202.76  4587.5  201.88  4593.4  201.15  4638.9  200.49  4702.3  196.82
  4710.3  197.00  4805.2  191.14  4811.1  190.36  4868.6  187.48  4920.0  186.47
  4948.4  187.00  4984.1  186.10  4990.6  184.64  4990.8  184.14  4994.3  184.14
  4994.6  184.64  4998.5  184.87  5007.8  186.84  5086.3  188.05  5150.8  192.24
  5158.9  192.07  5229.7  195.29  5264.8  195.98  5342.9  198.98  5378.6  201.24
  5392.3  201.14  5463.8  204.56  5484.6  203.91  5492.4  204.85  5515.9  206.01
#Mann=3,-1,0
  4559.7    0.12       0  4990.6    0.05       0  4994.6    0.12       0
Bank Sta=4990.6,4994.6
Exp/Cntr=0.3,0.1

Type RM Length L Ch R = 1,8249,338,338,338
BEGIN DESCRIPTION:
LGII4510
END DESCRIPTION:
XS GIS Cut Line= 3
      2519302.70     13564869.90      2519547.68     13564491.79
      2519786.46     13564088.52
#Sta/Elev= 30
  4708.8  200.97  4727.4  200.12  4772.3  199.48  4809.1  198.46  4872.4  195.09
  4923.8  193.38  4945.0  191.59  4960.1  188.01  4975.3  186.82  4981.2  185.77
  4986.7  183.30  4986.9  182.80  4990.4  182.80  4990.7  183.30  4996.4  185.10
  5002.3  185.51  5154.4  184.30  5205.5  185.29  5221.2  186.55  5264.0  187.67
  5329.9  190.53  5402.4  195.26  5411.3  195.22  5476.6  198.85  5498.0  199.21
  5513.6  200.66  5519.4  200.13  5550.7  201.65  5577.9  201.79  5628.0  203.83
#Mann=4,-1,0
  4708.8    0.04       0  4772.3    0.12       0  4986.7    0.05       0
  4990.7    0.12       0
Bank Sta=4986.7,4990.7
Exp/Cntr=0.3,0.1

Type RM Length L Ch R = 1,7911,278,278,278
BEGIN DESCRIPTION:
LGII4509
END DESCRIPTION:
XS GIS Cut Line= 4
      2519355.92     13564891.25      2519675.50     13564699.50
      2519755.39     13564624.94      2519803.32     13564145.61
#Sta/Elev= 30
  4428.9  199.35  4436.6  199.14  4438.2  199.08  4462.8  198.90  4533.6  195.84
  4570.5  195.49  4592.8  194.12  4628.8  192.21  4696.1  190.94  4761.0  188.00
  4782.4  187.78  4844.0  183.25  4851.6  182.79  4861.0  183.53  4868.3  182.67
  4875.1  183.39  4896.6  182.80  4903.5  183.45  4905.2  181.81  4905.4  181.31
  4908.9  181.31  4909.2  181.81  4930.9  183.51  4971.1  182.43  5001.3  182.54
  5041.5  182.88  5057.1  184.00  5071.6  184.04  5192.2  192.17  5392.6  202.11
#Mann=8,-1,0
  4428.9    0.04       0  4436.6    0.12       0  4438.2    0.04       0
  4592.8    0.12       0  4844.0    0.04       0  4851.6    0.12       0
  4905.2    0.05       0  4909.2    0.12       0
Bank Sta=4905.2,4909.2
Exp/Cntr=0.3,0.1

Type RM Length L Ch R = 1,7633,207,207,207
BEGIN DESCRIPTION:
LGII4508
END DESCRIPTION:
XS GIS Cut Line= 3
      2519393.21     13564912.55      2519856.58     13564731.46
      2520270.89     13564460.57
#Sta/Elev= 30
  4339.7  198.70  4401.2  196.19  4449.0  195.79  4470.5  193.92  4526.3  192.22
  4588.6  190.44  4652.3  187.45  4756.9  182.98  4762.2  183.18  4793.9  181.98
  4855.7  179.74  4955.1  180.24  4983.4  178.91  4983.6  178.41  4987.1  178.41
  4987.4  178.91  5042.6  181.19  5072.9  179.51  5122.1  180.39  5145.2  180.05
  5151.2  181.37  5157.9  182.04  5193.7  183.80  5202.5  186.63  5208.5  185.86
  5217.6  188.04  5280.9  191.20  5296.0  192.56  5325.2  192.81  5332.2  193.38
#Mann=6,-1,0
  4339.7    0.04       0  4526.3    0.12       0  4652.3    0.04       0
  4793.9    0.12       0  4983.4    0.05       0  4987.4    0.12       0
Bank Sta=4983.4,4987.4
Exp/Cntr=0.3,0.1

Type RM Length L Ch R = 1,7426,288,288,288
BEGIN DESCRIPTION:
LGII4507
END DESCRIPTION:
XS GIS Cut Line= 3
      2519478.42     13564976.46      2520011.03     13564859.28
      2520399.84     13564646.24
#Sta/Elev= 30
  4377.6  196.32  4457.7  194.69  4507.2  192.10  4545.2  190.96  4722.2  188.39
  4793.9  184.38  4845.1  179.43  4871.9  178.11  4893.4  178.13  4928.1  177.87
  4943.4  178.44  4959.5  177.71  4995.9  177.60  5030.7  178.24  5075.7  177.87
  5112.2  178.75  5150.1  178.21  5153.8  177.59  5154.0  177.09  5157.5  177.09
  5157.8  177.59  5209.8  179.67  5237.3  181.83  5259.1  185.51  5269.5  186.42
  5275.2  188.75  5291.4  189.95  5297.1  191.09  5349.4  193.85  5366.3  194.16
#Mann=4,-1,0
  4377.6    0.04       0  4893.4    0.12       0  5153.8    0.05       0
  5157.8    0.12       0
Bank Sta=5153.8,5157.8
Exp/Cntr=0.3,0.1

Type RM Length L Ch R = 1,7138,232,232,232
BEGIN DESCRIPTION:
Mapping XS 1e194895
END DESCRIPTION:
XS GIS Cut Line= 3
      2519782.21     13564954.26      2520127.72     13565051.49
      2520405.46     13564987.26
#Sta/Elev= 30
  4705.3  188.89  4749.8  188.80  4822.5  186.60  4871.7  183.20  4888.9  181.44
  4910.9  178.76  4916.1  178.83  4926.4  177.40  4945.0  176.07  4967.9  175.33
  5009.5  175.70  5051.0  176.90  5057.5  176.71  5061.5  175.51  5064.2  175.51
  5068.7  173.65  5073.8  174.83  5080.0  173.61  5080.2  173.11  5083.7  173.11
  5084.0  173.61  5092.2  175.89  5102.5  176.48  5174.3  176.58  5225.7  178.85
  5244.7  180.91  5249.9  180.48  5287.2  187.01  5336.3  188.33  5349.3  188.39
#Mann=5,-1,0
  4705.3    0.04       0  4888.9    0.12       0  5080.0    0.05       0
  5084.0    0.12       0  5336.3   0.013       0
Bank Sta=5080,5084
Exp/Cntr=0.3,0.1

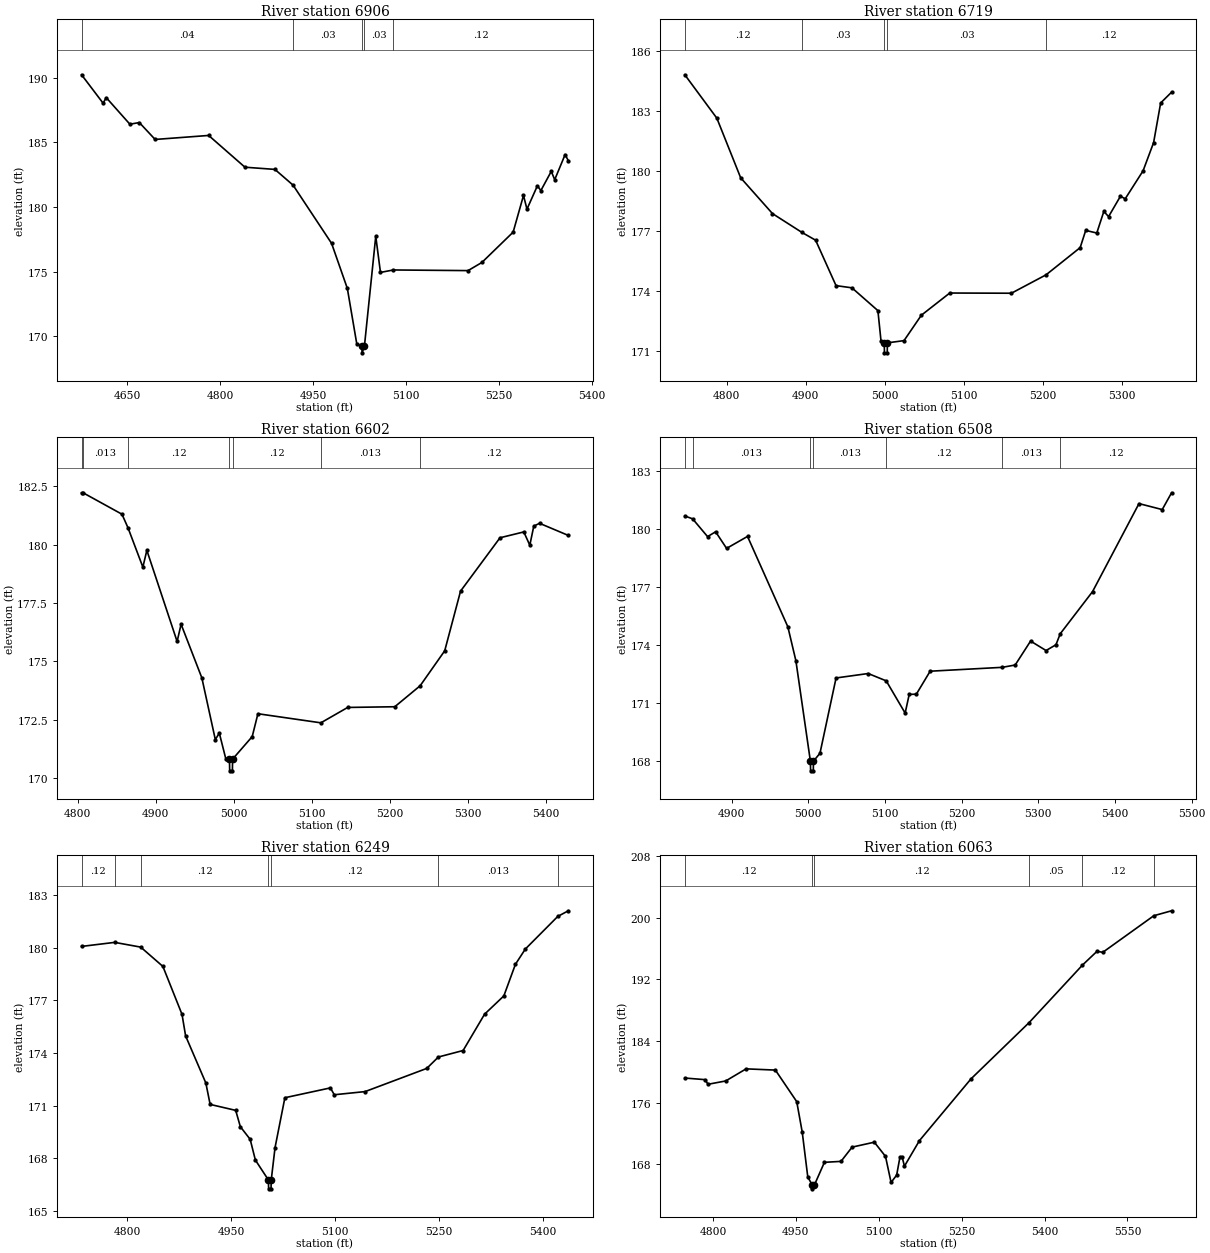
Type RM Length L Ch R = 1,6906,187,187,187
BEGIN DESCRIPTION:
LGII4505
END DESCRIPTION:
XS GIS Cut Line= 3
      2519558.36     13565306.66      2520085.60     13565210.80
      2520308.23     13565099.48
#Sta/Elev= 30
  4576.6  190.24  4611.3  188.04  4616.4  188.47  4654.5  186.41  4669.7  186.54
  4695.2  185.23  4781.5  185.54  4840.0  183.08  4888.3  182.91  4917.6  181.69
  4979.7  177.18  5005.1  173.69  5020.4  169.37  5028.6  169.20  5028.8  168.70
  5032.6  169.20  5050.9  177.73  5058.5  174.93  5079.3  175.12  5199.7  175.07
  5222.0  175.70  5272.4  178.05  5289.1  180.89  5294.7  179.83  5311.5  181.64
  5317.1  181.27  5333.9  182.76  5339.4  182.11  5356.2  184.06  5361.4  183.58
#Mann=5,-1,0
  4576.6    0.04       0  4917.6    0.03       0  5028.6    0.03       0
  5032.6    0.03       0  5079.3    0.12       0
Bank Sta=5028.6,5032.6
Exp/Cntr=0.3,0.1

Type RM Length L Ch R = 1,6719,117,117,117
BEGIN DESCRIPTION:
Mapping XS 5eadcf94
END DESCRIPTION:
XS GIS Cut Line= 3
      2519724.68     13565444.64      2519967.71     13565422.94
      2520274.81     13565214.60
#Sta/Elev= 30
  4747.2  184.81  4787.7  182.64  4817.8  179.66  4858.0  177.87  4895.2  176.93
  4912.5  176.54  4938.3  174.27  4958.4  174.16  4991.2  173.02  4995.2  171.48
  4999.2  171.41  4999.5  170.91  5003.0  170.91  5003.2  171.41  5024.2  171.52
  5046.1  172.79  5082.0  173.90  5159.9  173.89  5203.7  174.81  5246.8  176.17
  5253.8  177.03  5267.8  176.90  5276.7  177.98  5282.7  177.72  5297.7  178.74
  5303.7  178.61  5326.3  180.01  5339.6  181.42  5348.5  183.40  5362.3  183.94
#Mann=5,-1,0
  4747.2    0.12       0  4895.2    0.03       0  4999.2    0.03       0
  5003.2    0.03       0  5203.7    0.12       0
Bank Sta=4999.2,5003.2
Exp/Cntr=0.3,0.1

Type RM Length L Ch R = 1,6602,94,94,94
BEGIN DESCRIPTION:
Mapping XS 4131f388
END DESCRIPTION:
XS GIS Cut Line= 4
      2519784.36     13565577.02      2519973.14     13565535.79
      2520206.43     13565476.11      2520237.67     13565288.63
#Sta/Elev= 30
  4805.0  182.23  4806.9  182.23  4856.8  181.31  4864.5  180.73  4883.6  179.04
  4888.7  179.76  4927.5  175.85  4932.6  176.59  4959.2  174.29  4976.5  171.64
  4981.6  171.92  4989.9  170.82  4994.6  170.80  4994.9  170.30  4998.4  170.30
  4998.6  170.80  5023.8  171.77  5031.1  172.75  5111.8  172.36  5146.2  173.02
  5206.6  173.05  5239.1  173.95  5270.6  175.45  5290.9  178.01  5341.5  180.30
  5372.0  180.55  5379.7  179.98  5384.8  180.80  5392.2  180.92  5429.1  180.40
#Mann=7,-1,0
  4805.0    0.12       0  4806.9   0.013       0  4864.5    0.12       0
  4994.6    0.05       0  4998.6    0.12       0  5111.8   0.013       0
  5239.1    0.12       0
Bank Sta=4994.6,4998.6
Exp/Cntr=0.3,0.1

Type RM Length L Ch R = 1,6508,259,259,259
BEGIN DESCRIPTION:
LGII4503
END DESCRIPTION:
XS GIS Cut Line= 3
      2519826.65     13565675.77      2520220.53     13565553.15
      2520250.92     13565332.86
#Sta/Elev= 30
  4838.9  180.69  4849.1  180.54  4868.6  179.62  4879.1  179.87  4893.4  179.01
  4920.7  179.63  4973.3  174.95  4983.8  173.19  5002.7  167.99  5003.0  167.49
  5006.5  167.49  5006.7  167.99  5015.2  168.40  5036.2  172.30  5078.1  172.53
  5101.6  172.15  5126.3  170.48  5131.6  171.45  5140.9  171.46  5158.9  172.65
  5252.8  172.85  5269.8  172.97  5289.9  174.21  5310.1  173.72  5323.0  174.02
  5328.6  174.59  5370.7  176.77  5431.3  181.33  5461.6  181.02  5473.8  181.89
#Mann=7,-1,0
  4838.9    0.12       0  4849.1   0.013       0  5002.7    0.03       0
  5006.7   0.013       0  5101.6    0.12       0  5252.8   0.013       0
  5328.6    0.12       0
Bank Sta=5002.7,5006.7
Exp/Cntr=0.3,0.1

Type RM Length L Ch R = 1,6249,186,186,186
BEGIN DESCRIPTION:
LGII4502
END DESCRIPTION:
XS GIS Cut Line= 4
      2519961.31     13565846.82      2520154.83     13565796.65
      2520250.70     13565690.13      2520413.43     13565369.60
#Sta/Elev= 30
  4734.2  180.07  4782.0  180.30  4819.6  180.03  4851.6  178.93  4879.2  176.20
  4884.4  174.97  4913.6  172.29  4919.8  171.07  4956.7  170.73  4963.4  169.80
  4977.6  169.08  4985.1  167.90  5004.0  166.76  5004.2  166.26  5007.7  166.26
  5008.0  166.76  5013.5  168.61  5027.7  171.45  5093.4  172.01  5099.0  171.62
  5143.5  171.80  5232.5  173.12  5249.3  173.77  5285.0  174.14  5316.0  176.21
  5343.8  177.25  5360.5  179.05  5374.8  179.92  5421.7  181.78  5436.9  182.10
#Mann=7,-1,0
  4734.2    0.12       0  4782.0   0.013       0  4819.6    0.12       0
  5004.0    0.05       0  5008.0    0.12       0  5249.3   0.013       0
  5421.7    0.12       0
Bank Sta=5004,5008
Exp/Cntr=0.3,0.1

Type RM Length L Ch R = 1,6063,324,324,324
BEGIN DESCRIPTION:
Mapping XS a0c08fcc
END DESCRIPTION:
XS GIS Cut Line= 5
      2519958.36     13565877.58      2520067.69     13565913.09
      2520270.90     13565899.29      2520341.99     13565908.47
      2520815.09     13566037.56
#Sta/Elev= 30
  4749.2  179.21  4785.9  179.00  4791.2  178.40  4823.2  178.83  4860.1  180.40
  4913.1  180.24  4951.7  176.15  4961.7  172.18  4971.7  166.38  4979.7  165.34
  4980.0  164.84  4983.7  165.34  5001.8  168.28  5031.8  168.40  5051.9  170.25
  5092.1  170.89  5112.3  169.05  5122.4  165.67  5132.5  166.62  5138.5  168.97
  5142.4  168.97  5146.6  167.78  5173.7  171.09  5267.0  179.10  5372.3  186.41
  5468.7  193.86  5495.1  195.65  5505.4  195.51  5597.8  200.26  5629.9  200.90
#Mann=6,-1,0
  4749.2    0.12       0  4979.7    0.05       0  4983.7    0.12       0
  5372.3    0.05       0  5468.7    0.12       0  5597.8    0.03       0
Bank Sta=4979.7,4983.7
Exp/Cntr=0.3,0.1

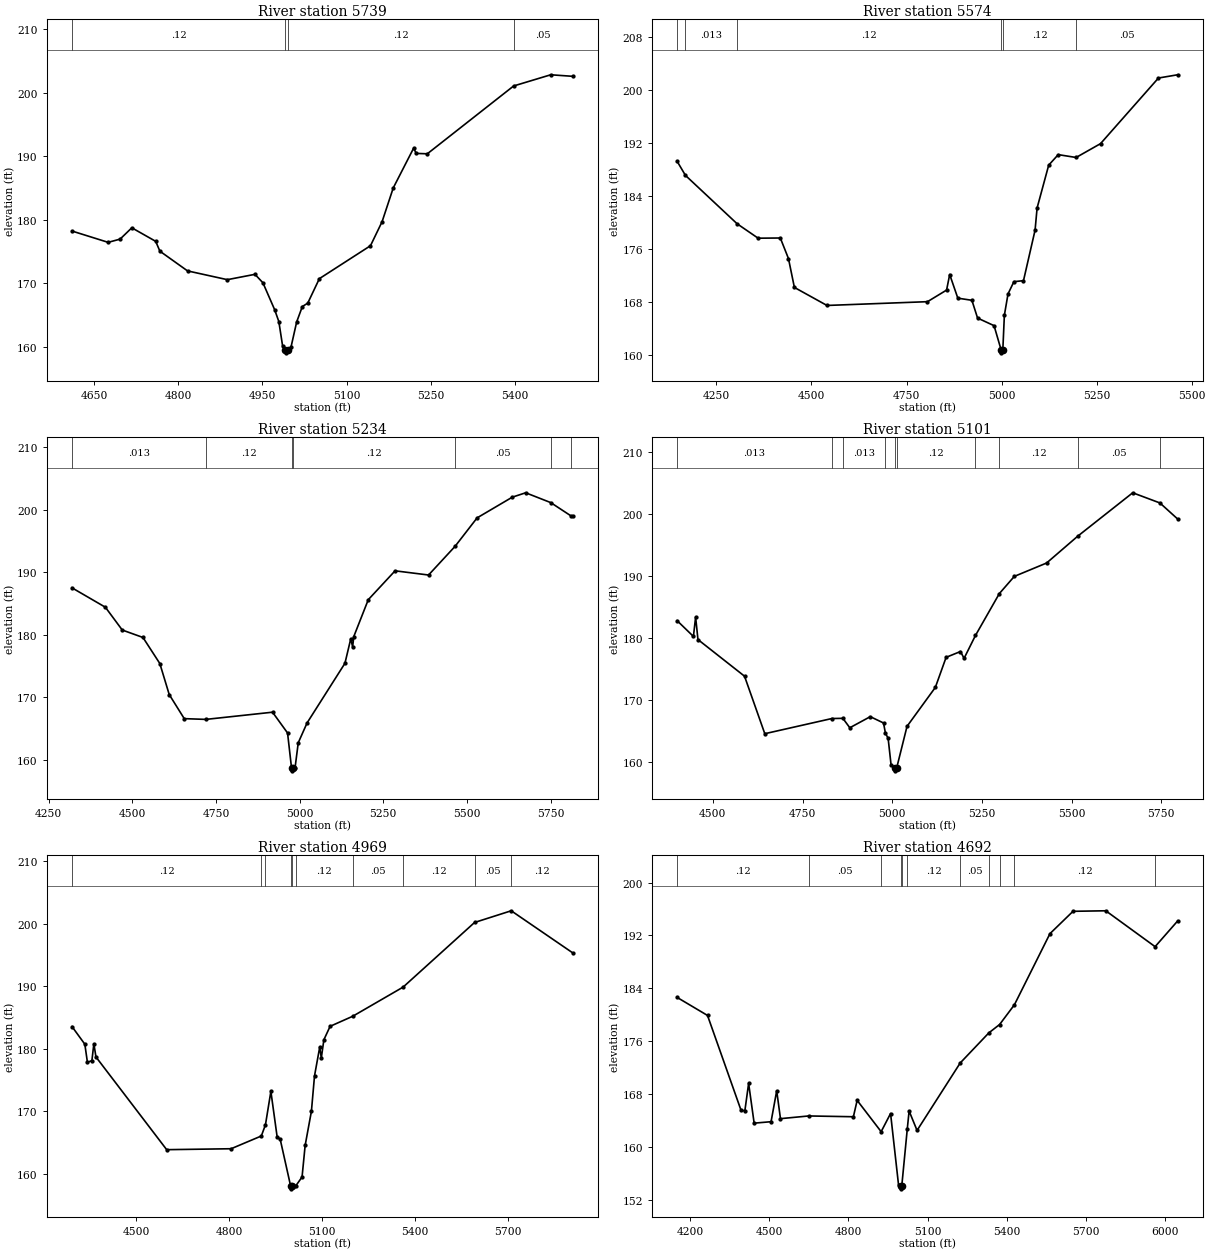
Type RM Length L Ch R = 1,5739,165,165,165
BEGIN DESCRIPTION:
Mapping XS c55c9159
END DESCRIPTION:
XS GIS Cut Line= 3
      2519951.86     13565897.09      2520210.13     13566183.58
      2520710.68     13566265.92
#Sta/Elev= 30
  4610.2  178.25  4674.7  176.47  4696.0  176.98  4716.9  178.76  4759.5  176.63
  4767.0  175.08  4816.3  171.98  4887.3  170.60  4936.6  171.44  4950.8  170.11
  4971.7  165.88  4979.2  164.01  4985.9  160.18  4991.0  159.59  4991.4  159.09
  4995.8  159.59  5000.9  159.99  5011.0  163.95  5021.1  166.37  5030.8  166.91
  5051.5  170.76  5142.7  175.94  5163.4  179.72  5183.3  185.03  5219.5  191.26
  5224.6  190.46  5244.1  190.40  5398.1  201.07  5464.3  202.83  5503.2  202.59
#Mann=4,-1,0
  4610.2    0.12       0  4991.0    0.05       0  4995.8    0.12       0
  5398.1    0.05       0
Bank Sta=4991,4995.8
Exp/Cntr=0.3,0.1

Type RM Length L Ch R = 1,5574,340,340,340
BEGIN DESCRIPTION:
Mapping XS b7b01be7
END DESCRIPTION:
XS GIS Cut Line= 3
      2519396.61     13565880.94      2520130.11     13566319.31
      2520563.83     13566478.70
#Sta/Elev= 30
  4146.6  189.31  4168.5  187.18  4304.6  179.87  4359.7  177.70  4418.1  177.73
  4439.5  174.63  4455.1  170.27  4540.8  167.55  4805.2  168.12  4855.4  169.87
  4863.6  172.22  4885.0  168.65  4922.0  168.33  4936.9  165.65  4980.3  164.50
  4998.6  160.90  4999.0  160.40  5003.4  160.90  5007.4  166.06  5017.0  169.29
  5032.5  171.14  5057.7  171.29  5088.2  178.92  5093.5  182.26  5124.0  188.72
  5149.1  190.31  5196.1  189.88  5260.4  191.97  5412.7  201.87  5463.2  202.36
#Mann=6,-1,0
  4146.6    0.04       0  4168.5   0.013       0  4304.6    0.12       0
  4998.6    0.05       0  5003.4    0.12       0  5196.1    0.05       0
Bank Sta=4998.6,5003.4
Exp/Cntr=0.3,0.1

Type RM Length L Ch R = 1,5234,133,133,133
BEGIN DESCRIPTION:
Mapping XS 8717c73f
END DESCRIPTION:
XS GIS Cut Line= 4
      2519214.35     13566124.01      2519821.95     13566423.47
      2519973.86     13566492.92      2520624.93     13566523.30
#Sta/Elev= 30
  4319.7  187.50  4419.5  184.40  4469.9  180.76  4531.8  179.57  4582.2  175.41
  4610.3  170.45  4655.2  166.60  4719.8  166.48  4919.1  167.63  4964.0  164.31
  4975.8  158.76  4976.1  158.26  4980.6  158.76  4986.5  158.78  4996.0  162.75
  5022.4  165.92  5135.5  175.44  5153.0  179.37  5158.5  178.07  5162.0  179.72
  5205.3  185.61  5285.4  190.22  5385.5  189.55  5464.7  194.13  5530.6  198.68
  5635.8  201.99  5675.8  202.69  5750.7  201.12  5811.1  199.00  5815.9  198.99
#Mann=7,-1,0
  4319.7   0.013       0  4719.8    0.12       0  4975.8    0.05       0
  4980.6    0.12       0  5464.7    0.05       0  5750.7    0.12       0
  5811.1    0.05       0
Bank Sta=4975.8,4980.6
Exp/Cntr=0.3,0.1

Type RM Length L Ch R = 1,5101,132,132,132
BEGIN DESCRIPTION:
Mapping XS cc9000f2
END DESCRIPTION:
XS GIS Cut Line= 3
      2519287.81     13566190.08      2519773.94     13566539.48
      2520570.19     13566550.33
#Sta/Elev= 30
  4400.4  182.81  4445.9  180.26  4452.0  183.39  4458.5  179.76  4588.3  173.85
  4644.8  164.57  4831.8  167.02  4862.4  167.05  4881.7  165.53  4938.8  167.32
  4975.7  166.30  4981.1  164.63  4988.5  163.84  4996.6  159.60  5007.7  159.08
  5008.1  158.58  5012.5  159.08  5041.2  165.76  5120.1  172.04  5150.1  176.89
  5190.1  177.83  5200.2  176.73  5231.9  180.42  5298.5  187.18  5340.2  189.95
  5430.2  192.11  5517.2  196.45  5670.2  203.44  5745.9  201.80  5795.4  199.21
#Mann=10,-1,0
  4400.4   0.013       0  4831.8    0.12       0  4862.4   0.013       0
  4981.1    0.12       0  5007.7    0.05       0  5012.5    0.12       0
  5231.9    0.05       0  5298.5    0.12       0  5517.2    0.05       0
  5745.9    0.12       0
Bank Sta=5007.7,5012.5
Exp/Cntr=0.3,0.1

Type RM Length L Ch R = 1,4969,277,277,277
BEGIN DESCRIPTION:
Mapping XS e239ff81
END DESCRIPTION:
XS GIS Cut Line= 4
      2519257.70     13566193.43      2519600.60     13566644.83
      2519921.78     13566679.55      2520640.09     13566580.02
#Sta/Elev= 30
  4292.4  183.57  4333.8  180.75  4342.1  177.87  4356.6  178.12  4362.9  180.82
  4369.7  178.71  4597.9  163.89  4805.8  164.04  4903.3  166.08  4916.6  167.87
  4934.1  173.21  4954.2  165.97  4964.3  165.53  4997.6  158.13  4997.9  157.63
  5002.4  158.13  5015.2  158.16  5034.7  159.52  5044.7  164.58  5064.9  170.04
  5074.9  175.69  5091.7  180.28  5096.8  178.54  5105.1  181.46  5125.2  183.61
  5198.3  185.22  5360.8  189.88  5591.3  200.21  5709.6  202.08  5907.5  195.37
#Mann=10,-1,0
  4292.4    0.12       0  4903.3    0.05       0  4916.6   0.013       0
  4997.6    0.03       0  5002.4   0.013       0  5015.2    0.12       0
  5198.3    0.05       0  5360.8    0.12       0  5591.3    0.05       0
  5709.6    0.12       0
Bank Sta=4997.6,5002.4
Exp/Cntr=0.3,0.1

Type RM Length L Ch R = 1,4692,201,201,201
BEGIN DESCRIPTION:
Mapping XS 06ba81c0
END DESCRIPTION:
XS GIS Cut Line= 4
      2519140.94     13566356.94      2519648.75     13566938.54
      2519904.82     13566916.84      2520721.49     13566626.56
#Sta/Elev= 30
  4151.4  182.63  4266.6  179.90  4393.8  165.52  4408.1  165.49  4422.3  169.62
  4443.2  163.60  4507.3  163.82  4528.6  168.50  4542.9  164.28  4649.9  164.69
  4819.1  164.57  4833.3  167.05  4924.2  162.31  4959.9  165.06  4990.0  154.28
  4997.6  154.16  4998.0  153.66  5002.5  154.16  5023.2  162.73  5030.1  165.44
  5060.2  162.50  5223.7  172.71  5332.3  177.27  5372.9  178.53  5429.0  181.52
  5563.6  192.28  5650.9  195.66  5775.0  195.74  5961.8  190.31  6047.2  194.20
#Mann=11,-1,0
  4151.4    0.12       0  4649.9    0.05       0  4924.2   0.013       0
  4997.6    0.03       0  5002.5   0.013       0  5023.2    0.12       0
  5223.7    0.05       0  5332.3    0.12       0  5372.9    0.05       0
  5429.0    0.12       0  5961.8   0.013       0
Bank Sta=4997.6,5002.5
Exp/Cntr=0.3,0.1

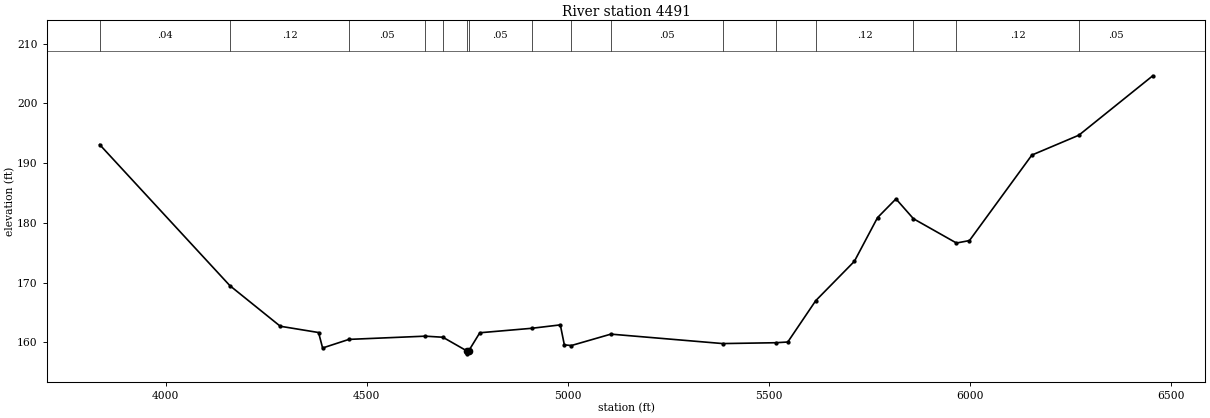
Type RM Length L Ch R = 1,4491,0,0,0
BEGIN DESCRIPTION:
Mapping XS 607e0131
END DESCRIPTION:
XS GIS Cut Line= 4
      2518571.93     13567058.96      2519548.51     13567126.60
      2519999.90     13567139.62      2521078.90     13566642.29
#Sta/Elev= 30
  3835.7  193.12  4159.7  169.48  4284.9  162.69  4380.1  161.64  4390.1  159.05
  4455.6  160.49  4645.1  161.03  4689.2  160.85  4748.5  158.57  4748.9  158.07
  4753.4  158.57  4781.0  161.60  4910.3  162.35  4981.2  162.92  4991.2  159.57
  5008.6  159.46  5106.9  161.37  5385.0  159.79  5516.4  159.93  5546.8  160.05
  5616.2  166.97  5712.3  173.56  5769.9  180.88  5815.8  184.02  5859.2  180.70
  5966.2  176.63  5998.5  177.04  6153.7  191.36  6270.6  194.69  6454.3  204.64
#Mann=16,-1,0
  3835.7    0.04       0  4159.7    0.12       0  4455.6    0.05       0
  4645.1    0.12       0  4689.2    0.05       0  4748.5    0.03       0
  4753.4    0.05       0  4910.3   0.013       0  5008.6     0.1       0
  5106.9    0.05       0  5385.0    0.12       0  5516.4    0.05       0
  5616.2    0.12       0  5859.2   0.013       0  5966.2    0.12       0
  6270.6    0.05       0
Bank Sta=4748.5,4753.4
Exp/Cntr=0.3,0.1

Chan Stop Cuts=-1