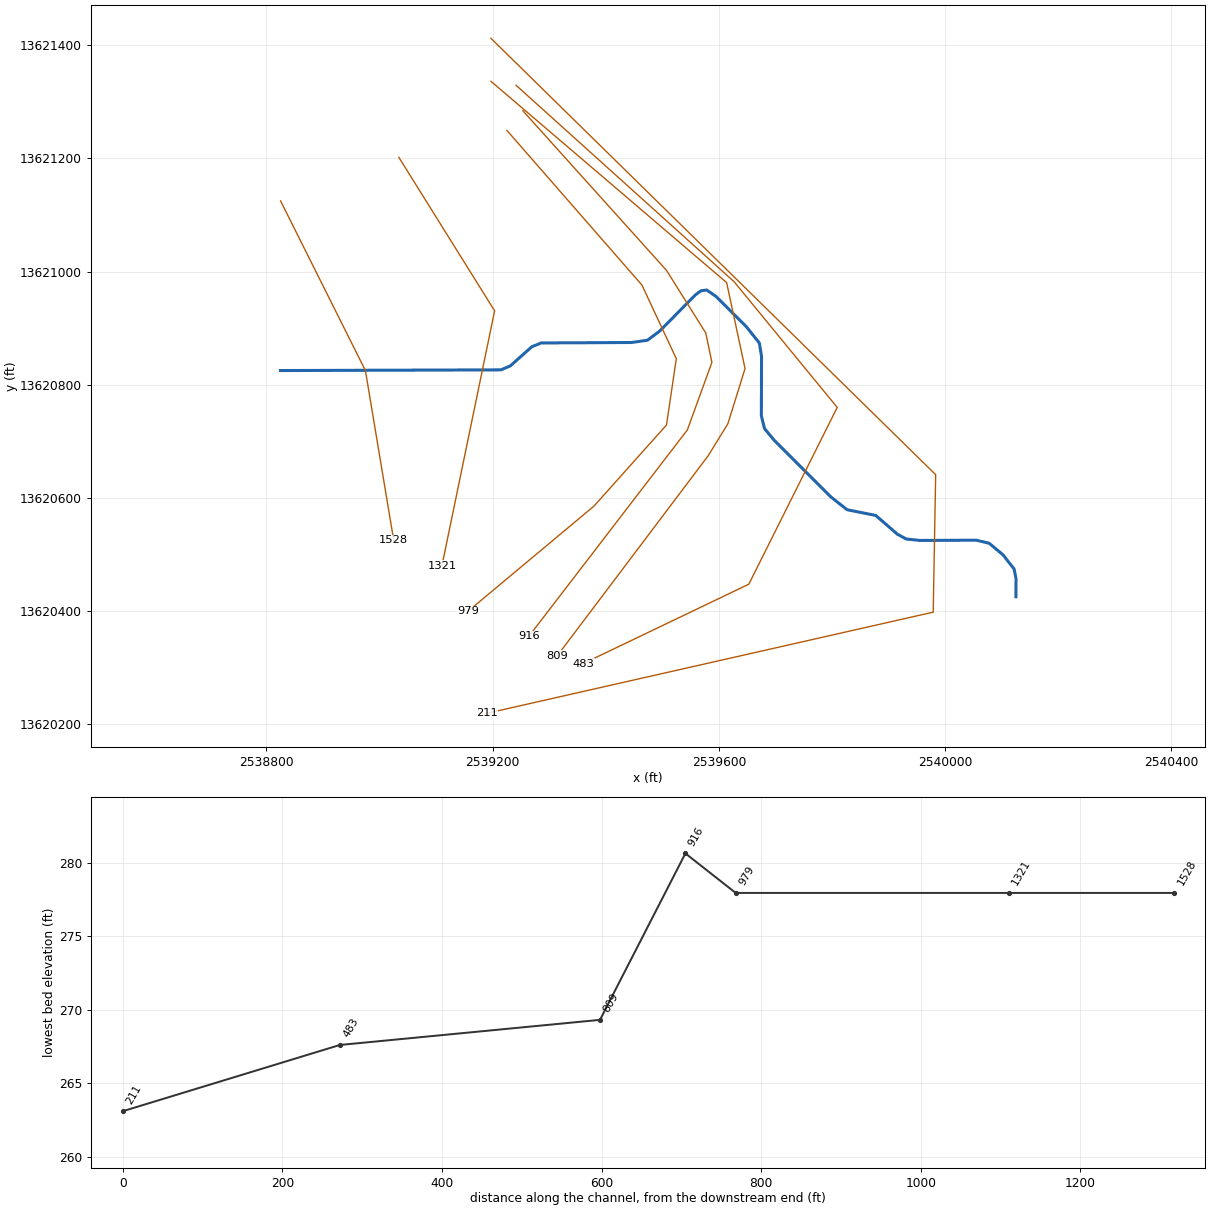
--- TRIB 18 TO IRISH CREEK.prj (project) ---

Proj Title=TRIB 18 TO IRISH CREEK Base Level Engineering
Current Plan=p01
Default Exp/Contr=0.3,0.1
English Units
Geom File=g01
Flow File=f01
Plan File=p01
BEGIN DESCRIPTION:
TRIB 18 TO IRISH CREEK
END DESCRIPTION:

--- TRIB 18 TO IRISH CREEK.p01 (plan) ---

Plan Title=Multiple Run
Short Identifier=Multiple
Geom File=g01
Flow File=f01
Subcritical Flow
K Sum by GR= 0
Std Step Tol= 0.01
Critical Tol= 0.01
Num of Std Step Trials= 20
Max Error Tol= 0.3
Flow Tol Ratio= 0.001
Split Flow NTrial= 30
Split Flow Tol= 0.02
Split Flow Ratio= 0.02
Log Output Level= 0
Friction Slope Method= 1
Unsteady Friction Slope Method= 2
Unsteady Bridges Friction Slope Method= 1
Parabolic Critical Depth
Global Vel Dist=  1 , 1 , 1
Global Log Level= 0
CheckData=True
Encroach Param= -1, 0, 0, 0
BEGIN DESCRIPTION:
Multiple Run
END DESCRIPTION:

--- TRIB 18 TO IRISH CREEK.f01 (steady flow) ---

Flow Title=Multiple
Number of Profiles=7
Profile Names=10-year,25-year,50-year,1pct_min,100-year,1pct_plu,500-year
River Rch & RM= TRIB 18 TO IRISH,Reach-1,1528
     170     249     314     193     386     770     573
Boundary for River Rch & Prof#=TRIB 18 TO IRISH,Reach-1,1
Up Type=0
Dn Type=3
Dn Slope=0.005
Boundary for River Rch & Prof#=TRIB 18 TO IRISH,Reach-1,2
Up Type=0
Dn Type=3
Dn Slope=0.005
Boundary for River Rch & Prof#=TRIB 18 TO IRISH,Reach-1,3
Up Type=0
Dn Type=3
Dn Slope=0.005
Boundary for River Rch & Prof#=TRIB 18 TO IRISH,Reach-1,4
Up Type=0
Dn Type=3
Dn Slope=0.005
Boundary for River Rch & Prof#=TRIB 18 TO IRISH,Reach-1,5
Up Type=0
Dn Type=3
Dn Slope=0.005
Boundary for River Rch & Prof#=TRIB 18 TO IRISH,Reach-1,6
Up Type=0
Dn Type=3
Dn Slope=0.005
Boundary for River Rch & Prof#=TRIB 18 TO IRISH,Reach-1,7
Up Type=0
Dn Type=3
Dn Slope=0.005

--- TRIB 18 TO IRISH CREEK.g01 (geometry) ---

Geom Title=Existing Conditions

River Reach=TRIB 18 TO IRISH,Reach-1
Reach XY= 30
      2538825.00     13620825.00      2539214.50     13620826.22
      2539231.06     13620833.14      2539268.94     13620866.86
      2539285.51     13620873.78      2539445.18     13620874.58
      2539473.54     13620878.56      2539495.16     13620894.69
      2539558.35     13620958.77      2539568.35     13620966.03
      2539578.35     13620967.41      2539595.05     13620955.81
      2539648.83     13620902.01      2539671.46     13620873.56
      2539675.27     13620850.12      2539674.98     13620744.99
      2539680.47     13620722.55      2539697.86     13620701.47
      2539798.18     13620601.29      2539826.63     13620578.94
      2539877.17     13620568.86      2539915.33     13620535.80
      2539930.93     13620527.25      2539954.86     13620524.67
      2540055.09     13620525.07      2540077.69     13620519.73
      2540102.24     13620499.15      2540121.88     13620474.02
      2540125.16     13620457.08      2540125.00     13620425.00

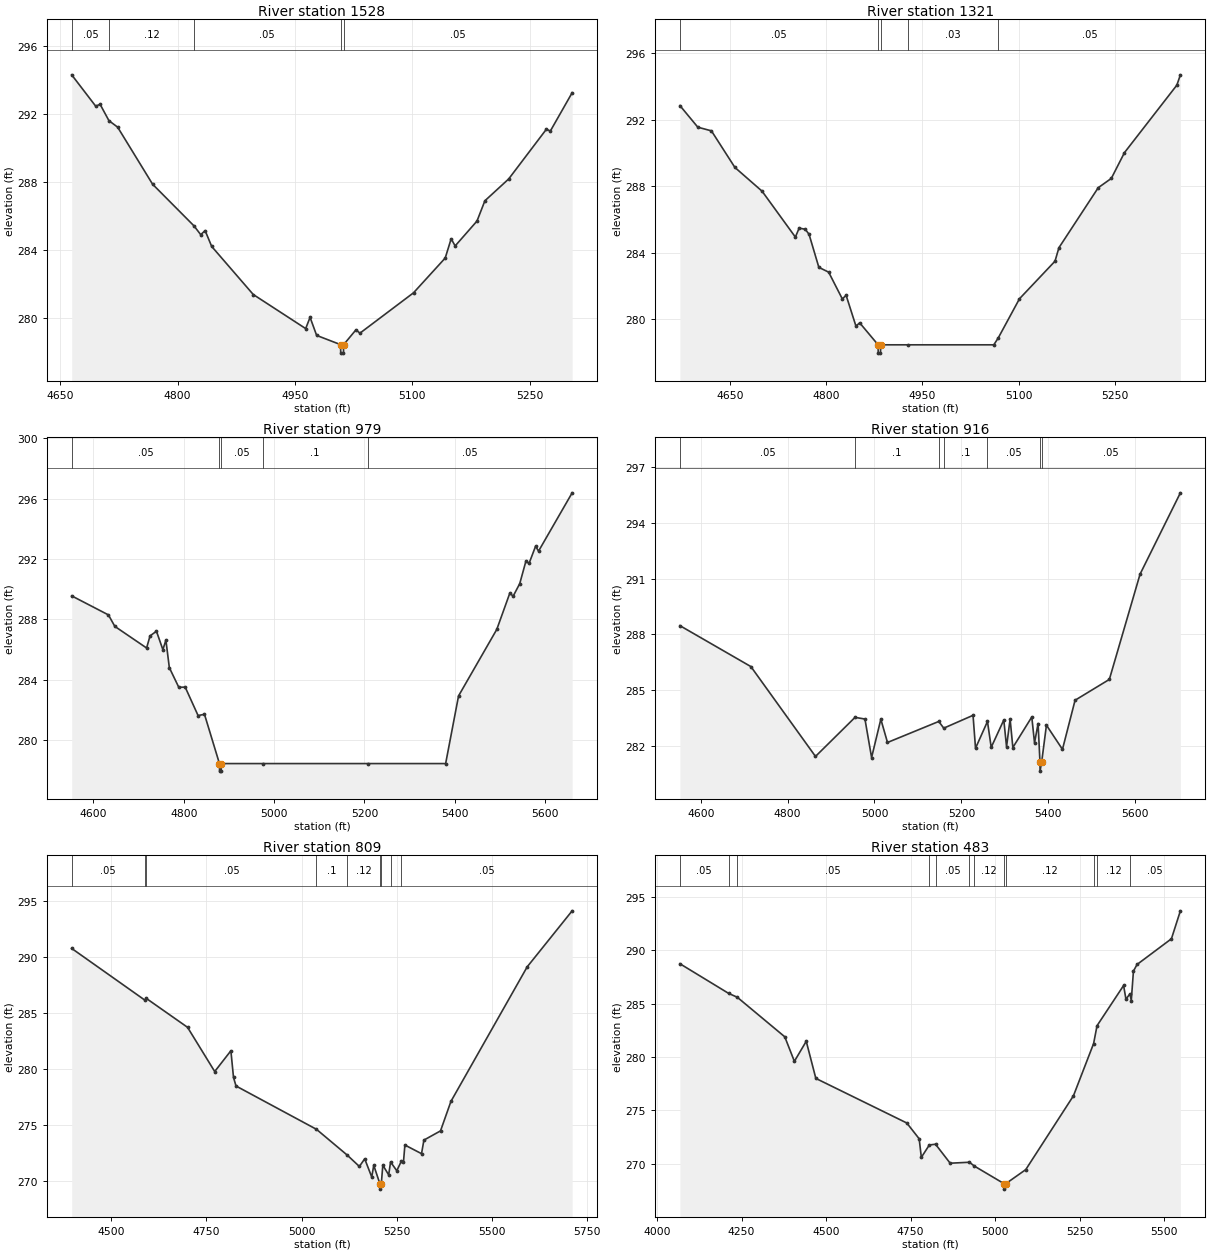
Type RM Length L Ch R = 1,1528,207,207,207
BEGIN DESCRIPTION:
TRIB 18 TO IRISH CREEK 2.0
END DESCRIPTION:
XS GIS Cut Line= 3
      2538825.01     13621124.98      2538975.00     13620825.00
      2539025.00     13620525.02
#Sta/Elev= 30
  4664.6  294.29  4695.3  292.45  4700.9  292.56  4712.2  291.60  4723.3  291.22
  4768.0  287.87  4820.8  285.43  4829.5  284.91  4835.1  285.15  4843.5  284.22
  4896.6  281.40  4963.6  279.40  4969.2  280.06  4977.6  279.00  5008.1  278.46
  5008.4  277.96  5011.9  277.96  5012.1  278.46  5027.9  279.33  5032.9  279.13
  5101.4  281.50  5141.9  283.54  5149.5  284.67  5154.6  284.25  5182.5  285.71
  5192.6  286.90  5223.0  288.18  5271.2  291.10  5276.2  290.99  5304.1  293.24
#Mann=5,-1,0
  4664.6    0.05       0  4712.2    0.12       0  4820.8    0.05       0
  5008.1    0.05       0  5012.1    0.05       0
Bank Sta=5008.1,5012.1
Exp/Cntr=0.3,0.1

Type RM Length L Ch R = 1,1321,342,342,342
BEGIN DESCRIPTION:
Mapping XS 0d0c7851
END DESCRIPTION:
XS GIS Cut Line= 3
      2539034.14     13621201.85      2539203.43     13620930.55
      2539110.20     13620479.57
#Sta/Elev= 30
  4572.0  292.85  4599.9  291.55  4621.1  291.33  4657.7  289.13  4700.1  287.70
  4752.0  284.94  4757.9  285.48  4767.4  285.41  4773.3  285.11  4788.6  283.12
  4803.9  282.83  4825.2  281.22  4831.1  281.44  4846.4  279.59  4852.3  279.78
  4881.0  278.46  4881.2  277.96  4884.7  277.96  4885.0  278.46  4927.9  278.46
  5061.4  278.46  5068.4  278.88  5101.4  281.23  5156.8  283.49  5162.9  284.30
  5224.2  287.91  5244.6  288.47  5265.1  290.02  5346.8  294.08  5352.3  294.70
#Mann=5,-1,0
  4572.0    0.05       0  4881.0    0.03       0  4885.0    0.05       0
  4927.9    0.03       0  5068.4    0.05       0
Bank Sta=4881,4885
Exp/Cntr=0.3,0.1

Type RM Length L Ch R = 1,979,63,63,63
BEGIN DESCRIPTION:
Mapping XS 966ff93b
END DESCRIPTION:
XS GIS Cut Line= 6
      2539225.11     13621249.59      2539463.84     13620976.12
      2539524.61     13620845.92      2539507.25     13620728.73
      2539379.21     13620585.50      2539156.36     13620399.43
#Sta/Elev= 30
  4552.1  289.56  4633.4  288.30  4647.6  287.54  4717.9  286.11  4725.5  286.91
  4739.7  287.22  4753.9  286.00  4760.6  286.63  4768.2  284.81  4789.1  283.51
  4803.3  283.52  4831.8  281.64  4846.0  281.72  4879.1  278.46  4879.4  277.96
  4882.9  277.96  4883.1  278.46  4974.6  278.46  5207.3  278.46  5379.7  278.46
  5408.3  282.94  5492.9  287.34  5521.5  289.72  5529.3  289.55  5543.7  290.37
  5557.2  291.84  5564.5  291.72  5578.8  292.85  5585.3  292.52  5659.7  296.38
#Mann=5,-1,0
  4552.1    0.05       0  4879.1    0.05       0  4883.1    0.05       0
  4974.6     0.1       0  5207.3    0.05       0
Bank Sta=4879.1,4883.1
Exp/Cntr=0.3,0.1

Type RM Length L Ch R = 1,916,107,107,107
BEGIN DESCRIPTION:
Mapping XS 965b2f72
END DESCRIPTION:
XS GIS Cut Line= 6
      2539253.35     13621284.27      2539507.25     13621002.17
      2539576.69     13620891.49      2539587.54     13620839.41
      2539544.14     13620720.05      2539264.18     13620355.46
#Sta/Elev= 30
  4552.2  288.47  4715.5  286.27  4864.2  281.44  4955.2  283.54  4978.0  283.45
  4993.3  281.38  5014.6  283.44  5029.9  282.19  5147.9  283.32  5159.4  282.96
  5226.8  283.65  5232.5  281.88  5260.0  283.32  5268.6  281.93  5297.6  283.40
  5303.9  281.96  5312.1  283.45  5318.4  281.92  5362.0  283.56  5368.3  282.17
  5376.5  283.21  5380.8  281.15  5381.0  280.65  5384.8  281.15  5395.7  283.12
  5432.6  281.82  5461.6  284.46  5540.5  285.58  5611.2  291.24  5704.0  295.61
#Mann=7,-1,0
  4552.2    0.05       0  4955.2     0.1       0  5147.9    0.12       0
  5159.4     0.1       0  5260.0    0.05       0  5380.8    0.05       0
  5384.8    0.05       0
Bank Sta=5380.8,5384.8
Exp/Cntr=0.3,0.1

Type RM Length L Ch R = 1,809,326,326,326
BEGIN DESCRIPTION:
Mapping XS d5b68921
END DESCRIPTION:
XS GIS Cut Line= 6
      2539196.93     13621336.35      2539613.58     13620980.47
      2539646.14     13620828.56      2539615.75     13620730.90
      2539581.03     13620674.48      2539314.09     13620320.73
#Sta/Elev= 30
  4395.8  290.77  4588.1  286.16  4591.7  286.32  4700.2  283.74  4771.6  279.80
  4814.1  281.65  4821.0  279.27  4827.6  278.51  5039.0  274.65  5119.5  272.36
  5151.7  271.34  5165.7  272.02  5184.2  270.40  5189.5  271.44  5205.4  269.82
  5205.7  269.32  5209.4  269.82  5213.3  271.45  5228.7  270.59  5233.7  271.74
  5250.0  270.96  5262.2  271.82  5267.6  271.74  5271.3  273.25  5315.0  272.48
  5321.3  273.69  5364.9  274.51  5392.3  277.14  5592.7  289.13  5710.8  294.12
#Mann=9,-1,0
  4395.8    0.05       0  4588.1    0.12       0  4591.7    0.05       0
  5039.0     0.1       0  5119.5    0.12       0  5205.4    0.05       0
  5209.4    0.12       0  5233.7     0.1       0  5262.2    0.05       0
Bank Sta=5205.4,5209.4
Exp/Cntr=0.3,0.1

Type RM Length L Ch R = 1,483,272,272,272
BEGIN DESCRIPTION:
Mapping XS ee464fd8
END DESCRIPTION:
XS GIS Cut Line= 5
      2539241.38     13621329.27      2539626.78     13620982.06
      2539809.08     13620759.83      2539652.83     13620447.33
      2539359.71     13620306.85
#Sta/Elev= 30
  4067.8  288.74  4211.9  285.96  4237.4  285.60  4378.0  281.89  4406.4  279.59
  4441.5  281.47  4469.9  277.99  4739.0  273.81  4775.6  272.33  4782.0  270.59
  4805.7  271.75  4823.9  271.82  4867.3  270.04  4924.4  270.13  4938.9  269.77
  5027.4  268.11  5027.6  267.61  5031.4  268.11  5090.9  269.44  5232.0  276.36
  5291.7  281.26  5301.8  282.93  5380.4  286.70  5387.3  285.42  5399.3  285.92
  5403.1  285.29  5409.5  288.05  5420.2  288.67  5521.9  291.08  5548.4  293.70
#Mann=12,-1,0
  4067.8    0.05       0  4211.9    0.12       0  4237.4    0.05       0
  4805.7    0.12       0  4823.9    0.05       0  4924.4     0.1       0
  4938.9    0.12       0  5027.4    0.05       0  5031.4    0.12       0
  5291.7    0.05       0  5301.8    0.12       0  5399.3    0.05       0
Bank Sta=5027.4,5031.4
Exp/Cntr=0.3,0.1

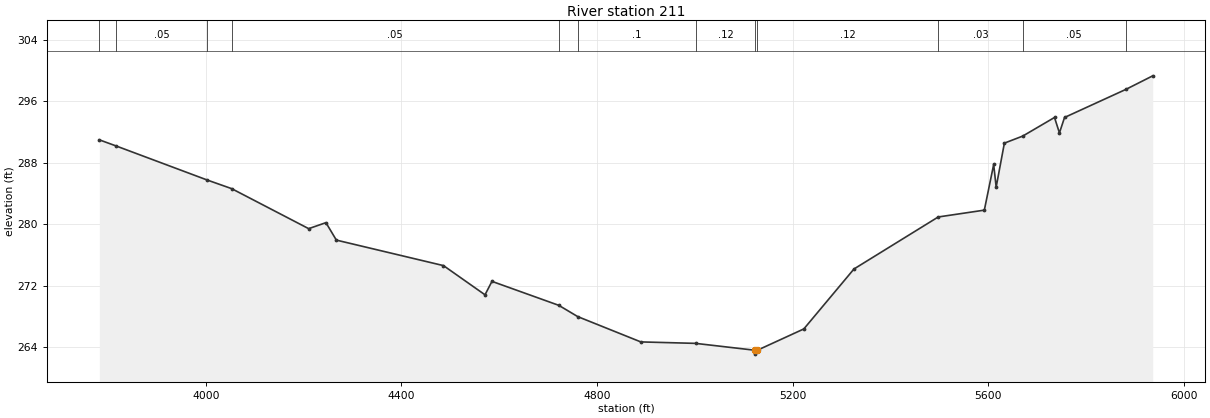
Type RM Length L Ch R = 1,211,0,0,0
BEGIN DESCRIPTION:
Mapping XS f6cc2db3
END DESCRIPTION:
XS GIS Cut Line= 4
      2539196.94     13621412.30      2539983.12     13620640.91
      2539978.78     13620397.86      2539189.11     13620218.94
#Sta/Elev= 30
  3782.4  290.99  3816.4  290.20  4003.4  285.75  4052.9  284.64  4210.5  279.43
  4245.8  280.21  4267.1  277.94  4486.2  274.62  4571.1  270.82  4585.3  272.57
  4722.0  269.45  4760.8  267.98  4889.7  264.69  5001.6  264.50  5123.8  263.60
  5124.1  263.10  5127.8  263.60  5223.1  266.38  5325.6  274.18  5497.9  280.95
  5592.2  281.84  5611.3  287.78  5616.4  284.84  5633.2  290.56  5670.8  291.48
  5735.7  293.90  5745.8  291.89  5756.2  293.90  5881.5  297.55  5936.6  299.32
#Mann=12,-1,0
  3782.4    0.12       0  3816.4    0.05       0  4003.4    0.12       0
  4052.9    0.05       0  4722.0    0.12       0  4760.8     0.1       0
  5001.6    0.12       0  5123.8    0.05       0  5127.8    0.12       0
  5497.9    0.03       0  5670.8    0.05       0  5881.5    0.03       0
Bank Sta=5123.8,5127.8
Exp/Cntr=0.3,0.1

Chan Stop Cuts=-1