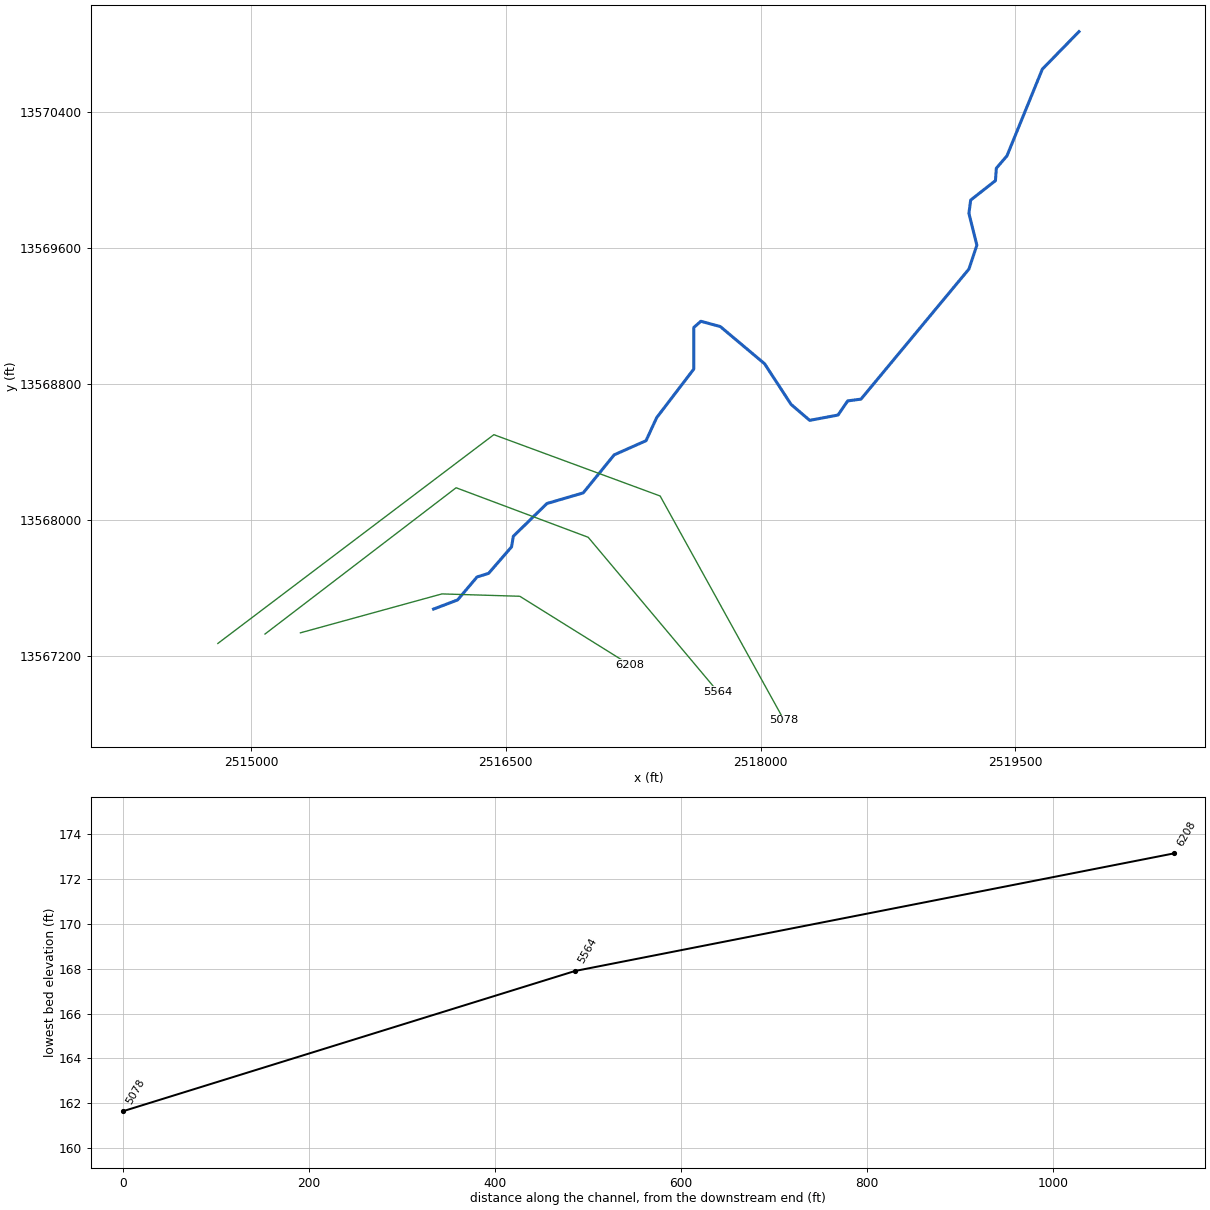
--- TRIB 19 TO GUADALUPE RIVER.prj (project) ---

Proj Title=TRIB 19 TO GUADALUPE RIVER Base Level Engineering
Current Plan=p01
Default Exp/Contr=0.3,0.1
English Units
Geom File=g01
Flow File=f01
Plan File=p01
BEGIN DESCRIPTION:
TRIB 19 TO GUADALUPE RIVER
END DESCRIPTION:

--- TRIB 19 TO GUADALUPE RIVER.p01 (plan) ---

Plan Title=Multiple Run
Short Identifier=Multiple
Geom File=g01
Flow File=f01
Subcritical Flow
K Sum by GR= 0
Std Step Tol= 0.01
Critical Tol= 0.01
Num of Std Step Trials= 20
Max Error Tol= 0.3
Flow Tol Ratio= 0.001
Split Flow NTrial= 30
Split Flow Tol= 0.02
Split Flow Ratio= 0.02
Log Output Level= 0
Friction Slope Method= 1
Unsteady Friction Slope Method= 2
Unsteady Bridges Friction Slope Method= 1
Parabolic Critical Depth
Global Vel Dist=  1 , 1 , 1
Global Log Level= 0
CheckData=True
Encroach Param= -1, 0, 0, 0
BEGIN DESCRIPTION:
Multiple Run
END DESCRIPTION:

--- TRIB 19 TO GUADALUPE RIVER.f01 (steady flow) ---

Flow Title=Multiple
Number of Profiles=7
Profile Names=10-year,25-year,50-year,1pct_min,100-year,1pct_plu,500-year
River Rch & RM= TRIB 19 TO GUADA,Reach-1,6208
     407     639     844     541    1080    2154    1746
Boundary for River Rch & Prof#=TRIB 19 TO GUADA,Reach-1,1
Up Type=0
Dn Type=3
Dn Slope=0.005
Boundary for River Rch & Prof#=TRIB 19 TO GUADA,Reach-1,2
Up Type=0
Dn Type=3
Dn Slope=0.005
Boundary for River Rch & Prof#=TRIB 19 TO GUADA,Reach-1,3
Up Type=0
Dn Type=3
Dn Slope=0.005
Boundary for River Rch & Prof#=TRIB 19 TO GUADA,Reach-1,4
Up Type=0
Dn Type=3
Dn Slope=0.005
Boundary for River Rch & Prof#=TRIB 19 TO GUADA,Reach-1,5
Up Type=0
Dn Type=3
Dn Slope=0.005
Boundary for River Rch & Prof#=TRIB 19 TO GUADA,Reach-1,6
Up Type=0
Dn Type=3
Dn Slope=0.005
Boundary for River Rch & Prof#=TRIB 19 TO GUADA,Reach-1,7
Up Type=0
Dn Type=3
Dn Slope=0.005

--- TRIB 19 TO GUADALUPE RIVER.g01 (geometry) ---

Geom Title=Existing Conditions

River Reach=TRIB 19 TO GUADA,Reach-1
Reach XY= 30
      2516075.00     13567475.00      2516216.50     13567528.83
      2516331.09     13567664.24      2516398.79     13567685.08
      2516534.21     13567841.33      2516544.63     13567903.83
      2516742.54     13568096.53      2516956.09     13568159.03
      2517138.38     13568382.99      2517325.88     13568466.33
      2517388.38     13568601.74      2517607.13     13568888.20
      2517607.13     13569132.99      2517648.79     13569169.45
      2517763.38     13569138.20      2518023.79     13568919.45
      2518180.04     13568679.87      2518289.42     13568586.12
      2518456.09     13568617.37      2518513.38     13568700.70
      2518591.50     13568711.12      2519226.92     13569476.74
      2519273.79     13569617.37      2519226.92     13569804.87
      2519237.34     13569882.99      2519383.17     13569997.58
      2519388.38     13570070.49      2519450.88     13570143.41
      2519659.21     13570653.83      2519875.00     13570875.00

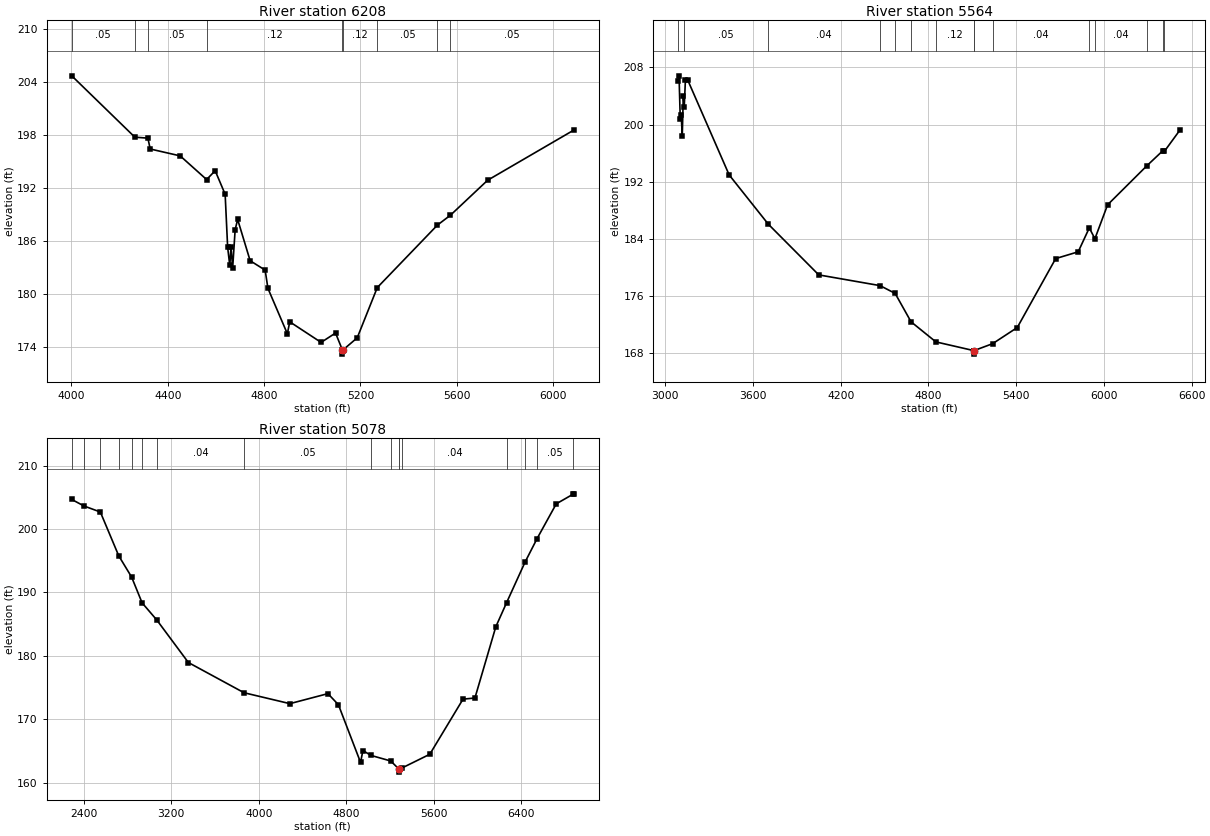
Type RM Length L Ch R = 1,6208,644,644,644
BEGIN DESCRIPTION:
Mapping XS f5cf14fd
END DESCRIPTION:
XS GIS Cut Line= 4
      2515291.05     13567335.15      2516124.35     13567564.30
      2516582.68     13567550.41      2517228.50     13567147.64
#Sta/Elev= 30
  4001.8  204.68  4263.6  197.73  4317.8  197.62  4327.4  196.39  4451.9  195.61
  4561.5  192.93  4597.1  193.93  4638.5  191.26  4648.9  185.24  4657.7  183.20
  4662.9  185.29  4669.7  182.92  4680.0  187.24  4690.4  188.41  4742.3  183.73
  4804.5  182.67  4816.1  180.60  4896.7  175.46  4906.7  176.81  5036.8  174.48
  5096.8  175.54  5124.8  173.65  5125.1  173.15  5128.8  173.65  5186.8  175.00
  5270.0  180.69  5519.7  187.77  5573.8  188.89  5728.1  192.85  6085.7  198.53
#Mann=9,-1,0
  4001.8    0.05       0  4263.6    0.04       0  4317.8    0.05       0
  4561.5    0.12       0  5124.8    0.05       0  5128.8    0.12       0
  5270.0    0.05       0  5519.7    0.04       0  5573.8    0.05       0
Bank Sta=5124.8,5128.8
Exp/Cntr=0.3,0.1

Type RM Length L Ch R = 1,5564,486,486,486
BEGIN DESCRIPTION:
Mapping XS 78a5436c
END DESCRIPTION:
XS GIS Cut Line= 4
      2515082.67     13567328.19      2516207.68     13568189.30
      2516985.46     13567897.64      2517748.50     13566988.92
#Sta/Elev= 30
  3087.6  206.13  3093.7  206.82  3101.9  200.83  3108.2  201.40  3115.7  198.47
  3122.7  204.02  3129.2  202.49  3137.3  206.28  3151.8  206.29  3436.5  192.96
  3704.4  186.07  4049.4  178.98  4468.8  177.48  4572.0  176.39  4680.7  172.42
  4850.6  169.61  5108.2  168.40  5108.5  167.90  5112.2  168.40  5238.6  169.36
  5407.3  171.62  5670.0  181.26  5824.1  182.21  5899.9  185.55  5938.4  184.04
  6025.1  188.78  6294.2  194.25  6402.7  196.34  6413.1  196.24  6521.6  199.28
#Mann=15,-1,0
  3087.6    0.12       0  3129.2    0.05       0  3704.4    0.04       0
  4468.8    0.05       0  4572.0    0.12       0  4680.7    0.04       0
  4850.6    0.12       0  5108.2    0.05       0  5112.2    0.12       0
  5238.6    0.04       0  5899.9   0.013       0  5938.4    0.04       0
  6294.2    0.05       0  6402.7    0.12       0  6413.1    0.05       0
Bank Sta=5108.2,5112.2
Exp/Cntr=0.3,0.1

Type RM Length L Ch R = 1,5078,0,0,0
BEGIN DESCRIPTION:
Mapping XS 3fc4663b
END DESCRIPTION:
XS GIS Cut Line= 4
      2514804.88     13567272.62      2516429.90     13568501.80
      2517409.07     13568140.69      2518138.24     13566821.24
#Sta/Elev= 30
  2290.9  204.68  2402.6  203.65  2552.1  202.70  2720.4  195.78  2838.0  192.43
  2933.8  188.36  3067.4  185.67  3356.8  178.94  3865.9  174.17  4284.7  172.45
  4632.3  174.03  4728.2  172.28  4930.7  163.17  4952.1  165.05  5025.5  164.28
  5206.4  163.40  5280.3  162.14  5280.5  161.64  5284.3  162.14  5312.3  162.32
  5563.6  164.46  5867.2  173.16  5976.0  173.34  6166.9  184.58  6266.0  188.41
  6433.9  194.78  6544.3  198.51  6719.5  203.99  6874.1  205.52  6879.6  205.57
#Mann=17,-1,0
  2290.9    0.05       0  2402.6   0.013       0  2552.1    0.05       0
  2720.4    0.12       0  2838.0    0.04       0  2933.8    0.05       0
  3067.4    0.04       0  3865.9    0.05       0  5025.5    0.12       0
  5206.4   0.013       0  5280.3    0.05       0  5284.3   0.013       0
  5312.3    0.04       0  6266.0    0.12       0  6433.9    0.04       0
  6544.3    0.05       0  6874.1   0.013       0
Bank Sta=5280.3,5284.3
Exp/Cntr=0.3,0.1

Chan Stop Cuts=-1