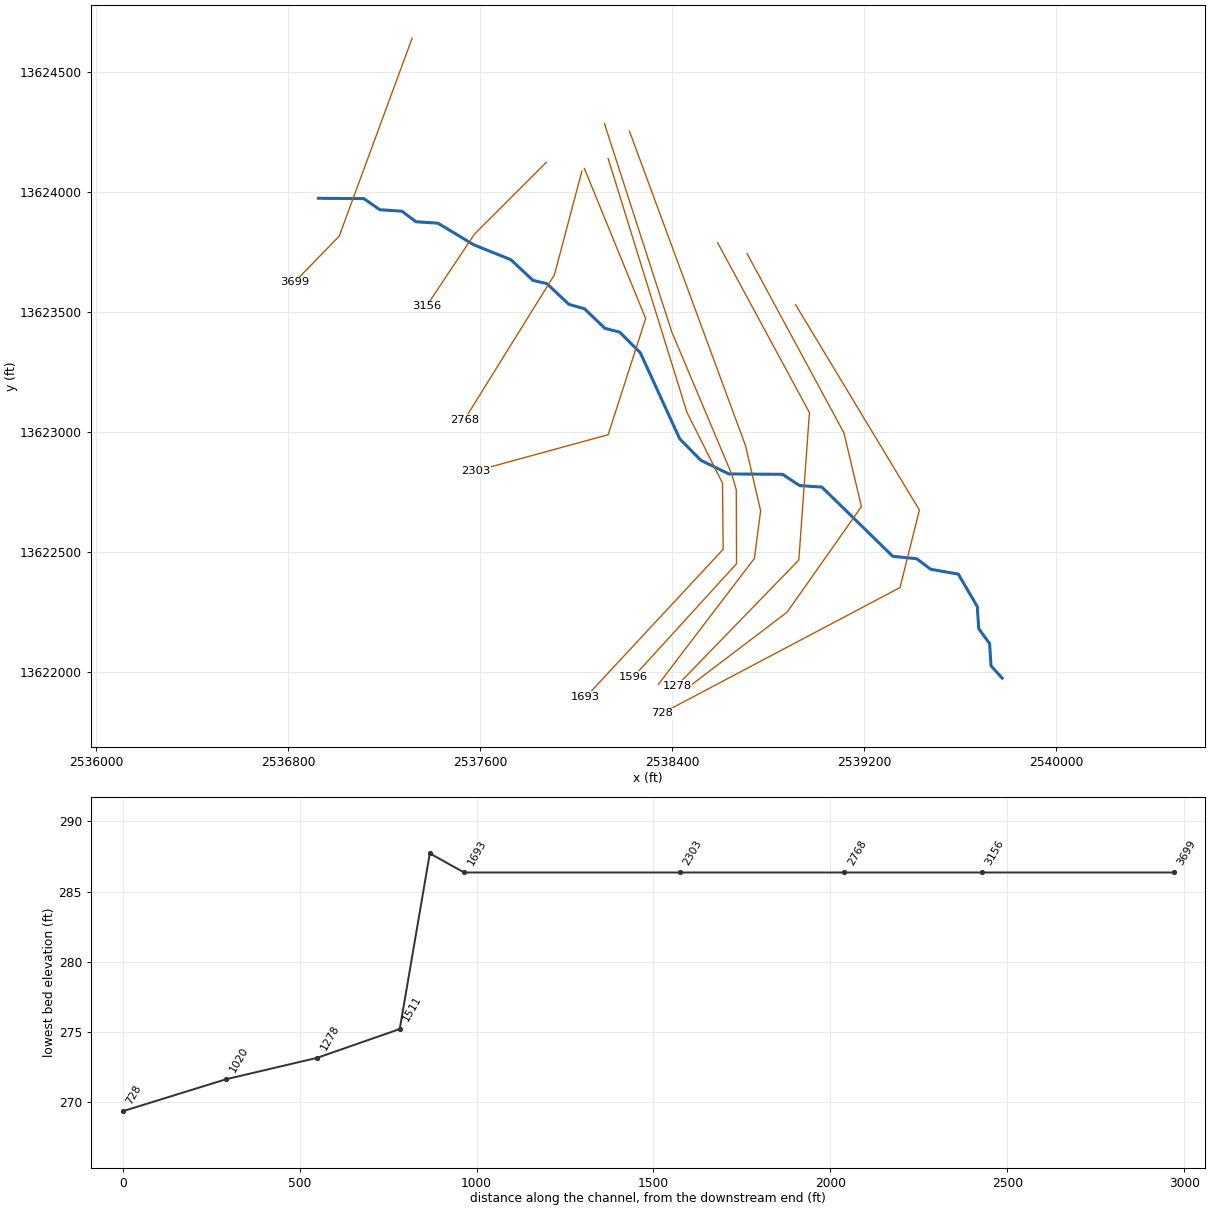
--- TRIB 19 TO IRISH CREEK.prj (project) ---

Proj Title=TRIB 19 TO IRISH CREEK Base Level Engineering
Current Plan=p01
Default Exp/Contr=0.3,0.1
English Units
Geom File=g01
Flow File=f01
Plan File=p01
BEGIN DESCRIPTION:
TRIB 19 TO IRISH CREEK
END DESCRIPTION:

--- TRIB 19 TO IRISH CREEK.p01 (plan) ---

Plan Title=Multiple Run
Short Identifier=Multiple
Geom File=g01
Flow File=f01
Subcritical Flow
K Sum by GR= 0
Std Step Tol= 0.01
Critical Tol= 0.01
Num of Std Step Trials= 20
Max Error Tol= 0.3
Flow Tol Ratio= 0.001
Split Flow NTrial= 30
Split Flow Tol= 0.02
Split Flow Ratio= 0.02
Log Output Level= 0
Friction Slope Method= 1
Unsteady Friction Slope Method= 2
Unsteady Bridges Friction Slope Method= 1
Parabolic Critical Depth
Global Vel Dist=  1 , 1 , 1
Global Log Level= 0
CheckData=True
Encroach Param= -1, 0, 0, 0
BEGIN DESCRIPTION:
Multiple Run
END DESCRIPTION:

--- TRIB 19 TO IRISH CREEK.f01 (steady flow) ---

Flow Title=Multiple
Number of Profiles=7
Profile Names=10-year,25-year,50-year,1pct_min,100-year,1pct_plu,500-year
River Rch & RM= TRIB 19 TO IRISH,Reach-1,3699
     741    1201    1621    1061    2116    4223    3568
Boundary for River Rch & Prof#=TRIB 19 TO IRISH,Reach-1,1
Up Type=0
Dn Type=3
Dn Slope=0.005
Boundary for River Rch & Prof#=TRIB 19 TO IRISH,Reach-1,2
Up Type=0
Dn Type=3
Dn Slope=0.005
Boundary for River Rch & Prof#=TRIB 19 TO IRISH,Reach-1,3
Up Type=0
Dn Type=3
Dn Slope=0.005
Boundary for River Rch & Prof#=TRIB 19 TO IRISH,Reach-1,4
Up Type=0
Dn Type=3
Dn Slope=0.005
Boundary for River Rch & Prof#=TRIB 19 TO IRISH,Reach-1,5
Up Type=0
Dn Type=3
Dn Slope=0.005
Boundary for River Rch & Prof#=TRIB 19 TO IRISH,Reach-1,6
Up Type=0
Dn Type=3
Dn Slope=0.005
Boundary for River Rch & Prof#=TRIB 19 TO IRISH,Reach-1,7
Up Type=0
Dn Type=3
Dn Slope=0.005

--- TRIB 19 TO IRISH CREEK.g01 (geometry) ---

Geom Title=Existing Conditions

River Reach=TRIB 19 TO IRISH,Reach-1
Reach XY= 30
      2536925.00     13623975.00      2537114.50     13623973.79
      2537180.98     13623927.35      2537273.40     13623921.15
      2537330.97     13623877.35      2537423.42     13623871.17
      2537572.80     13623781.08      2537727.29     13623719.15
      2537818.96     13623633.18      2537877.28     13623619.13
      2537968.96     13623533.18      2538034.67     13623514.20
      2538118.96     13623433.18      2538181.07     13623416.85
      2538266.87     13623331.07      2538430.83     13622972.69
      2538518.93     13622883.13      2538635.50     13622826.20
      2538859.78     13622824.48      2538930.98     13622777.36
      2539023.50     13622771.39      2539318.83     13622482.86
      2539419.02     13622472.64      2539476.60     13622428.86
      2539592.13     13622408.70      2539671.18     13622273.42
      2539677.35     13622180.97      2539722.68     13622119.04
      2539728.39     13622026.40      2539775.00     13621975.00

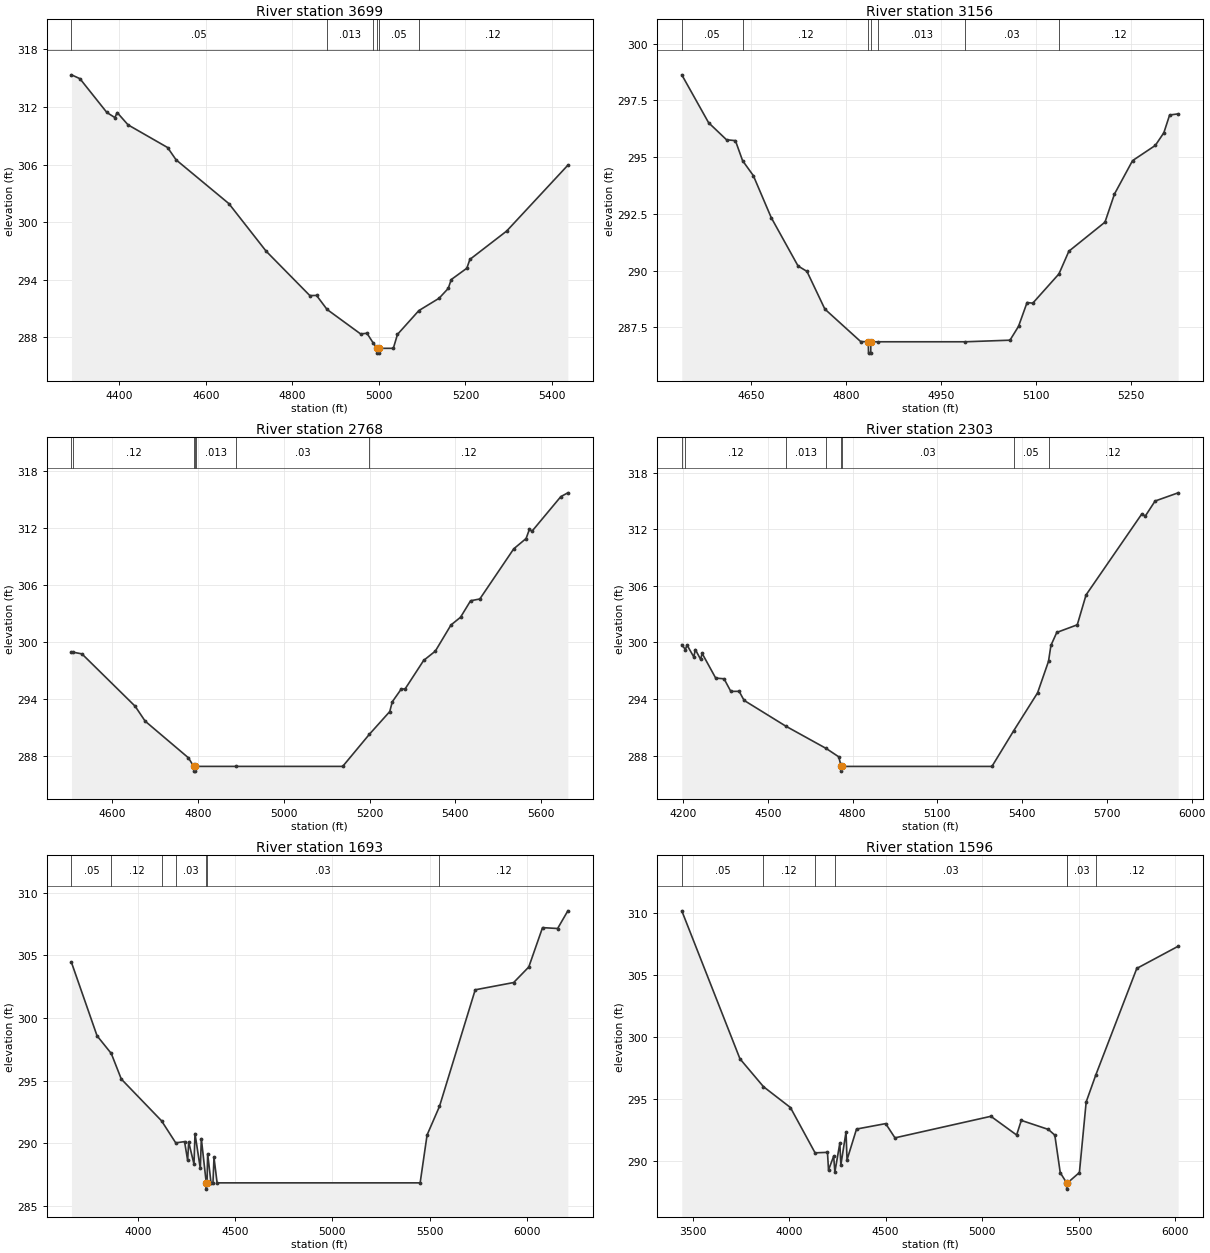
Type RM Length L Ch R = 1,3699,543,543,543
BEGIN DESCRIPTION:
TRIB 19 TO IRISH CREEK 6.0
END DESCRIPTION:
XS GIS Cut Line= 3
      2537315.51     13624641.71      2537011.68     13623817.03
      2536824.99     13623624.99
#Sta/Elev= 30
  4289.9  315.34  4309.4  314.94  4371.6  311.42  4390.1  310.89  4395.5  311.41
  4420.6  310.13  4511.9  307.77  4531.5  306.49  4653.5  301.93  4739.5  296.98
  4840.6  292.35  4856.0  292.37  4880.3  290.91  4957.8  288.36  4972.5  288.43
  4986.3  287.46  4995.6  286.86  4995.8  286.36  4999.3  286.36  4999.6  286.86
  5033.4  286.86  5043.0  288.31  5092.4  290.79  5139.0  292.07  5160.3  293.10
  5167.2  294.02  5203.2  295.20  5210.3  296.12  5295.2  299.07  5436.6  305.93
#Mann=6,-1,0
  4289.9    0.05       0  4880.3   0.013       0  4986.3    0.05       0
  4995.6    0.05       0  4999.6    0.05       0  5092.4    0.12       0
Bank Sta=4995.6,4999.6
Exp/Cntr=0.3,0.1

Type RM Length L Ch R = 1,3156,388,388,388
BEGIN DESCRIPTION:
TRIB 19 TO IRISH CREEK 5.0
END DESCRIPTION:
XS GIS Cut Line= 3
      2537874.97     13624124.97      2537575.00     13623825.00
      2537374.99     13623524.98
#Sta/Elev= 30
  4539.9  298.62  4582.3  296.51  4610.6  295.76  4624.7  295.72  4636.0  294.84
  4653.0  294.18  4681.3  292.33  4723.7  290.20  4737.8  289.96  4766.1  288.30
  4822.7  286.87  4834.8  286.86  4835.1  286.36  4838.6  286.36  4838.8  286.86
  4849.6  286.86  4988.3  286.86  5058.8  286.93  5072.3  287.54  5085.8  288.59
  5094.8  288.56  5136.2  289.85  5151.9  290.85  5209.0  292.13  5224.0  293.37
  5252.6  294.84  5288.6  295.51  5302.1  296.07  5311.2  296.85  5324.7  296.90
#Mann=7,-1,0
  4539.9    0.05       0  4636.0    0.12       0  4834.8    0.03       0
  4838.8    0.12       0  4849.6   0.013       0  4988.3    0.03       0
  5136.2    0.12       0
Bank Sta=4834.8,4838.8
Exp/Cntr=0.3,0.1

Type RM Length L Ch R = 1,2768,465,465,465
BEGIN DESCRIPTION:
Mapping XS c6d1ef59
END DESCRIPTION:
XS GIS Cut Line= 3
      2538023.39     13624088.60      2537908.80     13623656.30
      2537533.80     13623052.14
#Sta/Elev= 30
  4504.4  298.90  4508.0  298.90  4528.8  298.72  4653.0  293.20  4676.3  291.63
  4777.1  287.77  4789.7  286.86  4790.0  286.36  4793.5  286.36  4793.7  286.86
  4793.9  286.86  4889.1  286.86  5137.3  286.86  5199.3  290.23  5247.1  292.64
  5253.0  293.67  5274.3  295.04  5282.7  295.01  5326.2  298.03  5353.4  299.01
  5390.0  301.77  5412.2  302.58  5435.7  304.32  5457.3  304.51  5536.5  309.80
  5565.2  310.88  5573.1  311.86  5579.0  311.65  5646.3  315.30  5662.7  315.70
#Mann=7,-1,0
  4504.4    0.05       0  4508.0    0.12       0  4789.7    0.03       0
  4793.7    0.12       0  4793.9   0.013       0  4889.1    0.03       0
  5199.3    0.12       0
Bank Sta=4789.7,4793.7
Exp/Cntr=0.3,0.1

Type RM Length L Ch R = 1,2303,610,610,610
BEGIN DESCRIPTION:
Mapping XS 123bd553
END DESCRIPTION:
XS GIS Cut Line= 4
      2538033.78     13624099.06      2538289.01     13623474.01
      2538132.76     13622989.64      2537580.65     13622838.59
#Sta/Elev= 30
  4195.8  299.76  4208.5  299.25  4214.3  299.73  4238.3  298.46  4243.7  299.25
  4262.4  298.21  4267.8  298.84  4315.8  296.22  4345.3  296.15  4369.3  294.81
  4398.7  294.82  4416.2  293.86  4564.3  291.12  4706.3  288.77  4751.1  287.88
  4759.9  286.86  4760.1  286.36  4763.9  286.86  5293.3  286.86  5370.1  290.63
  5454.8  294.66  5493.5  298.00  5502.0  299.68  5522.7  301.06  5595.3  301.87
  5626.4  305.04  5823.4  313.61  5836.1  313.40  5870.6  314.99  5952.3  315.86
#Mann=8,-1,0
  4195.8    0.05       0  4208.5    0.12       0  4564.3   0.013       0
  4706.3    0.03       0  4759.9    0.03       0  4763.9    0.03       0
  5370.1    0.05       0  5493.5    0.12       0
Bank Sta=4759.9,4763.9
Exp/Cntr=0.3,0.1

Type RM Length L Ch R = 1,1693,97,97,97
BEGIN DESCRIPTION:
Mapping XS 0415eeb5
END DESCRIPTION:
XS GIS Cut Line= 5
      2538132.75     13624140.71      2538460.89     13623083.39
      2538609.36     13622787.83      2538611.97     13622511.79
      2538039.54     13621896.45
#Sta/Elev= 30
  3657.2  304.44  3788.8  298.59  3862.0  297.18  3913.5  295.14  4120.6  291.81
  4193.7  290.05  4239.1  290.15  4255.0  288.65  4260.2  290.13  4287.6  288.35
  4292.8  290.79  4320.1  288.01  4325.4  290.39  4350.7  286.86  4351.0  286.36
  4354.7  286.86  4357.9  289.19  4375.2  286.86  4385.3  286.86  4390.5  288.89
  4406.6  286.86  5451.4  286.86  5487.1  290.68  5550.9  292.96  5734.8  302.26
  5932.7  302.84  6010.4  304.08  6081.2  307.22  6158.9  307.15  6211.5  308.56
#Mann=7,-1,0
  3657.2    0.05       0  3862.0    0.12       0  4120.6   0.013       0
  4193.7    0.03       0  4350.7    0.03       0  4354.7    0.03       0
  5550.9    0.12       0
Bank Sta=4350.7,4354.7
Exp/Cntr=0.3,0.1

Type RM Length L Ch R = 1,1596,85,85,85
BEGIN DESCRIPTION:
Mapping XS 253b4ba3
END DESCRIPTION:
XS GIS Cut Line= 6
      2538117.15     13624286.47      2538398.39     13623416.72
      2538647.25     13622826.24      2538666.78     13622760.05
      2538667.87     13622451.89      2538237.28     13621979.61
#Sta/Elev= 30
  3443.6  310.19  3745.0  298.24  3866.9  295.99  4006.4  294.31  4134.2  290.65
  4198.5  290.69  4203.8  289.26  4230.5  290.38  4236.8  289.10  4262.5  291.44
  4267.8  289.67  4294.6  292.34  4299.8  290.09  4349.0  292.57  4500.0  293.01
  4548.1  291.86  5045.2  293.60  5178.5  292.09  5202.7  293.27  5342.9  292.54
  5376.4  292.08  5404.5  289.05  5437.9  288.22  5438.1  287.72  5441.9  288.22
  5503.8  289.06  5538.9  294.76  5588.8  296.94  5801.1  305.54  6015.5  307.33
#Mann=7,-1,0
  3443.6    0.05       0  3866.9    0.12       0  4134.2   0.013       0
  4236.8    0.03       0  5437.9    0.03       0  5441.9    0.03       0
  5588.8    0.12       0
Bank Sta=5437.9,5441.9
Exp/Cntr=0.3,0.1

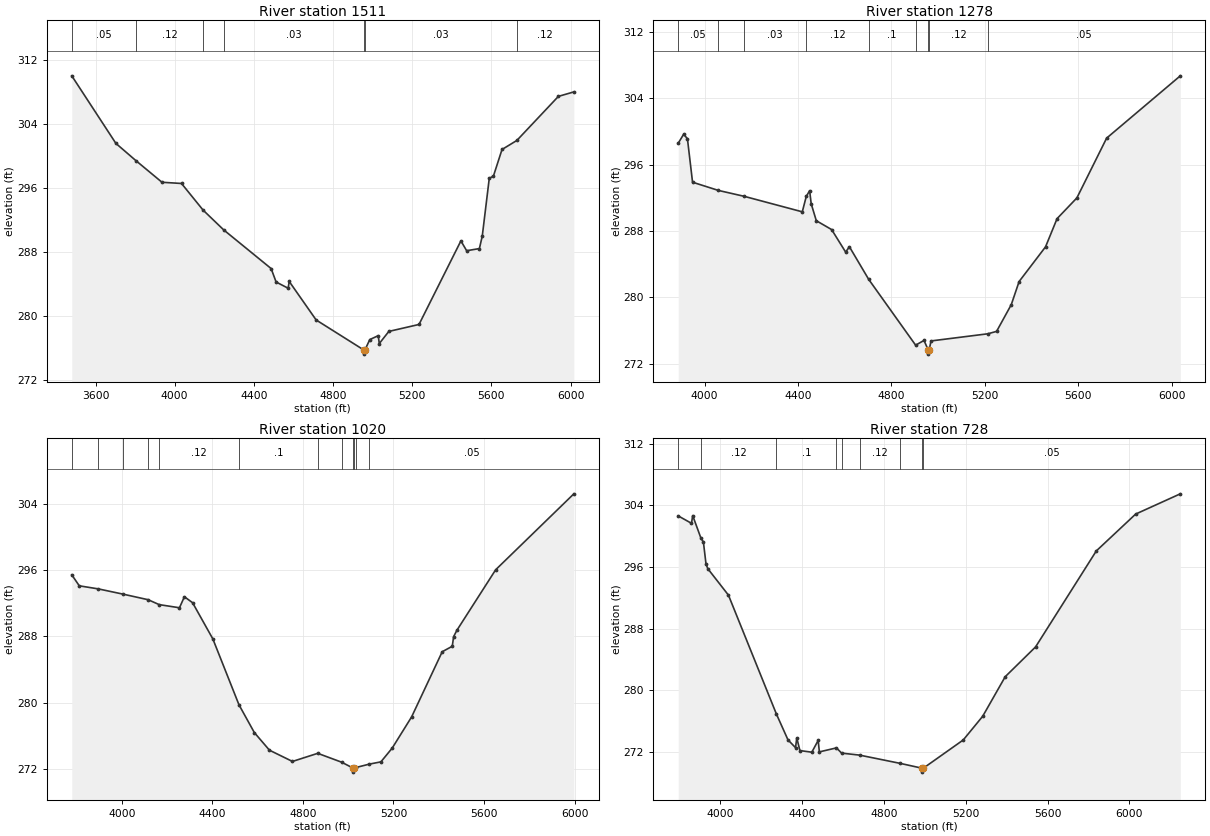
Type RM Length L Ch R = 1,1511,233,233,233
BEGIN DESCRIPTION:
Mapping XS 38ec4a04
END DESCRIPTION:
XS GIS Cut Line= 5
      2538221.31     13624255.23      2538705.68     13622942.76
      2538768.18     13622671.93      2538742.14     13622474.01
      2538341.85     13621948.96
#Sta/Elev= 30
  3480.1  310.00  3703.1  301.55  3804.0  299.40  3935.9  296.69  4034.6  296.54
  4143.6  293.21  4247.5  290.74  4487.4  285.90  4512.5  284.22  4573.4  283.44
  4578.7  284.29  4714.9  279.47  4956.9  275.70  4957.1  275.20  4960.9  275.70
  4985.9  277.02  5028.7  277.51  5033.8  276.52  5082.1  278.04  5234.6  278.91
  5446.2  289.36  5475.3  288.13  5539.7  288.40  5554.2  289.96  5589.6  297.19
  5610.4  297.45  5654.0  300.79  5729.0  301.92  5938.8  307.43  6016.9  307.99
#Mann=7,-1,0
  3480.1    0.05       0  3804.0    0.12       0  4143.6   0.013       0
  4247.5    0.03       0  4956.9    0.03       0  4960.9    0.03       0
  5729.0    0.12       0
Bank Sta=4956.9,4960.9
Exp/Cntr=0.3,0.1

Type RM Length L Ch R = 1,1278,258,258,258
BEGIN DESCRIPTION:
Mapping XS abe09e42
END DESCRIPTION:
XS GIS Cut Line= 4
      2538588.81     13623790.12      2538971.61     13623081.80
      2538927.34     13622467.22      2538419.74     13621944.00
#Sta/Elev= 30
  3887.3  298.57  3910.5  299.65  3926.7  299.11  3948.6  293.87  4059.1  292.88
  4169.5  292.17  4418.6  290.30  4435.7  292.16  4450.1  292.85  4456.7  291.28
  4478.6  289.23  4544.3  288.16  4604.2  285.45  4620.4  286.09  4703.0  282.16
  4904.0  274.23  4939.9  274.80  4957.9  273.65  4958.2  273.15  4961.9  273.65
  4970.0  274.74  5212.9  275.60  5250.7  275.89  5313.6  279.11  5347.2  281.90
  5460.4  286.08  5509.8  289.48  5594.7  291.98  5722.0  299.18  6037.6  306.69
#Mann=9,-1,0
  3887.3    0.05       0  4059.1   0.013       0  4169.5    0.03       0
  4435.7    0.12       0  4703.0     0.1       0  4904.0    0.12       0
  4957.9    0.05       0  4961.9    0.12       0  5212.9    0.05       0
Bank Sta=4957.9,4961.9
Exp/Cntr=0.3,0.1

Type RM Length L Ch R = 1,1020,292,292,292
BEGIN DESCRIPTION:
Mapping XS a298c9b1
END DESCRIPTION:
XS GIS Cut Line= 5
      2538711.77     13623744.69      2539115.44     13622997.25
      2539188.36     13622689.96      2538878.46     13622249.85
      2538468.47     13621938.47
#Sta/Elev= 30
  3778.5  295.45  3811.7  294.12  3895.6  293.75  4005.9  293.11  4116.2  292.44
  4164.7  291.85  4254.3  291.47  4276.2  292.80  4312.3  292.08  4401.8  287.71
  4517.3  279.75  4585.1  276.40  4651.9  274.27  4753.6  272.91  4865.3  273.89
  4970.8  272.82  5020.5  272.12  5020.7  271.62  5024.5  272.12  5034.6  272.18
  5093.7  272.59  5144.4  272.86  5194.5  274.53  5280.1  278.29  5415.3  286.16
  5459.7  286.82  5465.8  287.99  5480.6  288.77  5651.5  296.06  5996.9  305.23
#Mann=12,-1,0
  3778.5    0.05       0  3895.6   0.013       0  4005.9    0.05       0
  4116.2    0.03       0  4164.7    0.12       0  4517.3     0.1       0
  4865.3    0.12       0  4970.8    0.05       0  5020.5    0.05       0
  5024.5    0.05       0  5034.6    0.12       0  5093.7    0.05       0
Bank Sta=5020.5,5024.5
Exp/Cntr=0.3,0.1

Type RM Length L Ch R = 1,728,0,0,0
BEGIN DESCRIPTION:
Mapping XS b9576848
END DESCRIPTION:
XS GIS Cut Line= 4
      2538913.99     13623531.33      2539429.95     13622675.55
      2539349.22     13622352.64      2538356.70     13621828.17
#Sta/Elev= 30
  3794.0  302.63  3858.8  301.67  3864.7  302.67  3904.6  299.77  3917.1  299.23
  3929.8  296.38  3938.4  295.78  4039.4  292.34  4274.4  276.86  4330.6  273.53
  4367.5  272.52  4373.6  273.78  4388.9  272.14  4447.1  271.93  4478.2  273.46
  4484.0  271.97  4567.6  272.49  4592.7  271.81  4680.7  271.55  4880.6  270.47
  4987.7  269.84  4987.9  269.34  4991.7  269.84  5187.5  273.52  5282.6  276.60
  5392.7  281.74  5541.1  285.61  5838.0  298.08  6030.4  302.87  6248.7  305.50
#Mann=9,-1,0
  3794.0    0.05       0  3904.6    0.12       0  4274.4     0.1       0
  4567.6    0.12       0  4592.7    0.04       0  4680.7    0.12       0
  4880.6    0.05       0  4987.7    0.05       0  4991.7    0.05       0
Bank Sta=4987.7,4991.7
Exp/Cntr=0.3,0.1

Chan Stop Cuts=-1