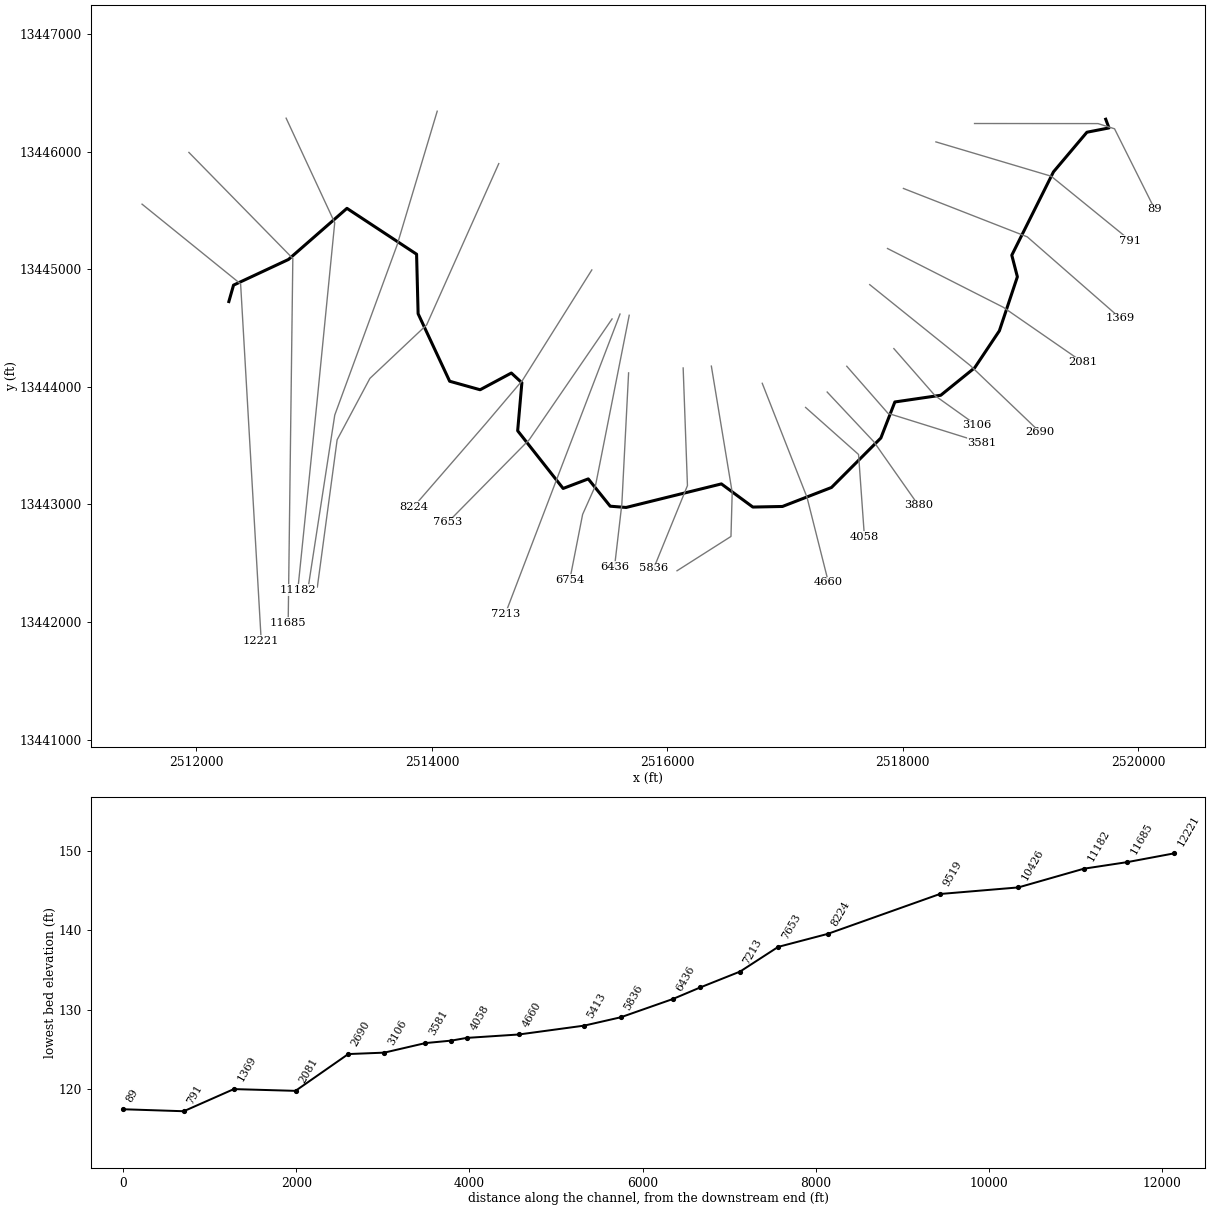
--- TRIB 1A TO ROAD CREEK.prj (project) ---

Proj Title=TRIB 1A TO ROAD CREEK Base Level Engineering
Current Plan=p01
Default Exp/Contr=0.3,0.1
English Units
Geom File=g01
Flow File=f01
Plan File=p01
Y Axis Title=Elevation
X Axis Title(PF)=Main Channel Distance
X Axis Title(XS)=Station
BEGIN DESCRIPTION:
TRIB 1A TO ROAD CREEK
END DESCRIPTION:
DSS Export Rating Curves= 0
DSS Export Rating Curve Sorted= 0
DSS Export Volume Flow Curves= 0
DXF OffsetX= 0
DXF OffsetY= 0
DXF ScaleX= 1
DXF ScaleY= 10

--- TRIB 1A TO ROAD CREEK.p01 (plan) ---

Plan Title=Multiple Run
Short Identifier=Multiple
Geom File=g01
Flow File=f01
Subcritical Flow
K Sum by GR= 0
Std Step Tol= 0.01
Critical Tol= 0.01
Num of Std Step Trials= 20
Max Error Tol= 0.3
Flow Tol Ratio= 0.001
Split Flow NTrial= 30
Split Flow Tol= 0.02
Split Flow Ratio= 0.02
Log Output Level= 0
Friction Slope Method= 1
Unsteady Friction Slope Method= 2
Unsteady Bridges Friction Slope Method= 1
Parabolic Critical Depth
Global Vel Dist=  1 , 1 , 1
Global Log Level= 0
CheckData=True
Encroach Param= -1, 0, 0, 0
BEGIN DESCRIPTION:
Multiple Run
END DESCRIPTION:

--- TRIB 1A TO ROAD CREEK.f01 (steady flow) ---

Flow Title=Multiple
Number of Profiles=7
Profile Names=10-year,25-year,50-year,1pct_min,100-year,1pct_plu,500-year
River Rch & RM= TRIB 1A TO ROAD ,Reach-1,12221
     384     580     744     461     920    1836    1391
River Rch & RM= TRIB 1A TO ROAD ,Reach-1,11685
     497     761     985     616    1229    2452    1892
River Rch & RM= TRIB 1A TO ROAD ,Reach-1,8224
     744    1175    1554     991    1978    3946    3173
River Rch & RM= TRIB 1A TO ROAD ,Reach-1,6754
     994    1592    2124    1366    2726    5439    4446
River Rch & RM= TRIB 1A TO ROAD ,Reach-1,4660
    1195    1931    2593    1678    3347    6679    5523
Boundary for River Rch & Prof#=TRIB 1A TO ROAD ,Reach-1,1
Up Type=0
Dn Type=3
Dn Slope=0.005
Boundary for River Rch & Prof#=TRIB 1A TO ROAD ,Reach-1,2
Up Type=0
Dn Type=3
Dn Slope=0.005
Boundary for River Rch & Prof#=TRIB 1A TO ROAD ,Reach-1,3
Up Type=0
Dn Type=3
Dn Slope=0.005
Boundary for River Rch & Prof#=TRIB 1A TO ROAD ,Reach-1,4
Up Type=0
Dn Type=3
Dn Slope=0.005
Boundary for River Rch & Prof#=TRIB 1A TO ROAD ,Reach-1,5
Up Type=0
Dn Type=3
Dn Slope=0.005
Boundary for River Rch & Prof#=TRIB 1A TO ROAD ,Reach-1,6
Up Type=0
Dn Type=3
Dn Slope=0.005
Boundary for River Rch & Prof#=TRIB 1A TO ROAD ,Reach-1,7
Up Type=0
Dn Type=3
Dn Slope=0.005

--- TRIB 1A TO ROAD CREEK.g01 (geometry) ---

Geom Title=Existing Conditions
Program Version=4.10

River Reach=TRIB 1A TO ROAD ,Reach-1
Reach XY= 30
        2512275.       13444725.      2512314.83      13444864.7
      2512781.41     13445082.77      2513278.33      13445517.4
        2513870.     13445127.57      2513882.99     13444621.66
      2514150.99     13444047.67      2514409.78     13443975.24
      2514675.01     13444117.47      2514764.52     13444034.85
      2514728.74     13443626.56      2515114.98     13443136.22
      2515328.57     13443217.46      2515514.88     13442985.34
      2515650.11     13442974.68      2516459.61     13443174.92
      2516726.63     13442978.13       2516978.3     13442983.08
      2517395.16     13443144.63      2517814.52      13443565.2
      2517933.48     13443871.49      2518323.54     13443928.54
      2518611.38     13444161.76      2518821.45     13444476.47
      2518974.39     13444935.62      2518926.96     13445119.11
      2519280.85     13445827.29       2519565.2     13446164.52
      2519752.71     13446201.05        2519725.       13446275.

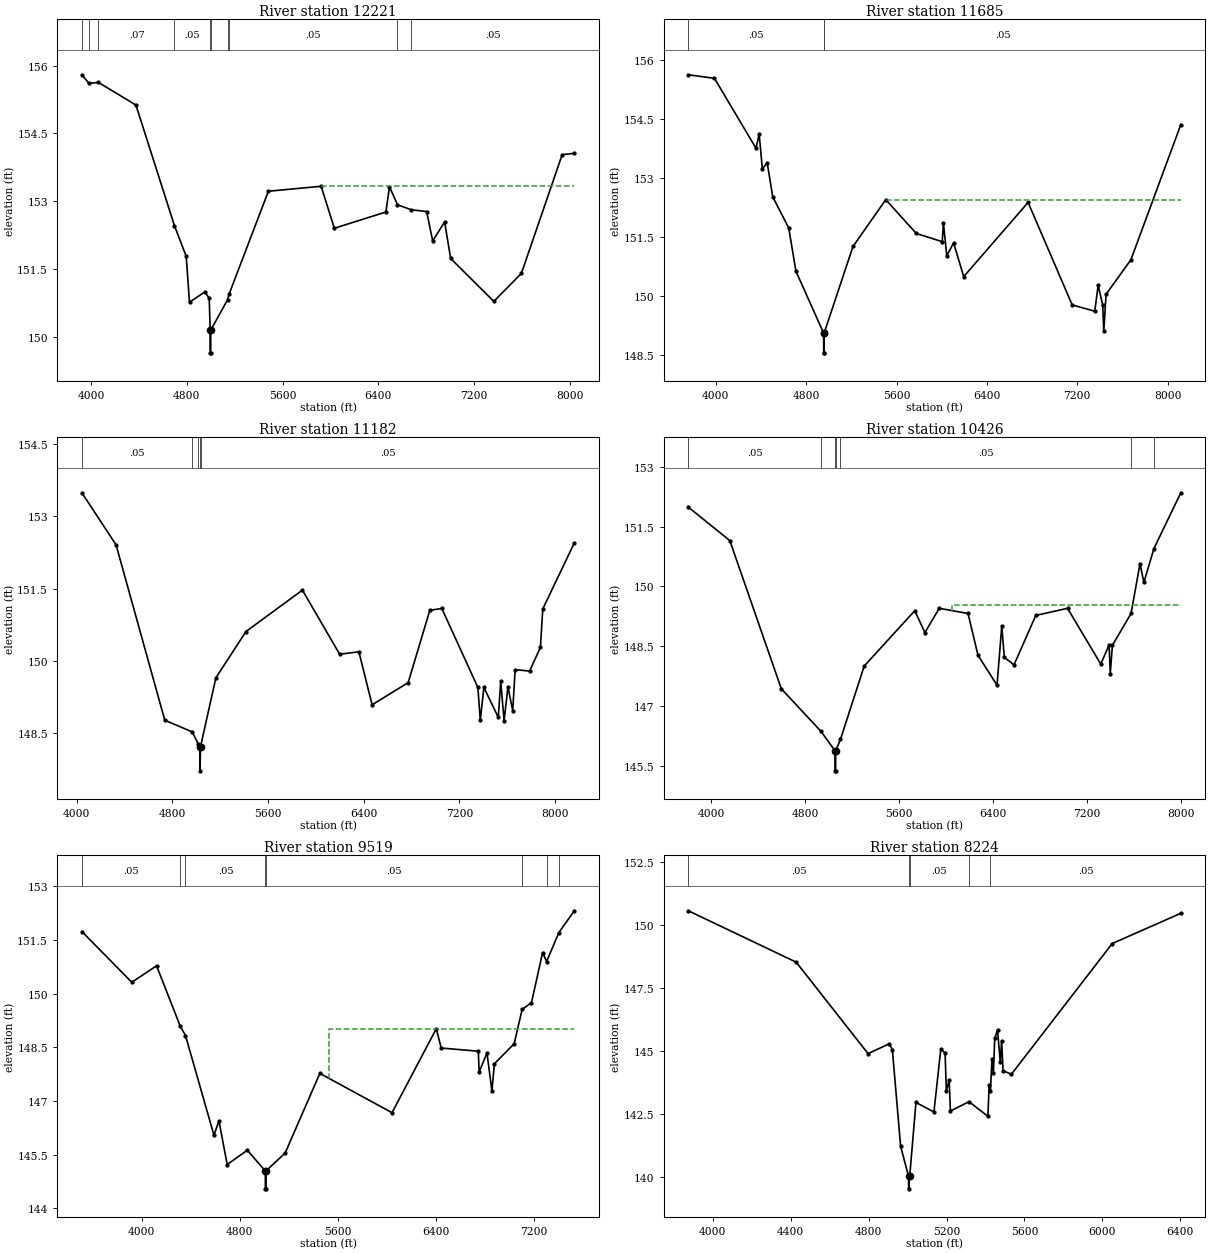
Type RM Length L Ch R = 1 ,12221   ,536,536,536
BEGIN DESCRIPTION:
TRIB 1A TO ROAD CREEK 22.0
END DESCRIPTION:
XS GIS Cut Line= 3
      2511537.54     13445552.98        2512375.       13444875.
      2512549.88     13441843.54
#Sta/Elev= 30
  3923.1   155.8  3982.3  155.61  4061.9  155.63  4374.7  155.13  4696.4  152.46
  4794.7  151.78  4822.4  150.76  4950.3  150.99    4987  150.85  4995.3  150.14
  4995.6  149.64  4999.2  149.64  4999.4  150.14  5141.1  150.82  5154.4  150.95
  5481.4  153.22  5922.1  153.33  6032.3   152.4    6463  152.76  6493.1  153.32
  6559.9  152.92  6674.6  152.81  6803.6  152.77  6853.7  152.12  6953.8  152.54
  7003.9  151.73  7364.5  150.78  7594.9   151.4  7935.5  154.03  8037.1  154.06
#Mann= 10 ,-1 , 0
  3923.1     .07       0  3982.3     .05       0  4061.9     .07       0
  4696.4     .05       0  4995.3     .05       0  4999.4     .05       0
  5141.1      .1       0  5154.4     .05       0  6559.9    .035       0
  6674.6     .05       0
#XS Ineff= 2 , 0
       0                    5922       0  153.33
Permanent Ineff=
       F       F
Bank Sta=4995.3,4999.4
XS Rating Curve= 0 ,0
Exp/Cntr=0.3,0.1

Type RM Length L Ch R = 1 ,11685   ,503,503,503
BEGIN DESCRIPTION:
Mapping XS 25d9a2be
END DESCRIPTION:
XS GIS Cut Line= 3
      2511935.64     13445992.76      2512818.56     13445091.27
      2512779.04     13441993.46
#Sta/Elev= 30
  3756.8  155.63  3988.2  155.54  4355.8  153.76  4384.1  154.12  4412.3  153.23
  4454.8  153.39  4504.4  152.52  4645.8  151.73  4709.4  150.63  4954.9  149.05
  4955.2  148.55  4958.8  148.55    4959  149.05  5214.9  151.26  5504.9  152.45
    5775  151.59    6005  151.38    6015  151.86    6045  151.02    6105  151.35
    6195  150.49    6765  152.38  7155.1  149.77  7355.1  149.61  7385.1  150.27
  7425.1  149.77  7435.1   149.1  7455.1  150.04  7675.1  150.92  8116.7  154.36
#Mann= 3 ,-1 , 0
  3756.8     .05       0  4954.9     .05       0    4959     .05       0
#XS Ineff= 2 , 0
       0                    5504       0  152.45
Permanent Ineff=
       F       F
Bank Sta=4954.9,4959
XS Rating Curve= 0 ,0
Exp/Cntr=0.3,0.1

Type RM Length L Ch R = 1 ,11182   ,756,756,756
BEGIN DESCRIPTION:
Mapping XS 50ce673e
END DESCRIPTION:
XS GIS Cut Line= 4
      2512761.65     13446283.96      2513174.46     13445395.09
      2513025.55     13443887.23      2512860.62     13442272.68
#Sta/Elev= 30
  4042.1  153.49  4328.1  152.41  4735.6  148.77  4964.1  148.53  5015.7  148.28
  5030.2  148.22  5030.5  147.72  5034.3  148.22  5162.9  149.65  5414.1  150.61
  5886.5  151.47  6197.9  150.14  6358.7  150.19  6469.2  149.09  6770.8  149.55
  6951.7  151.05  7052.2  151.09  7353.8  149.45  7373.9  148.77  7404.1  149.45
  7524.7  148.83  7544.8  149.58  7572.9  148.76  7605.1  149.46  7645.3  148.97
  7665.4  149.82    7786  149.79  7876.5  150.28  7896.6  151.08  8160.3  152.45
#Mann= 5 ,-1 , 0
  4042.1     .05       0  4964.1      .1       0  5015.7     .05       0
  5030.2     .05       0  5034.3     .05       0
#XS Ineff= 2 , 0
       0                  5886.5       0  151.47
Permanent Ineff=
       F       F
Bank Sta=5030.2,5034.3
XS Rating Curve= 0 ,0
Exp/Cntr=0.3,0.1

Type RM Length L Ch R = 1 ,10426   ,907,907,907
BEGIN DESCRIPTION:
Mapping XS fd544119
END DESCRIPTION:
XS GIS Cut Line= 4
      2514045.24     13446343.33      2513703.98     13445204.11
      2513174.79     13443760.12      2512951.76     13442311.73
#Sta/Elev= 30
  3804.4  151.99  4157.6  151.15    4596  147.43  4934.3  146.36  5054.3  145.87
  5054.7  145.37  5058.5  145.37  5058.8  145.87  5099.8  146.16  5301.6     148
  5732.3  149.39  5818.5  148.84  5940.6  149.45  6185.5  149.32  6270.7  148.27
  6432.5  147.52  6473.1  149.01  6494.4  148.22  6577.2  148.03  6762.3  149.27
  7032.5  149.45  7315.8  148.05  7386.6  148.53  7396.7  147.81  7414.6  148.52
  7573.7  149.32  7649.7  150.57  7682.6   150.1  7768.3  150.95    7997  152.35
#Mann= 7 ,-1 , 0
  3804.4     .05       0  4934.3      .1       0  5054.3     .05       0
  5058.8      .1       0  5099.8     .05       0  7573.7     .07       0
  7768.3     .05       0
#XS Ineff= 2 , 0
       0                  6051.9       0  149.54
Permanent Ineff=
       F       F
Bank Sta=5054.3,5058.8
XS Rating Curve= 0 ,0
Exp/Cntr=0.3,0.1

Type RM Length L Ch R = 1 ,9519    ,1295,1295,1295
BEGIN DESCRIPTION:
Mapping XS 419062a3
END DESCRIPTION:
XS GIS Cut Line= 5
       2514568.2      13445897.7      2513955.71     13444527.03
      2513473.37     13444071.92      2513194.92     13443549.83
      2513026.91     13442298.51
#Sta/Elev= 30
  3511.9  151.74  3919.4  150.32  4121.5  150.78  4313.8   149.1  4357.5  148.83
  4589.9  146.04  4630.8  146.44  4697.8  145.22  4862.1  145.62  5009.3  145.04
  5009.6  144.54  5013.5  144.54  5013.8  145.04  5170.7  145.54  5453.9  147.77
    6043  146.67  6404.1  149.02  6444.5  148.48  6747.1  148.39    6754  147.81
  6817.8  148.34  6858.1  147.28  6878.3  148.04  7039.7   148.6  7104.7  149.56
    7181  149.75  7271.8  151.15  7304.5   150.9  7404.4  151.71  7530.6  152.32
#Mann= 8 ,-1 , 0
  3511.9     .05       0  4313.8     .12       0  4357.5     .05       0
  5009.3     .05       0  5013.8     .05       0  7104.7     .12       0
  7304.5     .07       0  7404.4     .05       0
#XS Ineff= 2 , 0
       0                  5531.6       0     149
Permanent Ineff=
       F       F
Bank Sta=5009.3,5013.8
XS Rating Curve= 0 ,0
Exp/Cntr=0.3,0.1

Type RM Length L Ch R = 1 ,8224    ,571,571,571
BEGIN DESCRIPTION:
Mapping XS 11947cde
END DESCRIPTION:
XS GIS Cut Line= 4
      2515358.81     13444993.83      2514770.24      13444056.3
      2514452.53      13443681.3      2513843.95     13442979.08
#Sta/Elev= 30
  3874.5  150.57  4428.1  148.53  4796.9   144.9  4906.5  145.29  4921.8  145.05
  4964.2  141.22  5004.9  140.03  5005.4  139.53  5010.8  140.03  5042.9  142.96
  5135.2  142.58  5170.3  145.07  5192.4  144.93  5198.9  143.41  5213.2  143.86
  5219.8  142.62  5315.1  142.99  5412.1  142.41  5418.6  143.67  5425.2  143.42
  5432.9  144.68  5440.6  144.14  5447.2   145.5  5461.5  145.84  5475.8  144.55
  5482.4  145.41    5490  144.22  5532.8  144.08  6050.3  149.27  6402.2  150.47
#Mann= 5 ,-1 , 0
  3874.5     .05       0  5004.9     .05       0  5010.8     .05       0
  5315.1     .12       0  5425.2     .05       0
Bank Sta=5004.9,5010.8
XS Rating Curve= 0 ,0
Exp/Cntr=0.3,0.1

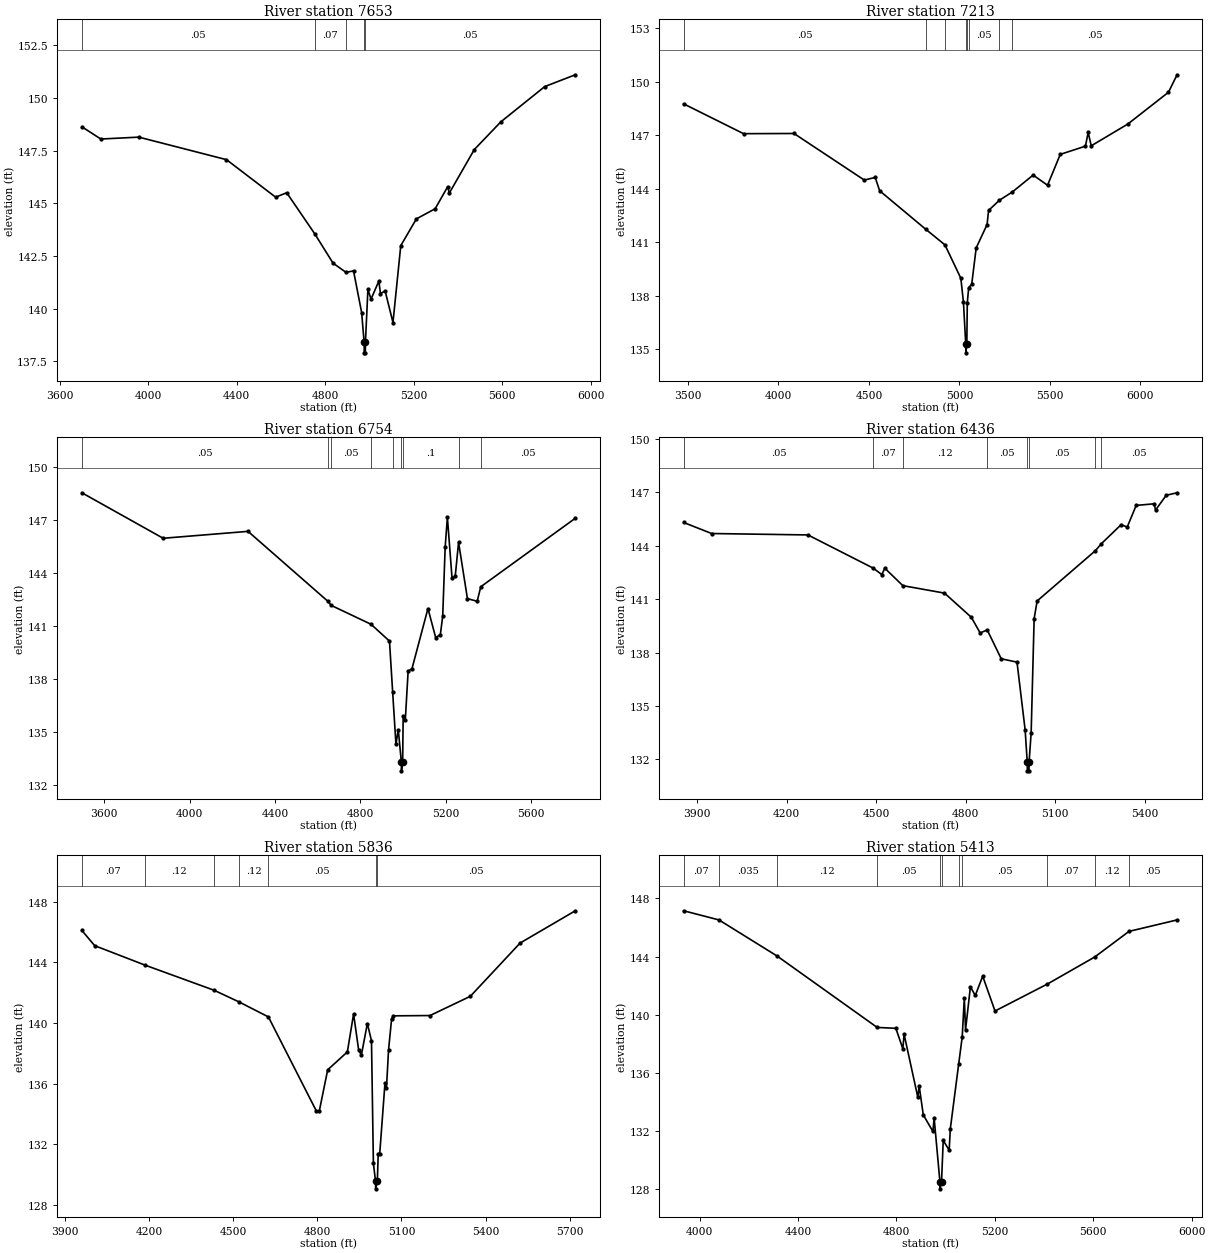
Type RM Length L Ch R = 1 ,7653    ,440,440,440
BEGIN DESCRIPTION:
Mapping XS 2f4b1b47
END DESCRIPTION:
XS GIS Cut Line= 3
      2515530.67     13444577.14      2514827.53     13443551.09
       2514135.8     13442848.95
#Sta/Elev= 30
  3700.8  148.63  3786.3  148.05    3958  148.14  4354.2  147.07  4576.2  145.29
  4626.3   145.5    4753  143.55  4835.5  142.16  4894.3  141.72  4928.2  141.79
  4964.9  139.81  4976.1   138.4  4976.6   137.9  4981.5   137.9    4982   138.4
  4993.2  140.91  5007.4  140.45  5042.7  141.31  5049.8  140.71    5071  140.84
  5106.4  139.34  5141.7  142.99  5212.4  144.26  5297.1  144.74  5353.8  145.79
  5360.8  145.48    5474  147.55  5594.3  148.87  5792.3  150.54  5930.3   151.1
#Mann= 5 ,-1 , 0
  3700.8     .05       0    4753     .07       0  4894.3     .05       0
  4976.1     .05       0    4982     .05       0
Bank Sta=4976.1,4982
XS Rating Curve= 0 ,0
Exp/Cntr=0.3,0.1

Type RM Length L Ch R = 1 ,7213    ,459,459,459
BEGIN DESCRIPTION:
Mapping XS 4def4bdb
END DESCRIPTION:
XS GIS Cut Line= 3
      2515598.36     13444618.76      2515061.91     13443217.75
      2514624.41     13442071.94
#Sta/Elev= 30
  3476.3  148.75  3807.1  147.08  4086.1  147.09  4474.6  144.48  4534.7  144.63
  4559.4  143.88  4813.4  141.73  4920.2  140.85    5008  138.98  5022.3  137.65
  5035.2   135.3  5035.7   134.8  5041.1   135.3  5043.7   137.6  5051.4  138.45
  5068.2  138.65  5092.9  140.68  5153.1  141.99  5161.4  142.78  5221.3  143.35
  5293.5  143.82  5407.7  144.76  5487.2  144.19  5557.5  145.92  5696.6  146.38
  5711.7  147.15  5728.7   146.4  5930.9  147.62  6155.4   149.4    6203  150.38
#Mann= 8 ,-1 , 0
  3476.3     .05       0  4813.4      .1       0  4920.2     .12       0
  5035.2     .05       0  5041.1     .12       0  5051.4     .05       0
  5221.3     .12       0  5293.5     .05       0
Bank Sta=5035.2,5041.1
XS Rating Curve= 0 ,0
Exp/Cntr=0.3,0.1

Type RM Length L Ch R = 1 ,6754    ,318,318,318
BEGIN DESCRIPTION:
Mapping XS 2a70ea3d
END DESCRIPTION:
XS GIS Cut Line= 4
      2515676.49     13444608.37      2515390.03     13443160.46
      2515280.66     13442915.67      2515171.44     13442359.17
#Sta/Elev= 30
  3495.3  148.52  3875.9  145.95  4273.5  146.34  4647.5  142.39  4662.7  142.16
  4849.7  141.09  4936.1  140.14  4950.9  137.27  4966.4  134.31  4977.3  135.14
  4991.7  133.31  4992.2  132.81  4997.8  133.31  5000.2   135.9  5010.1  135.66
  5023.5  138.45  5041.2  138.57  5116.3  141.98  5152.5  140.34  5174.4  140.51
  5185.4  141.54  5196.9  145.43  5207.3  147.14  5229.2  143.69    5244  143.79
  5259.7  145.72  5301.2  142.54  5346.9  142.39  5363.7  143.21  5806.5  147.08
#Mann= 9 ,-1 , 0
  3495.3     .05       0  4647.5     .07       0  4662.7     .05       0
  4849.7     .12       0  4950.9      .1       0  4991.7     .05       0
  4997.8      .1       0  5259.7     .07       0  5363.7     .05       0
Bank Sta=4991.7,4997.8
XS Rating Curve= 0 ,0
Exp/Cntr=0.3,0.1

Type RM Length L Ch R = 1 ,6436    ,600,600,600
BEGIN DESCRIPTION:
Mapping XS c6ebc9bd
END DESCRIPTION:
XS GIS Cut Line= 3
      2515671.28     13444118.76      2515613.99     13443004.21
      2515551.62     13442468.86
#Sta/Elev= 30
  3854.1  145.31    3948  144.69    4271  144.61  4490.4  142.74  4518.7  142.38
  4528.8  142.74  4589.3  141.76    4729  141.34  4819.1  139.98  4848.6   139.1
  4872.3  139.27  4919.3  137.65  4972.2  137.46  4999.5  133.65  5006.5  131.85
    5007  131.35  5012.3  131.35  5012.8  131.85  5019.7   133.5  5029.7  139.91
  5039.8   140.9  5235.5  143.73  5254.7  144.11  5321.7  145.19  5341.8  145.05
    5372  146.27    5432  146.36  5437.1  146.01  5472.7  146.84  5509.1  146.98
#Mann= 8 ,-1 , 0
  3854.1     .05       0  4490.4     .07       0  4589.3     .12       0
  4872.3     .05       0  5006.5     .05       0  5012.8     .05       0
  5235.5     .07       0  5254.7     .05       0
Bank Sta=5006.5,5012.8
XS Rating Curve= 0 ,0
Exp/Cntr=0.3,0.1

Type RM Length L Ch R = 1 ,5836    ,423,423,423
BEGIN DESCRIPTION:
Mapping XS e00efa19
END DESCRIPTION:
XS GIS Cut Line= 3
      2516134.83     13444160.45      2516171.28     13443160.46
      2515885.35     13442458.63
#Sta/Elev= 30
  3961.1   146.1  4006.6   145.1  4185.5  143.82  4431.9  142.16  4519.9   141.4
  4625.8   140.4  4797.1  134.18  4807.1  134.18  4837.1  136.91  4907.2  138.09
  4929.4  140.59  4947.2  138.25    4957  137.87  4978.5  139.96  4993.2  138.83
    5000  130.75  5007.6  129.56  5008.1  129.06  5014.1  129.56  5017.2  131.39
  5022.6  131.38  5041.3  136.04  5046.7  135.74    5054  138.21  5064.8  140.25
  5070.7  140.47  5201.8  140.49  5345.6  141.76  5522.8  145.27  5719.6   147.4
#Mann= 7 ,-1 , 0
  3961.1     .07       0  4185.5     .12       0  4431.9    .035       0
  4519.9     .12       0  4625.8     .05       0  5007.6     .05       0
  5014.1     .05       0
Bank Sta=5007.6,5014.1
XS Rating Curve= 0 ,0
Exp/Cntr=0.3,0.1

Type RM Length L Ch R = 1 ,5413    ,753,753,753
BEGIN DESCRIPTION:
Mapping XS 9e4a3f94
END DESCRIPTION:
XS GIS Cut Line= 4
      2516374.41     13444176.08      2516551.49     13443103.17
      2516541.08     13442728.17      2516082.77     13442436.52
#Sta/Elev= 30
    3935  147.15  4078.5  146.52  4314.4  144.04  4721.7  139.12  4797.6  139.06
    4826  137.65  4831.1  138.65  4887.1   134.3  4892.2  135.12  4909.1   133.1
  4948.2  131.96  4953.3  132.87  4976.7  128.51  4977.2  128.01  4983.3  128.51
  4990.2  131.34  5014.4  130.67    5019  132.14  5053.2  136.63  5067.4  138.47
  5075.9  141.14  5080.9  138.95  5100.6  141.91  5120.6  141.32  5150.6  142.65
  5200.7  140.25    5414  142.11  5606.3  143.97  5745.2  145.73  5940.8  146.52
#Mann= 11 ,-1 , 0
    3935     .07       0  4078.5    .035       0  4314.4     .12       0
  4721.7     .05       0  4976.7     .05       0  4983.3     .05       0
  5053.2     .07       0  5067.4     .05       0    5414     .07       0
  5606.3     .12       0  5745.2     .05       0
Bank Sta=4976.7,4983.3
XS Rating Curve= 0 ,0
Exp/Cntr=0.3,0.1

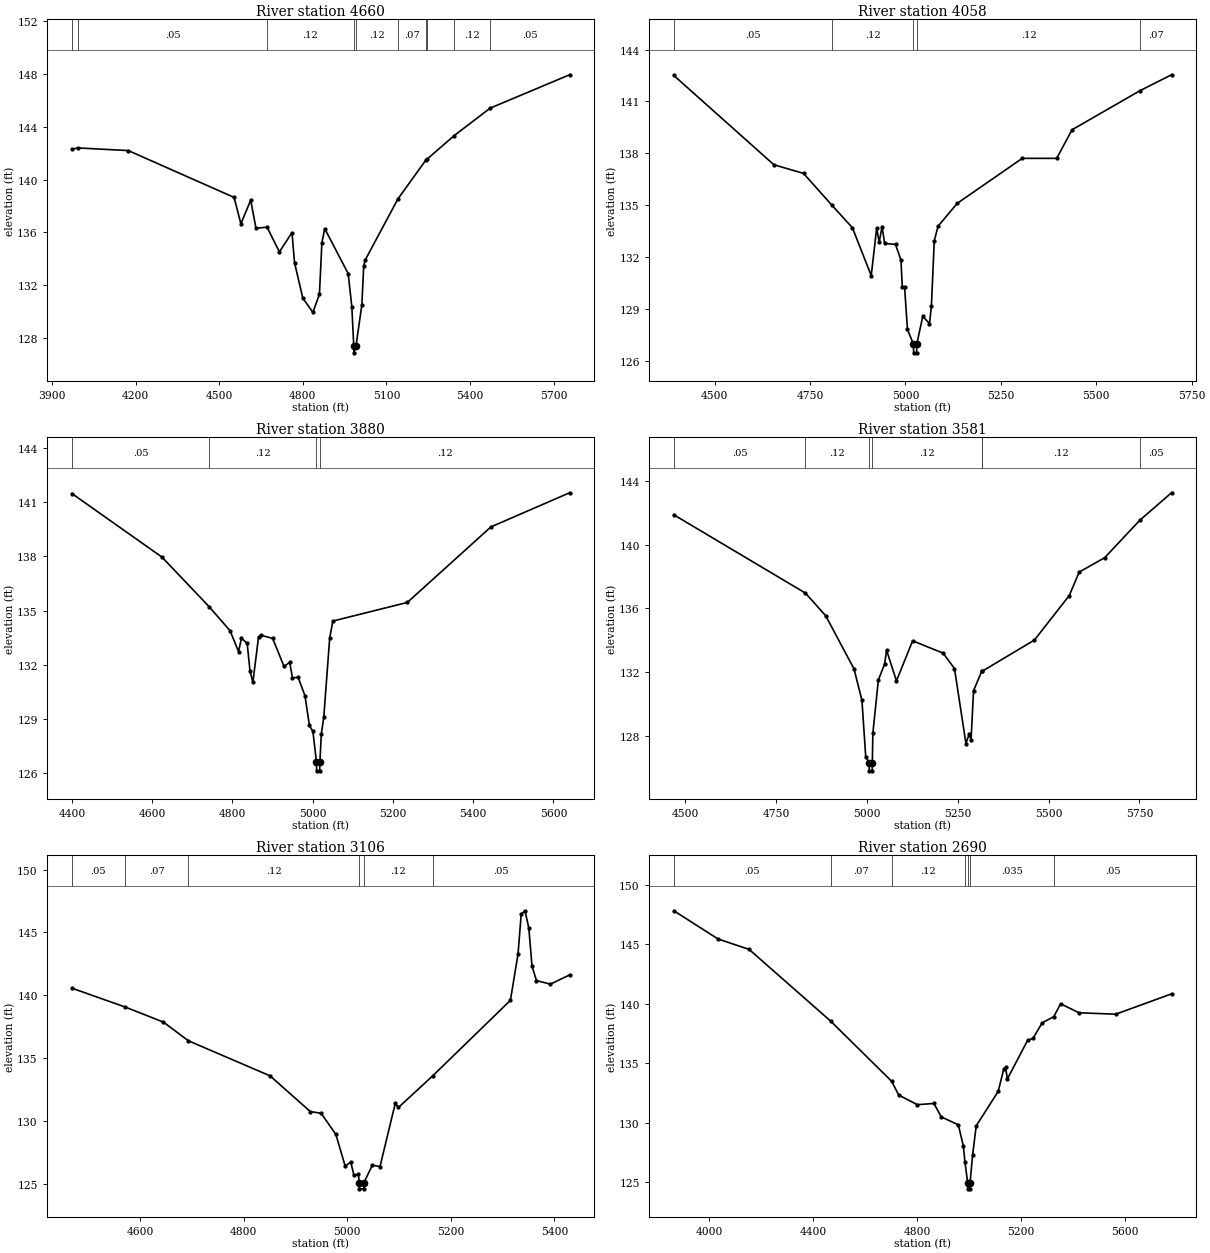
Type RM Length L Ch R = 1 ,4660    ,602,602,602
BEGIN DESCRIPTION:
Mapping XS ad86ed0a
END DESCRIPTION:
XS GIS Cut Line= 3
      2516806.72     13444030.21      2517186.91      13443061.5
      2517368.88     13442338.81
#Sta/Elev= 30
  3971.3  142.29  3993.3  142.39  4173.8  142.19  4553.4  138.65  4577.8  136.66
    4613  138.44    4632  136.32  4671.7   136.4    4716  134.53  4761.1  135.99
  4770.3  133.72  4800.1  131.03  4836.3  129.96  4859.7  131.34  4868.5  135.23
  4878.7  136.29  4962.8  132.89    4976  130.37  4982.8   127.4  4983.3   126.9
  4990.7   127.4  5011.9  130.53  5018.7  133.49  5024.2  133.93  5141.2  138.53
  5242.2  141.49  5245.7  141.54  5343.2  143.32  5472.5   145.4  5757.2  147.92
#Mann= 10 ,-1 , 0
  3971.3    .035       0  3993.3     .05       0  4671.7     .12       0
  4982.8     .05       0  4990.7     .12       0  5141.2     .07       0
  5242.2     .05       0  5245.7     .07       0  5343.2     .12       0
  5472.5     .05       0
Bank Sta=4982.8,4990.7
XS Rating Curve= 0 ,0
Exp/Cntr=0.3,0.1

Type RM Length L Ch R = 1 ,4058    ,178,178,178
BEGIN DESCRIPTION:
TRIB 1A TO ROAD CREEK 9.0
END DESCRIPTION:
XS GIS Cut Line= 3
      2517174.99     13443825.01        2517625.       13443425.
        2517675.     13442724.98
#Sta/Elev= 30
  4393.3   142.5  4655.5  137.34  4733.2  136.84  4807.9  134.99  4861.2   133.7
  4910.5  130.93  4924.7  133.67  4931.4  132.87  4938.9  133.77  4945.6  132.79
  4974.1  132.74  4988.3  131.83    4992  130.27  4997.9  130.27  5005.4  127.82
  5021.1  126.97  5021.6  126.47  5029.3  126.47  5029.8  126.97  5045.5  128.58
  5063.1  128.16  5068.1  129.15  5075.6  132.94  5085.6  133.79  5135.8  135.11
  5306.2  137.71  5396.4  137.71  5436.5  139.36  5615.4  141.63  5697.2  142.54
#Mann= 5 ,-1 , 0
  4393.3     .05       0  4807.9     .12       0  5021.1     .05       0
  5029.8     .12       0  5615.4     .07       0
Bank Sta=5021.1,5029.8
XS Rating Curve= 0 ,0
Exp/Cntr=0.3,0.1

Type RM Length L Ch R = 1 ,3880    ,299,299,299
BEGIN DESCRIPTION:
Mapping XS 6420ee24
END DESCRIPTION:
XS GIS Cut Line= 3
      2517358.41     13443955.81      2517754.27      13443533.9
      2518134.46     13442992.26
#Sta/Elev= 30
    4400  141.48  4624.5  137.96  4741.9  135.22  4794.4  133.88  4815.4  132.73
  4822.7  133.47  4836.9  133.19  4843.8  131.68  4851.1  131.02  4865.2  133.54
  4872.1  133.63  4900.4  133.46  4928.7  131.91  4942.9  132.13  4949.8  131.28
  4963.9   131.3  4980.9  130.29    4992  128.64  5000.7  128.31  5009.5  126.63
    5010  126.13  5017.7  126.13  5018.2  126.63  5021.6  128.16  5027.8   129.1
  5042.6   133.5  5050.5  134.42    5236  135.45  5444.3  139.63  5640.3  141.52
#Mann= 4 ,-1 , 0
    4400     .05       0  4741.9     .12       0  5009.5     .05       0
  5018.2     .12       0
Bank Sta=5009.5,5018.2
XS Rating Curve= 0 ,0
Exp/Cntr=0.3,0.1

Type RM Length L Ch R = 1 ,3581    ,475,475,475
BEGIN DESCRIPTION:
TRIB 1A TO ROAD CREEK 8.0
END DESCRIPTION:
XS GIS Cut Line= 3
      2517525.03     13444174.96        2517875.       13443775.
      2518674.99       13443525.
#Sta/Elev= 30
  4468.6  141.87  4830.9  136.96  4886.6  135.54  4964.5  132.21  4986.3  130.24
  4996.7   126.7  5006.1  126.32  5006.6  125.82  5014.4  125.82  5014.9  126.32
  5016.3  128.17  5031.5  131.52  5048.8  132.52    5054  133.38  5081.3  131.46
  5125.8  133.97  5209.6   133.2    5241  132.23  5272.5  127.53  5281.4  128.13
  5286.6  127.76  5293.4  130.84  5316.2  132.08    5317  132.06    5461  134.02
  5556.9  136.81  5584.1  138.28  5654.3  139.18    5751  141.53  5838.2  143.25
#Mann= 7 ,-1 , 0
  4468.6     .05       0  4830.9     .12       0  5006.1     .05       0
  5014.9     .12       0  5316.2     .05       0    5317     .12       0
    5751     .05       0
Bank Sta=5006.1,5014.9
XS Rating Curve= 0 ,0
Exp/Cntr=0.3,0.1

Type RM Length L Ch R = 1 ,3106    ,416,416,416
BEGIN DESCRIPTION:
TRIB 1A TO ROAD CREEK 7.0
END DESCRIPTION:
XS GIS Cut Line= 3
      2517924.98     13444325.03        2518275.       13443925.
      2518625.03     13443674.98
#Sta/Elev= 30
  4467.7  140.57  4570.1  139.08  4644.7  137.87  4692.8  136.39  4850.7   133.6
  4928.5  130.76  4949.4  130.63  4977.9  128.94  4995.9  126.42  5006.6  126.75
  5012.8  125.69  5021.4  125.77    5023  125.12  5023.5  124.62  5031.6  124.62
  5032.1  125.12  5048.4   126.5  5063.1  126.39  5092.6  131.41  5098.8  131.09
  5164.7  133.59  5315.1   139.6  5329.8  143.27    5336  146.46  5343.3  146.72
  5350.7  145.35  5356.9  142.31  5365.5  141.17  5392.5  140.89  5429.4  141.62
#Mann= 6 ,-1 , 0
  4467.7     .05       0  4570.1     .07       0  4692.8     .12       0
    5023     .05       0  5032.1     .12       0  5164.7     .05       0
Bank Sta=5023,5032.1
XS Rating Curve= 0 ,0
Exp/Cntr=0.3,0.1

Type RM Length L Ch R = 1 ,2690    ,609,609,609
BEGIN DESCRIPTION:
Mapping XS c71da74c
END DESCRIPTION:
XS GIS Cut Line= 3
      2517719.86     13444868.83      2518574.06      13444181.3
      2519167.81     13443613.59
#Sta/Elev= 30
  3862.7  147.83    4033  145.46    4153  144.58  4466.6  138.56  4702.1  133.49
  4729.4  132.33  4800.9  131.52  4864.9  131.62  4893.7  130.49  4959.2  129.82
  4978.4  128.04  4984.7  126.71  4995.2  124.94  4995.7  124.44  5003.9  124.44
  5004.4  124.94    5014  127.26  5028.1  129.74  5112.7  132.63  5134.1  134.51
    5141  134.65  5148.3  133.69  5225.9  136.92  5247.3  137.11  5282.5  138.41
    5327  138.92  5353.3  140.01  5424.1  139.25  5565.6  139.13  5780.7  140.84
#Mann= 7 ,-1 , 0
  3862.7     .05       0  4466.6     .07       0  4702.1     .12       0
  4984.7    .035       0  4995.2    .035       0  5004.4    .035       0
    5327     .05       0
Bank Sta=4995.2,5004.4
XS Rating Curve= 0 ,0
Exp/Cntr=0.3,0.1

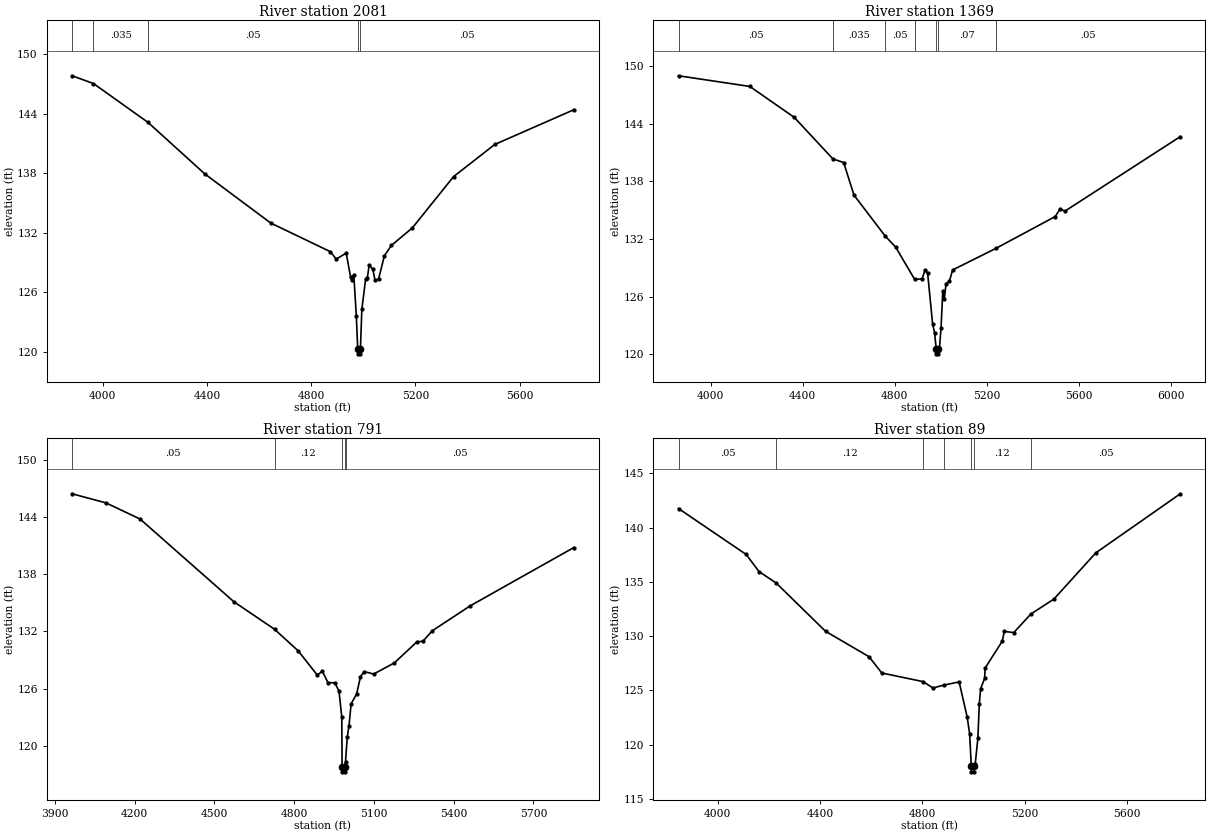
Type RM Length L Ch R = 1 ,2081    ,712,712,712
BEGIN DESCRIPTION:
Mapping XS 8297b051
END DESCRIPTION:
XS GIS Cut Line= 3
      2517870.94     13445176.08      2518855.31     13444676.09
      2519531.17     13444208.18
#Sta/Elev= 30
  3882.4  147.83  3964.5  147.05  4174.1  143.13  4391.7  137.95  4645.3  132.99
    4874  130.11  4896.4  129.36  4934.7  129.97  4951.3  127.57  4956.9  127.27
  4963.7   127.8  4973.6  123.59  4978.8  120.32  4979.3  119.82  4987.7  119.82
  4988.2  120.32  4989.3  120.32  4994.7  124.31  5009.5   127.4  5015.6  127.43
  5022.6  128.73  5036.6  128.37  5045.4  127.21  5059.1  127.37  5081.2   129.7
  5108.2  130.74  5188.6  132.51  5346.7  137.67  5504.8  140.91  5808.5  144.41
#Mann= 5 ,-1 , 0
  3882.4     .05       0  3964.5    .035       0  4174.1     .05       0
  4978.8     .05       0  4988.2     .05       0
Bank Sta=4978.8,4988.2
XS Rating Curve= 0 ,0
Exp/Cntr=0.3,0.1

Type RM Length L Ch R = 1 ,1369    ,578,578,578
BEGIN DESCRIPTION:
Mapping XS 0b64f4c1
END DESCRIPTION:
XS GIS Cut Line= 3
      2518006.38     13445686.49      2519058.44     13445275.05
      2519850.03      13444582.4
#Sta/Elev= 30
  3859.9  148.98  4169.8  147.87  4363.1  144.65  4531.3  140.32  4577.8  139.95
  4622.6  136.56  4758.9  132.28  4803.3  131.17  4886.6  127.78  4918.6  127.85
  4932.2  128.79  4942.9  128.41  4964.4  123.17  4972.9  122.26  4980.2  120.54
  4980.7  120.04  4989.3  120.04  4989.8  120.54  4994.4  120.66  5001.1  122.71
  5008.7  126.56  5015.3  125.75  5022.9  127.35  5037.1  127.57  5051.4  128.77
    5240  131.02  5497.5  134.33  5518.3   135.1  5540.2   134.9  6041.4  142.65
#Mann= 7 ,-1 , 0
  3859.9     .05       0  4531.3    .035       0  4758.9     .05       0
  4886.6     .07       0  4980.2     .05       0  4989.8     .07       0
    5240     .05       0
Bank Sta=4980.2,4989.8
XS Rating Curve= 0 ,0
Exp/Cntr=0.3,0.1

Type RM Length L Ch R = 1 ,791     ,702,702,702
BEGIN DESCRIPTION:
Mapping XS 9e8b3471
END DESCRIPTION:
XS GIS Cut Line= 3
       2518282.4     13446082.33      2519261.56     13445790.67
      2519933.45     13445243.78
#Sta/Elev= 30
  3964.3  146.44  4092.2  145.48  4220.2  143.79  4572.7  135.12  4726.2  132.22
  4815.3  129.95  4886.8  127.42  4906.1  127.82    4927  126.63  4953.2   126.6
  4968.7  125.71  4979.1  123.01  4980.3  117.76  4980.8  117.26  4989.5  117.26
    4990  117.76  4993.1  118.34  4999.9  120.95  5006.3   122.1  5014.2  124.39
    5035  125.44  5049.4  127.24  5063.8  127.78    5099  127.52  5177.2   128.7
    5262  130.91  5284.3  130.96  5319.5  132.06  5461.7  134.67  5852.3   140.8
#Mann= 5 ,-1 , 0
  3964.3     .05       0  4726.2     .12       0  4980.3     .05       0
    4990     .12       0  4993.1     .05       0
Bank Sta=4980.3,4990
XS Rating Curve= 0 ,0
Exp/Cntr=0.3,0.1

Type RM Length L Ch R = 1 ,89      ,0,0,0
BEGIN DESCRIPTION:
TRIB 1A TO ROAD CREEK 1.0
END DESCRIPTION:
XS GIS Cut Line= 4
      2518610.51     13446238.59      2519659.27     13446237.97
       2519799.9      13446193.7      2520141.76     13445509.44
#Sta/Elev= 30
  3847.6  141.75  4112.1  137.52  4162.1  135.95  4229.4  134.89  4422.1  130.45
  4592.1  128.11  4642.1  126.61  4802.7  125.82  4842.1  125.23  4885.1   125.5
  4944.3  125.79  4975.8  122.54  4985.3  120.99  4991.8  118.01  4992.3  117.51
  5001.1  117.51  5001.6  118.01  5007.2  118.26  5017.6  120.63  5022.9  123.71
  5028.2  125.15  5043.8  126.11    5046  127.07  5113.1  129.55  5120.6  130.44
  5157.8  130.33  5224.6  132.04  5314.4  133.41  5478.3  137.67  5808.7  143.11
#Mann= 7 ,-1 , 0
  3847.6     .05       0  4229.4     .12       0  4802.7     .07       0
  4885.1     .12       0  4991.8     .05       0  5001.6     .12       0
  5224.6     .05       0
Bank Sta=4991.8,5001.6
XS Rating Curve= 0 ,0
Exp/Cntr=0.3,0.1

Chan Stop Cuts=-1
Use User Specified Reach Order=0
Composite Channel Slope=5