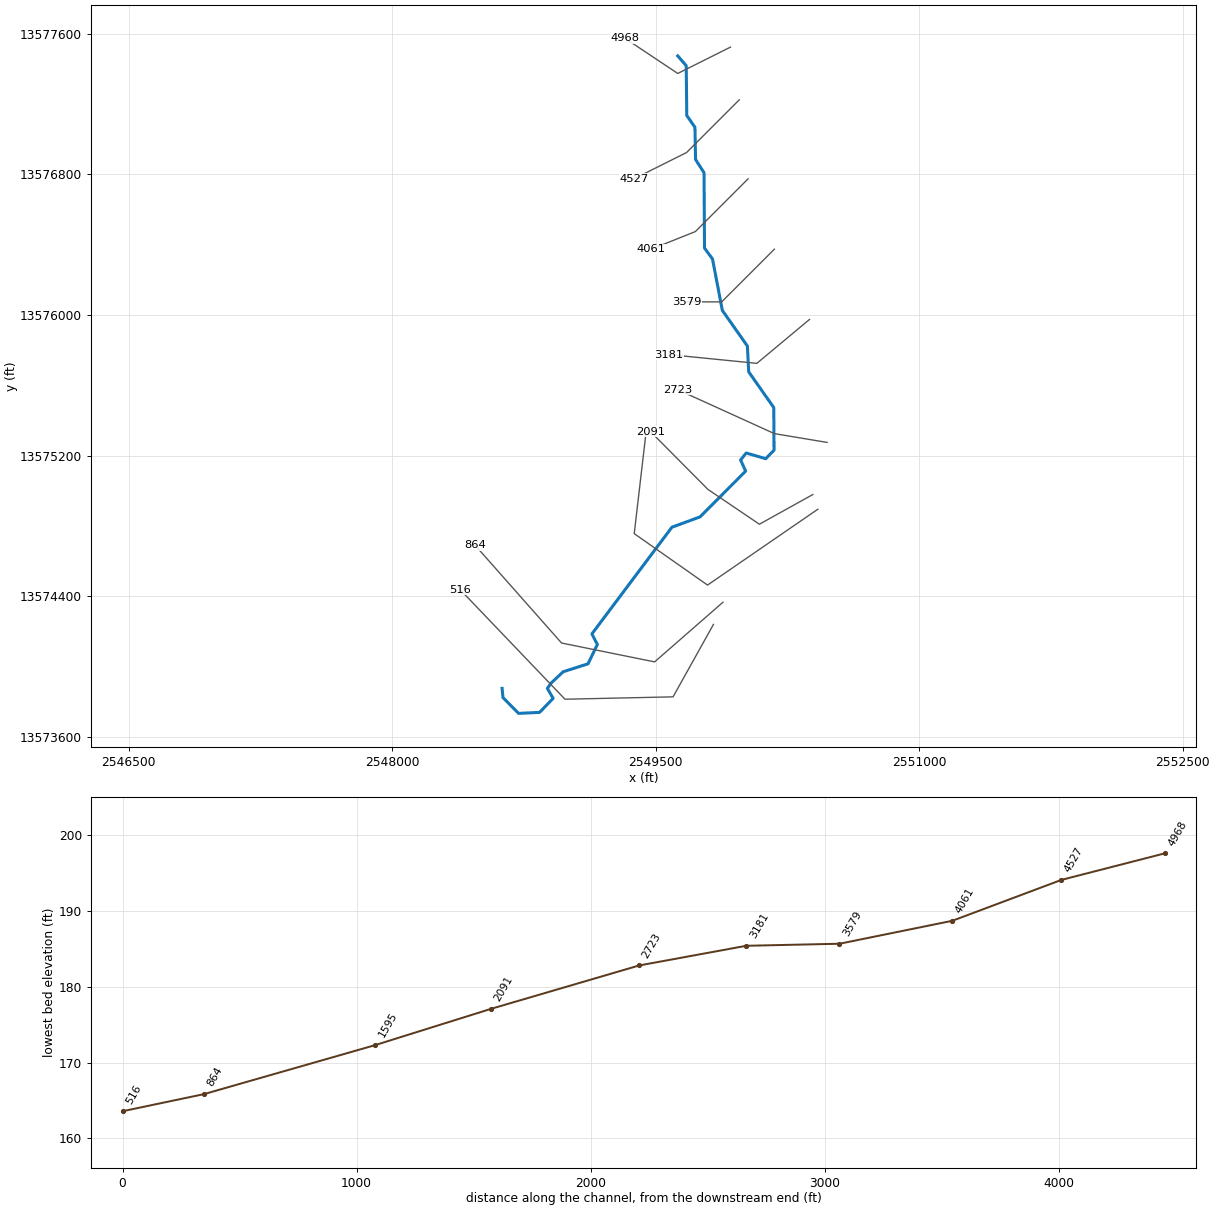
--- TRIB 1_1 TO IRISH CREEK.prj (project) ---

Proj Title=TRIB 1_1 TO IRISH CREEK Base Level Engineering
Current Plan=p01
Default Exp/Contr=0.3,0.1
English Units
Geom File=g01
Flow File=f01
Plan File=p01
BEGIN DESCRIPTION:
TRIB 1_1 TO IRISH CREEK
END DESCRIPTION:

--- TRIB 1_1 TO IRISH CREEK.p01 (plan) ---

Plan Title=Multiple Run
Short Identifier=Multiple
Geom File=g01
Flow File=f01
Subcritical Flow
K Sum by GR= 0
Std Step Tol= 0.01
Critical Tol= 0.01
Num of Std Step Trials= 20
Max Error Tol= 0.3
Flow Tol Ratio= 0.001
Split Flow NTrial= 30
Split Flow Tol= 0.02
Split Flow Ratio= 0.02
Log Output Level= 0
Friction Slope Method= 1
Unsteady Friction Slope Method= 2
Unsteady Bridges Friction Slope Method= 1
Parabolic Critical Depth
Global Vel Dist=  1 , 1 , 1
Global Log Level= 0
CheckData=True
Encroach Param= -1, 0, 0, 0
BEGIN DESCRIPTION:
Multiple Run
END DESCRIPTION:

--- TRIB 1_1 TO IRISH CREEK.f01 (steady flow) ---

Flow Title=Multiple
Number of Profiles=7
Profile Names=10-year,25-year,50-year,1pct_min,100-year,1pct_plu,500-year
River Rch & RM= TRIB 1_1 TO IRIS,Reach-1,4968
     441     691     913     585    1167    2329    1887
Boundary for River Rch & Prof#=TRIB 1_1 TO IRIS,Reach-1,1
Up Type=0
Dn Type=3
Dn Slope=0.005
Boundary for River Rch & Prof#=TRIB 1_1 TO IRIS,Reach-1,2
Up Type=0
Dn Type=3
Dn Slope=0.005
Boundary for River Rch & Prof#=TRIB 1_1 TO IRIS,Reach-1,3
Up Type=0
Dn Type=3
Dn Slope=0.005
Boundary for River Rch & Prof#=TRIB 1_1 TO IRIS,Reach-1,4
Up Type=0
Dn Type=3
Dn Slope=0.005
Boundary for River Rch & Prof#=TRIB 1_1 TO IRIS,Reach-1,5
Up Type=0
Dn Type=3
Dn Slope=0.005
Boundary for River Rch & Prof#=TRIB 1_1 TO IRIS,Reach-1,6
Up Type=0
Dn Type=3
Dn Slope=0.005
Boundary for River Rch & Prof#=TRIB 1_1 TO IRIS,Reach-1,7
Up Type=0
Dn Type=3
Dn Slope=0.005

--- TRIB 1_1 TO IRISH CREEK.g01 (geometry) ---

Geom Title=Existing Conditions

River Reach=TRIB 1_1 TO IRIS,Reach-1
Reach XY= 30
      2549625.00     13577475.00      2549673.11     13577419.22
      2549676.22     13577135.50      2549722.74     13577069.06
      2549726.22     13576885.51      2549774.48     13576809.78
      2549777.26     13576380.94      2549822.73     13576319.06
      2549878.62     13576026.50      2550021.24     13575823.44
      2550028.76     13575676.56      2550171.45     13575473.53
      2550172.95     13575230.45      2550125.33     13575182.25
      2550014.62     13575214.79      2549982.47     13575175.28
      2550011.35     13575111.67      2549751.87     13574851.18
      2549591.46     13574792.13      2549136.24     13574185.00
      2549167.23     13574125.09      2549114.41     13574014.95
      2548972.55     13573969.47      2548904.07     13573905.08
      2548882.56     13573875.01      2548915.70     13573818.31
      2548838.36     13573738.34      2548718.81     13573732.74
      2548630.30     13573822.46      2548625.00     13573875.00

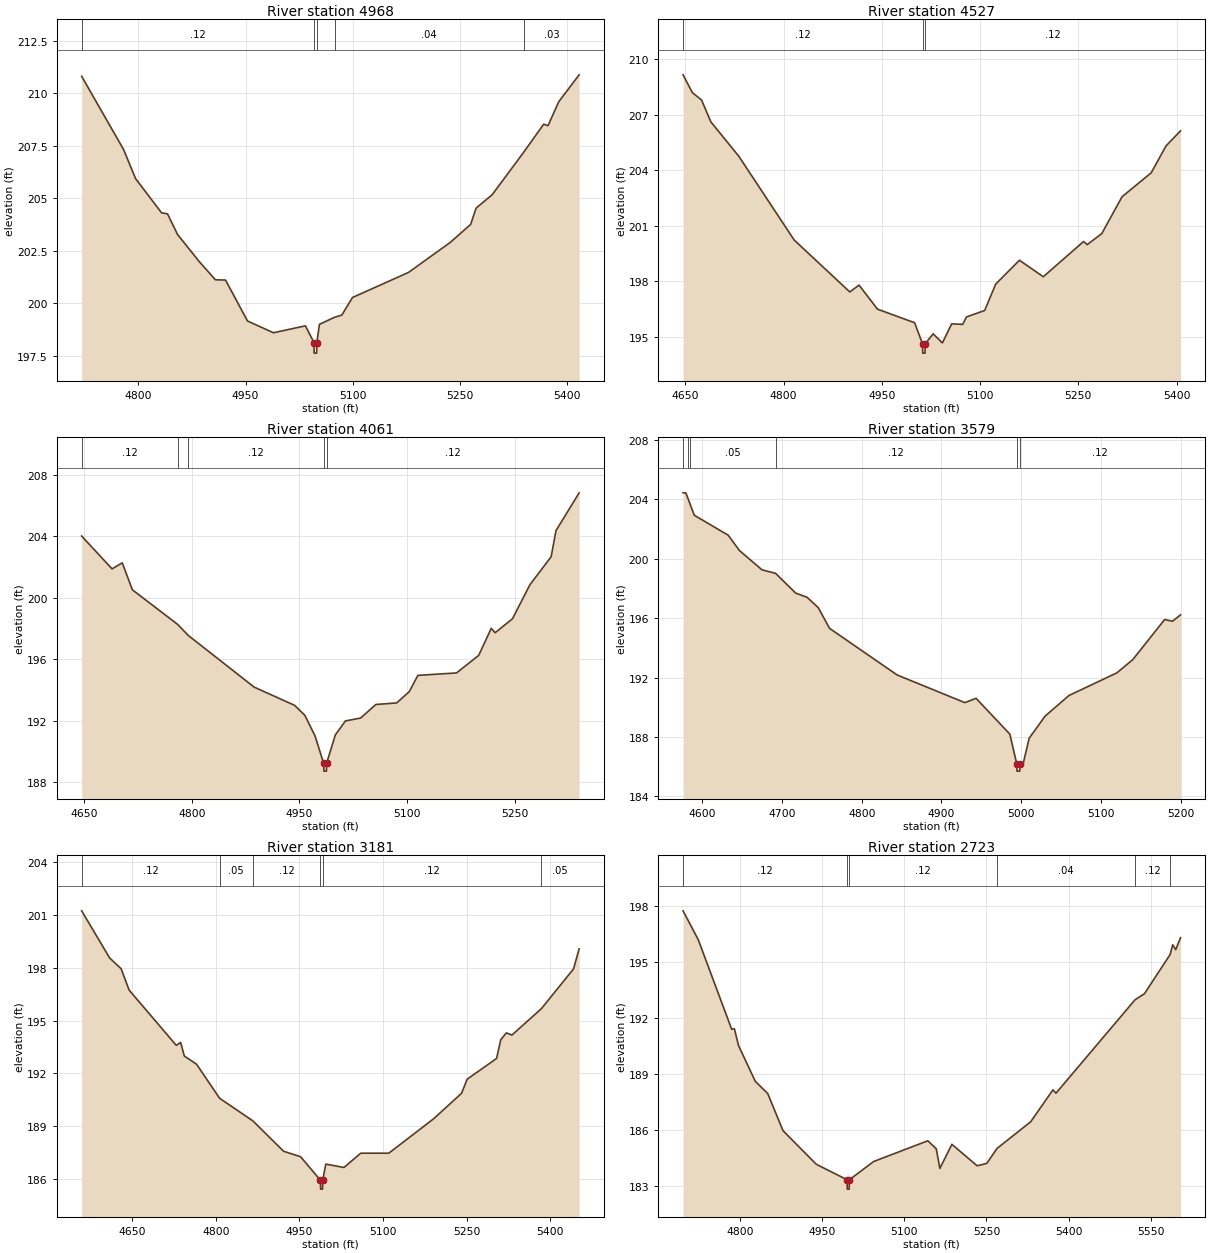
Type RM Length L Ch R = 1,4968,441,441,441
BEGIN DESCRIPTION:
TRIB 1_1 TO IRISH CREEK 7.0
END DESCRIPTION:
XS GIS Cut Line= 3
      2549924.96     13577524.98      2549625.00     13577375.00
      2549325.02     13577574.99
#Sta/Elev= 30
  4720.8  210.81  4779.5  207.32  4796.2  205.94  4832.6  204.31  4840.9  204.26
  4854.9  203.28  4885.7  201.97  4908.0  201.12  4922.0  201.11  4952.8  199.16
  4989.1  198.60  5033.8  198.93  5045.8  198.13  5046.0  197.63  5049.5  197.63
  5049.8  198.13  5053.4  199.00  5074.8  199.34  5084.7  199.44  5099.7  200.28
  5177.9  201.47  5236.4  202.90  5265.0  203.76  5272.5  204.53  5295.0  205.17
  5339.3  207.20  5367.1  208.53  5373.2  208.46  5388.2  209.60  5416.7  210.88
#Mann=5,-1,0
  4720.8    0.12       0  5045.8    0.05       0  5049.8    0.12       0
  5074.8    0.04       0  5339.3    0.03       0
Bank Sta=5045.8,5049.8
Exp/Cntr=0.3,0.1

Type RM Length L Ch R = 1,4527,466,466,466
BEGIN DESCRIPTION:
TRIB 1_1 TO IRISH CREEK 6.0
END DESCRIPTION:
XS GIS Cut Line= 3
      2549975.03     13577225.03      2549675.00     13576925.00
      2549375.01     13576775.01
#Sta/Elev= 30
  4646.4  209.14  4660.6  208.18  4674.7  207.78  4688.9  206.60  4731.3  204.76
  4816.1  200.23  4901.0  197.43  4915.1  197.80  4943.4  196.50  5000.0  195.77
  5012.1  194.63  5012.4  194.13  5015.9  194.13  5016.1  194.63  5028.3  195.17
  5042.4  194.68  5056.6  195.71  5073.5  195.68  5079.1  196.08  5107.0  196.43
  5123.8  197.85  5160.1  199.14  5196.5  198.25  5258.0  200.15  5263.6  199.98
  5285.9  200.58  5316.7  202.56  5361.4  203.86  5383.8  205.30  5406.1  206.12
#Mann=3,-1,0
  4646.4    0.12       0  5012.1    0.05       0  5016.1    0.12       0
Bank Sta=5012.1,5016.1
Exp/Cntr=0.3,0.1

Type RM Length L Ch R = 1,4061,482,482,482
BEGIN DESCRIPTION:
TRIB 1_1 TO IRISH CREEK 5.0
END DESCRIPTION:
XS GIS Cut Line= 3
      2550025.01     13576775.01      2549725.00     13576475.00
      2549475.04     13576375.01
#Sta/Elev= 30
  4646.4  204.00  4688.8  201.87  4703.0  202.26  4717.1  200.51  4780.3  198.26
  4794.9  197.55  4886.8  194.19  4943.4  193.00  4957.5  192.36  4971.7  191.02
  4983.8  189.23  4984.1  188.73  4987.6  188.73  4987.8  189.23  5000.0  191.08
  5014.1  191.99  5035.3  192.18  5056.5  193.06  5085.5  193.16  5103.0  193.89
  5115.1  194.95  5169.0  195.11  5199.9  196.25  5217.4  198.01  5222.8  197.72
  5247.0  198.63  5271.3  200.84  5300.9  202.66  5307.6  204.35  5339.9  206.81
#Mann=5,-1,0
  4646.4    0.12       0  4780.3    0.05       0  4794.9    0.12       0
  4983.8    0.05       0  4987.8    0.12       0
Bank Sta=4983.8,4987.8
Exp/Cntr=0.3,0.1

Type RM Length L Ch R = 1,3579,398,398,398
BEGIN DESCRIPTION:
TRIB 1_1 TO IRISH CREEK 4.0
END DESCRIPTION:
XS GIS Cut Line= 3
      2550175.00     13576375.00      2549875.00     13576075.00
      2549674.96     13576075.00
#Sta/Elev= 30
  4575.7  204.43  4579.2  204.43  4582.3  203.99  4584.3  203.70  4589.8  202.92
  4632.3  201.58  4646.4  200.55  4674.7  199.25  4691.8  199.01  4717.1  197.68
  4731.3  197.40  4745.4  196.70  4759.5  195.31  4844.4  192.17  4929.3  190.31
  4943.4  190.60  4985.8  188.19  4994.4  186.20  4994.7  185.70  4998.2  185.70
  4998.4  186.20  5002.5  186.20  5010.0  187.91  5030.0  189.40  5060.0  190.79
  5120.0  192.31  5140.0  193.20  5180.0  195.90  5190.0  195.79  5200.0  196.22
#Mann=6,-1,0
  4575.7    0.05       0  4582.3    0.12       0  4584.3    0.05       0
  4691.8    0.12       0  4994.4    0.05       0  4998.4    0.12       0
Bank Sta=4994.4,4998.4
Exp/Cntr=0.3,0.1

Type RM Length L Ch R = 1,3181,458,458,458
BEGIN DESCRIPTION:
TRIB 1_1 TO IRISH CREEK 3.0
END DESCRIPTION:
XS GIS Cut Line= 3
      2550374.99     13575974.99      2550075.00     13575725.00
      2549574.99     13575775.00
#Sta/Elev= 30
  4559.0  201.23  4609.1  198.56  4629.9  197.94  4644.2  196.73  4728.9  193.59
  4736.7  193.76  4743.2  192.99  4765.3  192.52  4806.6  190.59  4866.5  189.30
  4921.5  187.58  4952.0  187.27  4987.7  185.93  4987.9  185.43  4991.4  185.43
  4991.7  185.93  4997.2  186.85  5029.9  186.66  5060.0  187.47  5110.3  187.47
  5190.7  189.42  5240.9  190.87  5251.0  191.67  5303.8  192.85  5311.3  193.91
  5321.3  194.30  5331.4  194.18  5384.1  195.67  5441.9  197.93  5452.0  199.07
#Mann=6,-1,0
  4559.0    0.12       0  4806.6    0.05       0  4866.5    0.12       0
  4987.7    0.05       0  4991.7    0.12       0  5384.1    0.05       0
Bank Sta=4987.7,4991.7
Exp/Cntr=0.3,0.1

Type RM Length L Ch R = 1,2723,632,632,632
BEGIN DESCRIPTION:
TRIB 1_1 TO IRISH CREEK 2.0
END DESCRIPTION:
XS GIS Cut Line= 3
      2550474.97     13575275.00      2550175.00     13575325.00
      2549624.96     13575575.02
#Sta/Elev= 30
  4696.0  197.74  4723.8  196.19  4784.7  191.40  4789.7  191.42  4797.3  190.52
  4827.8  188.61  4850.6  187.95  4878.5  185.96  4939.3  184.16  4995.6  183.33
  4995.8  182.83  4999.3  182.83  4999.6  183.33  5044.0  184.31  5142.9  185.42
  5158.3  184.99  5164.9  183.94  5186.8  185.23  5233.0  184.08  5250.6  184.21
  5269.3  185.01  5330.7  186.44  5371.4  188.15  5376.9  187.97  5521.1  192.97
  5538.4  193.30  5585.3  195.40  5590.0  195.92  5595.5  195.66  5604.3  196.30
#Mann=6,-1,0
  4696.0    0.12       0  4995.6    0.05       0  4999.6    0.12       0
  5269.3    0.04       0  5521.1    0.12       0  5585.3    0.05       0
Bank Sta=4995.6,4999.6
Exp/Cntr=0.3,0.1

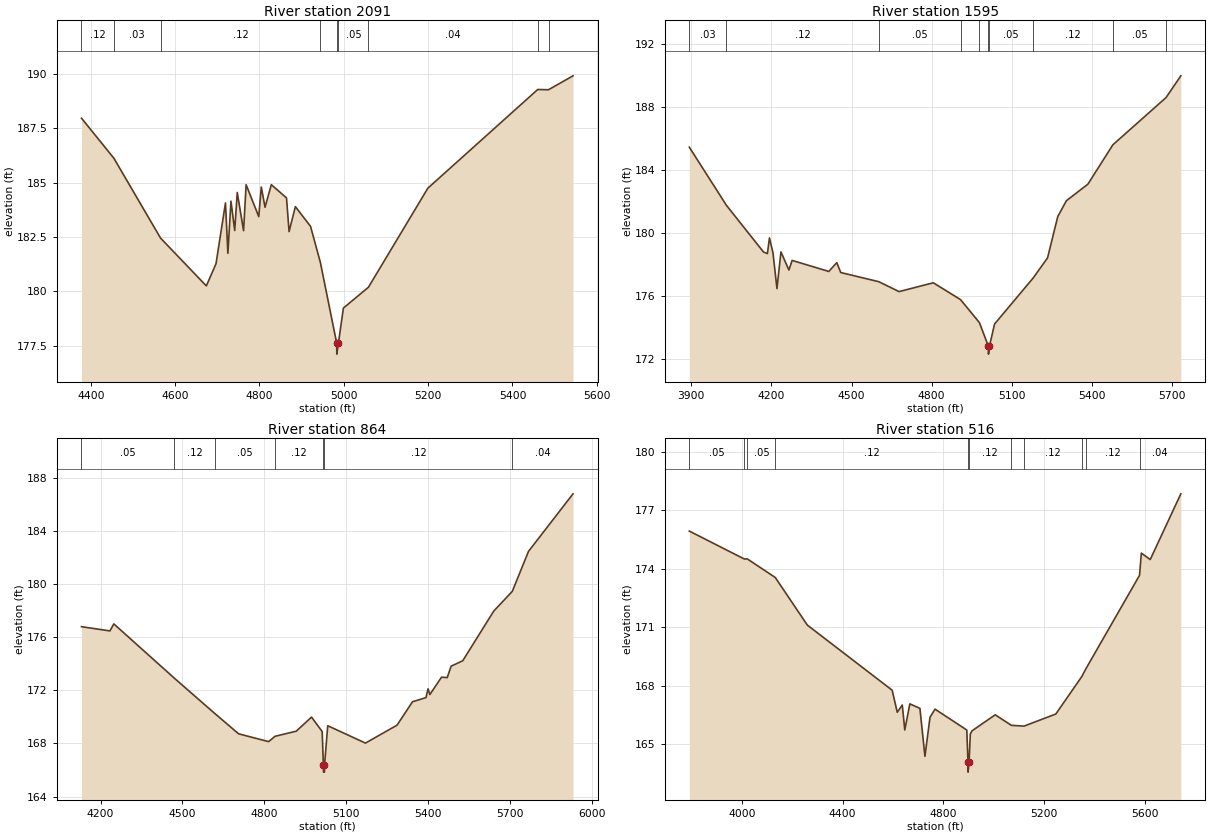
Type RM Length L Ch R = 1,2091,496,496,496
BEGIN DESCRIPTION:
TRIB 1_1 TO IRISH CREEK 1.0
END DESCRIPTION:
XS GIS Cut Line= 4
      2550393.78     13574978.38      2550089.52     13574809.35
      2549796.56     13575007.66      2549469.90     13575336.58
#Sta/Elev= 30
  4378.2  187.97  4454.9  186.13  4565.7  182.45  4674.2  180.25  4697.1  181.27
  4719.6  184.07  4725.3  181.75  4732.6  184.15  4741.5  182.80  4747.5  184.55
  4762.5  182.79  4768.5  184.91  4798.5  183.44  4804.5  184.80  4813.4  183.87
  4828.3  184.91  4864.3  184.30  4870.4  182.75  4885.3  183.90  4921.3  182.99
  4944.6  181.33  4983.3  177.61  4983.6  177.11  4987.3  177.61  4999.2  179.23
  5058.6  180.19  5199.5  184.75  5459.9  189.29  5485.5  189.28  5543.6  189.92
#Mann=9,-1,0
  4378.2    0.12       0  4454.9    0.03       0  4565.7    0.12       0
  4944.6    0.05       0  4983.3    0.05       0  4987.3    0.05       0
  5058.6    0.04       0  5459.9    0.05       0  5485.5    0.12       0
Bank Sta=4983.3,4987.3
Exp/Cntr=0.3,0.1

Type RM Length L Ch R = 1,1595,731,731,731
BEGIN DESCRIPTION:
LGII3712
END DESCRIPTION:
XS GIS Cut Line= 4
      2550422.29     13574894.70      2549794.42     13574463.04
      2549377.12     13574755.79      2549443.15     13575320.75
#Sta/Elev= 30
  3892.6  185.45  4031.5  181.76  4170.1  178.80  4185.0  178.69  4192.7  179.69
  4205.9  178.74  4220.8  176.47  4235.7  178.80  4265.5  177.65  4277.6  178.26
  4415.0  177.56  4444.8  178.12  4459.7  177.49  4601.9  176.91  4678.1  176.28
  4806.2  176.84  4908.3  175.77  4978.9  174.31  5012.5  172.81  5012.8  172.31
  5016.5  172.81  5035.5  174.22  5180.0  177.14  5234.0  178.42  5272.2  181.04
  5304.5  182.05  5385.0  183.10  5478.6  185.60  5677.7  188.60  5733.1  189.98
#Mann=10,-1,0
  3892.6    0.03       0  4031.5    0.12       0  4601.9    0.05       0
  4908.3    0.12       0  4978.9    0.05       0  5012.5    0.05       0
  5016.5    0.05       0  5180.0    0.12       0  5478.6    0.05       0
  5677.7    0.12       0
Bank Sta=5012.5,5016.5
Exp/Cntr=0.3,0.1

Type RM Length L Ch R = 1,864,348,348,348
BEGIN DESCRIPTION:
LGII3711
END DESCRIPTION:
XS GIS Cut Line= 4
      2549882.17     13574365.38      2549493.35     13574025.77
      2548963.60     13574133.16      2548470.50     13574690.58
#Sta/Elev= 30
  4130.0  176.81  4234.2  176.49  4248.5  177.02  4470.0  172.93  4619.1  170.25
  4705.8  168.73  4815.7  168.14  4839.0  168.54  4917.1  168.93  4972.9  169.99
  5011.9  168.90  5016.4  166.34  5016.7  165.84  5020.2  165.84  5020.4  166.34
  5032.3  169.34  5170.5  168.03  5286.1  169.38  5343.0  171.15  5392.3  171.46
  5399.8  172.12  5406.5  171.69  5449.2  173.00  5470.1  172.97  5484.3  173.83
  5527.0  174.24  5640.7  177.99  5708.4  179.47  5767.9  182.49  5931.0  186.83
#Mann=7,-1,0
  4130.0    0.05       0  4470.0    0.12       0  4619.1    0.05       0
  4839.0    0.12       0  5016.4    0.05       0  5020.4    0.12       0
  5708.4    0.04       0
Bank Sta=5016.4,5020.4
Exp/Cntr=0.3,0.1

Type RM Length L Ch R = 1,516,0,0,0
BEGIN DESCRIPTION:
LGII3711a
END DESCRIPTION:
XS GIS Cut Line= 4
      2549828.11     13574239.19      2549598.25     13573826.81
      2548983.04     13573813.29      2548385.82     13574437.54
#Sta/Elev= 30
  3791.8  175.94  4010.0  174.51  4022.4  174.51  4133.1  173.56  4260.3  171.12
  4597.2  167.78  4617.3  166.65  4637.3  167.02  4647.3  165.74  4667.3  167.08
  4707.3  166.85  4727.3  164.39  4747.3  166.39  4767.3  166.81  4893.4  165.74
  4898.3  164.08  4898.5  163.58  4902.3  164.08  4907.5  165.54  4914.4  165.70
  5006.3  166.52  5070.3  165.98  5120.8  165.94  5246.9  166.56  5350.0  168.48
  5365.9  168.87  5579.2  173.67  5586.5  174.81  5621.7  174.48  5743.2  177.85
#Mann=11,-1,0
  3791.8    0.05       0  4010.0    0.12       0  4022.4    0.05       0
  4133.1    0.12       0  4898.3    0.05       0  4902.3    0.12       0
  5070.3    0.05       0  5120.8    0.12       0  5350.0    0.05       0
  5365.9    0.12       0  5579.2    0.04       0
Bank Sta=4898.3,4902.3
Exp/Cntr=0.3,0.1

Chan Stop Cuts=-1