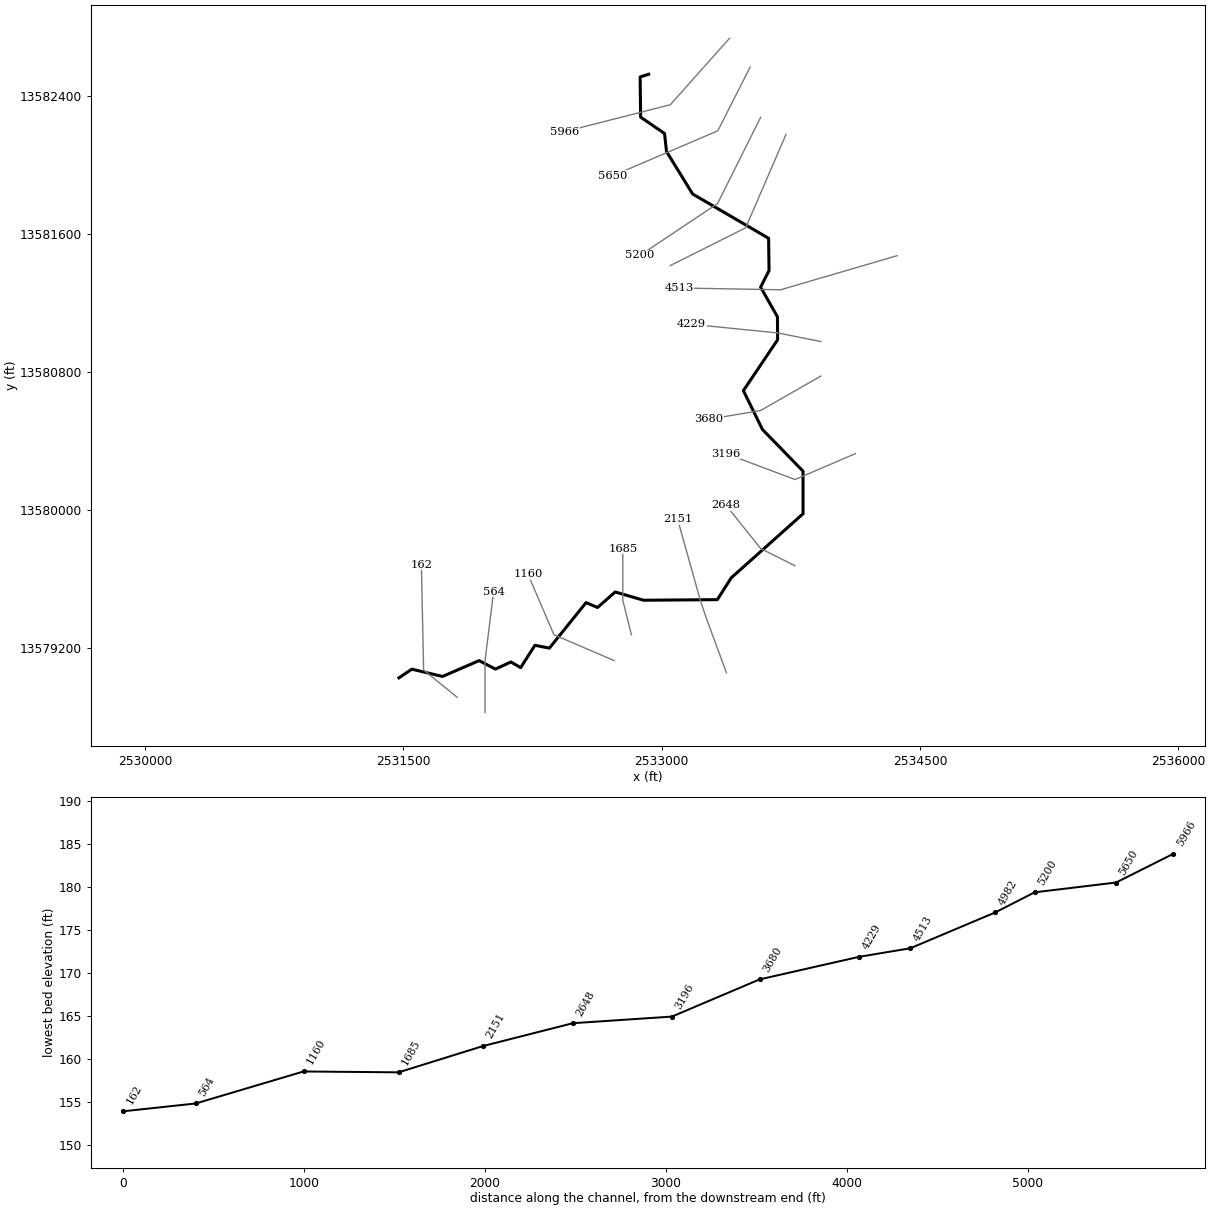
--- TRIB 1_1 TO OAXLEY BRANCH.prj (project) ---

Proj Title=TRIB 1_1 TO OAXLEY BRANCH Base Level Engineering
Current Plan=p01
Default Exp/Contr=0.3,0.1
English Units
Geom File=g01
Flow File=f01
Plan File=p01
BEGIN DESCRIPTION:
TRIB 1_1 TO OAXLEY BRANCH
END DESCRIPTION:

--- TRIB 1_1 TO OAXLEY BRANCH.p01 (plan) ---

Plan Title=Multiple Run
Short Identifier=Multiple
Geom File=g01
Flow File=f01
Subcritical Flow
K Sum by GR= 0
Std Step Tol= 0.01
Critical Tol= 0.01
Num of Std Step Trials= 20
Max Error Tol= 0.3
Flow Tol Ratio= 0.001
Split Flow NTrial= 30
Split Flow Tol= 0.02
Split Flow Ratio= 0.02
Log Output Level= 0
Friction Slope Method= 1
Unsteady Friction Slope Method= 2
Unsteady Bridges Friction Slope Method= 1
Parabolic Critical Depth
Global Vel Dist=  1 , 1 , 1
Global Log Level= 0
CheckData=True
Encroach Param= -1, 0, 0, 0
BEGIN DESCRIPTION:
Multiple Run
END DESCRIPTION:

--- TRIB 1_1 TO OAXLEY BRANCH.f01 (steady flow) ---

Flow Title=Multiple
Number of Profiles=7
Profile Names=10-year,25-year,50-year,1pct_min,100-year,1pct_plu,500-year
River Rch & RM= TRIB 1_1 TO OAXL,Reach-1,5966
     520     833    1115     725    1447    2886    2407
River Rch & RM= TRIB 1_1 TO OAXL,Reach-1,5650
     584     941    1265     826    1647    3287    2761
River Rch & RM= TRIB 1_1 TO OAXL,Reach-1,4513
     815    1339    1822    1202    2397    4784    4108
River Rch & RM= TRIB 1_1 TO OAXL,Reach-1,1160
     835    1372    1867    1231    2456    4900    4206
Boundary for River Rch & Prof#=TRIB 1_1 TO OAXL,Reach-1,1
Up Type=0
Dn Type=3
Dn Slope=0.005
Boundary for River Rch & Prof#=TRIB 1_1 TO OAXL,Reach-1,2
Up Type=0
Dn Type=3
Dn Slope=0.005
Boundary for River Rch & Prof#=TRIB 1_1 TO OAXL,Reach-1,3
Up Type=0
Dn Type=3
Dn Slope=0.005
Boundary for River Rch & Prof#=TRIB 1_1 TO OAXL,Reach-1,4
Up Type=0
Dn Type=3
Dn Slope=0.005
Boundary for River Rch & Prof#=TRIB 1_1 TO OAXL,Reach-1,5
Up Type=0
Dn Type=3
Dn Slope=0.005
Boundary for River Rch & Prof#=TRIB 1_1 TO OAXL,Reach-1,6
Up Type=0
Dn Type=3
Dn Slope=0.005
Boundary for River Rch & Prof#=TRIB 1_1 TO OAXL,Reach-1,7
Up Type=0
Dn Type=3
Dn Slope=0.005

--- TRIB 1_1 TO OAXLEY BRANCH.g01 (geometry) ---

Geom Title=Existing Conditions

River Reach=TRIB 1_1 TO OAXL,Reach-1
Reach XY= 30
      2532925.00     13582525.00      2532875.61     13582509.39
      2532878.45     13582276.25      2533017.25     13582181.45
      2533028.83     13582076.59      2533180.61     13581830.59
      2533621.60     13581573.77      2533624.13     13581386.94
      2533575.03     13581290.38      2533672.77     13581119.07
      2533673.96     13580985.44      2533475.02     13580690.41
      2533585.76     13580465.32      2533821.46     13580223.54
      2533821.47     13579976.45      2533404.62     13579605.16
      2533323.75     13579478.45      2532895.03     13579475.07
      2532730.89     13579523.02      2532628.33     13579433.02
      2532561.67     13579461.35      2532348.70     13579197.37
      2532264.69     13579213.88      2532181.95     13579084.18
      2532125.10     13579117.16      2532035.70     13579075.83
      2531940.40     13579124.90      2531728.30     13579033.08
      2531549.91     13579075.27      2531475.00     13579025.00

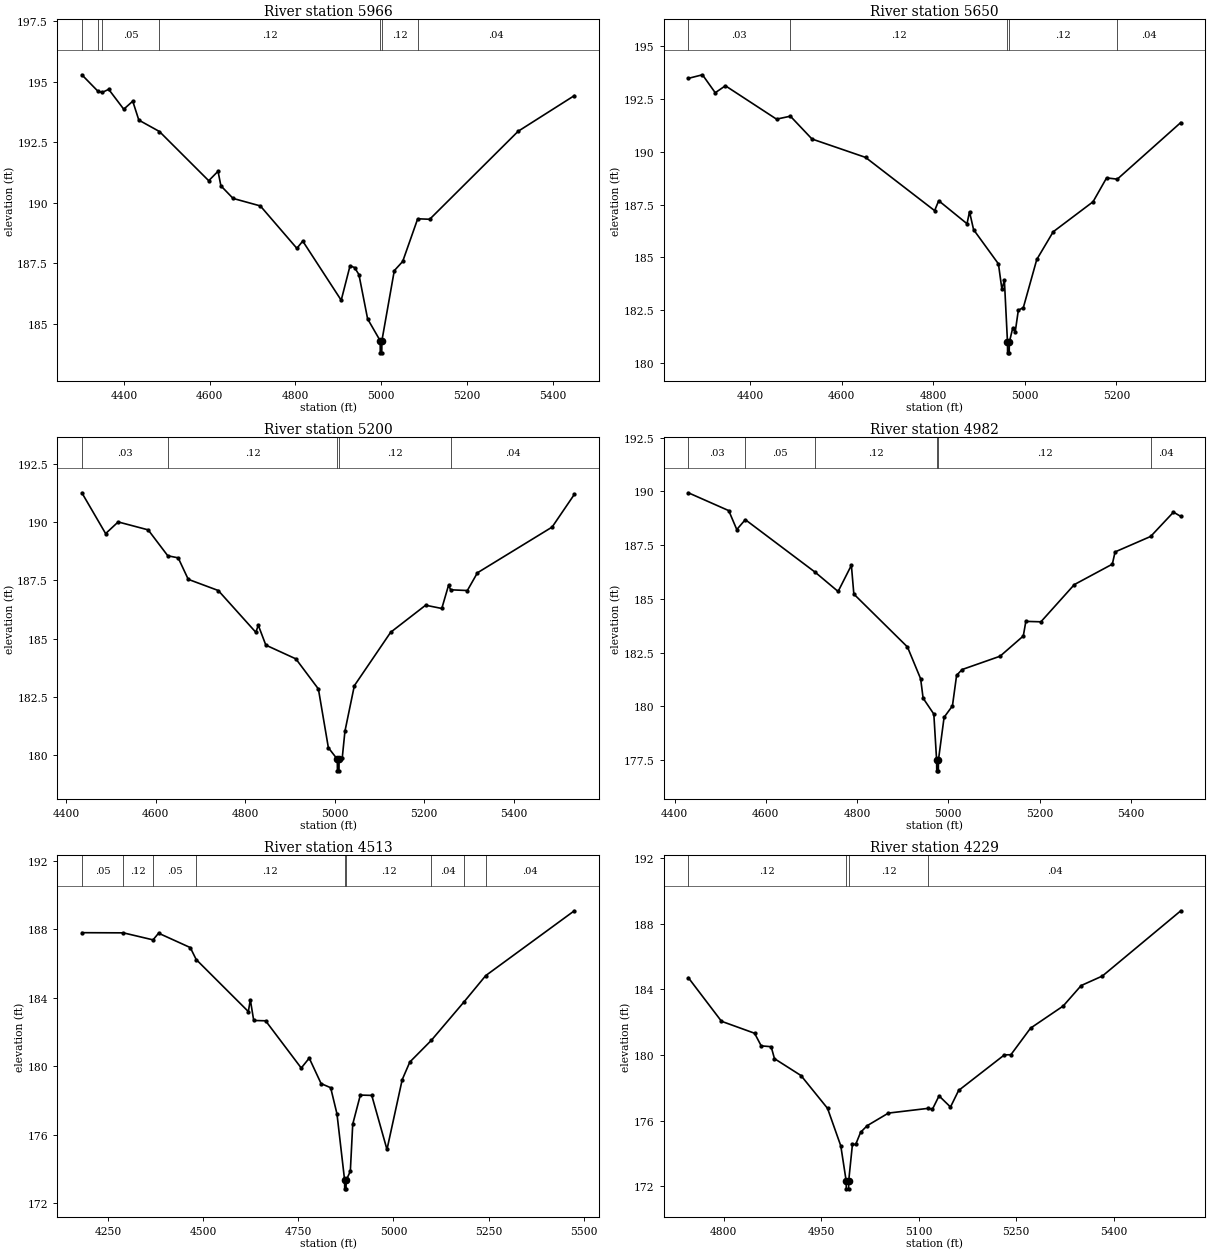
Type RM Length L Ch R = 1,5966,316,316,316
BEGIN DESCRIPTION:
Mapping XS 0fc42ef4
END DESCRIPTION:
XS GIS Cut Line= 3
      2533394.48     13582733.57      2533050.74     13582348.16
      2532438.06     13582192.40
#Sta/Elev= 30
  4301.8  195.28  4339.4  194.60  4349.0  194.55  4364.4  194.68  4399.5  193.86
  4420.5  194.19  4434.7  193.41  4482.7  192.94  4597.7  190.91  4619.4  191.30
  4626.1  190.70  4654.5  190.18  4718.1  189.87  4803.3  188.12  4817.0  188.42
  4906.7  185.98  4927.3  187.40  4937.7  187.33  4948.0  187.04  4968.3  185.21
  4997.6  184.31  4997.8  183.81  5001.3  183.81  5001.6  184.31  5030.5  187.20
  5050.1  187.58  5085.1  189.34  5113.1  189.32  5319.4  192.95  5450.4  194.42
#Mann=7,-1,0
  4301.8    0.05       0  4339.4    0.12       0  4349.0    0.05       0
  4482.7    0.12       0  4997.6    0.05       0  5001.6    0.12       0
  5085.1    0.04       0
Bank Sta=4997.6,5001.6
Exp/Cntr=0.3,0.1

Type RM Length L Ch R = 1,5650,450,450,450
BEGIN DESCRIPTION:
Mapping XS 6c85049a
END DESCRIPTION:
XS GIS Cut Line= 3
      2533514.28     13582566.91      2533326.78     13582197.12
      2532718.70     13581937.25
#Sta/Elev= 30
  4264.6  193.47  4295.5  193.64  4323.4  192.79  4345.6  193.12  4457.3  191.54
  4487.6  191.68  4534.8  190.60  4651.8  189.73  4802.7  187.21  4811.6  187.68
  4873.5  186.59  4878.9  187.16  4887.8  186.31  4942.1  184.69  4949.7  183.49
  4955.1  183.92  4961.9  180.98  4962.1  180.48  4965.6  180.48  4965.9  180.98
  4973.3  181.65  4978.7  181.46  4985.6  182.50  4996.5  182.62  5025.9  184.90
  5061.8  186.21  5148.8  187.63  5178.4  188.76  5201.8  188.70  5340.5  191.38
#Mann=5,-1,0
  4264.6    0.03       0  4487.6    0.12       0  4961.9    0.05       0
  4965.9    0.12       0  5201.8    0.04       0
Bank Sta=4961.9,4965.9
Exp/Cntr=0.3,0.1

Type RM Length L Ch R = 1,5200,218,218,218
BEGIN DESCRIPTION:
TRIB 1_1 TO OAKLEY BRANCH 10.0
END DESCRIPTION:
XS GIS Cut Line= 3
      2533575.00     13582275.00      2533325.00     13581775.00
      2532874.96     13581474.97
#Sta/Elev= 30
  4435.3  191.26  4488.4  189.51  4516.4  190.01  4583.4  189.67  4627.2  188.56
  4650.5  188.47  4672.9  187.55  4740.0  187.07  4823.8  185.28  4829.4  185.58
  4846.2  184.73  4913.3  184.14  4963.6  182.85  4985.9  180.33  5005.8  179.84
  5006.1  179.34  5009.6  179.34  5009.8  179.84  5016.9  179.90  5022.9  181.04
  5043.9  182.99  5125.0  185.28  5203.1  186.44  5239.2  186.30  5254.2  187.29
  5259.2  187.10  5296.3  187.07  5318.8  187.83  5485.6  189.79  5535.2  191.19
#Mann=5,-1,0
  4435.3    0.03       0  4627.2    0.12       0  5005.8    0.05       0
  5009.8    0.12       0  5259.2    0.04       0
Bank Sta=5005.8,5009.8
Exp/Cntr=0.3,0.1

Type RM Length L Ch R = 1,4982,469,469,469
BEGIN DESCRIPTION:
Mapping XS 49ec1454
END DESCRIPTION:
XS GIS Cut Line= 3
      2533722.64     13582176.33      2533488.24     13581634.62
      2533050.73     13581415.86
#Sta/Elev= 30
  4430.1  189.93  4518.7  189.10  4536.3  188.22  4555.0  188.68  4707.9  186.24
  4758.4  185.34  4787.5  186.56  4792.9  185.22  4910.4  182.76  4939.3  181.28
  4944.7  180.38  4968.2  179.64  4974.3  177.50  4974.6  177.00  4978.1  177.00
  4978.3  177.50  4990.7  179.49  5009.0  180.02  5018.1  181.44  5030.1  181.71
  5113.4  182.33  5164.3  183.27  5169.9  183.95  5202.9  183.93  5276.1  185.66
  5359.4  186.61  5365.5  187.18  5443.5  187.90  5493.5  189.03  5509.5  188.83
#Mann=6,-1,0
  4430.1    0.03       0  4555.0    0.05       0  4707.9    0.12       0
  4974.3    0.05       0  4978.3    0.12       0  5443.5    0.04       0
Bank Sta=4974.3,4978.3
Exp/Cntr=0.3,0.1

Type RM Length L Ch R = 1,4513,284,284,284
BEGIN DESCRIPTION:
Mapping XS 923d21d2
END DESCRIPTION:
XS GIS Cut Line= 3
      2534368.48     13581473.17      2533691.37     13581275.25
      2533102.81     13581285.66
#Sta/Elev= 30
  4181.3  187.81  4290.4  187.80  4368.4  187.39  4382.9  187.78  4466.2  186.94
  4481.8  186.24  4618.8  183.20  4624.0  183.89  4632.9  182.68  4664.2  182.66
  4757.8  179.90  4778.8  180.48  4810.0  178.99  4835.1  178.75  4851.7  177.22
  4871.8  173.34  4872.0  172.84  4875.5  172.84  4875.8  173.34  4886.8  173.87
  4893.1  176.62  4913.1  178.32  4943.1  178.30  4983.1  175.14  5023.1  179.22
  5043.1  180.25  5099.7  181.52  5186.1  183.78  5242.5  185.30  5475.4  189.09
#Mann=9,-1,0
  4181.3    0.05       0  4290.4    0.12       0  4368.4    0.05       0
  4481.8    0.12       0  4871.8    0.05       0  4875.8    0.12       0
  5099.7    0.04       0  5186.1    0.12       0  5242.5    0.04       0
Bank Sta=4871.8,4875.8
Exp/Cntr=0.3,0.1

Type RM Length L Ch R = 1,4229,549,549,549
BEGIN DESCRIPTION:
TRIB 1_1 TO OAKLEY BRANCH 8.0
END DESCRIPTION:
XS GIS Cut Line= 3
      2533924.97     13580975.01      2533675.00     13581025.00
      2533175.01     13581075.00
#Sta/Elev= 30
  4745.6  184.72  4796.6  182.06  4847.5  181.33  4857.7  180.56  4873.0  180.51
  4878.1  179.78  4918.9  178.75  4959.7  176.75  4980.1  174.46  4988.3  172.34
  4988.6  171.84  4992.1  171.84  4992.3  172.34  4998.0  174.55  5003.0  174.55
  5010.6  175.29  5020.6  175.69  5053.3  176.46  5114.6  176.75  5121.1  176.70
  5131.2  177.51  5148.8  176.83  5161.3  177.84  5231.7  180.01  5241.7  180.02
  5271.9  181.64  5322.1  182.99  5349.8  184.24  5382.4  184.82  5503.0  188.80
#Mann=4,-1,0
  4745.6    0.12       0  4988.3    0.05       0  4992.3    0.12       0
  5114.6    0.04       0
Bank Sta=4988.3,4992.3
Exp/Cntr=0.3,0.1

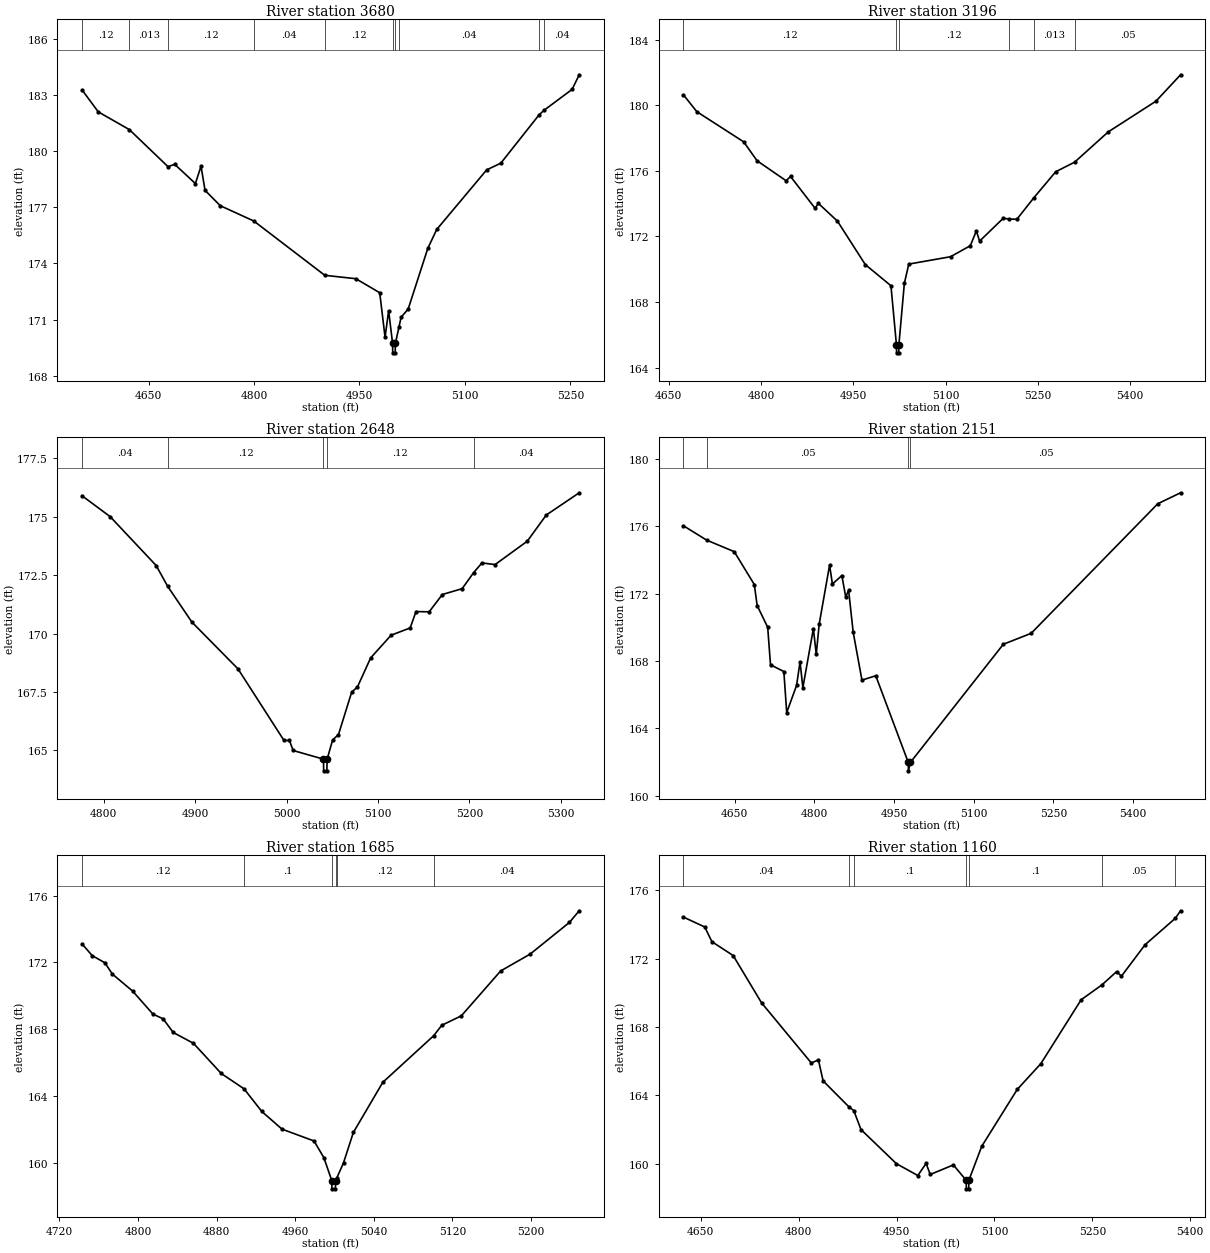
Type RM Length L Ch R = 1,3680,484,484,484
BEGIN DESCRIPTION:
TRIB 1_1 TO OAKLEY BRANCH 7.0
END DESCRIPTION:
XS GIS Cut Line= 3
      2533924.99     13580775.00      2533575.00     13580575.00
      2533275.04     13580525.01
#Sta/Elev= 30
  4555.4  183.26  4578.4  182.09  4622.7  181.14  4677.7  179.16  4687.1  179.29
  4716.6  178.26  4724.6  179.19  4730.3  177.90  4751.9  177.08  4799.7  176.26
  4900.7  173.36  4944.8  173.18  4978.8  172.43  4986.4  170.05  4991.5  171.47
  4997.1  169.72  4997.3  169.22  5000.8  169.22  5001.1  169.72  5006.3  170.62
  5009.2  171.12  5019.3  171.56  5047.2  174.80  5059.9  175.81  5130.9  178.99
  5151.1  179.35  5205.5  181.93  5212.4  182.17  5252.5  183.29  5262.6  184.07
#Mann=10,-1,0
  4555.4    0.12       0  4622.7   0.013       0  4677.7    0.12       0
  4799.7    0.04       0  4900.7    0.12       0  4997.1    0.05       0
  5001.1    0.12       0  5006.3    0.04       0  5205.5    0.12       0
  5212.4    0.04       0
Bank Sta=4997.1,5001.1
Exp/Cntr=0.3,0.1

Type RM Length L Ch R = 1,3196,548,548,548
BEGIN DESCRIPTION:
TRIB 1_1 TO OAKLEY BRANCH 6.0
END DESCRIPTION:
XS GIS Cut Line= 3
      2534125.03     13580325.01      2533775.00     13580175.00
      2533375.02     13580324.99
#Sta/Elev= 30
  4674.0  180.63  4695.8  179.60  4772.0  177.76  4793.7  176.61  4840.9  175.39
  4848.1  175.65  4888.0  173.71  4893.4  174.01  4924.3  172.93  4969.6  170.28
  5011.3  168.99  5020.2  165.40  5020.4  164.90  5023.9  164.90  5024.2  165.40
  5033.1  169.14  5040.3  170.31  5108.2  170.76  5140.3  171.43  5150.1  172.33
  5155.4  171.71  5193.7  173.10  5203.6  173.06  5215.9  173.04  5243.7  174.36
  5279.1  175.94  5309.7  176.52  5364.5  178.37  5442.0  180.24  5482.0  181.85
#Mann=6,-1,0
  4674.0    0.12       0  5020.2    0.05       0  5024.2    0.12       0
  5203.6    0.05       0  5243.7   0.013       0  5309.7    0.05       0
Bank Sta=5020.2,5024.2
Exp/Cntr=0.3,0.1

Type RM Length L Ch R = 1,2648,497,497,497
BEGIN DESCRIPTION:
TRIB 1_1 TO OAKLEY BRANCH 5.0
END DESCRIPTION:
XS GIS Cut Line= 3
      2533774.96     13579675.02      2533575.00     13579775.00
      2533375.01     13580024.98
#Sta/Elev= 30
  4776.4  175.89  4807.1  175.00  4857.4  172.91  4870.0  172.02  4896.5  170.49
  4946.9  168.49  4997.2  165.43  5003.2  165.43  5007.2  165.00  5040.4  164.63
  5040.6  164.13  5044.1  164.13  5044.4  164.63  5050.4  165.45  5056.8  165.68
  5071.2  167.49  5077.6  167.72  5092.0  168.96  5114.4  169.93  5135.2  170.24
  5141.6  170.94  5156.0  170.93  5170.4  171.67  5192.1  171.92  5204.5  172.60
  5213.7  173.02  5228.1  172.95  5263.3  173.95  5284.1  175.07  5320.1  176.02
#Mann=5,-1,0
  4776.4    0.04       0  4870.0    0.12       0  5040.4    0.05       0
  5044.4    0.12       0  5204.5    0.04       0
Bank Sta=5040.4,5044.4
Exp/Cntr=0.3,0.1

Type RM Length L Ch R = 1,2151,466,466,466
BEGIN DESCRIPTION:
TRIB 1_1 TO OAKLEY BRANCH 4.0
END DESCRIPTION:
XS GIS Cut Line= 4
      2533376.24     13579055.15      2533256.69     13579379.92
      2533225.00     13579475.00      2533092.71     13579946.18
#Sta/Elev= 30
  4553.8  176.03  4597.4  175.18  4649.5  174.49  4687.2  172.54  4692.6  171.29
  4712.4  170.00  4717.7  167.77  4742.8  167.37  4748.2  164.93  4766.8  166.55
  4773.3  167.95  4778.6  166.41  4798.4  169.92  4803.8  168.39  4809.4  170.20
  4828.9  173.69  4834.2  172.57  4852.0  173.07  4859.3  171.80  4864.7  172.20
  4873.3  169.71  4889.8  166.86  4915.8  167.12  4977.0  161.97  4977.3  161.47
  4981.0  161.97  5155.9  168.99  5208.3  169.64  5446.7  177.34  5489.5  177.99
#Mann=4,-1,0
  4553.8    0.04       0  4597.4    0.05       0  4977.0    0.05       0
  4981.0    0.05       0
Bank Sta=4977,4981
Exp/Cntr=0.3,0.1

Type RM Length L Ch R = 1,1685,525,525,525
BEGIN DESCRIPTION:
TRIB 1_1 TO OAKLEY BRANCH 3.0
END DESCRIPTION:
XS GIS Cut Line= 3
      2532825.00     13579275.00      2532775.00     13579475.00
      2532775.00     13579775.05
#Sta/Elev= 30
  4743.0  173.11  4753.3  172.41  4766.2  171.98  4773.9  171.30  4794.5  170.28
  4815.2  168.90  4825.5  168.62  4835.8  167.80  4856.4  167.15  4884.7  165.34
  4907.9  164.42  4926.0  163.06  4946.6  162.00  4979.2  161.29  4989.2  160.29
  4997.2  158.92  4997.4  158.42  5000.9  158.42  5001.2  158.92  5002.5  159.09
  5009.2  159.98  5019.2  161.80  5049.2  164.81  5101.1  167.61  5109.2  168.23
  5129.2  168.80  5169.2  171.49  5199.2  172.50  5239.2  174.40  5249.2  175.10
#Mann=6,-1,0
  4743.0    0.12       0  4907.9     0.1       0  4997.2    0.05       0
  5001.2     0.1       0  5002.5    0.12       0  5101.1    0.04       0
Bank Sta=4997.2,5001.2
Exp/Cntr=0.3,0.1

Type RM Length L Ch R = 1,1160,596,596,596
BEGIN DESCRIPTION:
TRIB 1_1 TO OAKLEY BRANCH 2.0
END DESCRIPTION:
XS GIS Cut Line= 3
      2532725.04     13579124.98      2532375.00     13579275.00
      2532225.01     13579624.99
#Sta/Elev= 30
  4623.5  174.43  4656.2  173.85  4667.1  172.99  4699.7  172.18  4743.2  169.41
  4819.4  165.89  4830.3  166.07  4837.5  164.84  4876.8  163.33  4884.5  163.10
  4895.5  161.99  4949.9  159.99  4982.6  159.30  4995.3  160.01  5001.6  159.36
  5037.0  159.92  5056.7  159.02  5056.9  158.52  5060.5  158.52  5060.8  159.02
  5080.5  161.01  5134.9  164.34  5171.1  165.85  5232.8  169.59  5264.6  170.46
  5287.2  171.24  5294.5  170.97  5330.7  172.81  5376.8  174.35  5385.1  174.80
#Mann=7,-1,0
  4623.5    0.04       0  4876.8    0.12       0  4884.5     0.1       0
  5056.7    0.05       0  5060.8     0.1       0  5264.6    0.05       0
  5376.8    0.12       0
Bank Sta=5056.7,5060.8
Exp/Cntr=0.3,0.1

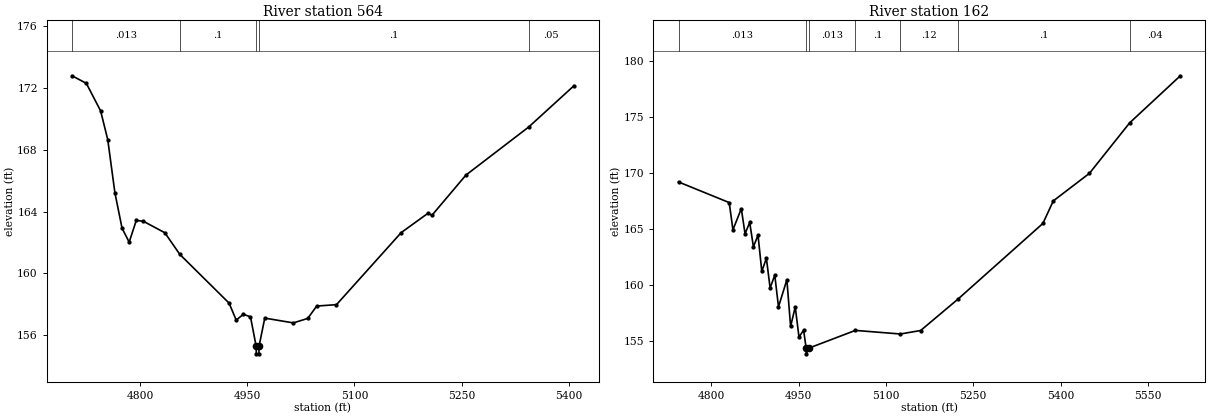
Type RM Length L Ch R = 1,564,402,402,402
BEGIN DESCRIPTION:
TRIB 1_1 TO OAKLEY BRANCH 1.0
END DESCRIPTION:
XS GIS Cut Line= 3
      2531975.00     13578825.01      2531975.00     13579125.00
      2532025.00     13579525.00
#Sta/Elev= 30
  4704.3  172.78  4724.3  172.29  4744.3  170.51  4754.3  168.65  4764.3  165.22
  4774.3  162.93  4784.3  162.02  4794.3  163.43  4804.3  163.37  4834.3  162.63
  4855.3  161.23  4924.3  158.08  4934.3  156.98  4944.3  157.36  4954.3  157.19
  4962.2  155.30  4962.5  154.80  4966.1  154.80  4966.3  155.30  4974.3  157.11
  5014.4  156.80  5034.5  157.09  5047.1  157.89  5074.8  157.98  5165.5  162.64
  5203.3  163.90  5208.4  163.75  5256.2  166.36  5344.2  169.47  5407.4  172.13
#Mann=5,-1,0
  4704.3   0.013       0  4855.3     0.1       0  4962.2    0.05       0
  4966.3     0.1       0  5344.2    0.05       0
Bank Sta=4962.2,4966.3
Exp/Cntr=0.3,0.1

Type RM Length L Ch R = 1,162,0,0,0
BEGIN DESCRIPTION:
TRIB 1_1 TO OAKLEY BRANCH 0.5
END DESCRIPTION:
XS GIS Cut Line= 3
      2531813.71     13578911.97      2531618.41     13579070.37
      2531605.42     13579681.18
#Sta/Elev= 30
  4743.5  169.22  4830.6  167.38  4837.0  164.95  4851.4  166.84  4857.8  164.60
  4865.8  165.61  4872.2  163.44  4880.1  164.47  4886.6  161.25  4894.5  162.41
  4900.9  159.76  4908.9  160.91  4915.3  158.08  4929.7  160.50  4936.1  156.34
  4944.1  158.07  4950.5  155.39  4958.5  156.00  4962.8  154.39  4963.1  153.89
  4967.0  154.39  5047.4  155.98  5124.7  155.66  5159.6  155.97  5223.3  158.75
  5369.7  165.52  5387.6  167.53  5449.7  169.99  5518.8  174.49  5605.9  178.69
#Mann=7,-1,0
  4743.5   0.013       0  4962.8    0.03       0  4967.0   0.013       0
  5047.4     0.1       0  5124.7    0.12       0  5223.3     0.1       0
  5518.8    0.04       0
Bank Sta=4962.8,4967
Exp/Cntr=0.3,0.1

Chan Stop Cuts=-1