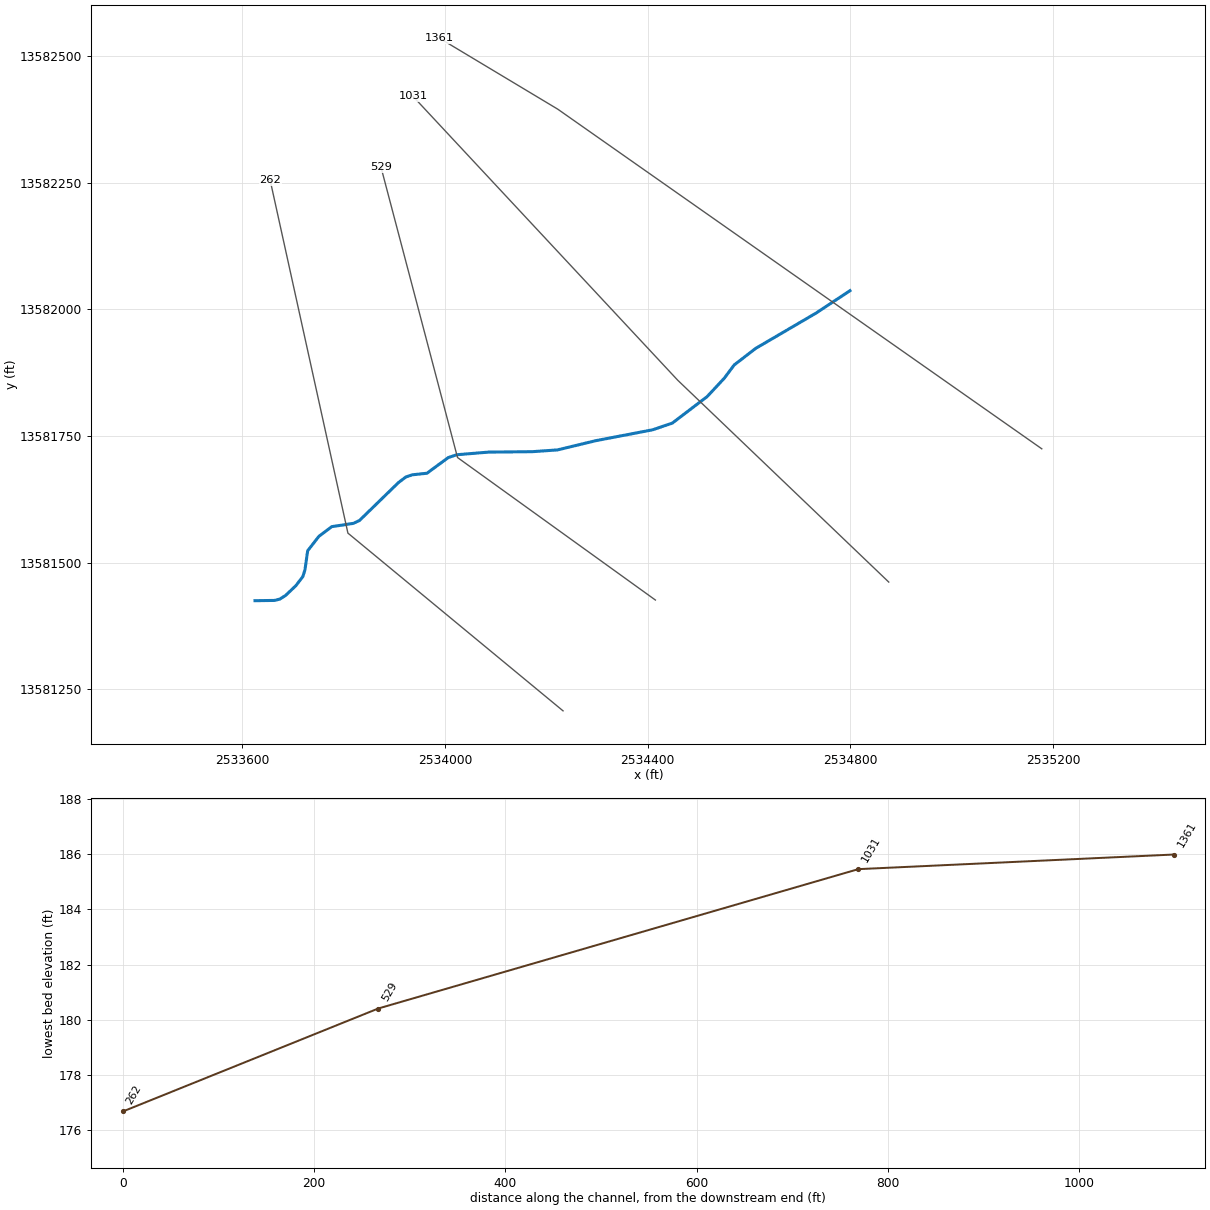
--- TRIB 1_1_1 TO OAXLEY BRANCH.prj (project) ---

Proj Title=TRIB 1_1_1 TO OAXLEY BRANCH Base Level Engineering
Current Plan=p01
Default Exp/Contr=0.3,0.1
English Units
Geom File=g01
Flow File=f01
Plan File=p01
BEGIN DESCRIPTION:
TRIB 1_1_1 TO OAXLEY BRANCH
END DESCRIPTION:

--- TRIB 1_1_1 TO OAXLEY BRANCH.p01 (plan) ---

Plan Title=Multiple Run
Short Identifier=Multiple
Geom File=g01
Flow File=f01
Subcritical Flow
K Sum by GR= 0
Std Step Tol= 0.01
Critical Tol= 0.01
Num of Std Step Trials= 20
Max Error Tol= 0.3
Flow Tol Ratio= 0.001
Split Flow NTrial= 30
Split Flow Tol= 0.02
Split Flow Ratio= 0.02
Log Output Level= 0
Friction Slope Method= 1
Unsteady Friction Slope Method= 2
Unsteady Bridges Friction Slope Method= 1
Parabolic Critical Depth
Global Vel Dist=  1 , 1 , 1
Global Log Level= 0
CheckData=True
Encroach Param= -1, 0, 0, 0
BEGIN DESCRIPTION:
Multiple Run
END DESCRIPTION:

--- TRIB 1_1_1 TO OAXLEY BRANCH.f01 (steady flow) ---

Flow Title=Multiple
Number of Profiles=7
Profile Names=10-year,25-year,50-year,1pct_min,100-year,1pct_plu,500-year
River Rch & RM= TRIB 1_1_1 TO OA,Reach-1,1361
     217     327     419     262     523    1044     803
Boundary for River Rch & Prof#=TRIB 1_1_1 TO OA,Reach-1,1
Up Type=0
Dn Type=3
Dn Slope=0.005
Boundary for River Rch & Prof#=TRIB 1_1_1 TO OA,Reach-1,2
Up Type=0
Dn Type=3
Dn Slope=0.005
Boundary for River Rch & Prof#=TRIB 1_1_1 TO OA,Reach-1,3
Up Type=0
Dn Type=3
Dn Slope=0.005
Boundary for River Rch & Prof#=TRIB 1_1_1 TO OA,Reach-1,4
Up Type=0
Dn Type=3
Dn Slope=0.005
Boundary for River Rch & Prof#=TRIB 1_1_1 TO OA,Reach-1,5
Up Type=0
Dn Type=3
Dn Slope=0.005
Boundary for River Rch & Prof#=TRIB 1_1_1 TO OA,Reach-1,6
Up Type=0
Dn Type=3
Dn Slope=0.005
Boundary for River Rch & Prof#=TRIB 1_1_1 TO OA,Reach-1,7
Up Type=0
Dn Type=3
Dn Slope=0.005

--- TRIB 1_1_1 TO OAXLEY BRANCH.g01 (geometry) ---

Geom Title=Existing Conditions

River Reach=TRIB 1_1_1 TO OA,Reach-1
Reach XY= 30
      2534799.45     13582036.82      2534732.01     13581992.35
      2534613.26     13581922.91      2534570.90     13581890.27
      2534551.11     13581863.84      2534517.43     13581827.77
      2534448.64     13581775.42      2534409.75     13581762.23
      2534297.56     13581740.79      2534222.04     13581722.56
      2534172.12     13581719.09      2534085.75     13581718.22
      2534023.25     13581713.01      2534006.32     13581707.37
      2533964.37     13581676.54      2533935.65     13581673.44
      2533922.72     13581669.13      2533908.34     13581658.32
      2533831.02     13581583.18      2533818.91     13581577.56
      2533776.43     13581571.11      2533751.16     13581552.14
      2533728.87     13581523.56      2533723.48     13581485.58
      2533719.28     13581472.52      2533705.49     13581454.54
      2533685.25     13581435.33      2533673.97     13581428.14
      2533663.38     13581425.50      2533625.00     13581425.00

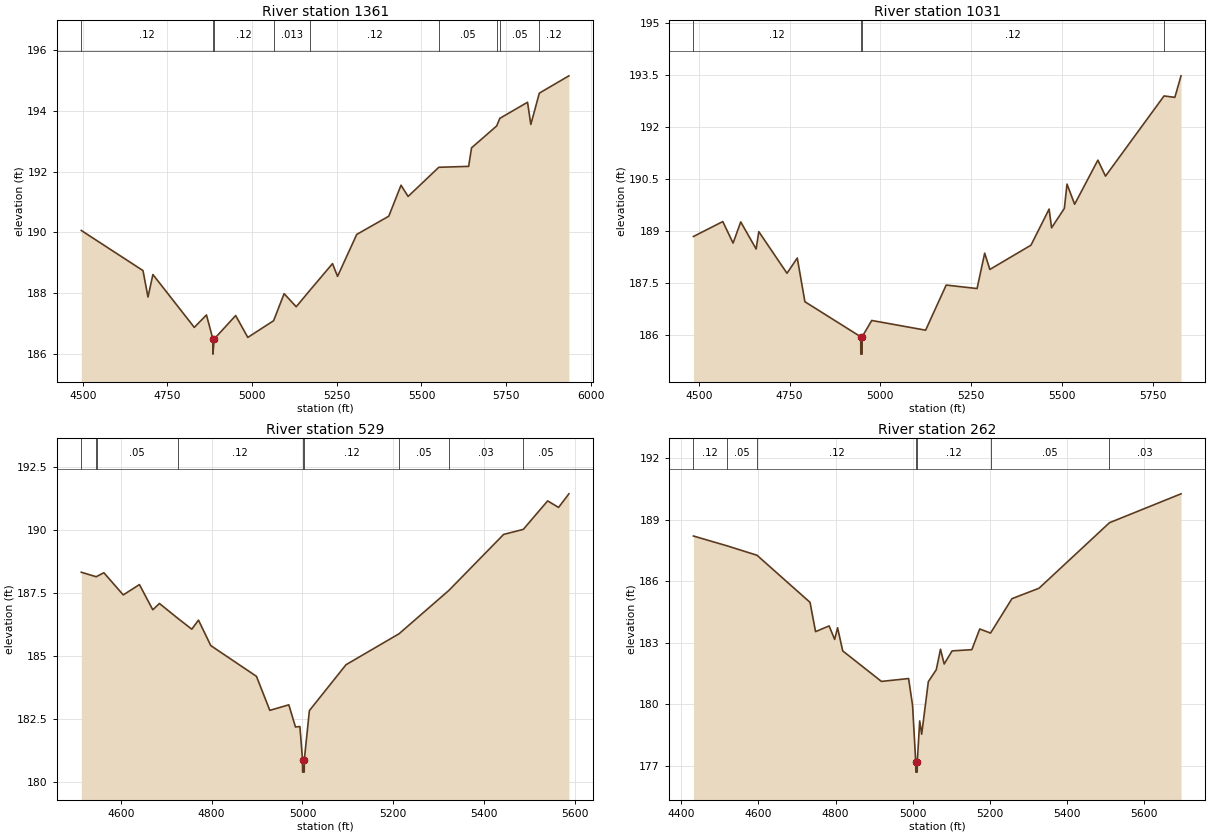
Type RM Length L Ch R = 1,1361,330,330,330
BEGIN DESCRIPTION:
Mapping XS ac397169
END DESCRIPTION:
XS GIS Cut Line= 3
      2535178.08     13581724.75      2534222.62     13582395.04
      2533989.15     13582535.12
#Sta/Elev= 30
  4495.8  190.06  4677.9  188.74  4692.7  187.87  4707.2  188.61  4829.4  186.87
  4865.3  187.28  4884.2  186.49  4884.4  185.99  4888.2  186.49  4951.5  187.26
  4987.3  186.54  5063.5  187.09  5094.5  187.98  5130.2  187.55  5171.4  188.10
  5237.4  188.97  5252.2  188.55  5308.9  189.93  5403.5  190.53  5439.6  191.55
  5460.5  191.18  5551.2  192.14  5639.2  192.17  5647.8  192.78  5722.0  193.50
  5731.2  193.75  5813.1  194.28  5822.8  193.55  5847.9  194.58  5935.2  195.15
#Mann=9,-1,0
  4495.8    0.12       0  4884.2    0.05       0  4888.2    0.12       0
  5063.5   0.013       0  5171.4    0.12       0  5551.2    0.05       0
  5722.0    0.12       0  5731.2    0.05       0  5847.9    0.12       0
Bank Sta=4884.2,4888.2
Exp/Cntr=0.3,0.1

Type RM Length L Ch R = 1,1031,502,502,502
BEGIN DESCRIPTION:
Mapping XS c5638a9b
END DESCRIPTION:
XS GIS Cut Line= 3
      2534876.01     13581461.72      2534459.36     13581860.15
      2533936.67     13582420.53
#Sta/Elev= 30
  4485.2  188.85  4566.1  189.28  4594.4  188.66  4615.5  189.27  4657.9  188.49
  4665.2  188.99  4742.9  187.79  4771.2  188.23  4792.2  186.97  4945.9  185.96
  4946.2  185.46  4949.7  185.46  4949.9  185.96  4976.2  186.43  5124.6  186.15
  5181.3  187.45  5266.3  187.35  5287.3  188.37  5301.5  187.90  5414.8  188.60
  5464.7  189.64  5471.5  189.10  5506.7  189.66  5514.0  190.36  5535.0  189.78
  5599.0  191.05  5620.0  190.59  5781.2  192.90  5811.0  192.86  5828.0  193.48
#Mann=4,-1,0
  4485.2    0.12       0  4945.9    0.05       0  4949.9    0.12       0
  5781.2    0.05       0
Bank Sta=4945.9,4949.9
Exp/Cntr=0.3,0.1

Type RM Length L Ch R = 1,529,267,267,267
BEGIN DESCRIPTION:
Mapping XS 696cb8f1
END DESCRIPTION:
XS GIS Cut Line= 3
      2534415.32     13581426.29      2534024.70     13581707.54
      2533873.72     13582280.23
#Sta/Elev= 30
  4513.0  188.34  4546.0  188.16  4546.8  188.17  4562.7  188.32  4605.4  187.44
  4641.0  187.85  4670.4  186.85  4685.1  187.10  4724.9  186.52  4756.3  186.08
  4771.0  186.44  4798.1  185.43  4898.7  184.21  4928.1  182.86  4969.9  183.08
  4984.6  182.20  4994.3  182.22  5000.1  180.91  5000.3  180.41  5003.8  180.41
  5004.1  180.91  5015.2  182.85  5095.8  184.67  5212.7  185.90  5322.4  187.62
  5442.9  189.84  5486.2  190.04  5539.8  191.17  5563.8  190.91  5586.6  191.45
#Mann=9,-1,0
  4513.0    0.05       0  4546.0    0.12       0  4546.8    0.05       0
  4724.9    0.12       0  5000.1    0.05       0  5004.1    0.12       0
  5212.7    0.05       0  5322.4    0.03       0  5486.2    0.05       0
Bank Sta=5000.1,5004.1
Exp/Cntr=0.3,0.1

Type RM Length L Ch R = 1,262,0,0,0
BEGIN DESCRIPTION:
TRIB 1_1-1 TO OAKLEY BRANCH 1.0
END DESCRIPTION:
XS GIS Cut Line= 3
      2534233.02     13581207.55      2533808.32     13581558.36
      2533654.91     13582254.41
#Sta/Elev= 30
  4431.7  188.21  4519.0  187.73  4596.5  187.27  4733.9  184.97  4748.2  183.54
  4783.4  183.82  4797.7  183.16  4805.3  183.73  4818.6  182.60  4918.9  181.11
  4989.3  181.25  4999.6  179.94  5007.8  177.18  5008.1  176.68  5011.6  176.68
  5011.8  177.18  5018.1  179.18  5023.2  178.53  5040.5  181.10  5061.0  181.68
  5072.0  182.68  5081.5  181.96  5102.0  182.60  5153.2  182.66  5173.7  183.67
  5201.7  183.47  5257.1  185.15  5327.3  185.66  5509.9  188.86  5695.3  190.27
#Mann=7,-1,0
  4431.7    0.12       0  4519.0    0.05       0  4596.5    0.12       0
  5007.8    0.05       0  5011.8    0.12       0  5201.7    0.05       0
  5509.9    0.03       0
Bank Sta=5007.8,5011.8
Exp/Cntr=0.3,0.1

Chan Stop Cuts=-1