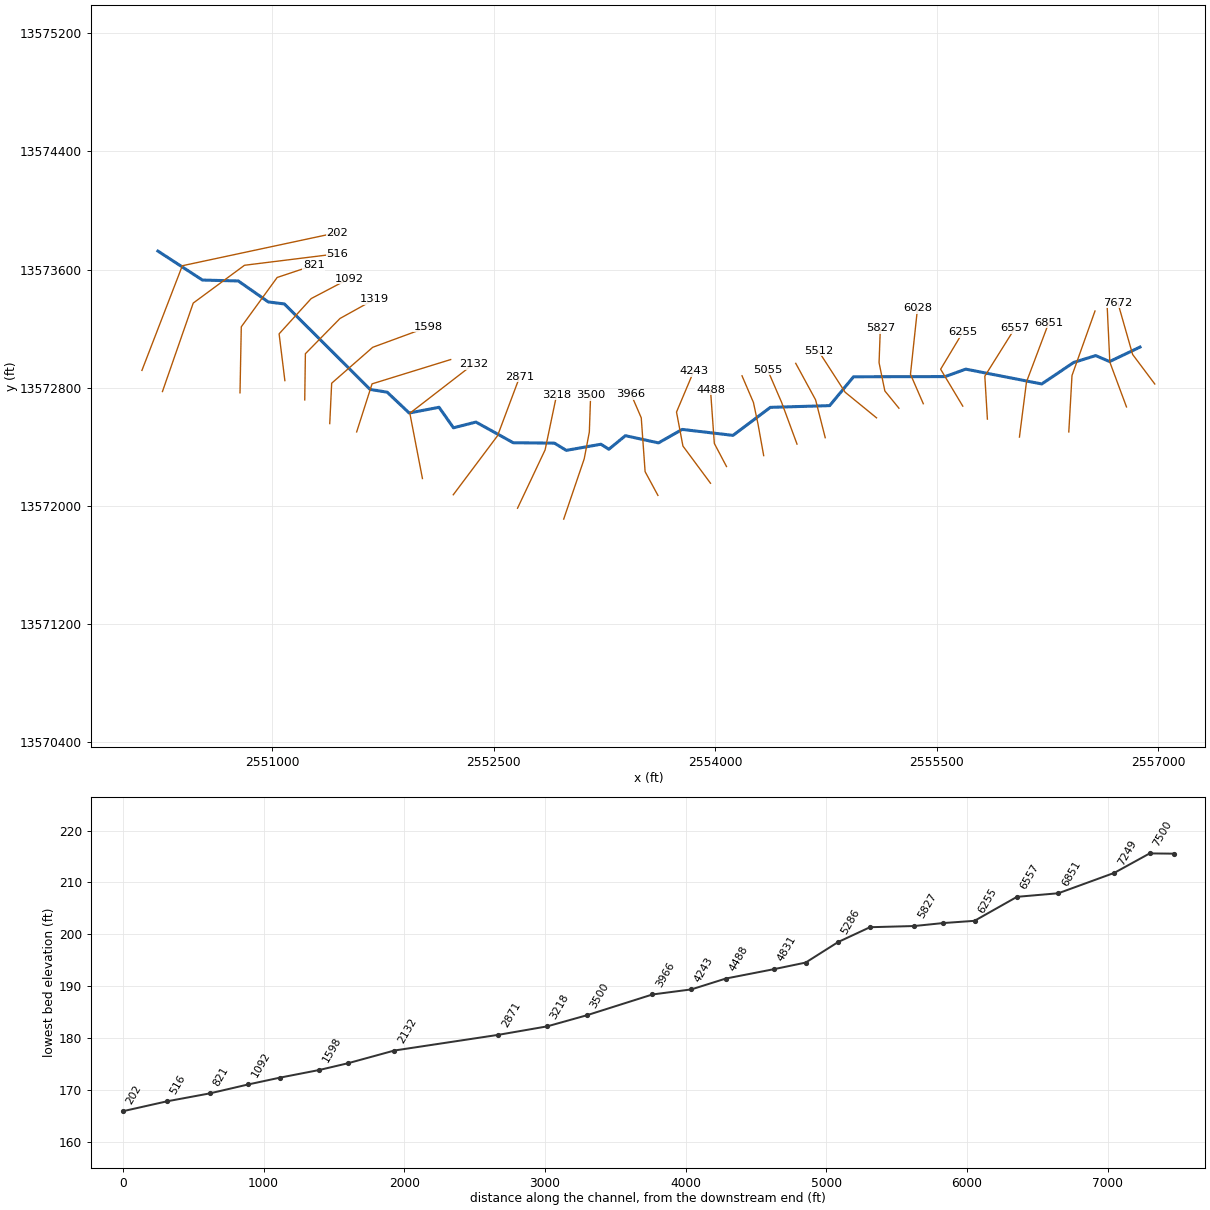
--- TRIB 1_2 TO IRISH CREEK.prj (project) ---

Proj Title=TRIB 1_2 TO IRISH CREEK Base Level Engineering
Current Plan=p01
Default Exp/Contr=0.3,0.1
English Units
Geom File=g01
Flow File=f01
Plan File=p01
BEGIN DESCRIPTION:
TRIB 1_2 TO IRISH CREEK
END DESCRIPTION:

--- TRIB 1_2 TO IRISH CREEK.p01 (plan) ---

Plan Title=Multiple Run
Short Identifier=Multiple
Geom File=g01
Flow File=f01
Subcritical Flow
K Sum by GR= 0
Std Step Tol= 0.01
Critical Tol= 0.01
Num of Std Step Trials= 20
Max Error Tol= 0.3
Flow Tol Ratio= 0.001
Split Flow NTrial= 30
Split Flow Tol= 0.02
Split Flow Ratio= 0.02
Log Output Level= 0
Friction Slope Method= 1
Unsteady Friction Slope Method= 2
Unsteady Bridges Friction Slope Method= 1
Parabolic Critical Depth
Global Vel Dist=  1 , 1 , 1
Global Log Level= 0
CheckData=True
Encroach Param= -1, 0, 0, 0
BEGIN DESCRIPTION:
Multiple Run
END DESCRIPTION:

--- TRIB 1_2 TO IRISH CREEK.f01 (steady flow) ---

Flow Title=Multiple
Number of Profiles=7
Profile Names=10-year,25-year,50-year,1pct_min,100-year,1pct_plu,500-year
River Rch & RM= TRIB 1_2 TO IRIS,Reach-1,7672
     638    1016    1354     873    1742    3476    2855
River Rch & RM= TRIB 1_2 TO IRIS,Reach-1,3500
     801    1293    1738    1130    2255    4499    3758
Boundary for River Rch & Prof#=TRIB 1_2 TO IRIS,Reach-1,1
Up Type=0
Dn Type=3
Dn Slope=0.005
Boundary for River Rch & Prof#=TRIB 1_2 TO IRIS,Reach-1,2
Up Type=0
Dn Type=3
Dn Slope=0.005
Boundary for River Rch & Prof#=TRIB 1_2 TO IRIS,Reach-1,3
Up Type=0
Dn Type=3
Dn Slope=0.005
Boundary for River Rch & Prof#=TRIB 1_2 TO IRIS,Reach-1,4
Up Type=0
Dn Type=3
Dn Slope=0.005
Boundary for River Rch & Prof#=TRIB 1_2 TO IRIS,Reach-1,5
Up Type=0
Dn Type=3
Dn Slope=0.005
Boundary for River Rch & Prof#=TRIB 1_2 TO IRIS,Reach-1,6
Up Type=0
Dn Type=3
Dn Slope=0.005
Boundary for River Rch & Prof#=TRIB 1_2 TO IRIS,Reach-1,7
Up Type=0
Dn Type=3
Dn Slope=0.005

--- TRIB 1_2 TO IRISH CREEK.g01 (geometry) ---

Geom Title=Existing Conditions

River Reach=TRIB 1_2 TO IRIS,Reach-1
Reach XY= 30
      2556875.00     13573075.00      2556668.88     13572976.84
      2556575.01     13573017.41      2556426.59     13572971.18
      2556209.78     13572825.25      2555695.05     13572925.59
      2555554.97     13572875.07      2554935.28     13572874.01
      2554773.55     13572678.53      2554371.77     13572666.76
      2554119.15     13572477.06      2553774.99     13572517.47
      2553614.50     13572426.19      2553390.34     13572475.04
      2553278.33     13572383.01      2553225.10     13572417.19
      2552990.22     13572375.52      2552909.78     13572424.48
      2552630.94     13572427.26      2552378.41     13572567.19
      2552226.28     13572528.38      2552128.67     13572667.31
      2551926.47     13572628.53      2551777.43     13572769.48
      2551661.70     13572788.40      2551081.17     13573367.14
      2550972.58     13573380.54      2550769.07     13573522.76
      2550526.55     13573528.75      2550225.00     13573725.00

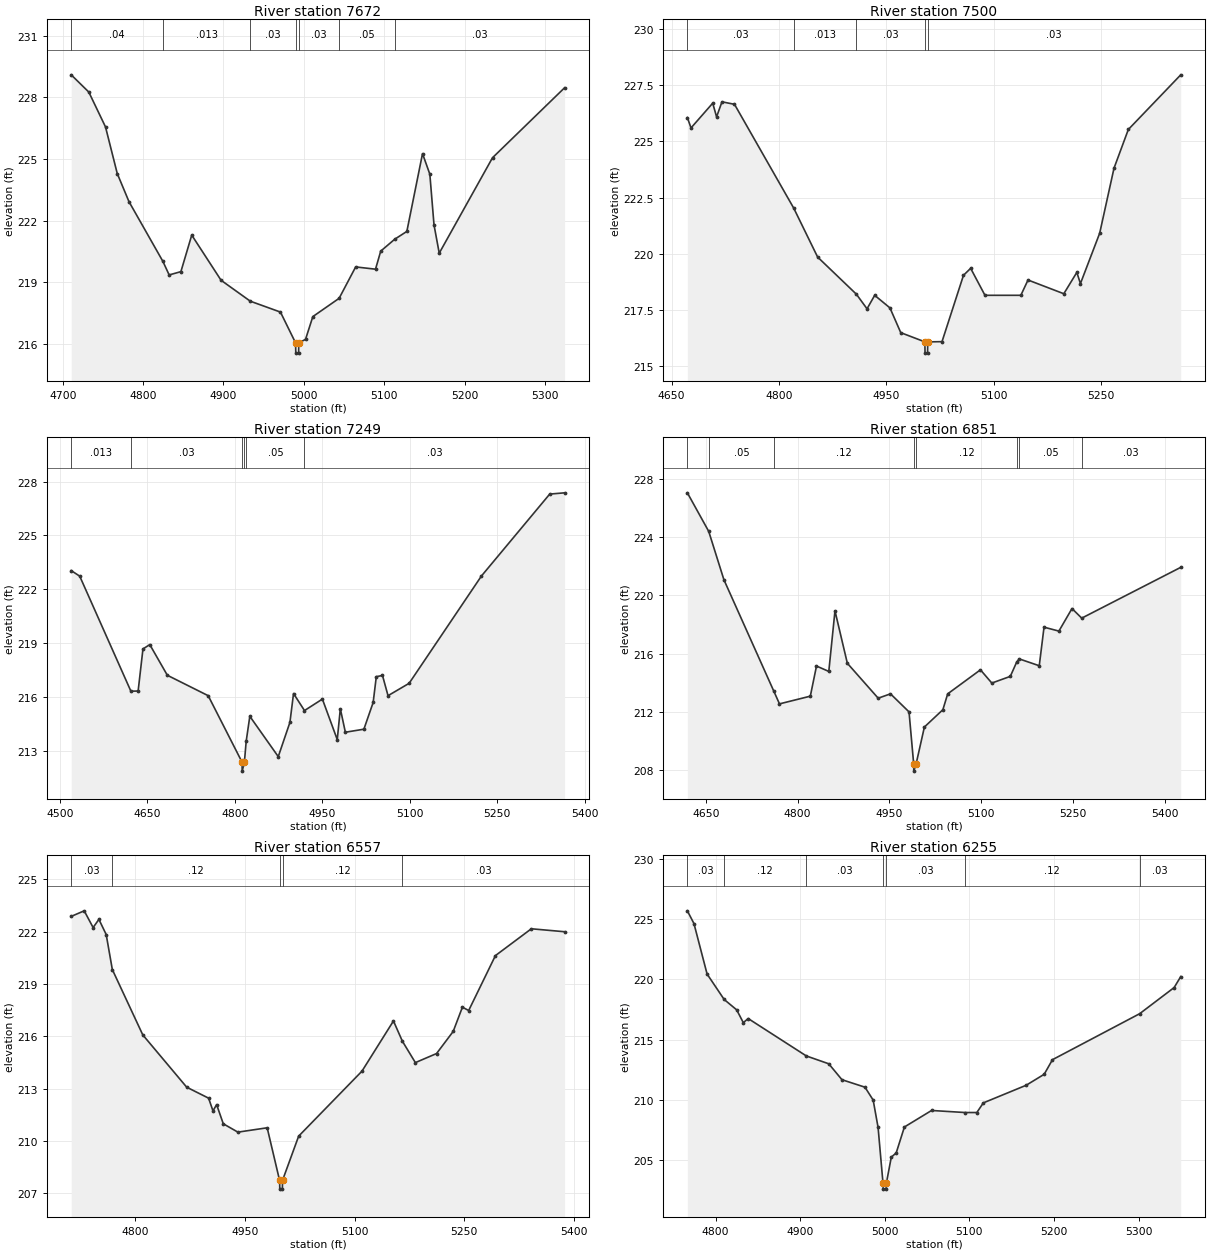
Type RM Length L Ch R = 1,7672,172,172,172
BEGIN DESCRIPTION:
TRIB 1_2 TO IRISH CREEK 16.0
END DESCRIPTION:
XS GIS Cut Line= 3
      2556975.02     13572824.97      2556825.00     13573025.00
      2556725.01     13573374.96
#Sta/Elev= 30
  4710.5  229.10  4732.4  228.26  4753.2  226.56  4767.8  224.29  4782.4  222.92
  4824.6  220.01  4832.4  219.35  4847.0  219.51  4860.5  221.29  4897.0  219.09
  4933.4  218.07  4970.9  217.54  4989.7  216.04  4990.0  215.54  4993.5  215.54
  4993.7  216.04  5002.1  216.21  5011.2  217.32  5043.9  218.21  5064.5  219.74
  5089.2  219.63  5095.7  220.51  5113.1  221.09  5128.2  221.47  5147.7  225.26
  5156.8  224.26  5162.0  221.79  5168.5  220.41  5234.8  225.06  5324.5  228.47
#Mann=7,-1,0
  4710.5    0.04       0  4824.6   0.013       0  4933.4    0.03       0
  4989.7    0.03       0  4993.7    0.03       0  5043.9    0.05       0
  5113.1    0.03       0
Bank Sta=4989.7,4993.7
Exp/Cntr=0.3,0.1

Type RM Length L Ch R = 1,7500,251,251,251
BEGIN DESCRIPTION:
Mapping XS 418f9893
END DESCRIPTION:
XS GIS Cut Line= 3
      2556783.44     13572669.76      2556670.61     13572973.53
      2556653.25     13573338.07
#Sta/Elev= 30
  4672.1  226.06  4677.2  225.60  4707.5  226.70  4712.9  226.09  4720.4  226.76
  4737.9  226.65  4820.7  222.03  4854.0  219.86  4908.1  218.21  4923.0  217.56
  4933.7  218.16  4955.0  217.60  4970.1  216.50  5003.8  216.09  5004.0  215.59
  5007.5  215.59  5007.8  216.09  5027.7  216.10  5057.7  219.05  5067.7  219.36
  5087.7  218.16  5137.8  218.16  5147.8  218.84  5197.8  218.23  5216.0  219.18
  5221.0  218.68  5247.9  220.92  5267.9  223.81  5287.9  225.53  5361.1  227.96
#Mann=5,-1,0
  4672.1    0.03       0  4820.7   0.013       0  4908.1    0.03       0
  5003.8    0.03       0  5007.8    0.03       0
Bank Sta=5003.8,5007.8
Exp/Cntr=0.3,0.1

Type RM Length L Ch R = 1,7249,398,398,398
BEGIN DESCRIPTION:
Mapping XS d5200b9c
END DESCRIPTION:
XS GIS Cut Line= 3
      2556392.83     13572500.41      2556414.53     13572882.39
      2556570.25     13573319.28
#Sta/Elev= 30
  4519.2  223.04  4533.8  222.73  4621.6  216.31  4634.0  216.32  4642.3  218.67
  4654.0  218.91  4684.1  217.20  4754.2  216.06  4812.3  212.35  4812.5  211.85
  4816.3  212.35  4819.4  213.52  4825.6  214.91  4874.4  212.66  4894.4  214.57
  4900.6  216.18  4919.4  215.23  4950.1  215.87  4975.6  213.61  4980.9  215.33
  4989.5  214.02  5021.3  214.19  5037.2  215.68  5042.6  217.12  5053.2  217.19
  5062.7  216.06  5098.9  216.75  5223.0  222.74  5340.1  227.31  5365.6  227.38
#Mann=6,-1,0
  4519.2   0.013       0  4621.6    0.03       0  4812.3    0.03       0
  4816.3    0.03       0  4819.4    0.05       0  4919.4    0.03       0
Bank Sta=4812.3,4816.3
Exp/Cntr=0.3,0.1

Type RM Length L Ch R = 1,6851,294,294,294
BEGIN DESCRIPTION:
Mapping XS be07f175
END DESCRIPTION:
XS GIS Cut Line= 3
      2556058.63     13572465.74      2556106.37     13572838.99
      2556257.80     13573241.35
#Sta/Elev= 30
  4619.9  227.04  4654.8  224.39  4679.6  221.07  4761.3  213.40  4770.4  212.54
  4820.8  213.07  4830.9  215.14  4851.0  214.77  4861.1  218.93  4881.3  215.33
  4931.7  212.93  4951.8  213.23  4982.1  211.99  4989.7  208.42  4989.9  207.92
  4993.7  208.42  5007.2  210.95  5037.4  212.14  5045.3  213.23  5098.8  214.88
  5117.4  213.97  5147.6  214.43  5158.1  215.42  5162.2  215.63  5194.9  215.16
  5202.7  217.81  5227.0  217.54  5248.4  219.09  5264.3  218.43  5426.1  221.92
#Mann=8,-1,0
  4619.9    0.03       0  4654.8    0.05       0  4761.3    0.12       0
  4989.7    0.05       0  4993.7    0.12       0  5158.1    0.03       0
  5162.2    0.05       0  5264.3    0.03       0
Bank Sta=4989.7,4993.7
Exp/Cntr=0.3,0.1

Type RM Length L Ch R = 1,6557,302,302,302
BEGIN DESCRIPTION:
Mapping XS a879af64
END DESCRIPTION:
XS GIS Cut Line= 3
      2555841.62     13572587.20      2555824.26     13572878.05
      2556028.24     13573203.55
#Sta/Elev= 30
  4712.1  222.88  4729.9  223.20  4742.1  222.24  4750.0  222.71  4760.0  221.84
  4768.4  219.83  4810.1  216.08  4870.2  213.08  4900.2  212.45  4906.2  211.72
  4911.2  212.08  4920.3  210.98  4940.3  210.50  4980.4  210.75  4997.4  207.73
  4997.7  207.23  5001.2  207.23  5001.4  207.73  5023.5  210.27  5110.2  214.00
  5153.3  216.88  5165.5  215.72  5183.3  214.49  5212.3  215.01  5235.1  216.28
  5247.7  217.67  5256.3  217.48  5292.9  220.63  5342.1  222.17  5387.6  222.00
#Mann=5,-1,0
  4712.1    0.03       0  4768.4    0.12       0  4997.4    0.05       0
  5001.4    0.12       0  5165.5    0.03       0
Bank Sta=4997.4,5001.4
Exp/Cntr=0.3,0.1

Type RM Length L Ch R = 1,6255,227,227,227
BEGIN DESCRIPTION:
TRIB 1_2 TO IRISH CREEK 13.0
END DESCRIPTION:
XS GIS Cut Line= 3
      2555674.99     13572675.02      2555525.00     13572925.00
      2555675.01     13573175.02
#Sta/Elev= 30
  4766.7  225.68  4774.5  224.62  4790.0  220.44  4810.2  218.33  4825.0  217.47
  4832.8  216.41  4838.6  216.75  4907.3  213.65  4933.8  213.00  4949.4  211.68
  4976.6  211.06  4986.3  209.99  4992.1  207.72  4997.9  203.11  4998.2  202.61
  5001.7  202.61  5001.9  203.11  5007.7  205.26  5013.5  205.61  5023.2  207.76
  5055.3  209.13  5094.9  208.96  5108.8  208.96  5116.5  209.76  5167.1  211.22
  5188.4  212.13  5198.2  213.34  5301.2  217.15  5342.0  219.32  5349.8  220.23
#Mann=7,-1,0
  4766.7    0.03       0  4810.2    0.12       0  4907.3    0.03       0
  4997.9    0.05       0  5001.9    0.03       0  5094.9    0.12       0
  5301.2    0.03       0
Bank Sta=4997.9,5001.9
Exp/Cntr=0.3,0.1

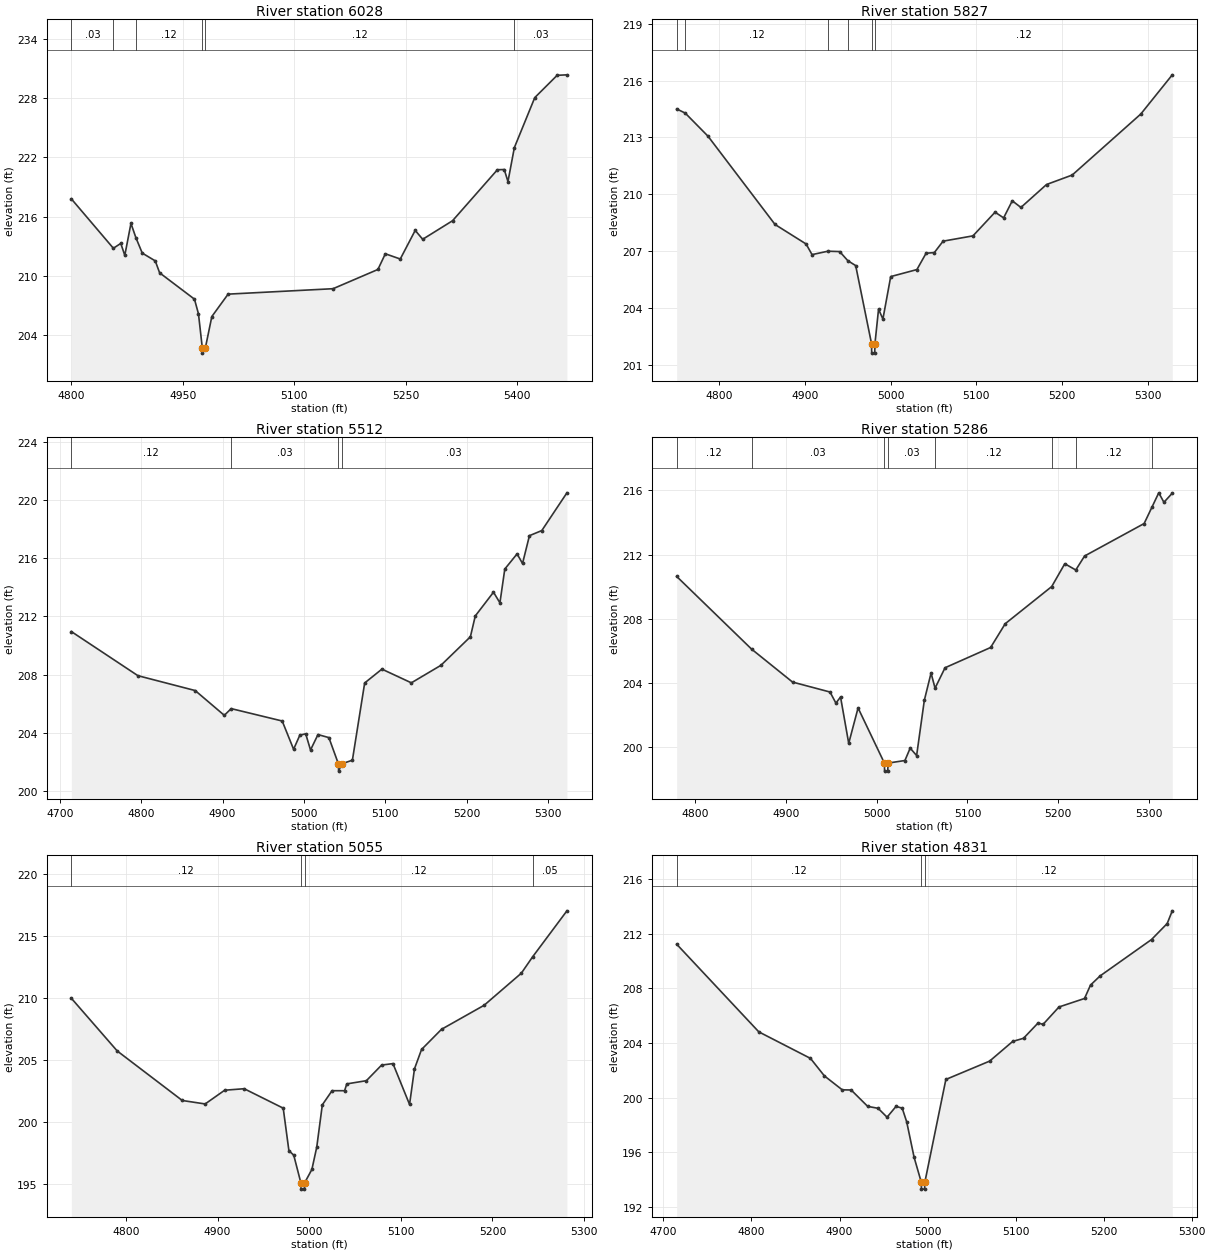
Type RM Length L Ch R = 1,6028,201,201,201
BEGIN DESCRIPTION:
Mapping XS 886a0c5c
END DESCRIPTION:
XS GIS Cut Line= 3
      2555407.60     13572691.40      2555320.78     13572891.07
      2555368.52     13573338.10
#Sta/Elev= 30
  4799.8  217.81  4856.4  212.80  4866.4  213.29  4871.8  212.08  4880.1  215.32
  4886.7  213.88  4895.3  212.31  4912.8  211.52  4918.7  210.31  4965.6  207.64
  4971.0  206.15  4976.2  202.67  4976.4  202.17  4980.2  202.67  4989.0  205.88
  5010.9  208.15  5152.2  208.70  5212.6  210.65  5222.6  212.24  5242.7  211.71
  5262.8  214.61  5272.9  213.71  5313.1  215.59  5373.5  220.76  5382.7  220.78
  5387.7  219.56  5396.3  223.00  5423.8  228.07  5453.9  230.33  5467.1  230.38
#Mann=6,-1,0
  4799.8    0.03       0  4856.4    0.05       0  4886.7    0.12       0
  4976.2    0.05       0  4980.2    0.12       0  5396.3    0.03       0
Bank Sta=4976.2,4980.2
Exp/Cntr=0.3,0.1

Type RM Length L Ch R = 1,5827,315,315,315
BEGIN DESCRIPTION:
Mapping XS a9c27937
END DESCRIPTION:
XS GIS Cut Line= 4
      2555242.67     13572661.01      2555147.17     13572778.22
      2555108.11     13572969.19      2555116.73     13573201.82
#Sta/Elev= 30
  4750.0  214.50  4760.0  214.28  4786.6  213.06  4864.9  208.40  4901.2  207.37
  4908.1  206.81  4926.7  206.99  4940.4  206.97  4949.9  206.49  4959.1  206.23
  4977.6  202.11  4977.8  201.61  4981.3  201.61  4981.6  202.11  4985.8  203.93
  4990.9  203.41  5000.0  205.65  5030.6  206.02  5041.3  206.88  5051.0  206.92
  5061.2  207.52  5096.1  207.80  5121.9  209.05  5131.9  208.75  5142.0  209.65
  5152.1  209.30  5182.0  210.51  5212.0  211.01  5292.1  214.23  5328.9  216.30
#Mann=6,-1,0
  4750.0    0.05       0  4760.0    0.12       0  4926.7    0.03       0
  4949.9    0.12       0  4977.6    0.05       0  4981.6    0.12       0
Bank Sta=4977.6,4981.6
Exp/Cntr=0.3,0.1

Type RM Length L Ch R = 1,5512,226,226,226
BEGIN DESCRIPTION:
Mapping XS 82edfab4
END DESCRIPTION:
XS GIS Cut Line= 3
      2555090.73     13572595.95      2554878.07     13572769.54
      2554696.32     13573050.82
#Sta/Elev= 30
  4714.0  210.96  4795.9  207.93  4866.3  206.91  4902.1  205.21  4910.6  205.67
  4973.3  204.82  4987.3  202.88  4995.0  203.85  5002.2  203.94  5008.1  202.83
  5017.3  203.89  5030.7  203.68  5042.4  201.88  5042.7  201.38  5046.4  201.88
  5059.6  202.13  5074.7  207.43  5095.9  208.38  5132.1  207.44  5168.4  208.64
  5204.7  210.60  5210.7  212.03  5233.1  213.66  5241.0  212.93  5247.0  215.25
  5262.1  216.29  5268.8  215.63  5277.3  217.54  5292.5  217.89  5323.4  220.48
#Mann=4,-1,0
  4714.0    0.12       0  4910.6    0.03       0  5042.4    0.03       0
  5046.4    0.03       0
Bank Sta=5042.4,5046.4
Exp/Cntr=0.3,0.1

Type RM Length L Ch R = 1,5286,231,231,231
BEGIN DESCRIPTION:
Mapping XS 3494f349
END DESCRIPTION:
XS GIS Cut Line= 3
      2554743.54     13572461.34      2554678.42     13572717.46
      2554543.86     13572964.87
#Sta/Elev= 30
  4779.7  210.64  4862.2  206.12  4907.3  204.07  4948.6  203.45  4955.1  202.76
  4960.2  203.14  4969.2  200.26  4979.5  202.46  5008.5  199.03  5008.7  198.53
  5012.2  198.53  5012.5  199.03  5031.1  199.19  5036.9  199.96  5044.0  199.50
  5052.5  202.94  5059.9  204.63  5064.3  203.69  5075.3  204.96  5125.5  206.22
  5141.6  207.70  5192.8  210.01  5207.2  211.43  5219.3  211.04  5229.0  211.91
  5294.6  213.93  5303.3  214.96  5310.7  215.84  5316.4  215.25  5325.6  215.82
#Mann=8,-1,0
  4779.7    0.12       0  4862.2    0.03       0  5008.5    0.03       0
  5012.5    0.03       0  5064.3    0.12       0  5192.8    0.05       0
  5219.3    0.12       0  5303.3    0.05       0
Bank Sta=5008.5,5012.5
Exp/Cntr=0.3,0.1

Type RM Length L Ch R = 1,5055,224,224,224
BEGIN DESCRIPTION:
Mapping XS 3844d8d2
END DESCRIPTION:
XS GIS Cut Line= 3
      2554552.55     13572417.99      2554448.39     13572700.10
      2554353.22     13572920.72
#Sta/Elev= 30
  4740.3  209.99  4790.4  205.73  4861.4  201.73  4886.4  201.45  4907.7  202.56
  4929.0  202.68  4971.6  201.11  4977.8  197.68  4983.1  197.31  4990.9  195.07
  4991.2  194.57  4994.7  194.57  4994.9  195.07  5002.9  196.16  5008.2  197.96
  5014.3  201.38  5024.9  202.52  5038.6  202.52  5041.0  203.07  5062.4  203.33
  5079.0  204.59  5091.4  204.71  5109.5  201.41  5114.9  204.29  5122.6  205.85
  5144.4  207.48  5190.9  209.42  5231.5  212.01  5243.8  213.33  5281.3  217.05
#Mann=4,-1,0
  4740.3    0.12       0  4990.9    0.05       0  4994.9    0.12       0
  5243.8    0.05       0
Bank Sta=4990.9,4994.9
Exp/Cntr=0.3,0.1

Type RM Length L Ch R = 1,4831,343,343,343
BEGIN DESCRIPTION:
Mapping XS 788b9ce4
END DESCRIPTION:
XS GIS Cut Line= 4
      2554326.85     13572339.90      2554287.80     13572556.87
      2554257.41     13572700.10      2554180.16     13572880.37
#Sta/Elev= 30
  4715.0  211.22  4808.3  204.81  4867.0  202.87  4882.8  201.59  4903.1  200.57
  4913.2  200.56  4932.0  199.36  4943.8  199.22  4954.0  198.57  4964.2  199.36
  4971.2  199.23  4976.3  198.23  4984.7  195.64  4992.9  193.81  4993.1  193.31
  4996.6  193.31  4996.9  193.81  5020.8  201.33  5070.5  202.67  5096.7  204.11
  5109.0  204.34  5125.7  205.47  5131.1  205.35  5149.3  206.63  5178.3  207.25
  5185.1  208.23  5196.0  208.90  5254.4  211.56  5272.2  212.73  5278.0  213.66
#Mann=3,-1,0
  4715.0    0.12       0  4992.9    0.05       0  4996.9    0.12       0
Bank Sta=4992.9,4996.9
Exp/Cntr=0.3,0.1

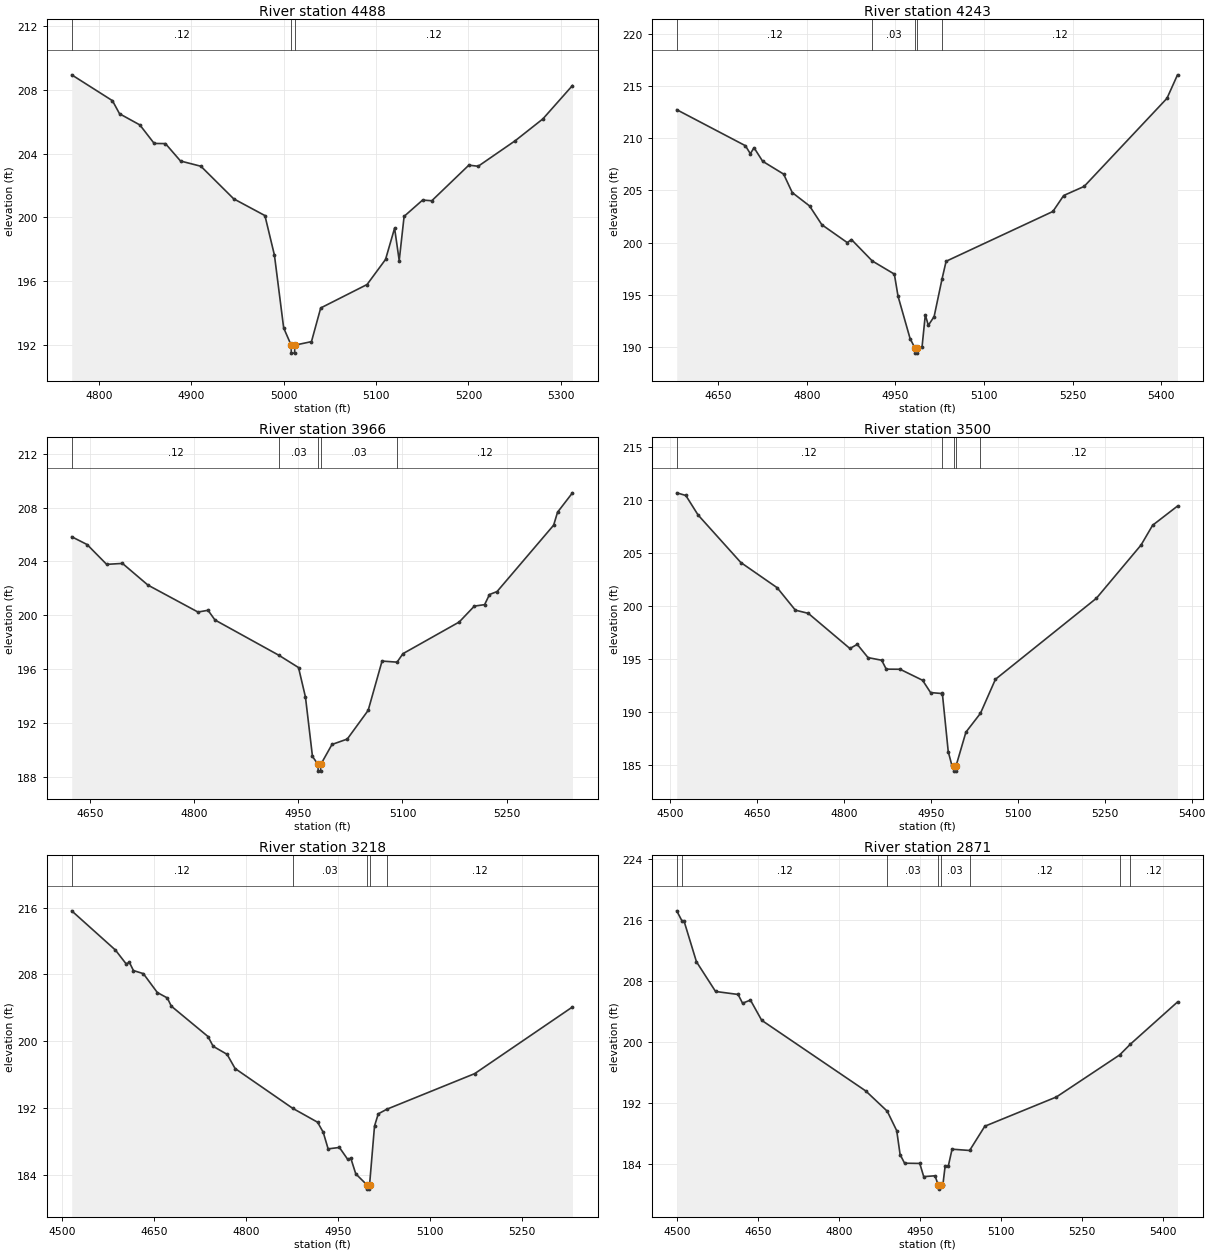
Type RM Length L Ch R = 1,4488,245,245,245
BEGIN DESCRIPTION:
Mapping XS a17143e2
END DESCRIPTION:
XS GIS Cut Line= 3
      2554075.14     13572266.04      2553992.66     13572422.32
      2553966.62     13572786.88
#Sta/Elev= 30
  4770.5  208.94  4814.6  207.32  4822.3  206.50  4844.3  205.80  4859.8  204.64
  4872.0  204.63  4888.3  203.54  4910.4  203.21  4945.9  201.17  4979.7  200.12
  4990.0  197.64  5000.0  193.08  5008.1  192.00  5008.3  191.50  5011.8  191.50
  5012.1  192.00  5030.1  192.22  5040.1  194.33  5090.3  195.80  5110.3  197.37
  5120.1  199.33  5125.1  197.30  5130.4  200.07  5150.4  201.09  5160.4  201.05
  5200.5  203.28  5210.6  203.21  5250.7  204.81  5280.7  206.18  5312.7  208.27
#Mann=3,-1,0
  4770.5    0.12       0  5008.1    0.05       0  5012.1    0.12       0
Bank Sta=5008.1,5012.1
Exp/Cntr=0.3,0.1

Type RM Length L Ch R = 1,4243,277,277,277
BEGIN DESCRIPTION:
Mapping XS c2ff9b89
END DESCRIPTION:
XS GIS Cut Line= 4
      2553966.63     13572153.20      2553779.98     13572404.96
      2553736.58     13572634.99      2553853.19     13572911.41
#Sta/Elev= 30
  4579.9  212.73  4696.1  209.28  4704.5  208.51  4710.7  209.09  4725.3  207.79
  4760.8  206.56  4775.4  204.79  4804.7  203.51  4825.5  201.71  4868.5  200.00
  4875.6  200.29  4910.8  198.24  4948.2  196.98  4954.4  194.87  4974.8  190.81
  4982.9  189.91  4983.2  189.41  4986.7  189.41  4986.9  189.91  4995.1  190.02
  5000.6  193.08  5005.7  192.07  5015.5  192.91  5029.0  196.54  5035.8  198.21
  5216.5  202.98  5234.8  204.51  5269.4  205.38  5409.6  213.82  5427.4  216.07
#Mann=5,-1,0
  4579.9    0.12       0  4910.8    0.03       0  4982.9    0.03       0
  4986.9    0.03       0  5029.0    0.12       0
Bank Sta=4982.9,4986.9
Exp/Cntr=0.3,0.1

Type RM Length L Ch R = 1,3966,466,466,466
BEGIN DESCRIPTION:
Mapping XS efac9bcd
END DESCRIPTION:
XS GIS Cut Line= 4
      2553610.74     13572070.72      2553523.91     13572231.35
      2553497.87     13572595.93      2553429.20     13572754.71
#Sta/Elev= 30
  4623.7  205.83  4645.9  205.25  4674.0  203.78  4696.8  203.85  4733.5  202.24
  4805.5  200.24  4820.0  200.37  4830.0  199.65  4922.4  197.02  4950.3  196.12
  4960.3  193.93  4970.4  189.52  4978.4  188.93  4978.6  188.43  4982.1  188.43
  4982.4  188.93  4998.5  190.41  5020.5  190.81  5050.6  192.94  5070.6  196.60
  5092.2  196.52  5100.7  197.15  5181.7  199.50  5203.5  200.68  5218.3  200.79
  5225.3  201.54  5236.2  201.76  5317.7  206.69  5323.3  207.65  5344.8  209.09
#Mann=5,-1,0
  4623.7    0.12       0  4922.4    0.03       0  4978.4    0.03       0
  4982.4    0.03       0  5092.2    0.12       0
Bank Sta=4978.4,4982.4
Exp/Cntr=0.3,0.1

Type RM Length L Ch R = 1,3500,282,282,282
BEGIN DESCRIPTION:
Mapping XS 46808f4b
END DESCRIPTION:
XS GIS Cut Line= 4
      2552972.69     13571910.16      2553111.58     13572318.15
      2553146.30     13572500.44      2553154.98     13572747.83
#Sta/Elev= 30
  4511.5  210.71  4527.2  210.46  4548.3  208.62  4622.1  204.13  4684.8  201.75
  4716.2  199.63  4738.5  199.33  4810.3  196.01  4823.0  196.40  4841.6  195.15
  4865.2  194.90  4873.0  194.06  4896.9  194.05  4935.7  193.01  4949.5  191.85
  4968.4  191.76  4969.8  191.79  4980.0  186.27  4986.3  184.97  4989.3  184.93
  4989.6  184.43  4993.2  184.43  4993.5  184.93  5010.5  188.11  5035.6  189.89
  5061.4  193.10  5235.6  200.75  5312.7  205.78  5332.7  207.65  5375.6  209.46
#Mann=5,-1,0
  4511.5    0.12       0  4968.4    0.03       0  4989.3    0.03       0
  4993.5    0.03       0  5035.6    0.12       0
Bank Sta=4989.3,4993.5
Exp/Cntr=0.3,0.1

Type RM Length L Ch R = 1,3218,347,347,347
BEGIN DESCRIPTION:
Mapping XS 615a685f
END DESCRIPTION:
XS GIS Cut Line= 3
      2552660.19     13571983.94      2552846.82     13572378.92
      2552924.72     13572751.10
#Sta/Elev= 30
  4515.8  215.61  4587.2  210.91  4604.5  209.27  4610.0  209.43  4616.5  208.46
  4632.7  208.09  4655.5  205.83  4671.8  205.18  4678.3  204.20  4738.2  200.56
  4746.6  199.39  4769.3  198.43  4782.4  196.73  4876.1  191.98  4917.0  190.30
  4926.2  189.10  4934.2  187.11  4952.6  187.28  4966.1  185.86  4971.2  185.99
  4979.3  184.12  4997.6  182.79  4997.9  182.29  5001.6  182.29  5001.8  182.79
  5009.9  189.84  5016.0  191.30  5029.8  191.85  5173.4  196.12  5332.9  204.10
#Mann=5,-1,0
  4515.8    0.12       0  4876.1    0.03       0  4997.6    0.03       0
  5001.8    0.03       0  5029.8    0.12       0
Bank Sta=4997.6,5001.8
Exp/Cntr=0.3,0.1

Type RM Length L Ch R = 1,2871,739,739,739
BEGIN DESCRIPTION:
TRIB 1_2 TO IRISH CREEK 6.0
END DESCRIPTION:
XS GIS Cut Line= 3
      2552224.97     13572074.96      2552525.00     13572475.00
      2552674.98     13572874.96
#Sta/Elev= 30
  4500.0  217.17  4510.2  215.78  4513.6  215.81  4536.5  210.49  4571.9  206.59
  4613.6  206.20  4621.9  205.05  4636.5  205.46  4657.3  202.81  4850.0  193.54
  4889.8  190.88  4907.3  188.33  4913.6  185.19  4921.9  184.06  4950.0  184.03
  4957.3  182.30  4978.2  182.41  4984.4  181.16  4984.7  180.66  4988.7  181.16
  4992.8  181.24  4996.9  183.64  5002.7  183.64  5009.8  185.90  5042.3  185.73
  5070.4  188.91  5203.0  192.75  5320.2  198.27  5340.0  199.68  5427.2  205.21
#Mann=8,-1,0
  4500.0    0.05       0  4510.2    0.12       0  4889.8    0.03       0
  4984.4    0.03       0  4988.7    0.03       0  5042.3    0.12       0
  5320.2    0.05       0  5340.0    0.12       0
Bank Sta=4984.4,4988.7
Exp/Cntr=0.3,0.1

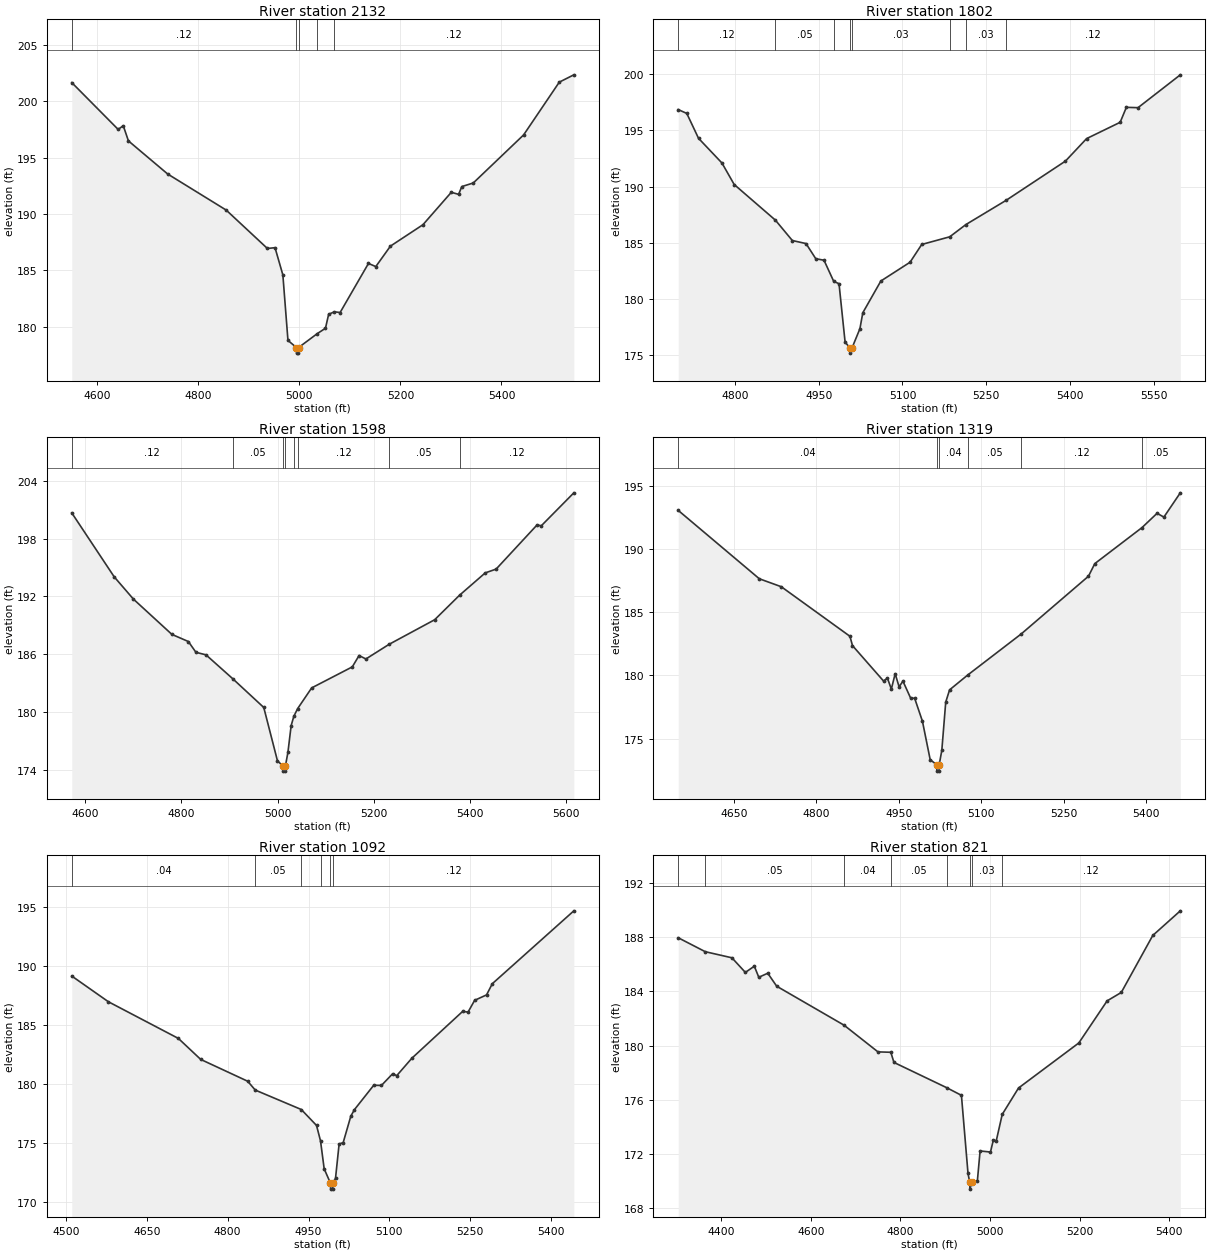
Type RM Length L Ch R = 1,2132,330,330,330
BEGIN DESCRIPTION:
Mapping XS f7b37d98
END DESCRIPTION:
XS GIS Cut Line= 3
      2552016.14     13572184.90      2551930.86     13572627.05
      2552360.63     13572959.25
#Sta/Elev= 30
  4549.7  201.68  4641.5  197.52  4651.6  197.85  4661.8  196.50  4739.4  193.56
  4855.3  190.35  4936.8  186.94  4951.9  187.01  4967.4  184.59  4977.5  178.77
  4994.2  178.14  4994.5  177.64  4998.3  177.64  4998.6  178.14  5035.4  179.37
  5051.7  179.85  5058.0  181.09  5069.2  181.31  5080.7  181.25  5136.8  185.61
  5151.3  185.33  5180.3  187.15  5244.6  189.05  5300.7  191.93  5315.2  191.75
  5321.5  192.44  5344.2  192.76  5443.8  197.03  5514.4  201.72  5543.2  202.37
#Mann=5,-1,0
  4549.7    0.12       0  4994.2    0.05       0  4998.6    0.12       0
  5035.4    0.03       0  5069.2    0.12       0
Bank Sta=4994.2,4998.6
Exp/Cntr=0.3,0.1

Type RM Length L Ch R = 1,1802,204,204,204
BEGIN DESCRIPTION:
Mapping XS 2619a6cf
END DESCRIPTION:
XS GIS Cut Line= 3
      2551570.78     13572500.45      2551674.95     13572825.97
      2552207.34     13572990.44
#Sta/Elev= 30
  4698.5  196.84  4713.8  196.50  4734.8  194.29  4776.8  192.09  4798.7  190.18
  4872.5  187.01  4902.8  185.20  4927.3  184.93  4944.8  183.58  4959.5  183.45
  4976.9  181.57  4986.4  181.36  4997.3  176.16  5005.6  175.69  5005.9  175.19
  5010.0  175.69  5023.8  177.36  5029.0  178.78  5061.3  181.60  5113.6  183.27
  5134.5  184.85  5184.6  185.53  5213.6  186.62  5285.5  188.77  5391.8  192.26
  5429.7  194.26  5489.8  195.71  5500.9  197.04  5521.8  197.01  5597.5  199.93
#Mann=8,-1,0
  4698.5    0.12       0  4872.5    0.05       0  4976.9    0.03       0
  5005.6    0.03       0  5010.0    0.03       0  5184.6    0.05       0
  5213.6    0.03       0  5285.5    0.12       0
Bank Sta=5005.6,5010
Exp/Cntr=0.3,0.1

Type RM Length L Ch R = 1,1598,279,279,279
BEGIN DESCRIPTION:
Mapping XS 3734db4d
END DESCRIPTION:
XS GIS Cut Line= 4
      2551388.49     13572556.83      2551401.51     13572830.31
      2551679.29     13573073.36      2552056.87     13573212.24
#Sta/Elev= 30
  4571.6  200.67  4659.9  194.04  4699.9  191.73  4780.0  188.07  4814.3  187.33
  4830.1  186.21  4851.0  185.95  4906.3  183.49  4971.3  180.49  4999.8  174.96
  5011.8  174.39  5012.1  173.89  5015.9  173.89  5016.2  174.39  5021.6  175.84
  5028.3  178.61  5033.9  179.58  5041.9  180.38  5071.0  182.52  5155.6  184.70
  5169.7  185.88  5183.9  185.52  5232.2  187.04  5327.1  189.59  5378.8  192.13
  5432.4  194.45  5455.0  194.84  5540.2  199.42  5549.0  199.33  5616.8  202.75
#Mann=8,-1,0
  4571.6    0.12       0  4906.3    0.05       0  5011.8    0.05       0
  5016.2    0.05       0  5033.9    0.03       0  5041.9    0.12       0
  5232.2    0.05       0  5378.8    0.12       0
Bank Sta=5011.8,5016.2
Exp/Cntr=0.3,0.1

Type RM Length L Ch R = 1,1319,227,227,227
BEGIN DESCRIPTION:
Mapping XS 39db75e1
END DESCRIPTION:
XS GIS Cut Line= 4
      2551219.22     13572717.44      2551223.56     13573029.96
      2551457.94     13573268.67      2551691.17     13573398.25
#Sta/Elev= 30
  4548.5  193.05  4696.1  187.64  4736.1  187.01  4861.0  183.09  4865.7  182.35
  4922.2  179.55  4929.3  179.78  4936.4  178.91  4943.4  180.13  4950.5  179.09
  4957.5  179.54  4971.7  178.18  4978.8  178.19  4993.0  176.37  5007.1  173.33
  5019.0  172.92  5019.3  172.42  5023.2  172.42  5023.5  172.92  5028.3  174.07
  5035.4  177.88  5042.4  178.85  5075.6  180.03  5172.7  183.27  5295.2  187.84
  5306.8  188.84  5392.7  191.69  5420.1  192.82  5432.5  192.52  5462.4  194.44
#Mann=6,-1,0
  4548.5    0.04       0  5019.0    0.04       0  5023.5    0.04       0
  5075.6    0.05       0  5172.7    0.12       0  5392.7    0.05       0
Bank Sta=5019,5023.5
Exp/Cntr=0.3,0.1

Type RM Length L Ch R = 1,1092,271,271,271
BEGIN DESCRIPTION:
Mapping XS a1fa5a77
END DESCRIPTION:
XS GIS Cut Line= 4
      2551084.67     13572847.66      2551045.61     13573164.51
      2551262.62     13573403.22      2551518.67     13573537.75
#Sta/Elev= 30
  4510.9  189.17  4578.8  186.99  4708.6  183.88  4750.0  182.10  4837.1  180.25
  4851.2  179.50  4936.6  177.85  4964.8  176.50  4972.2  175.19  4979.0  172.82
  4990.7  171.60  4991.0  171.10  4994.9  171.10  4995.2  171.60  5000.0  172.01
  5006.7  174.93  5014.2  175.04  5028.4  177.29  5035.1  177.84  5070.9  179.91
  5085.1  179.89  5106.1  180.89  5113.5  180.72  5141.6  182.20  5236.0  186.18
  5245.8  186.11  5258.0  187.11  5280.1  187.57  5290.8  188.52  5442.0  194.70
#Mann=6,-1,0
  4510.9    0.04       0  4851.2    0.05       0  4936.6    0.03       0
  4972.2    0.12       0  4990.7    0.05       0  4995.2    0.12       0
Bank Sta=4990.7,4995.2
Exp/Cntr=0.3,0.1

Type RM Length L Ch R = 1,821,305,305,305
BEGIN DESCRIPTION:
Mapping XS 520cb23f
END DESCRIPTION:
XS GIS Cut Line= 4
      2550780.85     13572765.17      2550789.53     13573212.25
      2551032.59     13573546.45      2551280.00     13573628.92
#Sta/Elev= 30
  4303.8  187.96  4364.2  186.93  4423.7  186.48  4453.7  185.40  4473.7  185.86
  4483.7  185.04  4503.7  185.34  4523.7  184.38  4674.2  181.50  4749.8  179.53
  4778.5  179.50  4785.5  178.75  4902.9  176.89  4936.2  176.32  4950.9  170.55
  4954.8  169.89  4955.1  169.39  4959.3  169.89  4971.8  170.00  4977.9  172.21
  5001.1  172.13  5007.3  173.00  5014.0  172.96  5027.3  174.91  5063.7  176.86
  5198.4  180.19  5261.6  183.30  5293.2  183.92  5363.5  188.13  5425.0  189.95
#Mann=8,-1,0
  4303.8    0.04       0  4364.2    0.05       0  4674.2    0.04       0
  4778.5    0.05       0  4902.9    0.03       0  4954.8    0.03       0
  4959.3    0.03       0  5027.3    0.12       0
Bank Sta=4954.8,4959.3
Exp/Cntr=0.3,0.1

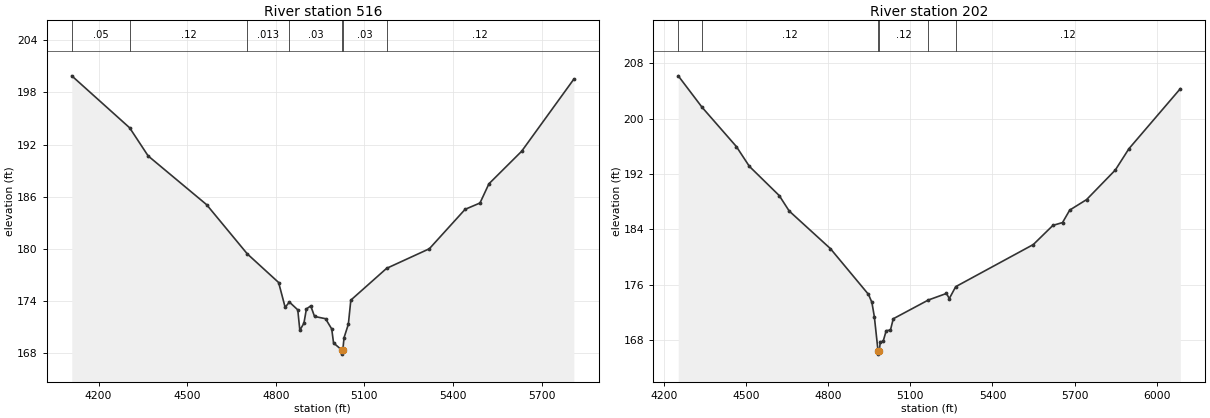
Type RM Length L Ch R = 1,516,314,314,314
BEGIN DESCRIPTION:
Mapping XS 41248b84
END DESCRIPTION:
XS GIS Cut Line= 4
      2550255.68     13572773.89      2550464.01     13573372.84
      2550811.23     13573628.92      2551440.33     13573707.01
#Sta/Elev= 30
  4109.4  199.92  4305.4  193.93  4368.0  190.69  4565.8  185.08  4703.5  179.41
  4809.6  176.11  4831.7  173.25  4846.0  173.86  4874.4  172.96  4881.4  170.61
  4895.2  171.42  4903.7  173.07  4918.3  173.41  4931.2  172.20  4968.4  171.94
  4989.3  170.76  4995.5  169.15  5022.5  168.36  5022.8  167.86  5027.0  168.36
  5031.0  169.75  5045.6  171.30  5054.0  174.08  5175.0  177.74  5319.8  180.00
  5440.8  184.54  5491.2  185.27  5521.4  187.48  5632.2  191.23  5808.9  199.54
#Mann=7,-1,0
  4109.4    0.05       0  4305.4    0.12       0  4703.5   0.013       0
  4846.0    0.03       0  5022.5    0.03       0  5027.0    0.03       0
  5175.0    0.12       0
Bank Sta=5022.5,5027
Exp/Cntr=0.3,0.1

Type RM Length L Ch R = 1,202,0,0,0
BEGIN DESCRIPTION:
TRIB 1_2 TO IRISH CREEK 1.0
END DESCRIPTION:
XS GIS Cut Line= 3
      2550116.78     13572917.08      2550390.34     13573625.82
      2551439.64     13573850.07
#Sta/Elev= 30
  4253.0  206.17  4339.9  201.63  4465.2  195.95  4512.6  193.09  4621.8  188.86
  4658.1  186.63  4808.2  181.21  4947.5  174.58  4959.9  173.43  4968.9  171.35
  4982.2  166.45  4982.5  165.95  4986.9  166.45  4990.4  167.66  5001.1  167.82
  5012.2  169.34  5027.6  169.42  5037.9  171.06  5165.9  173.77  5232.2  174.72
  5242.4  173.98  5265.9  175.70  5549.2  181.79  5620.8  184.56  5655.7  184.96
  5682.1  186.77  5743.5  188.28  5848.5  192.56  5898.0  195.63  6085.7  204.31
#Mann=6,-1,0
  4253.0    0.05       0  4339.9    0.12       0  4982.2    0.05       0
  4986.9    0.12       0  5165.9   0.013       0  5265.9    0.12       0
Bank Sta=4982.2,4986.9
Exp/Cntr=0.3,0.1

Chan Stop Cuts=-1