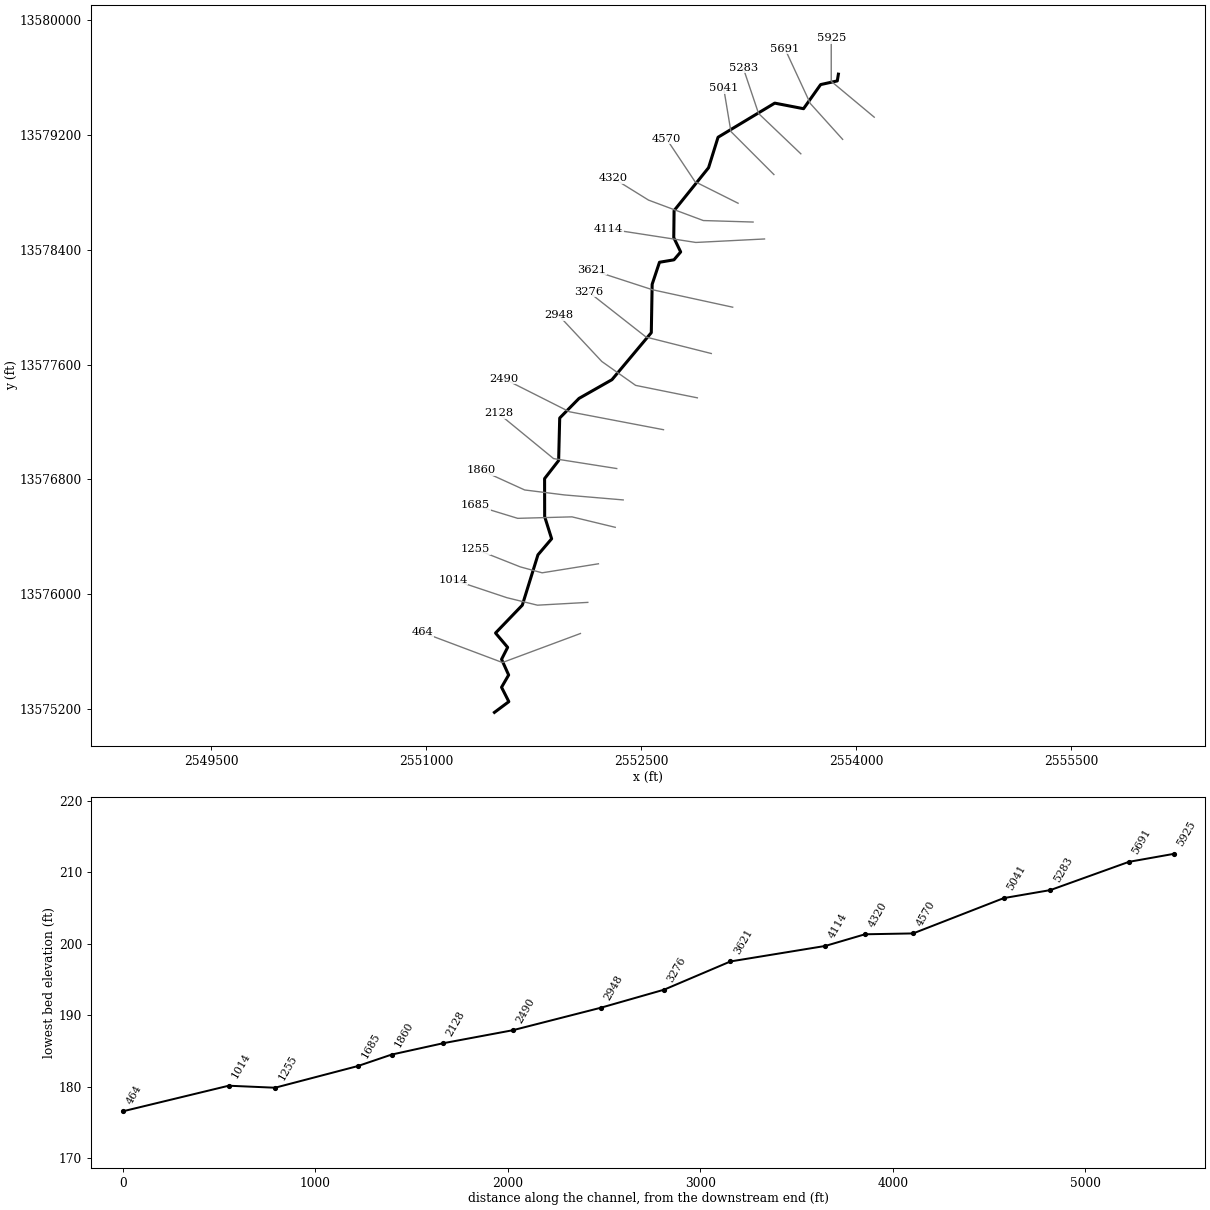
--- TRIB 1_3 TO IRISH CREEK.prj (project) ---

Proj Title=TRIB 1_3 TO IRISH CREEK Base Level Engineering
Current Plan=p01
Default Exp/Contr=0.3,0.1
English Units
Geom File=g01
Flow File=f01
Plan File=p01
BEGIN DESCRIPTION:
TRIB 1_3 TO IRISH CREEK
END DESCRIPTION:

--- TRIB 1_3 TO IRISH CREEK.p01 (plan) ---

Plan Title=Multiple Run
Short Identifier=Multiple
Geom File=g01
Flow File=f01
Subcritical Flow
K Sum by GR= 0
Std Step Tol= 0.01
Critical Tol= 0.01
Num of Std Step Trials= 20
Max Error Tol= 0.3
Flow Tol Ratio= 0.001
Split Flow NTrial= 30
Split Flow Tol= 0.02
Split Flow Ratio= 0.02
Log Output Level= 0
Friction Slope Method= 1
Unsteady Friction Slope Method= 2
Unsteady Bridges Friction Slope Method= 1
Parabolic Critical Depth
Global Vel Dist=  1 , 1 , 1
Global Log Level= 0
CheckData=True
Encroach Param= -1, 0, 0, 0
BEGIN DESCRIPTION:
Multiple Run
END DESCRIPTION:

--- TRIB 1_3 TO IRISH CREEK.f01 (steady flow) ---

Flow Title=Multiple
Number of Profiles=7
Profile Names=10-year,25-year,50-year,1pct_min,100-year,1pct_plu,500-year
River Rch & RM= TRIB 1_3 TO IRIS,Reach-1,5925
     477     754    1000     644    1285    2563    2096
River Rch & RM= TRIB 1_3 TO IRIS,Reach-1,4114
     643    1032    1384     899    1794    3580    2984
Boundary for River Rch & Prof#=TRIB 1_3 TO IRIS,Reach-1,1
Up Type=0
Dn Type=3
Dn Slope=0.005
Boundary for River Rch & Prof#=TRIB 1_3 TO IRIS,Reach-1,2
Up Type=0
Dn Type=3
Dn Slope=0.005
Boundary for River Rch & Prof#=TRIB 1_3 TO IRIS,Reach-1,3
Up Type=0
Dn Type=3
Dn Slope=0.005
Boundary for River Rch & Prof#=TRIB 1_3 TO IRIS,Reach-1,4
Up Type=0
Dn Type=3
Dn Slope=0.005
Boundary for River Rch & Prof#=TRIB 1_3 TO IRIS,Reach-1,5
Up Type=0
Dn Type=3
Dn Slope=0.005
Boundary for River Rch & Prof#=TRIB 1_3 TO IRIS,Reach-1,6
Up Type=0
Dn Type=3
Dn Slope=0.005
Boundary for River Rch & Prof#=TRIB 1_3 TO IRIS,Reach-1,7
Up Type=0
Dn Type=3
Dn Slope=0.005

--- TRIB 1_3 TO IRISH CREEK.g01 (geometry) ---

Geom Title=Existing Conditions

River Reach=TRIB 1_3 TO IRIS,Reach-1
Reach XY= 30
      2553875.00     13579625.00      2553867.23     13579577.85
      2553751.11     13579552.28      2553631.76     13579384.12
      2553430.86     13579422.94      2553035.38     13579185.11
      2552969.17     13578972.70      2552728.55     13578673.53
      2552726.24     13578485.50      2552774.47     13578385.45
      2552727.69     13578330.45      2552626.62     13578313.42
      2552575.52     13578159.79      2552569.54     13577822.55
      2552295.09     13577494.79      2552065.32     13577364.22
      2551930.46     13577227.45      2551922.93     13576930.86
      2551824.96     13576805.02      2551825.52     13576540.22
      2551874.06     13576385.48      2551778.62     13576273.50
      2551669.48     13575922.57      2551482.61     13575728.33
      2551567.15     13575628.41      2551524.81     13575545.20
      2551574.21     13575435.69      2551524.62     13575350.00
      2551575.55     13575249.92      2551475.00     13575175.00

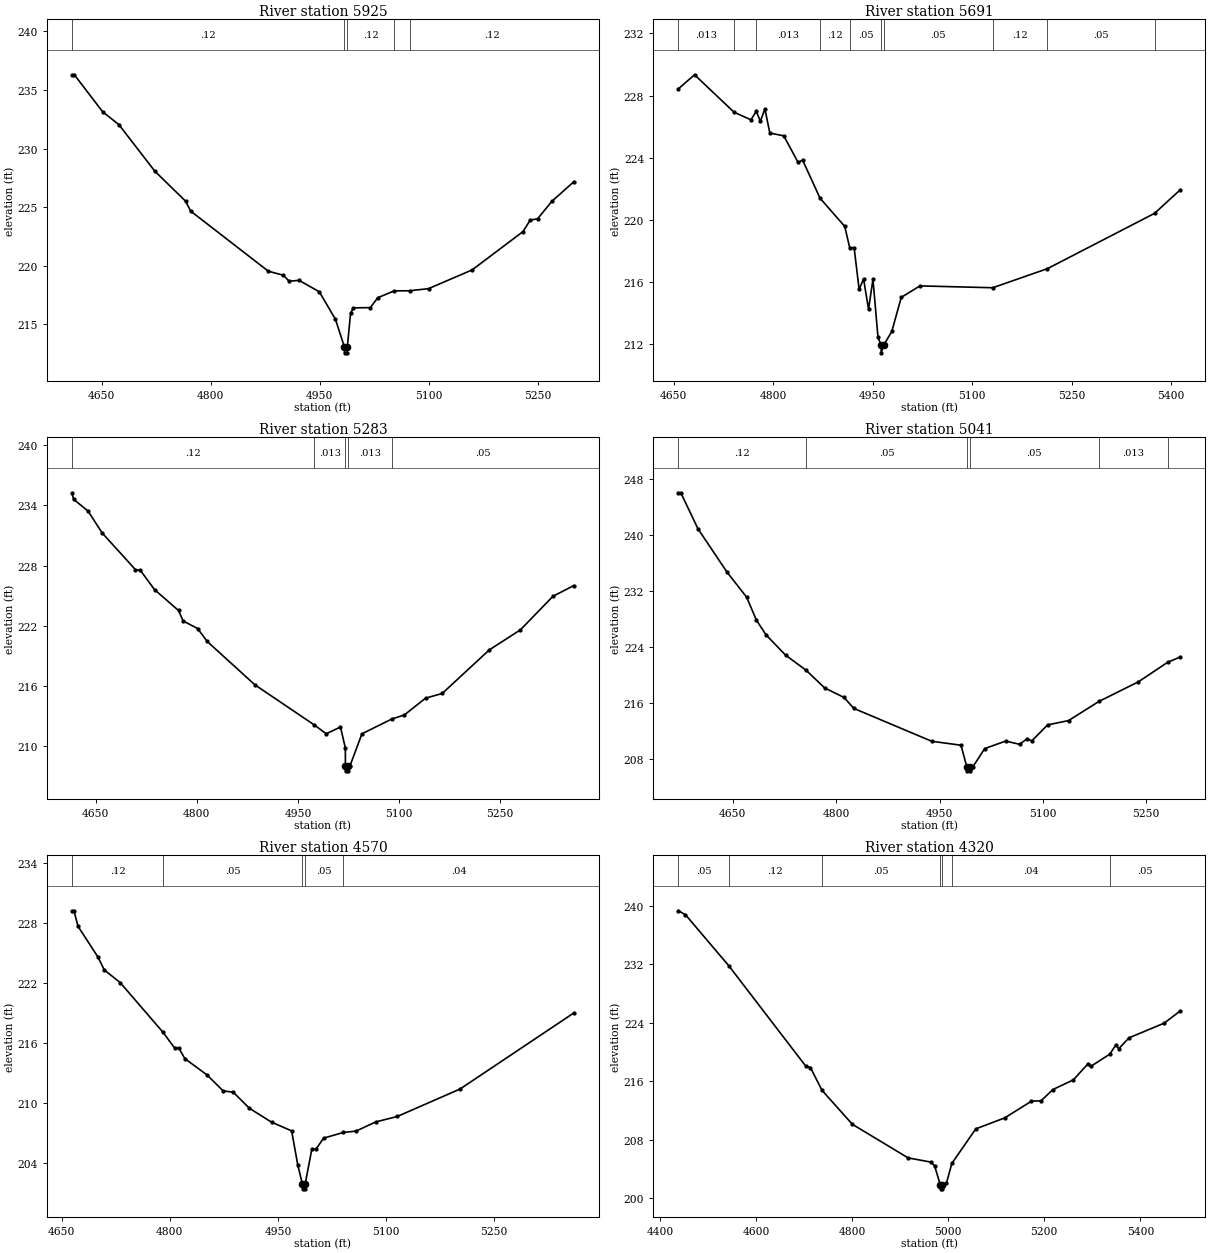
Type RM Length L Ch R = 1,5925,234,234,234
BEGIN DESCRIPTION:
TRIB 1_3 TO IRISH CREEK 12.0
END DESCRIPTION:
XS GIS Cut Line= 3
      2554125.04     13579324.97      2553825.00     13579575.00
      2553825.00     13579875.04
#Sta/Elev= 30
  4609.3  236.30  4612.6  236.30  4651.7  233.13  4673.8  232.05  4723.2  228.08
  4765.6  225.51  4772.7  224.66  4879.5  219.53  4900.3  219.18  4908.1  218.67
  4921.8  218.75  4949.7  217.77  4971.9  215.42  4984.2  213.06  4984.4  212.56
  4987.9  212.56  4988.2  213.06  4992.7  215.94  4996.6  216.40  5019.9  216.42
  5029.9  217.26  5052.6  217.85  5074.0  217.86  5099.9  218.04  5159.9  219.64
  5229.9  222.91  5239.9  223.90  5249.9  224.00  5269.9  225.51  5299.9  227.17
#Mann=5,-1,0
  4609.3    0.12       0  4984.2    0.05       0  4988.2    0.12       0
  5052.6    0.05       0  5074.0    0.12       0
Bank Sta=4984.2,4988.2
Exp/Cntr=0.3,0.1

Type RM Length L Ch R = 1,5691,408,408,408
BEGIN DESCRIPTION:
Mapping XS 09f8972e
END DESCRIPTION:
XS GIS Cut Line= 3
      2553904.70     13579170.27      2553679.01     13579420.27
      2553502.43     13579801.12
#Sta/Elev= 30
  4657.2  228.44  4681.5  229.34  4741.1  226.93  4766.6  226.44  4774.5  226.99
  4780.8  226.35  4787.6  227.14  4795.0  225.59  4816.0  225.41  4837.6  223.70
  4844.4  223.85  4870.6  221.40  4907.9  219.58  4915.4  218.21  4922.1  218.20
  4929.6  215.52  4936.3  216.20  4943.8  214.25  4950.5  216.18  4958.0  212.45
  4962.7  211.94  4962.9  211.44  4966.7  211.94  4978.9  212.82  4993.1  215.01
  5021.3  215.75  5131.0  215.63  5213.5  216.86  5375.0  220.42  5413.8  221.94
#Mann=10,-1,0
  4657.2   0.013       0  4741.1    0.12       0  4774.5   0.013       0
  4870.6    0.12       0  4915.4    0.05       0  4962.7    0.05       0
  4966.7    0.05       0  5131.0    0.12       0  5213.5    0.05       0
  5375.0    0.12       0
Bank Sta=4962.7,4966.7
Exp/Cntr=0.3,0.1

Type RM Length L Ch R = 1,5283,242,242,242
BEGIN DESCRIPTION:
Mapping XS 5e73a262
END DESCRIPTION:
XS GIS Cut Line= 3
      2553613.04     13579069.57      2553317.90     13579350.83
      2553210.32     13579670.10
#Sta/Elev= 30
  4614.7  235.27  4617.1  234.62  4638.5  233.45  4659.6  231.25  4708.9  227.59
  4716.2  227.52  4737.3  225.59  4772.8  223.51  4779.7  222.46  4801.1  221.71
  4815.3  220.42  4886.0  216.09  4973.7  212.10  4992.0  211.19  5013.1  211.87
  5020.3  209.77  5020.4  207.99  5020.6  207.49  5024.1  207.49  5024.4  207.99
  5027.2  207.99  5044.9  211.19  5089.3  212.67  5107.8  213.07  5139.3  214.75
  5164.0  215.22  5233.8  219.57  5280.1  221.58  5328.3  224.93  5359.3  226.00
#Mann=5,-1,0
  4614.7    0.12       0  4973.7   0.013       0  5020.4    0.03       0
  5024.4   0.013       0  5089.3    0.05       0
Bank Sta=5020.4,5024.4
Exp/Cntr=0.3,0.1

Type RM Length L Ch R = 1,5041,471,471,471
BEGIN DESCRIPTION:
TRIB 1_3 TO IRISH CREEK 10.0
END DESCRIPTION:
XS GIS Cut Line= 3
      2553424.99     13578925.01      2553125.00     13579225.00
      2553075.00     13579525.01
#Sta/Elev= 30
  4571.0  246.09  4574.5  246.09  4599.3  240.96  4641.7  234.73  4670.0  231.18
  4684.1  227.91  4698.3  225.78  4726.6  222.89  4756.4  220.73  4783.1  218.22
  4811.4  216.85  4825.5  215.29  4938.7  210.59  4981.1  210.03  4989.7  206.87
  4990.0  206.37  4993.5  206.37  4993.7  206.87  4997.8  206.87  5015.5  209.55
  5045.9  210.62  5066.2  210.16  5076.4  210.91  5084.0  210.66  5106.8  212.93
  5137.2  213.55  5181.4  216.29  5238.6  219.09  5280.8  221.86  5299.4  222.64
#Mann=6,-1,0
  4571.0    0.12       0  4756.4    0.05       0  4989.7    0.05       0
  4993.7    0.05       0  5181.4   0.013       0  5280.8    0.05       0
Bank Sta=4989.7,4993.7
Exp/Cntr=0.3,0.1

Type RM Length L Ch R = 1,4570,250,250,250
BEGIN DESCRIPTION:
TRIB 1_3 TO IRISH CREEK 9.0
END DESCRIPTION:
XS GIS Cut Line= 3
      2553174.98     13578725.01      2552875.00     13578875.00
      2552675.02     13579174.96
#Sta/Elev= 30
  4664.4  229.25  4667.2  229.25  4672.8  227.69  4700.7  224.60  4709.1  223.34
  4731.5  222.05  4790.8  217.08  4806.9  215.50  4812.5  215.53  4820.9  214.46
  4851.6  212.83  4874.0  211.23  4888.0  211.10  4910.3  209.50  4941.1  208.10
  4969.0  207.23  4977.4  203.86  4983.8  201.93  4984.1  201.43  4987.6  201.43
  4987.8  201.93  4997.0  205.40  5002.8  205.40  5013.3  206.50  5040.7  207.07
  5058.4  207.21  5085.4  208.12  5115.5  208.67  5202.6  211.42  5360.3  219.03
#Mann=5,-1,0
  4664.4    0.12       0  4790.8    0.05       0  4983.8    0.05       0
  4987.8    0.05       0  5040.7    0.04       0
Bank Sta=4983.8,4987.8
Exp/Cntr=0.3,0.1

Type RM Length L Ch R = 1,4320,206,206,206
BEGIN DESCRIPTION:
Mapping XS 5f6adae8
END DESCRIPTION:
XS GIS Cut Line= 4
      2553279.71     13578593.88      2552932.48     13578604.30
      2552550.53     13578746.66      2552304.03     13578899.43
#Sta/Elev= 30
  4438.2  239.31  4452.9  238.77  4542.8  231.82  4703.0  218.11  4713.0  217.89
  4737.2  214.77  4800.4  210.13  4916.4  205.54  4964.3  204.96  4971.7  204.43
  4983.7  201.81  4983.9  201.31  4987.4  201.31  4987.7  201.81  4996.3  202.10
  5007.5  204.79  5057.3  209.50  5118.0  211.02  5173.3  213.29  5193.2  213.34
  5217.9  214.88  5260.5  216.20  5291.2  218.42  5297.1  218.06  5336.3  219.71
  5349.1  221.00  5355.0  220.45  5376.2  221.94  5449.5  223.95  5483.2  225.63
#Mann=7,-1,0
  4438.2    0.05       0  4542.8    0.12       0  4737.2    0.05       0
  4983.7    0.05       0  4987.7    0.05       0  5007.5    0.04       0
  5336.3    0.05       0
Bank Sta=4983.7,4987.7
Exp/Cntr=0.3,0.1

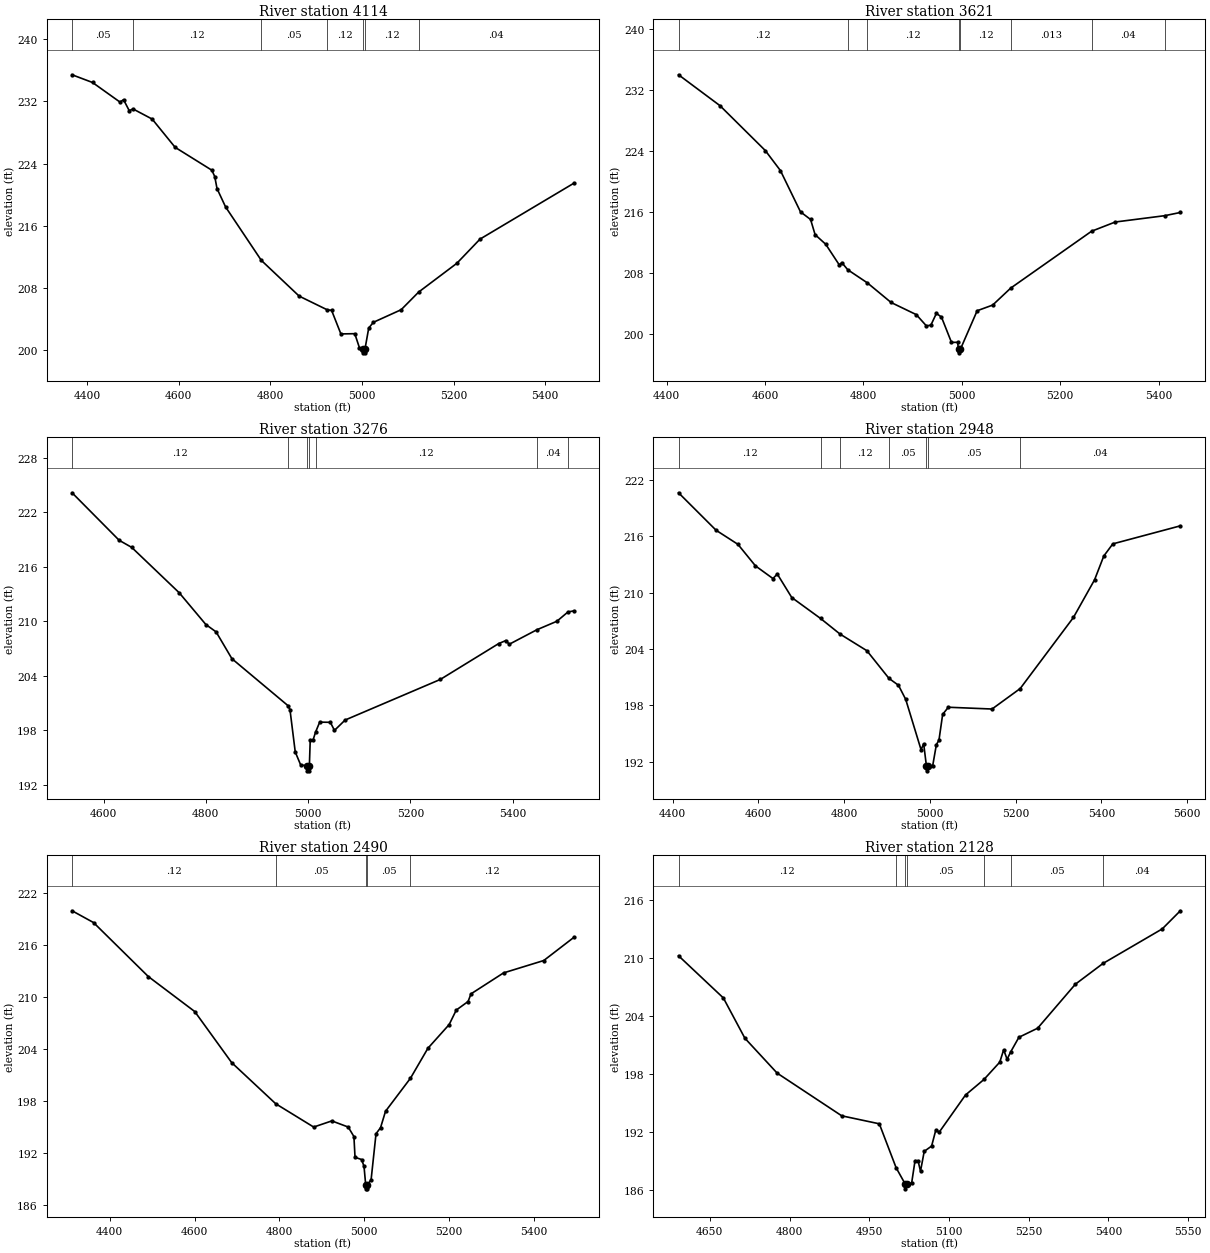
Type RM Length L Ch R = 1,4114,493,493,493
BEGIN DESCRIPTION:
Mapping XS 47bc7fcc
END DESCRIPTION:
XS GIS Cut Line= 3
      2553359.51     13578475.83      2552880.40     13578451.52
      2552272.72     13578545.28
#Sta/Elev= 30
  4367.8  235.40  4412.4  234.41  4472.4  231.89  4480.1  232.20  4492.5  230.79
  4500.8  231.01  4542.5  229.71  4592.6  226.08  4672.7  223.14  4679.0  222.33
  4684.0  220.78  4702.7  218.42  4780.6  211.56  4863.1  206.97  4924.3  205.21
  4933.9  205.14  4954.2  202.11  4984.5  202.14  4994.6  200.34  5002.8  200.18
  5003.0  199.68  5006.5  199.68  5006.8  200.18  5014.9  202.86  5025.0  203.60
  5085.7  205.22  5123.9  207.49  5207.1  211.18  5257.7  214.29  5462.4  221.47
#Mann=7,-1,0
  4367.8    0.05       0  4500.8    0.12       0  4780.6    0.05       0
  4924.3    0.12       0  5002.8    0.05       0  5006.8    0.12       0
  5123.9    0.04       0
Bank Sta=5002.8,5006.8
Exp/Cntr=0.3,0.1

Type RM Length L Ch R = 1,3621,345,345,345
BEGIN DESCRIPTION:
Mapping XS d91cbca3
END DESCRIPTION:
XS GIS Cut Line= 3
      2553137.38     13578000.13      2552578.31     13578121.66
      2552152.11     13578260.27
#Sta/Elev= 30
  4424.0  233.96  4508.3  229.91  4600.4  224.03  4631.1  221.41  4672.0  215.99
  4692.5  214.99  4701.7  213.00  4723.2  211.75  4750.9  209.03  4756.0  209.34
  4768.1  208.40  4808.0  206.68  4856.2  204.11  4907.4  202.52  4927.9  201.05
  4937.1  201.14  4948.3  202.68  4958.6  202.20  4979.0  198.88  4991.3  198.89
  4993.3  198.01  4993.5  197.51  4997.3  198.01  5031.2  203.03  5062.7  203.77
  5099.5  206.00  5263.8  213.45  5312.0  214.66  5412.7  215.49  5444.3  215.91
#Mann=8,-1,0
  4424.0    0.12       0  4768.1   0.013       0  4808.0    0.12       0
  4993.3    0.05       0  4997.3    0.12       0  5099.5   0.013       0
  5263.8    0.04       0  5412.7   0.013       0
Bank Sta=4993.3,4997.3
Exp/Cntr=0.3,0.1

Type RM Length L Ch R = 1,3276,328,328,328
BEGIN DESCRIPTION:
Mapping XS 974559ea
END DESCRIPTION:
XS GIS Cut Line= 3
      2552988.07     13577677.21      2552533.17     13577791.80
      2552130.42     13578107.75
#Sta/Elev= 30
  4538.5  224.16  4630.6  218.93  4655.1  218.15  4747.9  213.16  4800.1  209.66
  4820.1  208.85  4851.0  205.90  4960.7  200.73  4964.5  200.30  4974.8  195.64
  4985.1  194.25  4998.4  194.06  4998.7  193.56  5002.2  193.56  5002.4  194.06
  5004.1  196.95  5009.6  196.95  5014.6  197.83  5022.6  198.92  5043.4  198.90
  5051.5  198.01  5072.3  199.15  5258.5  203.62  5372.4  207.56  5386.6  207.90
  5393.2  207.49  5447.0  209.08  5486.3  210.02  5508.1  211.05  5519.5  211.16
#Mann=7,-1,0
  4538.5    0.12       0  4960.7    0.05       0  4998.4    0.05       0
  5002.4    0.05       0  5014.6    0.12       0  5447.0    0.04       0
  5508.1    0.12       0
Bank Sta=4998.4,5002.4
Exp/Cntr=0.3,0.1

Type RM Length L Ch R = 1,2948,458,458,458
BEGIN DESCRIPTION:
Mapping XS 97e44636
END DESCRIPTION:
XS GIS Cut Line= 4
      2552890.85     13577368.18      2552460.26     13577455.00
      2552224.15     13577621.66      2551922.03     13577944.61
#Sta/Elev= 30
  4413.6  220.64  4501.2  216.65  4552.2  215.15  4593.0  212.86  4633.8  211.51
  4644.0  211.99  4677.7  209.49  4744.9  207.26  4790.3  205.60  4852.9  203.83
  4904.5  200.88  4926.6  200.15  4943.5  198.65  4979.3  193.29  4985.4  193.92
  4991.9  191.54  4992.2  191.04  4995.9  191.54  5006.3  191.54  5015.0  193.82
  5021.1  194.31  5029.7  197.05  5042.9  197.81  5144.9  197.62  5210.6  199.80
  5334.8  207.37  5384.1  211.38  5405.6  213.91  5426.6  215.20  5584.1  217.12
#Mann=7,-1,0
  4413.6    0.12       0  4744.9    0.05       0  4790.3    0.12       0
  4904.5    0.05       0  4991.9    0.05       0  4995.9    0.05       0
  5210.6    0.04       0
Bank Sta=4991.9,4995.9
Exp/Cntr=0.3,0.1

Type RM Length L Ch R = 1,2490,362,362,362
BEGIN DESCRIPTION:
Mapping XS 6733a588
END DESCRIPTION:
XS GIS Cut Line= 3
      2552654.67     13577145.97      2551998.45     13577270.97
      2551538.35     13577502.75
#Sta/Elev= 30
  4311.3  219.98  4361.9  218.62  4491.1  212.39  4600.6  208.35  4687.6  202.46
  4791.5  197.71  4881.0  195.02  4923.8  195.73  4962.5  195.02  4975.9  193.92
  4978.5  191.53  4994.1  191.27  4999.7  190.48  5003.6  188.39  5003.8  187.89
  5007.3  187.89  5007.6  188.39  5016.4  188.93  5028.0  194.25  5038.7  194.95
  5050.4  196.84  5109.3  200.66  5150.3  204.11  5200.5  206.85  5217.2  208.52
  5245.1  209.51  5251.9  210.39  5328.7  212.81  5423.6  214.24  5494.5  216.91
#Mann=5,-1,0
  4311.3    0.12       0  4791.5    0.05       0  5003.6    0.05       0
  5007.6    0.05       0  5109.3    0.12       0
Bank Sta=5003.6,5007.6
Exp/Cntr=0.3,0.1

Type RM Length L Ch R = 1,2128,268,268,268
BEGIN DESCRIPTION:
Mapping XS 29cd680d
END DESCRIPTION:
XS GIS Cut Line= 3
      2552328.33     13576875.13      2551887.34     13576944.58
      2551502.24     13577260.29
#Sta/Elev= 30
  4591.1  210.26  4675.5  205.88  4716.0  201.70  4776.7  198.08  4898.2  193.65
  4969.0  192.82  5000.6  188.26  5017.7  186.57  5017.9  186.07  5021.7  186.57
  5029.8  186.66  5036.2  188.99  5041.8  188.99  5046.5  187.90  5053.5  189.96
  5067.4  190.51  5075.3  192.17  5081.7  191.95  5131.2  195.81  5165.9  197.42
  5195.7  199.22  5203.0  200.50  5209.5  199.52  5216.1  200.27  5231.7  201.80
  5266.9  202.74  5338.0  207.31  5389.9  209.46  5501.5  213.05  5535.5  214.93
#Mann=7,-1,0
  4591.1    0.12       0  5000.6    0.05       0  5017.7    0.05       0
  5021.7    0.05       0  5165.9    0.04       0  5216.1    0.05       0
  5389.9    0.04       0
Bank Sta=5017.7,5021.7
Exp/Cntr=0.3,0.1

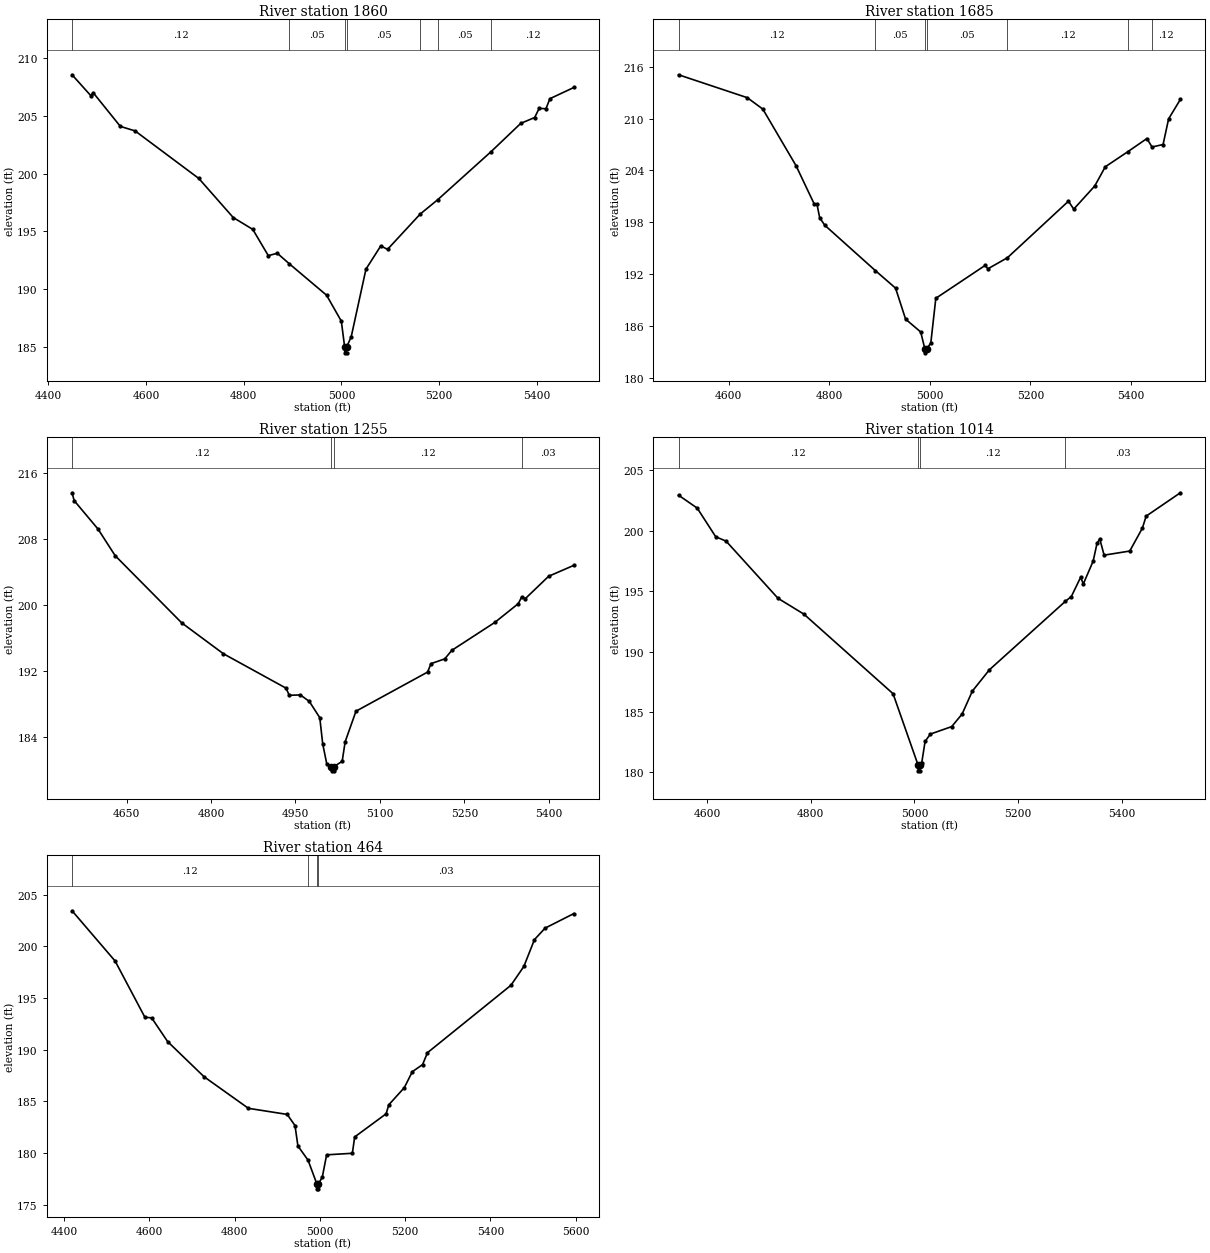
Type RM Length L Ch R = 1,1860,175,175,175
BEGIN DESCRIPTION:
Mapping XS 03d66876
END DESCRIPTION:
XS GIS Cut Line= 4
      2552373.48     13576656.38      2551963.73     13576691.11
      2551685.95     13576725.83      2551380.40     13576864.72
#Sta/Elev= 30
  4448.9  208.56  4487.1  206.76  4492.1  207.01  4547.7  204.09  4577.8  203.70
  4708.3  199.58  4778.6  196.20  4818.7  195.17  4850.4  192.90  4868.9  193.10
  4893.5  192.19  4969.7  189.47  4999.9  187.22  5006.7  184.98  5007.0  184.48
  5010.5  184.48  5010.7  184.98  5020.1  185.87  5050.3  191.73  5080.6  193.74
  5094.4  193.44  5161.3  196.50  5197.1  197.74  5306.5  201.91  5367.0  204.35
  5395.5  204.86  5404.7  205.65  5418.6  205.62  5426.7  206.49  5475.7  207.46
#Mann=7,-1,0
  4448.9    0.12       0  4893.5    0.05       0  5006.7    0.05       0
  5010.7    0.05       0  5161.3    0.04       0  5197.1    0.05       0
  5306.5    0.12       0
Bank Sta=5006.7,5010.7
Exp/Cntr=0.3,0.1

Type RM Length L Ch R = 1,1685,430,430,430
BEGIN DESCRIPTION:
Mapping XS 7b0412d9
END DESCRIPTION:
XS GIS Cut Line= 4
      2552317.92     13576465.41      2552015.81     13576538.33
      2551637.34     13576527.91      2551342.23     13576618.18
#Sta/Elev= 30
  4500.1  215.06  4636.8  212.41  4667.7  211.09  4733.7  204.55  4770.4  200.05
  4775.5  200.06  4780.9  198.50  4791.1  197.64  4891.7  192.39  4931.7  190.37
  4951.7  186.78  4981.8  185.29  4989.8  183.38  4990.0  182.88  4993.8  183.38
  5001.8  184.00  5011.8  189.19  5110.2  193.01  5115.2  192.60  5154.3  193.89
  5275.6  200.43  5286.1  199.51  5327.9  202.19  5348.8  204.41  5394.0  206.17
  5431.6  207.68  5441.8  206.70  5463.8  206.99  5474.8  209.96  5498.1  212.20
#Mann=7,-1,0
  4500.1    0.12       0  4891.7    0.05       0  4989.8    0.05       0
  4993.8    0.05       0  5154.3    0.12       0  5394.0    0.03       0
  5441.8    0.12       0
Bank Sta=4989.8,4993.8
Exp/Cntr=0.3,0.1

Type RM Length L Ch R = 1,1255,241,241,241
BEGIN DESCRIPTION:
Mapping XS a49b3885
END DESCRIPTION:
XS GIS Cut Line= 4
      2552200.53     13576211.08      2551807.70     13576148.14
      2551655.79     13576189.37      2551343.33     13576313.05
#Sta/Elev= 30
  4553.2  213.65  4556.9  212.70  4599.3  209.24  4629.7  206.01  4747.9  197.84
  4822.1  194.08  4933.5  189.89  4938.9  189.03  4958.6  189.08  4974.6  188.29
  4993.2  186.31  4998.4  183.13  5005.7  180.66  5014.0  180.35  5014.3  179.85
  5017.8  179.85  5018.0  180.35  5033.0  181.01  5038.2  183.37  5057.5  187.10
  5184.6  191.85  5190.8  192.88  5215.2  193.46  5227.6  194.49  5304.3  197.90
  5345.9  200.18  5351.6  200.96  5358.4  200.79  5399.7  203.50  5444.5  204.83
#Mann=4,-1,0
  4553.2    0.12       0  5014.0    0.05       0  5018.0    0.12       0
  5351.6    0.03       0
Bank Sta=5014,5018
Exp/Cntr=0.3,0.1

Type RM Length L Ch R = 1,1014,550,550,550
BEGIN DESCRIPTION:
Mapping XS fb1237e0
END DESCRIPTION:
XS GIS Cut Line= 4
      2552126.66     13575941.97      2551775.14     13575922.44
      2551562.47     13575974.53      2551185.48     13576100.19
#Sta/Elev= 30
  4544.8  202.93  4580.9  201.86  4616.6  199.49  4636.6  199.13  4736.8  194.40
  4786.8  193.09  4958.8  186.51  5006.9  180.63  5007.2  180.13  5010.7  180.13
  5010.9  180.63  5014.1  180.78  5020.6  182.56  5030.8  183.17  5072.0  183.79
  5092.1  184.83  5111.9  186.73  5144.8  188.49  5291.3  194.15  5302.9  194.55
  5320.8  196.14  5326.0  195.59  5345.0  197.48  5352.4  198.94  5357.7  199.32
  5366.1  197.97  5415.6  198.31  5439.9  200.20  5447.3  201.20  5513.2  203.13
#Mann=4,-1,0
  4544.8    0.12       0  5006.9    0.05       0  5010.9    0.12       0
  5291.3    0.03       0
Bank Sta=5006.9,5010.9
Exp/Cntr=0.3,0.1

Type RM Length L Ch R = 1,464,0,0,0
BEGIN DESCRIPTION:
TRIB 1_3 TO IRISH CREEK 1.0
END DESCRIPTION:
XS GIS Cut Line= 3
      2552074.96     13575724.98      2551530.75     13575522.67
      2550972.95     13575732.33
#Sta/Elev= 30
  4419.1  203.45  4520.0  198.59  4589.8  193.15  4605.7  193.09  4643.1  190.80
  4728.4  187.40  4832.5  184.34  4923.5  183.75  4941.8  182.67  4948.6  180.70
  4972.4  179.32  4992.8  177.05  4993.0  176.55  4996.5  176.55  4996.8  177.05
  5005.8  177.68  5015.9  179.84  5076.3  179.99  5081.7  181.57  5155.4  183.81
  5161.7  184.68  5198.1  186.34  5216.8  187.88  5240.9  188.57  5252.4  189.72
  5448.0  196.24  5478.3  198.06  5503.2  200.66  5528.1  201.77  5595.6  203.18
#Mann=4,-1,0
  4419.1    0.12       0  4972.4    0.03       0  4992.8    0.03       0
  4996.8    0.03       0
Bank Sta=4992.8,4996.8
Exp/Cntr=0.3,0.1

Chan Stop Cuts=-1