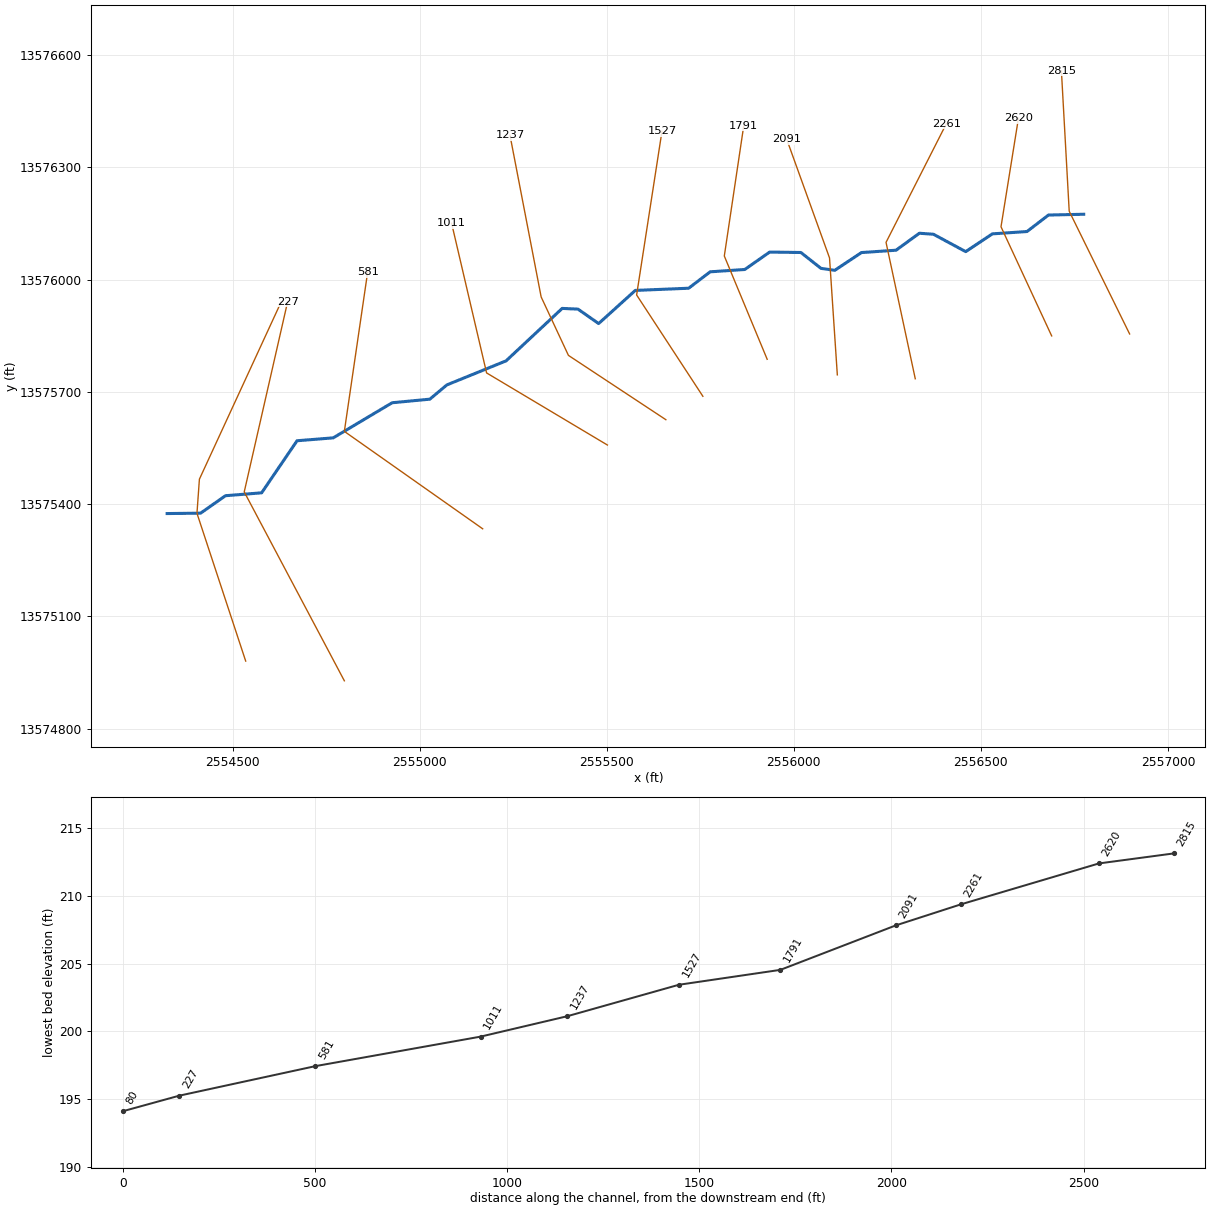
--- TRIB 1_4 TO IRISH CREEK.prj (project) ---

Proj Title=TRIB 1_4 TO IRISH CREEK Base Level Engineering
Current Plan=p01
Default Exp/Contr=0.3,0.1
English Units
Geom File=g01
Flow File=f01
Plan File=p01
BEGIN DESCRIPTION:
TRIB 1_4 TO IRISH CREEK
END DESCRIPTION:

--- TRIB 1_4 TO IRISH CREEK.p01 (plan) ---

Plan Title=Multiple Run
Short Identifier=Multiple
Geom File=g01
Flow File=f01
Subcritical Flow
K Sum by GR= 0
Std Step Tol= 0.01
Critical Tol= 0.01
Num of Std Step Trials= 20
Max Error Tol= 0.3
Flow Tol Ratio= 0.001
Split Flow NTrial= 30
Split Flow Tol= 0.02
Split Flow Ratio= 0.02
Log Output Level= 0
Friction Slope Method= 1
Unsteady Friction Slope Method= 2
Unsteady Bridges Friction Slope Method= 1
Parabolic Critical Depth
Global Vel Dist=  1 , 1 , 1
Global Log Level= 0
CheckData=True
Encroach Param= -1, 0, 0, 0
BEGIN DESCRIPTION:
Multiple Run
END DESCRIPTION:

--- TRIB 1_4 TO IRISH CREEK.f01 (steady flow) ---

Flow Title=Multiple
Number of Profiles=7
Profile Names=10-year,25-year,50-year,1pct_min,100-year,1pct_plu,500-year
River Rch & RM= TRIB 1_4 TO IRIS,Reach-1,2815
     465     733     970     624    1244    2483    2022
River Rch & RM= TRIB 1_4 TO IRIS,Reach-1,2261
     613     982    1313     852    1699    3391    2816
Boundary for River Rch & Prof#=TRIB 1_4 TO IRIS,Reach-1,1
Up Type=0
Dn Type=3
Dn Slope=0.005
Boundary for River Rch & Prof#=TRIB 1_4 TO IRIS,Reach-1,2
Up Type=0
Dn Type=3
Dn Slope=0.005
Boundary for River Rch & Prof#=TRIB 1_4 TO IRIS,Reach-1,3
Up Type=0
Dn Type=3
Dn Slope=0.005
Boundary for River Rch & Prof#=TRIB 1_4 TO IRIS,Reach-1,4
Up Type=0
Dn Type=3
Dn Slope=0.005
Boundary for River Rch & Prof#=TRIB 1_4 TO IRIS,Reach-1,5
Up Type=0
Dn Type=3
Dn Slope=0.005
Boundary for River Rch & Prof#=TRIB 1_4 TO IRIS,Reach-1,6
Up Type=0
Dn Type=3
Dn Slope=0.005
Boundary for River Rch & Prof#=TRIB 1_4 TO IRIS,Reach-1,7
Up Type=0
Dn Type=3
Dn Slope=0.005

--- TRIB 1_4 TO IRISH CREEK.g01 (geometry) ---

Geom Title=Existing Conditions

River Reach=TRIB 1_4 TO IRIS,Reach-1
Reach XY= 30
      2556775.00     13576175.00      2556680.87     13576172.90
      2556623.42     13576128.83      2556530.97     13576122.62
      2556459.60     13576075.10      2556373.28     13576121.60
      2556335.69     13576124.23      2556273.42     13576078.89
      2556180.97     13576072.62      2556109.61     13576025.09
      2556072.82     13576030.38      2556019.03     13576072.81
      2555935.55     13576073.90      2555869.03     13576027.36
      2555776.60     13576021.14      2555719.06     13575977.27
      2555576.47     13575971.43      2555478.40     13575882.84
      2555423.35     13575921.41      2555381.05     13575923.34
      2555231.06     13575783.14      2555072.82     13575718.88
      2555027.32     13575680.77      2554926.58     13575671.17
      2554769.03     13575577.34      2554672.33     13575569.58
      2554577.67     13575430.42      2554480.97     13575422.66
      2554414.58     13575376.02      2554325.00     13575375.00

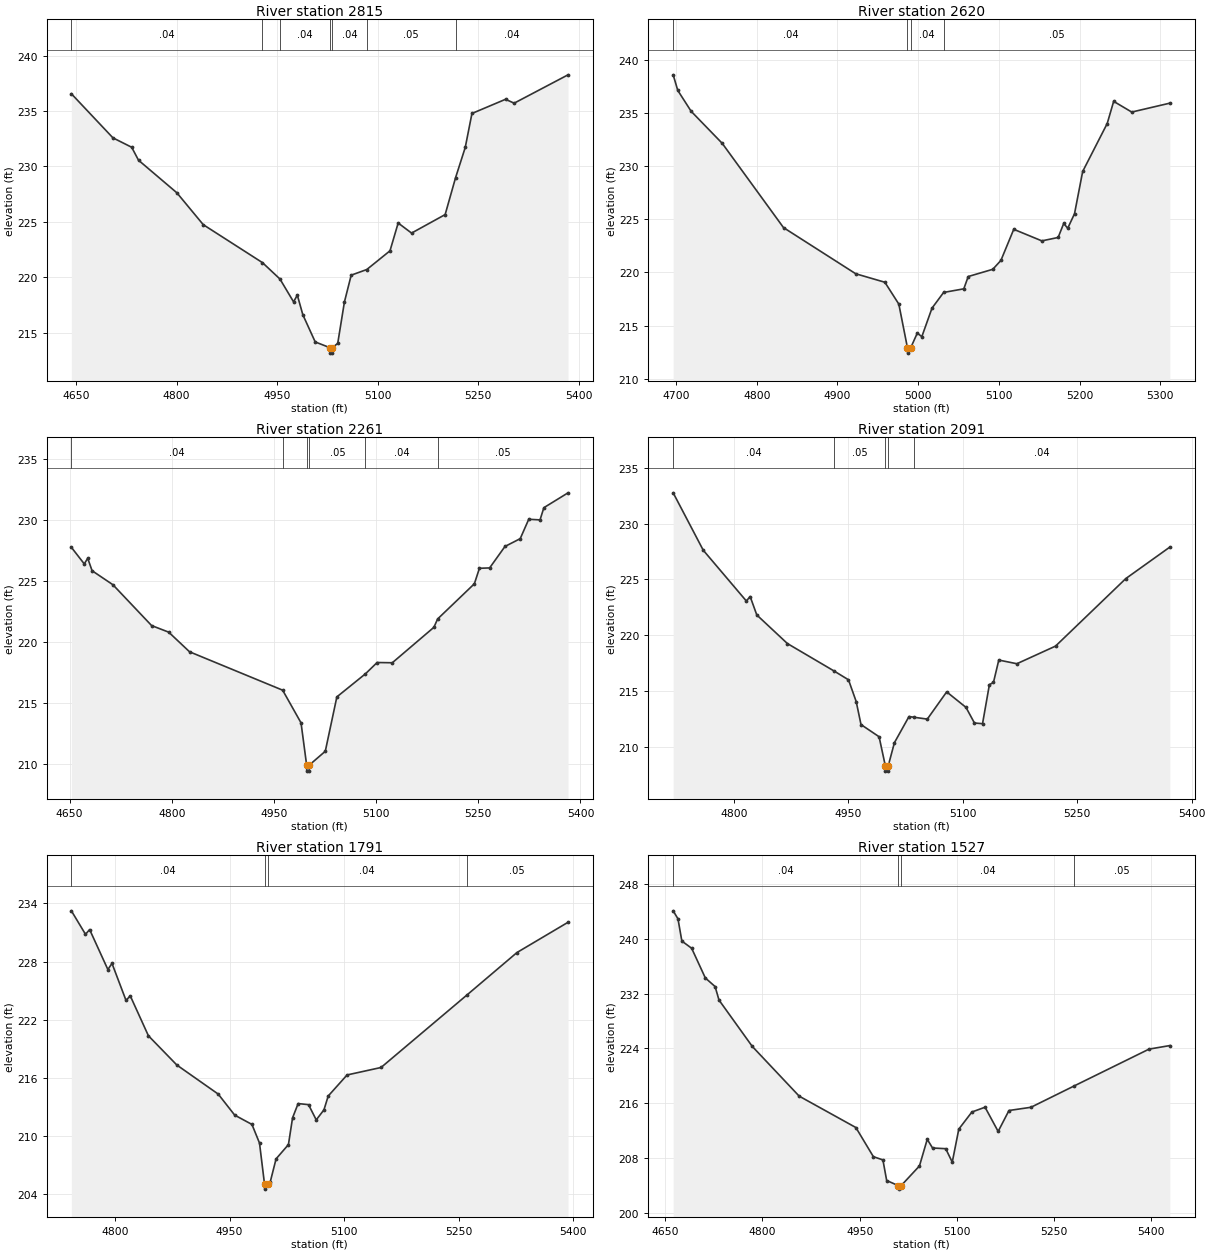
Type RM Length L Ch R = 1,2815,195,195,195
BEGIN DESCRIPTION:
Mapping XS f18ea7a1
END DESCRIPTION:
XS GIS Cut Line= 3
      2556897.70     13575855.10      2556736.26     13576183.19
      2556715.43     13576558.15
#Sta/Elev= 30
  4643.0  236.56  4705.0  232.58  4733.0  231.73  4743.2  230.56  4800.4  227.62
  4839.8  224.74  4928.2  221.31  4954.3  219.83  4974.6  217.77  4980.2  218.38
  4988.4  216.61  5006.9  214.15  5028.5  213.64  5028.8  213.14  5032.3  213.14
  5032.5  213.64  5040.5  214.02  5050.5  217.76  5060.6  220.18  5083.9  220.69
  5118.5  222.38  5130.7  224.89  5150.7  223.98  5200.8  225.65  5216.4  228.99
  5230.8  231.71  5240.8  234.78  5290.9  236.06  5303.8  235.71  5384.2  238.27
#Mann=7,-1,0
  4643.0    0.04       0  4928.2    0.05       0  4954.3    0.04       0
  5028.5    0.04       0  5032.5    0.04       0  5083.9    0.05       0
  5216.4    0.04       0
Bank Sta=5028.5,5032.5
Exp/Cntr=0.3,0.1

Type RM Length L Ch R = 1,2620,359,359,359
BEGIN DESCRIPTION:
Mapping XS bb4523b0
END DESCRIPTION:
XS GIS Cut Line= 3
      2556689.39     13575849.85      2556553.96     13576141.53
      2556600.59     13576431.62
#Sta/Elev= 30
  4696.5  238.63  4702.2  237.16  4718.8  235.19  4757.3  232.17  4833.2  224.23
  4922.7  219.88  4958.8  219.08  4976.1  217.02  4986.8  212.90  4987.1  212.40
  4990.8  212.90  4999.0  214.29  5004.6  213.95  5017.2  216.64  5031.6  218.12
  5056.6  218.46  5062.1  219.62  5092.5  220.30  5102.6  221.14  5118.5  224.07
  5153.3  222.98  5173.5  223.30  5180.4  224.62  5185.4  224.17  5193.8  225.54
  5203.9  229.52  5234.3  234.04  5242.3  236.13  5264.7  235.12  5311.9  235.96
#Mann=4,-1,0
  4696.5    0.04       0  4986.8    0.04       0  4990.8    0.04       0
  5031.6    0.05       0
Bank Sta=4986.8,4990.8
Exp/Cntr=0.3,0.1

Type RM Length L Ch R = 1,2261,170,170,170
BEGIN DESCRIPTION:
Mapping XS 1524fbef
END DESCRIPTION:
XS GIS Cut Line= 3
      2556324.79     13575735.32      2556246.67     13576099.86
      2556408.13     13576417.57
#Sta/Elev= 30
  4652.5  227.74  4671.4  226.38  4676.5  226.84  4682.9  225.82  4713.5  224.67
  4770.3  221.32  4795.4  220.78  4826.0  219.17  4962.7  216.02  4989.7  213.34
  4997.9  209.88  4998.1  209.38  5001.6  209.38  5001.9  209.88  5025.3  211.01
  5042.3  215.47  5084.2  217.36  5101.4  218.29  5123.7  218.27  5184.8  221.18
  5190.2  221.86  5244.2  224.75  5251.6  226.02  5266.6  226.05  5289.1  227.81
  5311.5  228.45  5324.0  230.04  5340.6  229.99  5346.2  230.99  5381.7  232.21
#Mann=6,-1,0
  4652.5    0.04       0  4962.7    0.05       0  4997.9    0.05       0
  5001.9    0.05       0  5084.2    0.04       0  5190.2    0.05       0
Bank Sta=4997.9,5001.9
Exp/Cntr=0.3,0.1

Type RM Length L Ch R = 1,2091,300,300,300
BEGIN DESCRIPTION:
Mapping XS c10d6f51
END DESCRIPTION:
XS GIS Cut Line= 3
      2556116.47     13575745.67      2556095.63     13576058.19
      2555981.03     13576375.94
#Sta/Elev= 30
  4720.4  232.75  4759.8  227.61  4816.3  223.06  4821.3  223.46  4830.0  221.81
  4870.1  219.25  4931.3  216.79  4950.2  216.00  4960.3  214.05  4966.6  211.99
  4990.3  210.90  4998.4  208.32  4998.6  207.82  5002.1  207.82  5002.4  208.32
  5010.4  210.37  5029.5  212.71  5036.6  212.64  5053.5  212.48  5078.9  214.92
  5104.2  213.53  5115.3  212.13  5125.9  212.07  5134.9  215.57  5140.2  215.76
  5147.2  217.77  5170.9  217.44  5221.6  219.02  5313.7  225.07  5371.4  227.89
#Mann=5,-1,0
  4720.4    0.04       0  4931.3    0.05       0  4998.4    0.05       0
  5002.4    0.05       0  5036.6    0.04       0
Bank Sta=4998.4,5002.4
Exp/Cntr=0.3,0.1

Type RM Length L Ch R = 1,1791,264,264,264
BEGIN DESCRIPTION:
Mapping XS 76edc43c
END DESCRIPTION:
XS GIS Cut Line= 3
      2555928.95     13575787.40      2555814.38     13576063.40
      2555866.29     13576411.21
#Sta/Elev= 30
  4742.8  233.23  4761.3  230.81  4766.7  231.30  4790.6  227.18  4796.0  227.81
  4814.4  223.99  4819.9  224.47  4843.7  220.35  4881.0  217.33  4935.1  214.34
  4956.7  212.17  4979.3  211.21  4989.2  209.29  4995.8  205.04  4996.0  204.54
  4999.8  205.04  5003.2  205.26  5010.9  207.66  5027.1  209.13  5032.5  211.89
  5039.8  213.36  5053.4  213.25  5063.5  211.68  5073.6  212.71  5079.2  214.14
  5103.9  216.31  5148.4  217.08  5260.4  224.52  5326.4  228.93  5393.3  232.05
#Mann=4,-1,0
  4742.8    0.04       0  4995.8    0.04       0  4999.8    0.04       0
  5260.4    0.05       0
Bank Sta=4995.8,4999.8
Exp/Cntr=0.3,0.1

Type RM Length L Ch R = 1,1527,290,290,290
BEGIN DESCRIPTION:
Mapping XS c78dcc38
END DESCRIPTION:
XS GIS Cut Line= 3
      2555757.08     13575688.42      2555580.01     13575959.24
      2555647.72     13576396.76
#Sta/Elev= 30
  4662.3  244.11  4669.7  242.94  4675.7  239.69  4690.8  238.64  4711.9  234.30
  4727.0  233.04  4733.0  231.07  4784.3  224.30  4856.7  217.03  4944.2  212.44
  4971.2  208.18  4985.9  207.71  4991.7  204.70  5009.9  203.94  5010.2  203.44
  5013.9  203.94  5042.3  206.83  5054.3  210.72  5062.5  209.45  5082.8  209.35
  5092.9  207.38  5103.0  212.21  5123.2  214.71  5143.5  215.41  5163.7  211.87
  5180.4  214.93  5214.3  215.40  5281.0  218.52  5396.5  223.90  5428.6  224.42
#Mann=4,-1,0
  4662.3    0.04       0  5009.9    0.04       0  5013.9    0.04       0
  5281.0    0.05       0
Bank Sta=5009.9,5013.9
Exp/Cntr=0.3,0.1

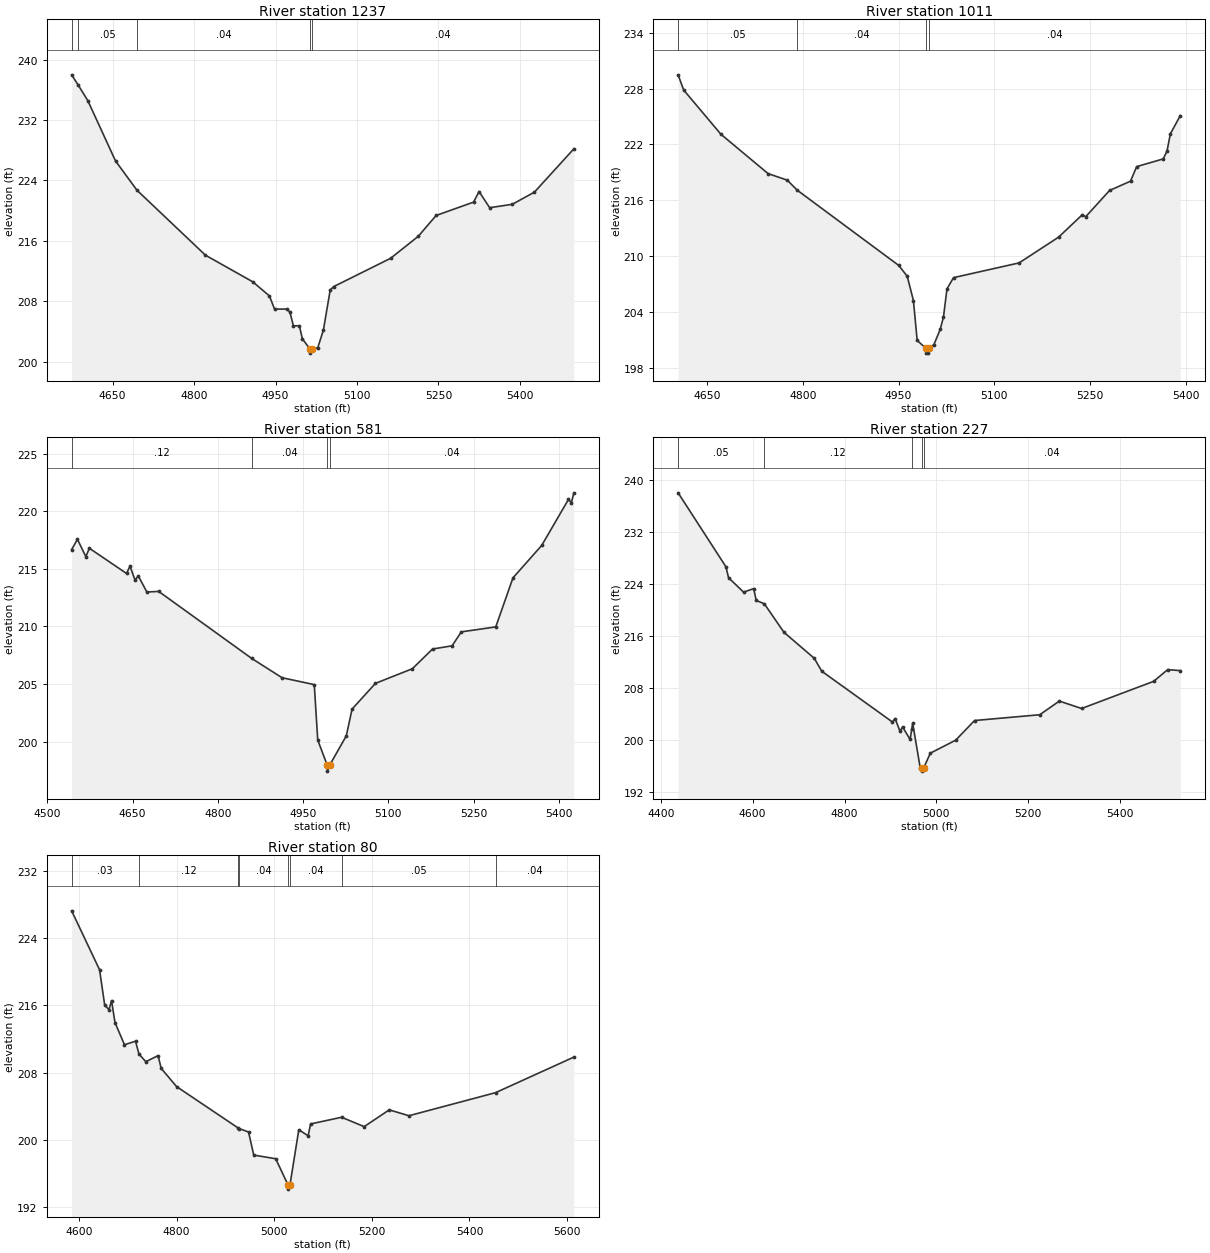
Type RM Length L Ch R = 1,1237,226,226,226
BEGIN DESCRIPTION:
Mapping XS 4ec6ec71
END DESCRIPTION:
XS GIS Cut Line= 4
      2555658.13     13575625.90      2555397.71     13575797.78
      2555324.80     13575954.03      2555241.46     13576386.32
#Sta/Elev= 30
  4574.6  237.98  4586.8  236.61  4604.3  234.57  4655.4  226.57  4694.8  222.70
  4821.0  214.09  4908.0  210.57  4938.7  208.70  4948.2  206.96  4971.1  206.95
  4976.6  206.54  4982.9  204.73  4993.9  204.75  4999.4  203.02  5014.0  201.62
  5014.2  201.12  5018.0  201.62  5027.8  201.84  5038.1  204.16  5050.7  209.48
  5056.8  209.92  5161.9  213.68  5212.8  216.59  5245.7  219.35  5314.6  221.12
  5324.8  222.52  5344.3  220.38  5385.9  220.83  5426.7  222.44  5499.3  228.18
#Mann=5,-1,0
  4574.6    0.04       0  4586.8    0.05       0  4694.8    0.04       0
  5014.0    0.04       0  5018.0    0.04       0
Bank Sta=5014,5018
Exp/Cntr=0.3,0.1

Type RM Length L Ch R = 1,1011,430,430,430
BEGIN DESCRIPTION:
Mapping XS aa0688ab
END DESCRIPTION:
XS GIS Cut Line= 3
      2555501.88     13575558.19      2555178.96     13575750.90
      2555085.44     13576150.97
#Sta/Elev= 30
  4604.6  229.47  4613.3  227.84  4671.7  223.09  4745.6  218.87  4775.6  218.17
  4791.3  217.09  4950.3  209.02  4963.6  207.86  4973.3  205.25  4979.2  200.97
  4993.1  200.11  4993.4  199.61  4996.9  199.61  4997.1  200.11  5005.4  200.52
  5015.3  202.16  5020.4  203.49  5025.9  206.51  5036.2  207.71  5138.9  209.29
  5200.7  212.05  5238.1  214.47  5243.2  214.24  5280.6  217.06  5313.5  218.06
  5323.1  219.62  5364.8  220.45  5370.7  221.30  5375.9  223.13  5391.5  225.10
#Mann=4,-1,0
  4604.6    0.05       0  4791.3    0.04       0  4993.1    0.04       0
  4997.1    0.04       0
Bank Sta=4993.1,4997.1
Exp/Cntr=0.3,0.1

Type RM Length L Ch R = 1,581,354,354,354
BEGIN DESCRIPTION:
Mapping XS 4bd9bbe3
END DESCRIPTION:
XS GIS Cut Line= 3
      2555168.54     13575334.24      2554798.76     13575594.65
      2554861.12     13576020.83
#Sta/Elev= 30
  4543.0  216.67  4553.2  217.55  4568.0  216.05  4574.1  216.78  4639.5  214.59
  4645.6  215.23  4654.3  214.03  4660.4  214.36  4675.2  212.98  4696.1  213.03
  4859.7  207.21  4912.9  205.54  4969.6  204.94  4975.7  200.13  4992.5  197.93
  4992.8  197.43  4996.5  197.93  5025.9  200.49  5036.1  202.82  5077.2  205.05
  5142.1  206.32  5177.5  208.03  5212.0  208.31  5228.1  209.52  5288.7  209.95
  5319.0  214.21  5369.6  217.03  5416.6  221.02  5421.7  220.73  5426.0  221.59
#Mann=4,-1,0
  4543.0    0.12       0  4859.7    0.04       0  4992.5    0.04       0
  4996.5    0.04       0
Bank Sta=4992.5,4996.5
Exp/Cntr=0.3,0.1

Type RM Length L Ch R = 1,227,147,147,147
BEGIN DESCRIPTION:
TRIB 1_4 TO IRISH CREEK 1.0
END DESCRIPTION:
XS GIS Cut Line= 3
      2554798.76     13574927.97      2554531.17     13575432.86
      2554647.29     13575941.76
#Sta/Elev= 30
  4437.7  238.04  4541.8  226.67  4547.5  224.99  4580.2  222.77  4602.2  223.31
  4607.8  221.49  4625.4  220.98  4668.2  216.59  4734.1  212.60  4750.5  210.61
  4904.4  202.80  4910.1  203.33  4920.8  201.38  4926.4  202.04  4942.8  200.12
  4946.5  201.77  4948.4  202.62  4964.8  195.76  4968.4  195.75  4968.7  195.25
  4972.4  195.75  4986.8  198.01  5042.1  200.01  5083.1  203.03  5225.1  203.92
  5267.7  206.02  5316.2  204.88  5472.9  209.05  5503.7  210.86  5531.1  210.70
#Mann=5,-1,0
  4437.7    0.05       0  4625.4    0.12       0  4946.5    0.04       0
  4968.4    0.04       0  4972.4    0.04       0
Bank Sta=4968.4,4972.4
Exp/Cntr=0.3,0.1

Type RM Length L Ch R = 1,80,0,0,0
BEGIN DESCRIPTION:
TRIB 1_4 TO IRISH CREEK 0.5
END DESCRIPTION:
XS GIS Cut Line= 4
      2554535.04     13574980.69      2554404.82     13575375.69
      2554411.33     13575466.84      2554629.77     13575940.50
#Sta/Elev= 30
  4585.0  227.28  4642.2  220.25  4652.7  216.05  4661.5  215.49  4666.7  216.58
  4673.8  213.96  4693.2  211.32  4715.9  211.73  4722.9  210.21  4737.0  209.29
  4762.0  210.02  4768.5  208.49  4800.1  206.32  4925.9  201.40  4928.2  201.32
  4947.4  200.91  4958.1  198.16  5003.1  197.72  5028.3  194.60  5028.6  194.10
  5032.3  194.60  5050.4  201.18  5069.5  200.46  5074.5  201.87  5138.1  202.67
  5184.3  201.55  5235.7  203.55  5276.1  202.85  5453.5  205.60  5613.9  209.84
#Mann=8,-1,0
  4585.0    0.03       0  4722.9    0.12       0  4925.9    0.03       0
  4928.2    0.04       0  5028.3    0.04       0  5032.3    0.04       0
  5138.1    0.05       0  5453.5    0.04       0
Bank Sta=5028.3,5032.3
Exp/Cntr=0.3,0.1

Chan Stop Cuts=-1