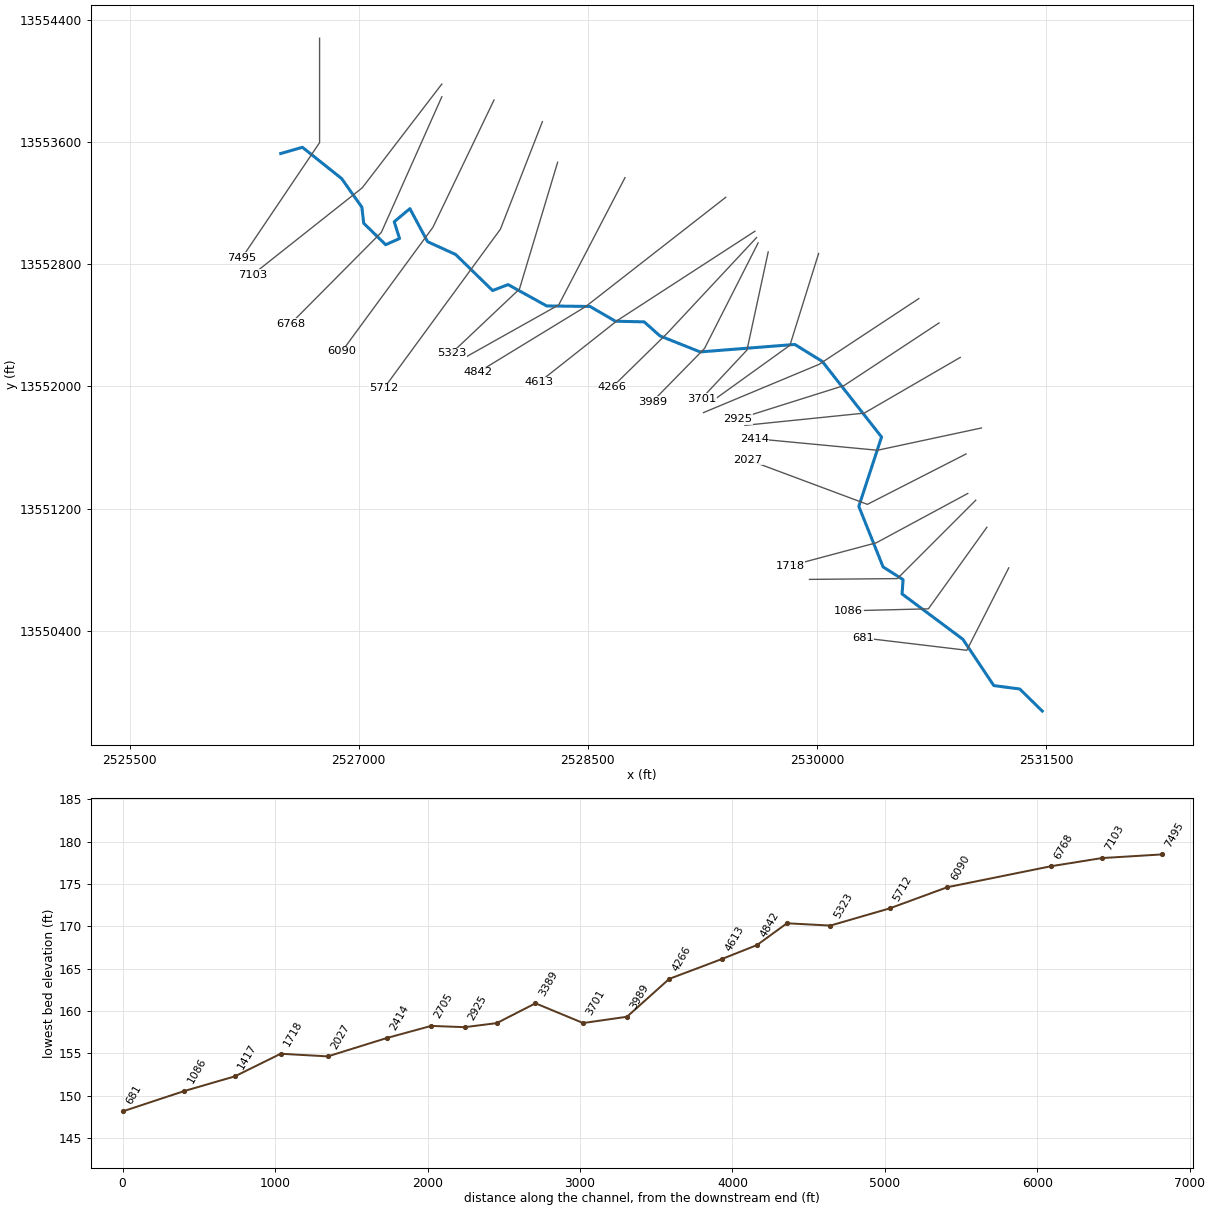
--- TRIB 2 TO CARLISLE CREEK.prj (project) ---

Proj Title=TRIB 2 TO CARLISLE CREEK Base Level Engineering
Current Plan=p01
Default Exp/Contr=0.3,0.1
English Units
Geom File=g01
Flow File=f01
Plan File=p01
BEGIN DESCRIPTION:
TRIB 2 TO CARLISLE CREEK
END DESCRIPTION:

--- TRIB 2 TO CARLISLE CREEK.p01 (plan) ---

Plan Title=Multiple Run
Short Identifier=Multiple
Geom File=g01
Flow File=f01
Subcritical Flow
K Sum by GR= 0
Std Step Tol= 0.01
Critical Tol= 0.01
Num of Std Step Trials= 20
Max Error Tol= 0.3
Flow Tol Ratio= 0.001
Split Flow NTrial= 30
Split Flow Tol= 0.02
Split Flow Ratio= 0.02
Log Output Level= 0
Friction Slope Method= 1
Unsteady Friction Slope Method= 2
Unsteady Bridges Friction Slope Method= 1
Parabolic Critical Depth
Global Vel Dist=  1 , 1 , 1
Global Log Level= 0
CheckData=True
Encroach Param= -1, 0, 0, 0
BEGIN DESCRIPTION:
Multiple Run
END DESCRIPTION:

--- TRIB 2 TO CARLISLE CREEK.f01 (steady flow) ---

Flow Title=Multiple
Number of Profiles=7
Profile Names=10-year,25-year,50-year,1pct_min,100-year,1pct_plu,500-year
River Rch & RM= TRIB 2 TO CARLIS,Reach-1,7495
     726    1179    1591    1041    2077    4145    3504
River Rch & RM= TRIB 2 TO CARLIS,Reach-1,7103
     950    1563    2129    1404    2801    5588    4798
River Rch & RM= TRIB 2 TO CARLIS,Reach-1,4613
    1178    1962    2693    1788    3567    7117    6199
River Rch & RM= TRIB 2 TO CARLIS,Reach-1,2925
    1335    2229    3063    2033    4057    8095    7045
Boundary for River Rch & Prof#=TRIB 2 TO CARLIS,Reach-1,1
Up Type=0
Dn Type=3
Dn Slope=0.005
Boundary for River Rch & Prof#=TRIB 2 TO CARLIS,Reach-1,2
Up Type=0
Dn Type=3
Dn Slope=0.005
Boundary for River Rch & Prof#=TRIB 2 TO CARLIS,Reach-1,3
Up Type=0
Dn Type=3
Dn Slope=0.005
Boundary for River Rch & Prof#=TRIB 2 TO CARLIS,Reach-1,4
Up Type=0
Dn Type=3
Dn Slope=0.005
Boundary for River Rch & Prof#=TRIB 2 TO CARLIS,Reach-1,5
Up Type=0
Dn Type=3
Dn Slope=0.005
Boundary for River Rch & Prof#=TRIB 2 TO CARLIS,Reach-1,6
Up Type=0
Dn Type=3
Dn Slope=0.005
Boundary for River Rch & Prof#=TRIB 2 TO CARLIS,Reach-1,7
Up Type=0
Dn Type=3
Dn Slope=0.005

--- TRIB 2 TO CARLISLE CREEK.g01 (geometry) ---

Geom Title=Existing Conditions

River Reach=TRIB 2 TO CARLIS,Reach-1
Reach XY= 30
      2526489.62     13553525.00      2526631.73     13553565.92
      2526888.24     13553361.38      2527021.17     13553173.41
      2527032.86     13553068.83      2527176.68     13552928.08
      2527267.62     13552968.57      2527232.82     13553078.44
      2527335.31     13553164.18      2527451.16     13552947.85
      2527634.68     13552864.24      2527876.65     13552628.16
      2527978.31     13552666.93      2528230.93     13552527.24
      2528514.50     13552523.80      2528680.93     13552427.24
      2528869.14     13552422.93      2528972.71     13552330.85
      2529235.50     13552226.22      2529855.02     13552275.04
      2530034.68     13552164.22      2530423.04     13551669.11
      2530274.22     13551214.95      2530433.03     13550818.66
      2530563.88     13550735.31      2530557.47     13550641.65
      2530955.21     13550345.09      2531158.20     13550041.42
      2531327.45     13550019.54      2531475.00     13549875.00

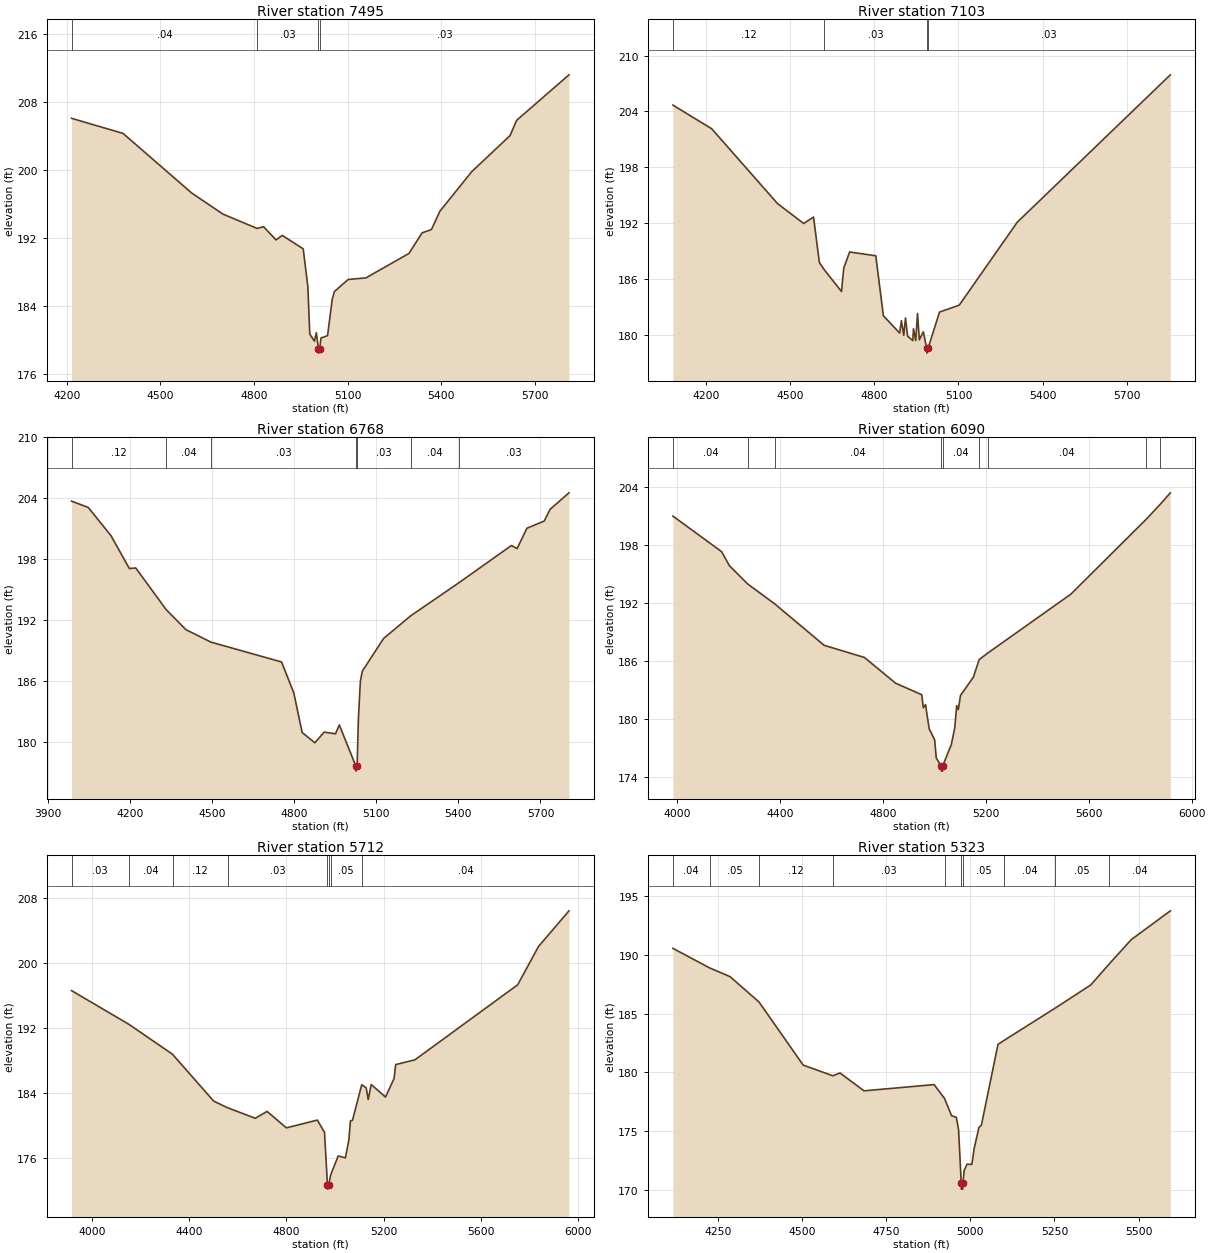
Type RM Length L Ch R = 1,7495,392,392,392
BEGIN DESCRIPTION:
LGII3449
END DESCRIPTION:
XS GIS Cut Line= 3
      2526744.11     13554279.96      2526744.11     13553596.35
      2526235.61     13552841.93
#Sta/Elev= 30
  4215.4  206.13  4380.4  204.35  4600.4  197.33  4700.4  194.85  4810.0  193.16
  4830.4  193.37  4870.4  191.81  4890.4  192.34  4957.5  190.76  4972.4  186.31
  4978.5  180.72  4993.5  179.89  4999.5  180.89  5006.4  178.98  5006.7  178.48
  5010.4  178.98  5014.5  180.26  5035.5  180.54  5050.4  184.81  5057.4  185.73
  5101.4  187.15  5158.4  187.34  5296.3  190.22  5338.3  192.64  5368.2  193.03
  5395.3  195.19  5497.2  199.84  5620.1  204.10  5641.1  205.89  5808.8  211.25
#Mann=4,-1,0
  4215.4    0.04       0  4810.0    0.03       0  5006.4    0.03       0
  5010.4    0.03       0
Bank Sta=5006.4,5010.4
Exp/Cntr=0.3,0.1

Type RM Length L Ch R = 1,7103,335,335,335
BEGIN DESCRIPTION:
LGII3448
END DESCRIPTION:
XS GIS Cut Line= 3
      2527544.38     13553979.81      2527023.37     13553300.42
      2526302.66     13552729.68
#Sta/Elev= 30
  4080.8  204.68  4219.3  202.14  4454.1  194.11  4547.5  191.97  4582.8  192.66
  4603.6  187.78  4621.4  186.99  4682.5  184.67  4690.7  187.19  4711.6  188.91
  4805.0  188.50  4832.1  182.06  4890.1  180.21  4896.4  181.53  4904.7  179.96
  4911.0  181.83  4918.6  179.87  4937.0  179.40  4939.5  180.66  4947.5  179.40
  4953.9  182.31  4960.4  179.48  4974.7  180.34  4986.8  178.55  4987.2  178.05
  4991.4  178.55  5032.4  182.46  5102.9  183.20  5309.7  192.10  5856.3  207.93
#Mann=4,-1,0
  4080.8    0.12       0  4621.4    0.03       0  4986.8    0.03       0
  4991.4    0.03       0
Bank Sta=4986.8,4991.4
Exp/Cntr=0.3,0.1

Type RM Length L Ch R = 1,6768,678,678,678
BEGIN DESCRIPTION:
LGII3447
END DESCRIPTION:
XS GIS Cut Line= 3
      2527544.39     13553896.48      2527148.41     13553008.65
      2526553.15     13552409.23
#Sta/Elev= 30
  3987.3  203.72  4048.2  203.10  4131.3  200.32  4198.5  197.07  4221.7  197.13
  4332.8  193.02  4405.0  191.04  4496.4  189.81  4754.5  187.85  4799.2  184.79
  4829.7  180.89  4875.8  179.88  4910.3  180.93  4951.3  180.76  4965.4  181.64
  5025.7  177.58  5026.1  177.08  5030.4  177.58  5035.1  182.25  5042.2  185.93
  5049.3  186.94  5127.1  190.17  5226.4  192.41  5402.8  195.68  5593.8  199.34
  5614.9  199.04  5650.3  201.04  5713.9  201.76  5735.2  202.91  5804.2  204.54
#Mann=7,-1,0
  3987.3    0.12       0  4332.8    0.04       0  4496.4    0.03       0
  5025.7    0.03       0  5030.4    0.03       0  5226.4    0.04       0
  5402.8    0.03       0
Bank Sta=5025.7,5030.4
Exp/Cntr=0.3,0.1

Type RM Length L Ch R = 1,6090,378,378,378
BEGIN DESCRIPTION:
LGII3446
END DESCRIPTION:
XS GIS Cut Line= 3
      2527886.16     13553875.61      2527486.03     13553042.00
      2526890.27     13552229.60
#Sta/Elev= 30
  3985.1  201.02  4174.3  197.34  4204.7  195.88  4275.7  193.99  4380.1  191.94
  4572.6  187.64  4729.0  186.38  4849.9  183.72  4951.6  182.52  4957.8  181.17
  4966.3  181.50  4980.5  179.00  5001.8  177.84  5008.0  175.97  5027.7  175.11
  5028.1  174.61  5032.1  174.61  5032.4  175.11  5066.6  177.37  5079.7  179.07
  5087.5  181.39  5093.7  180.98  5102.1  182.44  5152.3  184.35  5174.7  186.16
  5207.7  186.83  5530.5  192.93  5824.2  200.71  5878.3  202.25  5917.2  203.43
#Mann=9,-1,0
  3985.1    0.04       0  4275.7    0.12       0  4380.1    0.04       0
  5027.7    0.04       0  5032.4    0.04       0  5174.7    0.03       0
  5207.7    0.04       0  5824.2    0.03       0  5878.3   0.013       0
Bank Sta=5027.7,5032.4
Exp/Cntr=0.3,0.1

Type RM Length L Ch R = 1,5712,389,389,389
BEGIN DESCRIPTION:
LGII3445
END DESCRIPTION:
XS GIS Cut Line= 3
      2528202.92     13553733.86      2527927.84     13553029.49
      2527165.99     13551988.71
#Sta/Elev= 30
  3916.6  196.58  4152.2  192.43  4332.0  188.73  4501.2  182.96  4558.4  182.14
  4672.5  180.84  4720.8  181.69  4800.3  179.66  4927.7  180.62  4957.1  179.11
  4969.3  172.61  4969.7  172.11  4974.1  172.61  4982.6  173.87  5013.4  176.20
  5042.8  175.96  5057.4  178.18  5063.6  180.51  5072.1  180.59  5110.2  184.98
  5128.5  184.60  5136.9  183.16  5149.3  185.00  5208.0  183.46  5243.5  185.76
  5249.7  187.46  5329.2  188.05  5751.5  197.29  5837.2  202.01  5962.6  206.41
#Mann=8,-1,0
  3916.6    0.03       0  4152.2    0.04       0  4332.0    0.12       0
  4558.4    0.03       0  4969.3    0.05       0  4974.1    0.03       0
  4982.6    0.05       0  5110.2    0.04       0
Bank Sta=4969.3,4974.1
Exp/Cntr=0.3,0.1

Type RM Length L Ch R = 1,5323,285,285,285
BEGIN DESCRIPTION:
Mapping XS 92e7bf75
END DESCRIPTION:
XS GIS Cut Line= 3
      2528302.59     13553467.81      2528052.58     13552637.93
      2527608.16     13552217.80
#Sta/Elev= 30
  4116.1  190.56  4225.5  188.89  4286.1  188.15  4372.2  185.99  4503.3  180.63
  4591.4  179.72  4612.8  179.96  4684.0  178.44  4892.4  178.97  4923.4  177.79
  4944.1  176.33  4958.4  176.19  4965.0  175.16  4973.0  170.58  4973.3  170.08
  4977.5  170.08  4977.9  170.58  4981.7  171.67  4990.4  172.20  5004.5  172.18
  5011.4  173.54  5025.6  175.32  5032.9  175.52  5082.2  182.39  5100.3  182.73
  5250.8  185.45  5358.1  187.45  5413.0  189.24  5478.3  191.30  5594.4  193.75
#Mann=10,-1,0
  4116.1    0.04       0  4225.5    0.05       0  4372.2    0.12       0
  4591.4    0.03       0  4923.4    0.05       0  4973.0    0.05       0
  4977.9    0.05       0  5100.3    0.04       0  5250.8    0.05       0
  5413.0    0.04       0
Bank Sta=4973,4977.9
Exp/Cntr=0.3,0.1

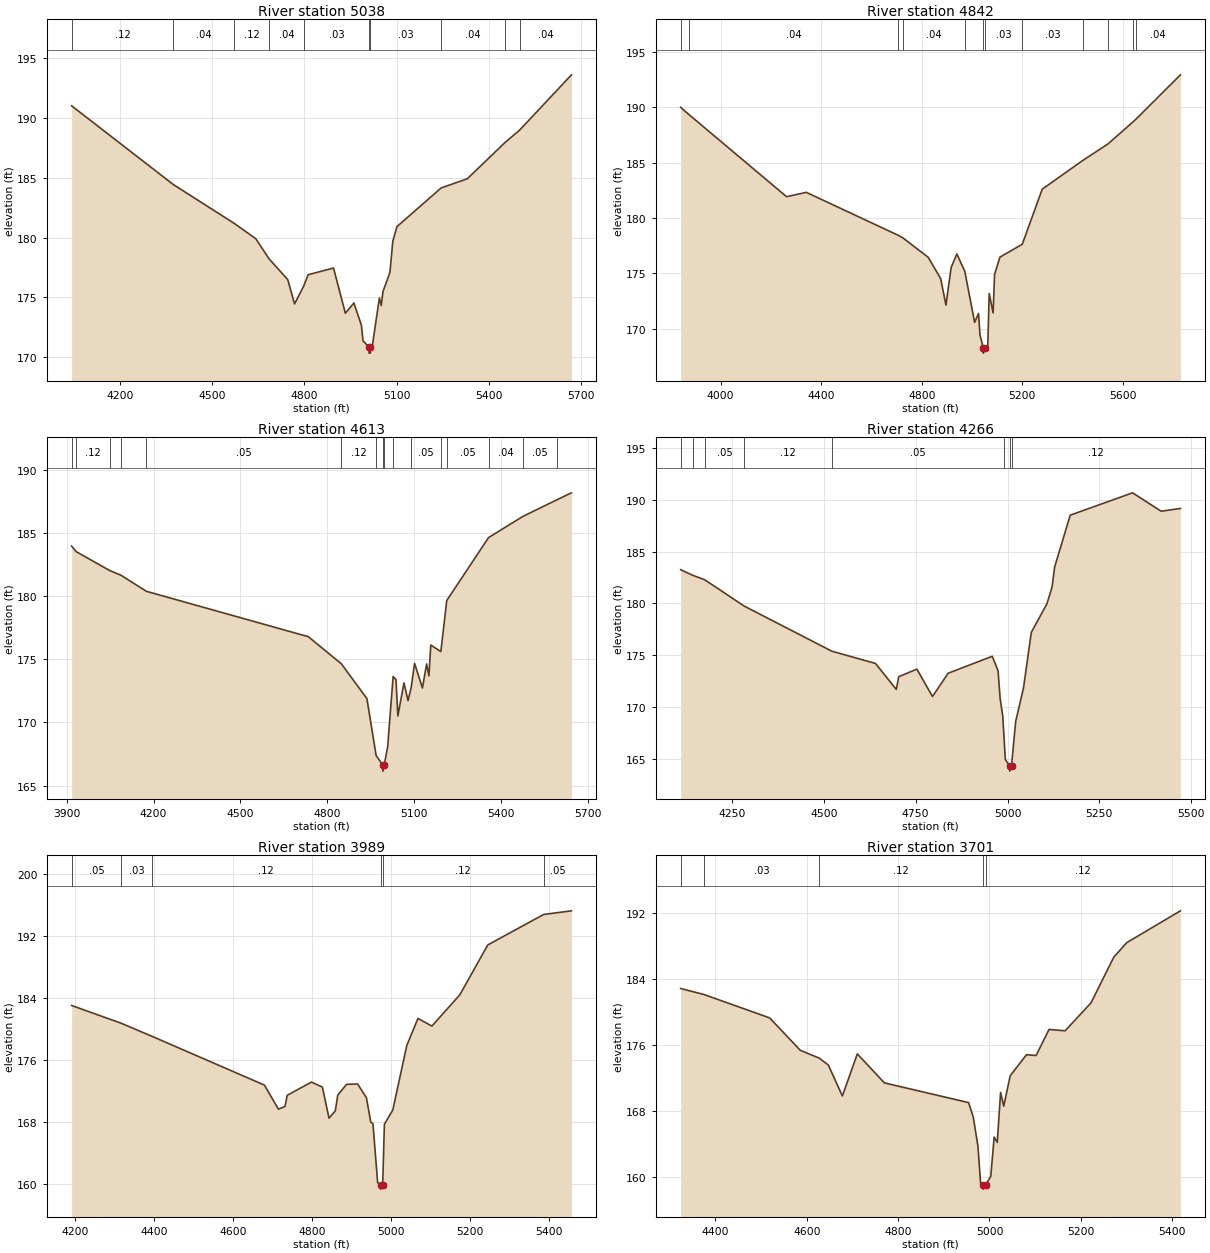
Type RM Length L Ch R = 1,5038,196,196,196
BEGIN DESCRIPTION:
Mapping XS 1e178cf0
END DESCRIPTION:
XS GIS Cut Line= 3
      2528743.57     13553367.11      2528309.53     13552533.76
      2527709.43     13552197.29
#Sta/Elev= 30
  4041.9  191.01  4372.7  184.44  4571.9  181.18  4641.9  179.90  4684.7  178.23
  4745.7  176.49  4767.8  174.46  4797.5  175.95  4812.0  176.90  4894.7  177.46
  4933.3  173.68  4961.0  174.54  4985.4  172.69  4990.8  171.38  5010.1  170.85
  5010.4  170.35  5014.6  170.35  5015.0  170.85  5021.1  170.94  5044.0  174.96
  5050.1  174.33  5055.9  175.50  5078.4  177.10  5087.8  179.71  5101.3  180.92
  5245.2  184.15  5330.6  184.92  5452.0  187.92  5500.7  188.98  5669.5  193.60
#Mann=10,-1,0
  4041.9    0.12       0  4372.7    0.04       0  4571.9    0.12       0
  4684.7    0.04       0  4797.5    0.03       0  5010.1    0.03       0
  5015.0    0.03       0  5245.2    0.04       0  5452.0    0.05       0
  5500.7    0.04       0
Bank Sta=5010.1,5015
Exp/Cntr=0.3,0.1

Type RM Length L Ch R = 1,4842,229,229,229
BEGIN DESCRIPTION:
Mapping XS ada4530a
END DESCRIPTION:
XS GIS Cut Line= 3
      2529403.25     13553238.60      2528486.61     13552523.34
      2527781.78     13552092.80
#Sta/Elev= 30
  3840.7  190.01  3872.6  189.38  4262.2  181.93  4340.9  182.32  4706.2  178.44
  4727.0  178.17  4825.7  176.45  4875.5  174.51  4896.3  172.12  4917.1  175.53
  4939.7  176.75  4971.2  175.19  5010.5  170.56  5025.9  171.37  5031.8  169.42
  5044.6  168.28  5045.0  167.78  5049.8  168.28  5062.7  168.45  5068.5  173.17
  5084.0  171.42  5089.8  174.89  5111.1  176.46  5200.1  177.63  5279.5  182.61
  5441.8  185.22  5539.9  186.68  5640.1  188.68  5653.2  188.96  5829.3  192.95
#Mann=12,-1,0
  3840.7    0.03       0  3872.6    0.04       0  4706.2    0.05       0
  4727.0    0.04       0  4971.2    0.03       0  5044.6    0.03       0
  5049.8    0.03       0  5200.1    0.03       0  5441.8    0.05       0
  5539.9    0.04       0  5640.1   0.013       0  5653.2    0.04       0
Bank Sta=5044.6,5049.8
Exp/Cntr=0.3,0.1

Type RM Length L Ch R = 1,4613,347,347,347
BEGIN DESCRIPTION:
Mapping XS 415729e2
END DESCRIPTION:
XS GIS Cut Line= 3
      2529594.21     13553016.37      2528694.95     13552433.06
      2528181.02     13552026.78
#Sta/Elev= 30
  3916.9  183.98  3933.0  183.54  4048.1  182.05  4086.9  181.68  4175.1  180.40
  4734.8  176.80  4848.9  174.65  4937.2  171.89  4969.1  167.37  4991.8  166.64
  4992.2  166.14  4997.1  166.64  5008.8  168.07  5027.8  173.65  5037.7  173.39
  5044.1  170.52  5065.2  173.14  5079.3  171.73  5090.4  172.81  5101.8  174.69
  5129.0  172.73  5143.4  174.64  5151.5  173.70  5157.9  176.14  5192.6  175.62
  5213.1  179.67  5357.4  184.66  5476.2  186.34  5594.8  187.67  5643.9  188.21
#Mann=16,-1,0
  3916.9    0.05       0  3933.0    0.12       0  4048.1   0.013       0
  4086.9    0.12       0  4175.1    0.05       0  4848.9    0.12       0
  4969.1    0.05       0  4991.8    0.05       0  4997.1    0.05       0
  5027.8    0.12       0  5090.4    0.05       0  5192.6    0.12       0
  5213.1    0.05       0  5357.4    0.04       0  5476.2    0.05       0
  5594.8    0.04       0
Bank Sta=4991.8,4997.1
Exp/Cntr=0.3,0.1

Type RM Length L Ch R = 1,4266,277,277,277
BEGIN DESCRIPTION:
Mapping XS 83acd0bc
END DESCRIPTION:
XS GIS Cut Line= 3
      2529604.67     13552974.73      2529017.86     13552346.26
      2528660.24     13551995.58
#Sta/Elev= 30
  4110.1  183.25  4142.9  182.71  4175.5  182.28  4282.8  179.74  4521.9  175.37
  4640.5  174.19  4697.1  171.68  4704.0  172.91  4753.3  173.64  4795.8  170.99
  4838.3  173.24  4958.5  174.88  4974.4  173.48  4979.9  170.80  4987.1  169.10
  4990.8  166.89  4994.1  164.91  5005.6  164.28  5006.0  163.78  5010.9  164.28
  5022.3  168.59  5043.6  171.82  5064.8  177.19  5107.2  179.94  5121.4  181.58
  5128.4  183.52  5170.8  188.52  5340.5  190.68  5418.4  188.90  5470.8  189.17
#Mann=8,-1,0
  4110.1    0.05       0  4142.9    0.12       0  4175.5    0.05       0
  4282.8    0.12       0  4521.9    0.05       0  4990.8    0.12       0
  5005.6    0.05       0  5010.9    0.12       0
Bank Sta=5005.6,5010.9
Exp/Cntr=0.3,0.1

Type RM Length L Ch R = 1,3989,288,288,288
BEGIN DESCRIPTION:
Mapping XS b39da356
END DESCRIPTION:
XS GIS Cut Line= 3
      2529615.07     13552939.98      2529264.39     13552249.04
      2528921.49     13551899.20
#Sta/Elev= 30
  4192.1  183.05  4317.3  180.76  4394.7  179.08  4679.9  172.76  4715.3  169.65
  4732.0  169.99  4737.6  171.44  4798.8  173.15  4826.6  172.50  4843.3  168.49
  4859.3  169.43  4865.5  171.47  4887.8  172.86  4915.7  172.90  4937.9  171.14
  4949.0  167.98  4954.6  167.75  4966.4  160.15  4973.7  159.81  4974.1  159.31
  4979.1  159.81  4983.5  167.71  5004.7  169.53  5040.1  177.87  5068.4  181.38
  5103.7  180.39  5174.4  184.43  5245.1  190.88  5386.5  194.82  5456.8  195.29
#Mann=6,-1,0
  4192.1    0.05       0  4317.3    0.03       0  4394.7    0.12       0
  4973.7    0.05       0  4979.1    0.12       0  5386.5    0.05       0
Bank Sta=4973.7,4979.1
Exp/Cntr=0.3,0.1

Type RM Length L Ch R = 1,3701,312,312,312
BEGIN DESCRIPTION:
Mapping XS 17d0437e
END DESCRIPTION:
XS GIS Cut Line= 3
      2529681.05     13552880.97      2529542.17     13552238.62
      2529243.95     13551919.60
#Sta/Elev= 30
  4324.0  182.82  4374.7  182.10  4518.8  179.27  4585.9  175.35  4627.2  174.41
  4647.3  173.57  4678.0  169.83  4710.7  174.92  4770.0  171.41  4954.2  169.03
  4964.4  167.31  4974.7  163.78  4980.5  159.31  4985.9  159.07  4986.3  158.57
  4991.5  159.07  5002.8  160.11  5010.2  164.85  5017.0  164.23  5024.3  170.26
  5031.2  168.60  5045.3  172.27  5081.0  174.82  5102.0  174.72  5130.3  177.87
  5165.5  177.71  5222.2  181.08  5272.0  186.61  5300.3  188.36  5417.9  192.21
#Mann=5,-1,0
  4324.0    0.05       0  4374.7    0.03       0  4627.2    0.12       0
  4985.9    0.05       0  4991.5    0.12       0
Bank Sta=4985.9,4991.5
Exp/Cntr=0.3,0.1

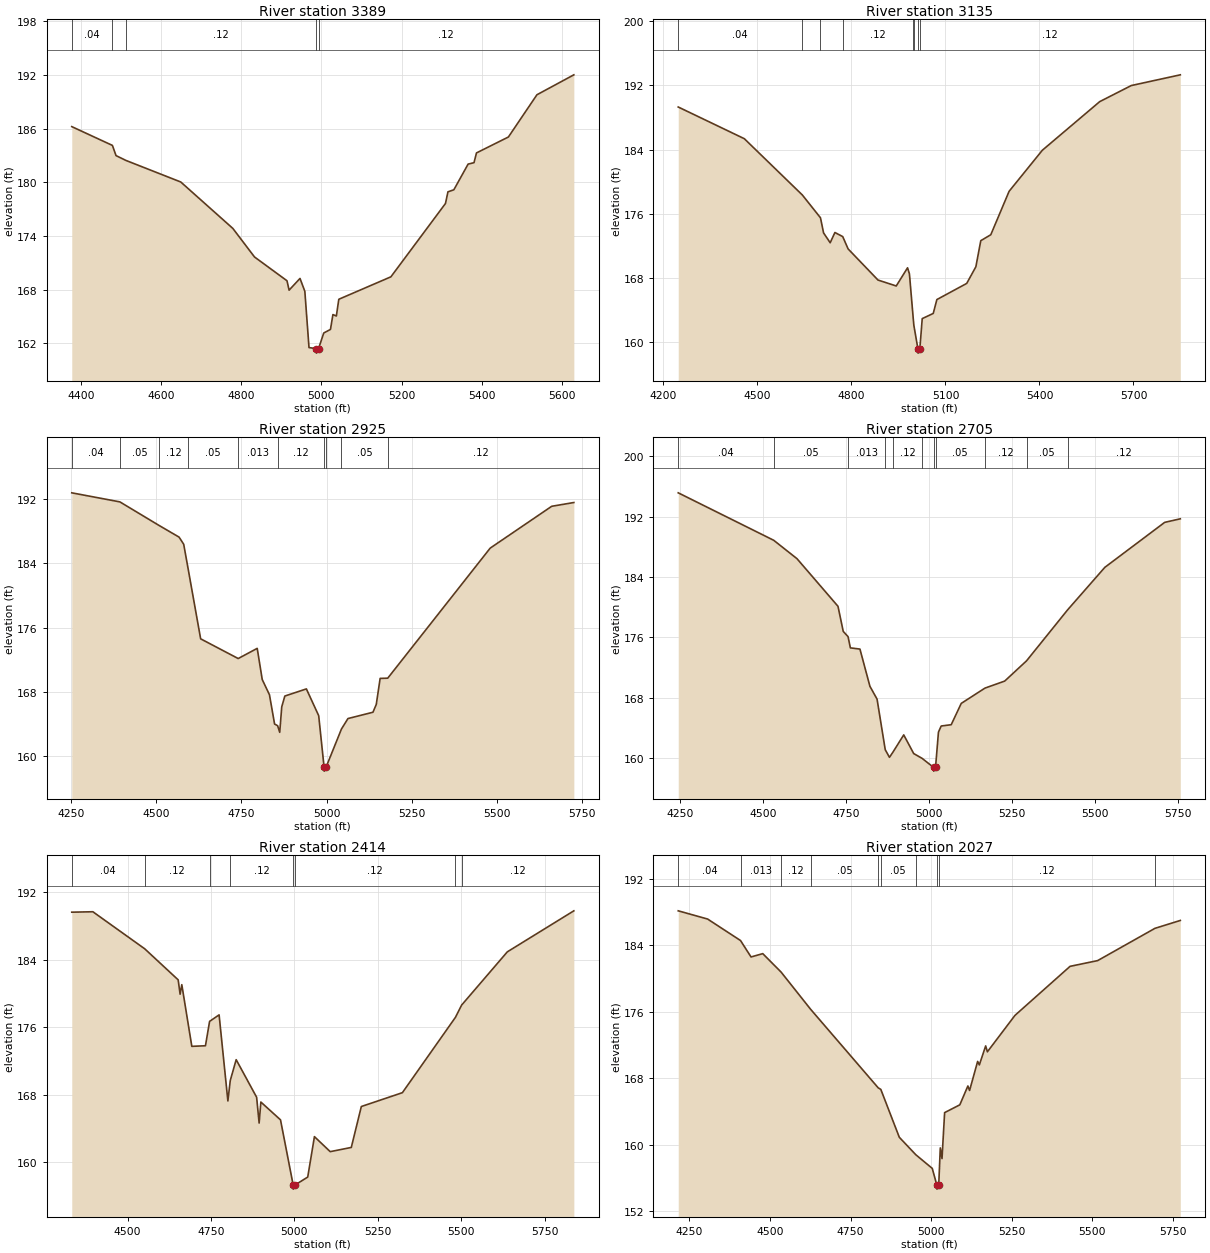
Type RM Length L Ch R = 1,3389,254,254,254
BEGIN DESCRIPTION:
Mapping XS 93acb2b2
END DESCRIPTION:
XS GIS Cut Line= 3
      2530010.91     13552870.53      2529823.42     13552269.87
      2529316.45     13551905.27
#Sta/Elev= 30
  4376.6  186.22  4478.1  184.12  4487.1  182.98  4511.9  182.44  4648.8  180.03
  4778.8  174.84  4832.9  171.65  4914.0  168.99  4919.3  167.94  4946.5  169.25
  4958.6  167.81  4969.0  161.52  4987.2  161.40  4987.6  160.90  4992.8  161.40
  5005.8  163.15  5022.6  163.55  5028.7  165.21  5037.3  165.05  5043.4  166.92
  5173.5  169.43  5309.8  177.63  5315.9  178.93  5330.7  179.16  5366.3  182.03
  5381.0  182.19  5387.2  183.28  5466.9  185.06  5538.1  189.78  5630.3  192.01
#Mann=5,-1,0
  4376.6    0.04       0  4478.1   0.013       0  4511.9    0.12       0
  4987.2    0.05       0  4992.8    0.12       0
Bank Sta=4987.2,4992.8
Exp/Cntr=0.3,0.1

Type RM Length L Ch R = 1,3135,210,210,210
BEGIN DESCRIPTION:
Mapping XS ae103561
END DESCRIPTION:
XS GIS Cut Line= 3
      2530667.14     13552575.41      2530014.39     13552144.87
      2529257.44     13551828.90
#Sta/Elev= 30
  4247.2  189.31  4458.1  185.35  4643.2  178.32  4701.1  175.47  4711.0  173.58
  4732.1  172.35  4747.2  173.63  4772.1  173.12  4789.3  171.58  4884.7  167.69
  4942.9  166.95  4979.0  169.22  4985.0  168.46  4997.2  162.85  4999.1  162.04
  5012.2  159.06  5012.6  158.56  5018.1  159.06  5025.8  162.87  5061.0  163.52
  5072.5  165.25  5167.8  167.27  5197.0  169.35  5212.7  172.61  5244.6  173.35
  5303.1  178.78  5409.2  183.91  5592.2  189.98  5692.9  191.99  5849.4  193.33
#Mann=8,-1,0
  4247.2    0.04       0  4643.2    0.12       0  4701.1   0.013       0
  4772.1    0.12       0  4997.2    0.05       0  4999.1    0.12       0
  5012.2    0.05       0  5018.1    0.12       0
Bank Sta=5012.2,5018.1
Exp/Cntr=0.3,0.1

Type RM Length L Ch R = 1,2925,220,220,220
BEGIN DESCRIPTION:
Mapping XS 8cfa8321
END DESCRIPTION:
XS GIS Cut Line= 3
      2530799.11     13552415.70      2530177.58     13552005.98
      2529483.14     13551787.23
#Sta/Elev= 30
  4252.4  192.81  4393.5  191.68  4509.2  188.72  4567.2  187.28  4580.7  186.39
  4594.3  183.18  4630.4  174.59  4740.5  172.13  4796.3  173.40  4811.0  169.51
  4832.2  167.61  4847.2  163.96  4856.1  163.75  4862.3  162.92  4868.2  166.10
  4877.3  167.45  4940.5  168.34  4976.6  165.00  4992.4  158.58  4992.9  158.08
  4998.3  158.58  5043.3  163.33  5062.4  164.64  5135.8  165.43  5145.5  166.41
  5156.8  169.65  5179.1  169.68  5479.6  185.91  5660.0  191.13  5724.9  191.60
#Mann=10,-1,0
  4252.4    0.04       0  4393.5    0.05       0  4509.2    0.12       0
  4594.3    0.05       0  4740.5   0.013       0  4856.1    0.12       0
  4992.4    0.05       0  4998.3    0.12       0  5043.3    0.05       0
  5179.1    0.12       0
Bank Sta=4992.4,4998.3
Exp/Cntr=0.3,0.1

Type RM Length L Ch R = 1,2705,291,291,291
BEGIN DESCRIPTION:
Mapping XS 40939c27
END DESCRIPTION:
XS GIS Cut Line= 3
      2530938.03     13552190.03      2530309.53     13551825.43
      2529529.10     13551745.65
#Sta/Elev= 30
  4244.7  195.17  4532.1  188.87  4602.1  186.43  4725.5  180.11  4741.3  176.78
  4755.8  176.08  4762.8  174.59  4791.6  174.43  4821.6  169.49  4843.1  167.79
  4867.7  161.08  4880.4  160.06  4890.9  160.75  4923.4  163.04  4953.4  160.56
  4978.5  159.93  5013.1  158.73  5013.6  158.23  5019.1  158.73  5027.9  163.41
  5036.2  164.22  5066.3  164.39  5096.5  167.22  5167.9  169.25  5227.2  170.18
  5293.0  172.87  5416.7  179.64  5528.7  185.28  5708.8  191.25  5755.8  191.72
#Mann=11,-1,0
  4244.7    0.04       0  4532.1    0.05       0  4755.8   0.013       0
  4867.7    0.05       0  4890.9    0.12       0  4978.5    0.05       0
  5013.1    0.05       0  5019.1    0.05       0  5167.9    0.12       0
  5293.0    0.05       0  5416.7    0.12       0
Bank Sta=5013.1,5019.1
Exp/Cntr=0.3,0.1

Type RM Length L Ch R = 1,2414,387,387,387
BEGIN DESCRIPTION:
Mapping XS e63459e0
END DESCRIPTION:
XS GIS Cut Line= 3
      2531076.92     13551728.21      2530396.33     13551582.37
      2529590.78     13551658.76
#Sta/Elev= 30
  4332.6  189.62  4395.9  189.67  4551.3  185.28  4651.6  181.60  4657.4  179.90
  4662.5  181.03  4692.5  173.72  4733.4  173.79  4745.8  176.68  4774.3  177.45
  4800.6  167.25  4807.8  169.68  4825.5  172.14  4886.8  167.69  4894.3  164.63
  4899.5  167.12  4958.4  165.01  4996.3  157.30  4996.8  156.80  5002.3  157.30
  5040.0  158.23  5060.1  163.02  5107.4  161.24  5170.6  161.74  5200.7  166.59
  5323.8  168.23  5482.7  177.15  5501.4  178.61  5638.4  184.92  5837.8  189.78
#Mann=8,-1,0
  4332.6    0.04       0  4551.3    0.12       0  4745.8   0.013       0
  4807.8    0.12       0  4996.3    0.05       0  5002.3    0.12       0
  5482.7    0.05       0  5501.4    0.12       0
Bank Sta=4996.3,5002.3
Exp/Cntr=0.3,0.1

Type RM Length L Ch R = 1,2027,309,309,309
BEGIN DESCRIPTION:
Mapping XS 1a4f10ab
END DESCRIPTION:
XS GIS Cut Line= 3
      2530976.23     13551558.08      2530330.36     13551228.20
      2529549.54     13551519.71
#Sta/Elev= 30
  4215.2  188.17  4306.4  187.18  4408.6  184.59  4441.2  182.61  4477.6  183.01
  4534.5  180.79  4626.3  176.30  4836.2  166.83  4844.1  166.65  4901.5  160.88
  4952.6  158.78  5003.8  157.13  5017.9  155.13  5018.4  154.63  5023.9  155.13
  5028.8  159.60  5034.1  158.31  5042.2  163.85  5089.4  164.79  5114.4  167.06
  5119.7  166.52  5144.7  170.02  5150.0  169.60  5169.6  171.89  5175.0  171.18
  5260.6  175.57  5431.7  181.48  5517.3  182.17  5695.2  186.06  5773.9  187.01
#Mann=10,-1,0
  4215.2    0.04       0  4408.6   0.013       0  4534.5    0.12       0
  4626.3    0.05       0  4836.2    0.12       0  4844.1    0.05       0
  4952.6    0.12       0  5017.9    0.05       0  5023.9    0.12       0
  5695.2    0.05       0
Bank Sta=5017.9,5023.9
Exp/Cntr=0.3,0.1

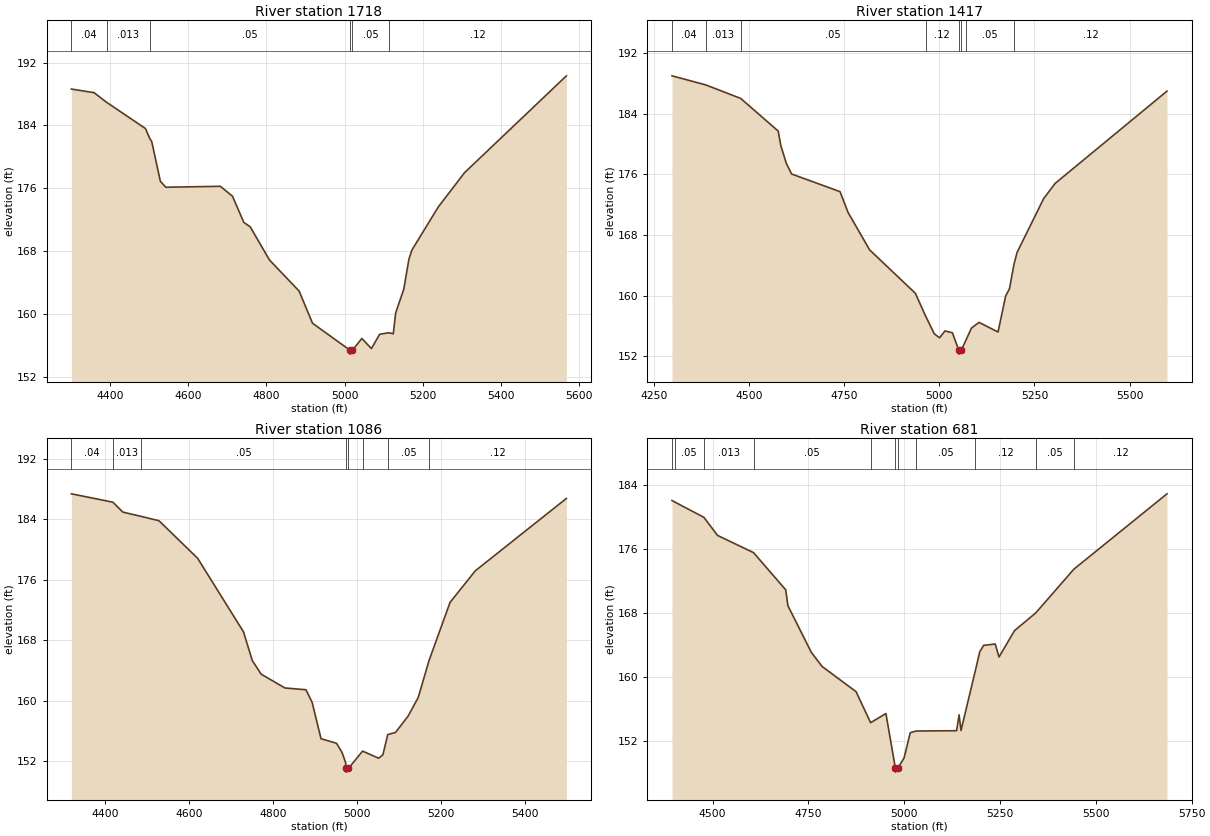
Type RM Length L Ch R = 1,1718,301,301,301
BEGIN DESCRIPTION:
Mapping XS e9a06802
END DESCRIPTION:
XS GIS Cut Line= 3
      2530987.48     13551299.38      2530388.52     13550976.47
      2529823.42     13550825.43
#Sta/Elev= 30
  4301.7  188.63  4359.6  188.17  4391.6  186.95  4491.0  183.61  4501.7  182.38
  4507.2  181.92  4529.1  176.91  4543.1  176.15  4682.4  176.27  4713.5  175.01
  4742.4  171.68  4758.6  171.13  4808.1  166.90  4883.9  162.95  4918.0  158.87
  5013.8  155.44  5014.3  154.94  5020.0  155.44  5044.3  156.93  5068.6  155.64
  5089.6  157.46  5113.2  157.66  5124.5  157.52  5130.7  160.19  5151.4  163.20
  5164.5  167.01  5172.1  168.16  5239.5  173.64  5306.7  178.00  5567.1  190.31
#Mann=6,-1,0
  4301.7    0.04       0  4391.6   0.013       0  4501.7    0.05       0
  5013.8    0.05       0  5020.0    0.05       0  5113.2    0.12       0
Bank Sta=5013.8,5020
Exp/Cntr=0.3,0.1

Type RM Length L Ch R = 1,1417,331,331,331
BEGIN DESCRIPTION:
Mapping XS cc736d54
END DESCRIPTION:
XS GIS Cut Line= 3
      2531039.55     13551255.10      2530526.54     13550742.09
      2529951.06     13550736.88
#Sta/Elev= 30
  4297.3  189.01  4385.6  187.82  4477.8  186.03  4576.4  181.72  4583.4  179.79
  4597.6  177.48  4611.7  176.05  4739.0  173.72  4760.2  170.96  4816.8  166.03
  4937.0  160.30  4963.8  157.31  4986.5  154.97  5000.6  154.42  5014.8  155.33
  5034.3  155.09  5051.2  152.77  5051.7  152.27  5057.4  152.77  5070.3  154.15
  5084.3  155.70  5104.3  156.46  5154.3  155.19  5174.3  159.95  5184.3  160.90
  5196.2  164.13  5204.3  165.70  5274.4  172.82  5304.4  174.81  5598.3  186.99
#Mann=8,-1,0
  4297.3    0.04       0  4385.6   0.013       0  4477.8    0.05       0
  4963.8    0.12       0  5051.2    0.05       0  5057.4    0.12       0
  5070.3    0.05       0  5196.2    0.12       0
Bank Sta=5051.2,5057.4
Exp/Cntr=0.3,0.1

Type RM Length L Ch R = 1,1086,405,405,405
BEGIN DESCRIPTION:
Mapping XS 3ea52bc4
END DESCRIPTION:
XS GIS Cut Line= 3
      2531112.51     13551078.06      2530729.67     13550544.18
      2530208.09     13550531.20
#Sta/Elev= 30
  4319.7  187.37  4418.6  186.26  4442.2  184.95  4486.2  184.38  4528.2  183.81
  4620.3  178.84  4729.5  169.10  4750.5  165.30  4771.4  163.51  4828.0  161.68
  4878.2  161.44  4893.0  159.76  4914.1  154.96  4951.0  154.36  4964.2  153.14
  4972.8  151.78  4973.3  151.04  4973.8  150.54  4979.5  151.04  5013.0  153.32
  5051.4  152.38  5061.4  152.84  5073.0  155.51  5091.4  155.79  5121.4  157.95
  5145.5  160.41  5171.3  165.31  5221.4  173.01  5281.4  177.18  5498.4  186.76
#Mann=8,-1,0
  4319.7    0.04       0  4418.6   0.013       0  4486.2    0.05       0
  4973.3    0.05       0  4979.5    0.05       0  5013.0    0.12       0
  5073.0    0.05       0  5171.3    0.12       0
Bank Sta=4973.3,4979.5
Exp/Cntr=0.3,0.1

Type RM Length L Ch R = 1,681,0,0,0
BEGIN DESCRIPTION:
TRIB 2 TO CARLISLE CREEK 1.0
END DESCRIPTION:
XS GIS Cut Line= 3
      2531255.69     13550812.36      2530981.10     13550272.81
      2530300.03     13550354.06
#Sta/Elev= 30
  4394.3  182.10  4401.3  181.91  4477.6  179.99  4513.1  177.73  4607.0  175.58
  4691.1  170.92  4696.7  168.94  4757.8  163.11  4785.7  161.35  4874.6  158.19
  4912.4  154.31  4952.4  155.46  4977.1  148.63  4977.6  148.13  4983.4  148.63
  4999.7  149.89  5015.9  153.06  5031.3  153.27  5136.8  153.31  5143.3  155.29
  5148.3  153.34  5184.9  160.66  5197.2  163.18  5207.3  163.98  5237.5  164.15
  5247.5  162.53  5287.8  165.82  5343.5  168.05  5442.8  173.51  5685.6  182.93
#Mann=11,-1,0
  4394.3    0.04       0  4401.3    0.05       0  4477.6   0.013       0
  4607.0    0.05       0  4912.4    0.12       0  4977.1    0.05       0
  4983.4    0.12       0  5031.3    0.05       0  5184.9    0.12       0
  5343.5    0.05       0  5442.8    0.12       0
Bank Sta=4977.1,4983.4
Exp/Cntr=0.3,0.1

Chan Stop Cuts=-1