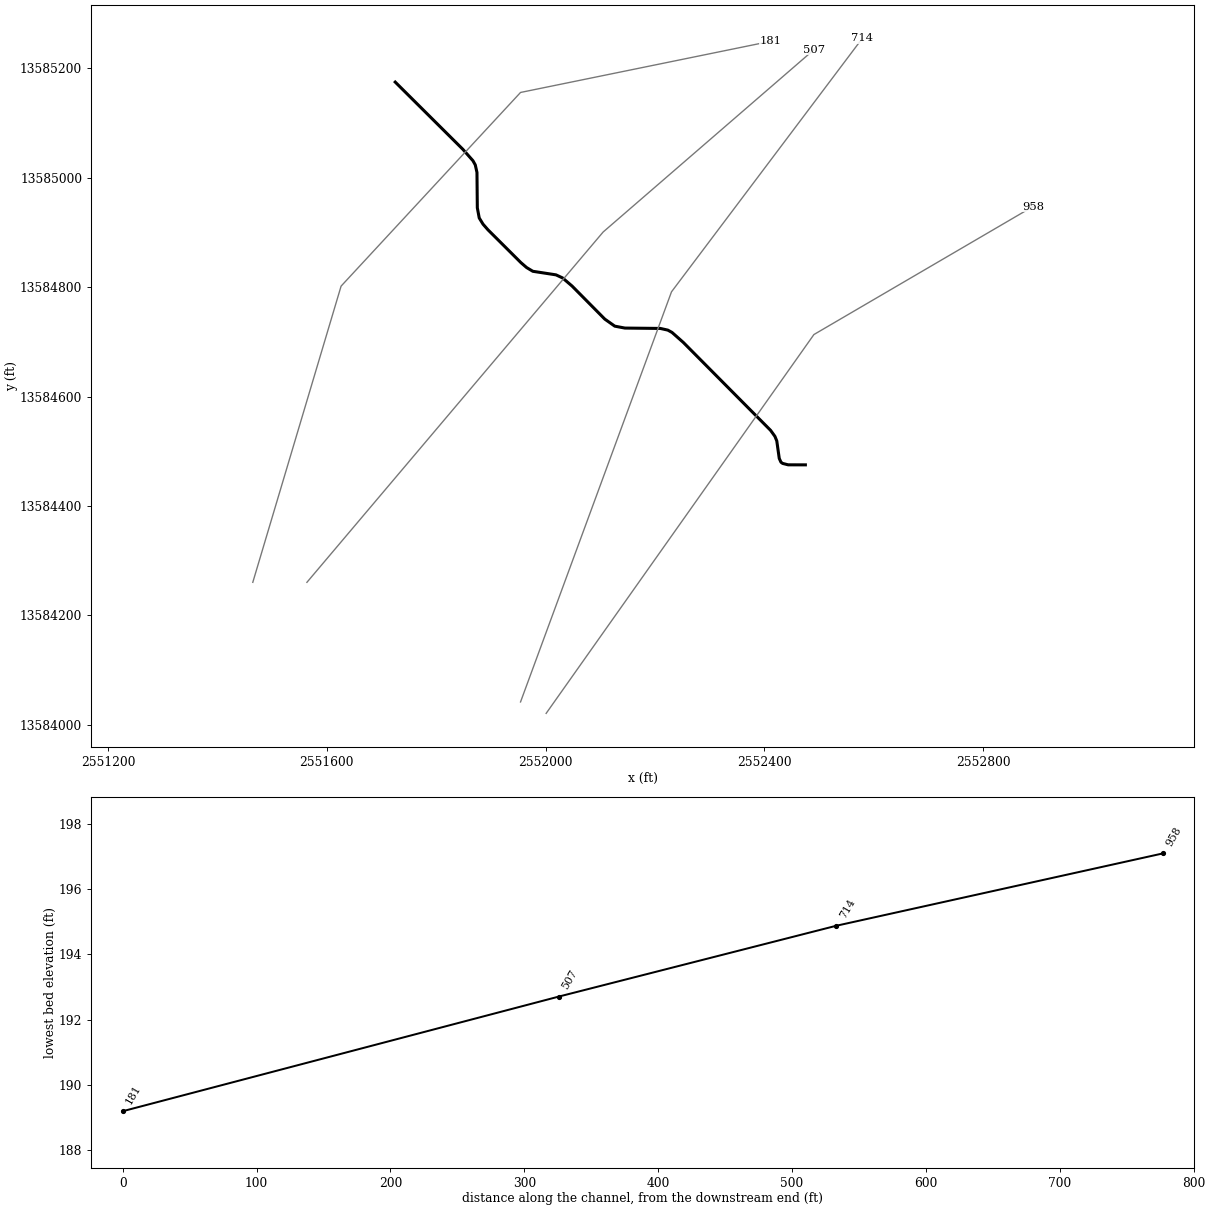
--- TRIB 2 TO CRITTENOON HOLLOW.prj (project) ---

Proj Title=TRIB 2 TO CRITTENOON HOLLOW Base Level Engineering
Current Plan=p01
Default Exp/Contr=0.3,0.1
English Units
Geom File=g01
Flow File=f01
Plan File=p01
Y Axis Title=Elevation
X Axis Title(PF)=Main Channel Distance
X Axis Title(XS)=Station
BEGIN DESCRIPTION:
TRIB 2 TO CRITTENOON HOLLOW
END DESCRIPTION:
DSS Export Rating Curves= 0
DSS Export Rating Curve Sorted= 0
DSS Export Volume Flow Curves= 0
DXF OffsetX= 0
DXF OffsetY= 0
DXF ScaleX= 1
DXF ScaleY= 10

--- TRIB 2 TO CRITTENOON HOLLOW.p01 (plan) ---

Plan Title=Multiple Run
Short Identifier=Multiple
Geom File=g01
Flow File=f01
Subcritical Flow
K Sum by GR= 0
Std Step Tol= 0.01
Critical Tol= 0.01
Num of Std Step Trials= 20
Max Error Tol= 0.3
Flow Tol Ratio= 0.001
Split Flow NTrial= 30
Split Flow Tol= 0.02
Split Flow Ratio= 0.02
Log Output Level= 0
Friction Slope Method= 1
Unsteady Friction Slope Method= 2
Unsteady Bridges Friction Slope Method= 1
Parabolic Critical Depth
Global Vel Dist=  1 , 1 , 1
Global Log Level= 0
CheckData=True
Encroach Param= -1, 0, 0, 0
BEGIN DESCRIPTION:
Multiple Run
END DESCRIPTION:

--- TRIB 2 TO CRITTENOON HOLLOW.f01 (steady flow) ---

Flow Title=Multiple
Number of Profiles=7
Profile Names=10-year,25-year,50-year,1pct_min,100-year,1pct_plu,500-year
River Rch & RM= TRIB 2 TO CRITTE,Reach-1,958
     337     524     688     440     878    1752    1409
Boundary for River Rch & Prof#=TRIB 2 TO CRITTE,Reach-1,1
Up Type=0
Dn Type=3
Dn Slope=0.005
Boundary for River Rch & Prof#=TRIB 2 TO CRITTE,Reach-1,2
Up Type=0
Dn Type=3
Dn Slope=0.005
Boundary for River Rch & Prof#=TRIB 2 TO CRITTE,Reach-1,3
Up Type=0
Dn Type=3
Dn Slope=0.005
Boundary for River Rch & Prof#=TRIB 2 TO CRITTE,Reach-1,4
Up Type=0
Dn Type=3
Dn Slope=0.005
Boundary for River Rch & Prof#=TRIB 2 TO CRITTE,Reach-1,5
Up Type=0
Dn Type=3
Dn Slope=0.005
Boundary for River Rch & Prof#=TRIB 2 TO CRITTE,Reach-1,6
Up Type=0
Dn Type=3
Dn Slope=0.005
Boundary for River Rch & Prof#=TRIB 2 TO CRITTE,Reach-1,7
Up Type=0
Dn Type=3
Dn Slope=0.005

--- TRIB 2 TO CRITTENOON HOLLOW.g01 (geometry) ---

Geom Title=Existing Conditions
Program Version=4.10

River Reach=TRIB 2 TO CRITTE,Reach-1
Reach XY= 30
        2552475.       13584475.      2552443.46     13584475.07
      2552433.44     13584477.63      2552430.33     13584479.92
      2552427.22     13584486.76       2552422.7     13584518.79
      2552419.29     13584527.13       2552411.4     13584538.08
      2552251.87     13584698.82      2552231.17     13584717.14
       2552223.5     13584721.39      2552209.78     13584724.47
      2552145.06     13584725.14       2552126.5     13584728.63
      2552108.26     13584741.49      2552048.44     13584801.93
      2552031.04     13584816.82      2552018.94     13584822.46
      2551976.63     13584828.97       2551965.3     13584835.77
      2551954.87     13584844.77      2551894.61      13584904.8
      2551885.51     13584915.19      2551878.61     13584926.49
      2551875.13     13584945.05      2551874.47     13585009.78
      2551871.39      13585023.5      2551867.14     13585031.17
      2551848.83     13585051.87        2551725.       13585175.

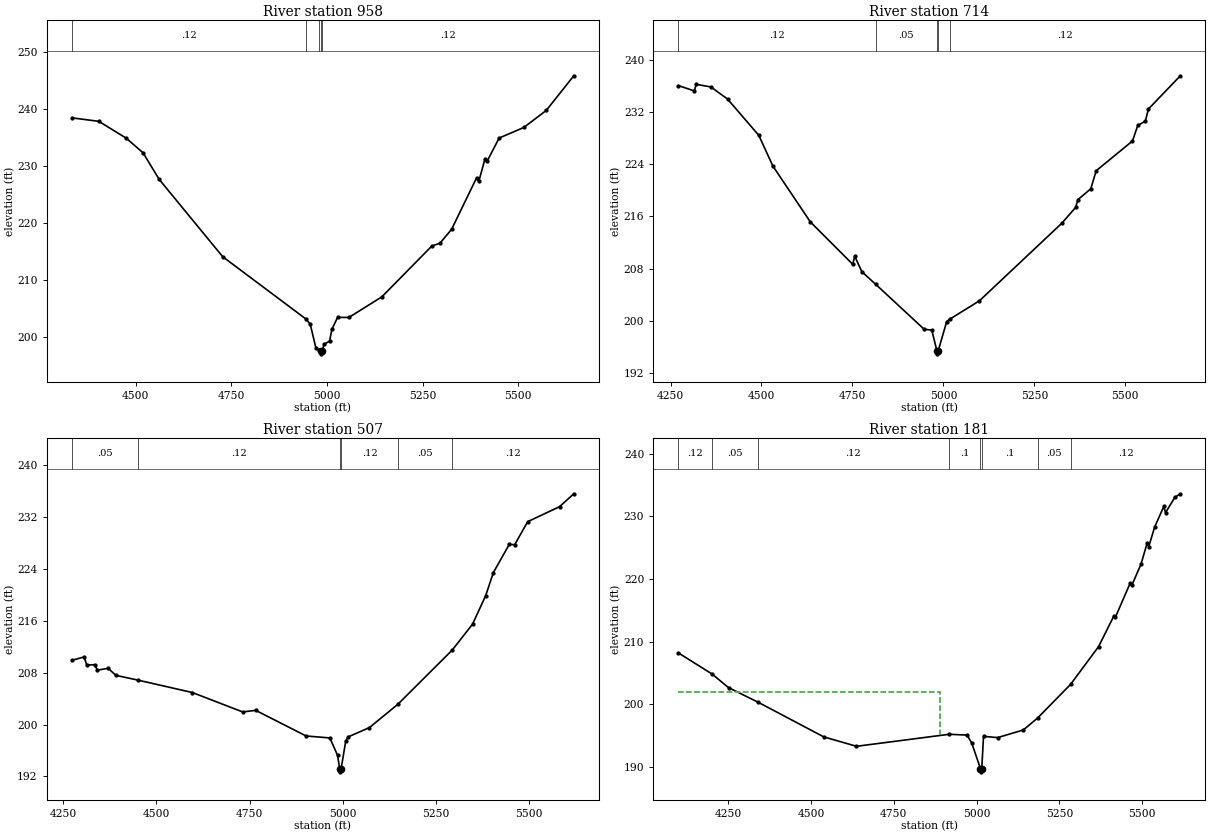
Type RM Length L Ch R = 1 ,958     ,244,244,244
BEGIN DESCRIPTION:
LGII3826
END DESCRIPTION:
XS GIS Cut Line= 3
      2552000.99     13584020.55      2552490.59     13584713.29
      2552890.78     13584947.16
#Sta/Elev= 30
  4333.6  238.49  4403.8  237.88  4475.2  234.94  4519.5  232.36  4561.4  227.72
  4727.6  214.14  4945.2  203.21  4956.5  202.29  4971.3  198.13  4978.4  197.81
  4984.1   197.6  4984.4   197.1  4988.1   197.6  4992.2  198.74    5007  199.34
  5013.1  201.38  5027.9   203.5  5057.5  203.48  5143.7   207.1  5274.2     216
  5295.7  216.51    5326  218.94  5391.5     228  5397.3   227.4    5413  231.23
  5418.8  230.87  5450.2  234.95  5514.7   236.8  5573.4  239.79  5645.4  245.87
#Mann= 5 ,-1 , 0
  4333.6     .12       0  4945.2     .05       0  4978.4     .12       0
  4984.1     .05       0  4988.1     .12       0
Bank Sta=4984.1,4988.1
XS Rating Curve= 0 ,0
Exp/Cntr=0.3,0.1

Type RM Length L Ch R = 1 ,714     ,207,207,207
BEGIN DESCRIPTION:
LGII3825
END DESCRIPTION:
XS GIS Cut Line= 3
      2551954.14     13584041.43      2552230.18     13584791.41
      2552579.15     13585254.97
#Sta/Elev= 30
  4271.8  236.13  4315.3  235.31  4320.6  236.33  4360.9  235.92  4406.7  234.06
  4492.7  228.47  4531.3  223.75  4634.4  215.16  4750.9  208.64  4756.2  209.89
    4776   207.5  4813.8  205.58  4946.9  198.67  4968.2  198.52  4981.9  195.38
  4982.2  194.88  4985.9  195.38    5009  199.83  5016.9  200.19  5099.1  203.04
  5326.1     215  5363.4   217.4  5369.8  218.59  5405.2  220.27  5419.8  223.03
  5519.7  227.61  5534.3  230.01  5555.1  230.66  5563.4  232.52  5651.2  237.64
#Mann= 5 ,-1 , 0
  4271.8     .12       0  4813.8     .05       0  4981.9     .05       0
  4985.9     .05       0  5016.9     .12       0
Bank Sta=4981.9,4985.9
XS Rating Curve= 0 ,0
Exp/Cntr=0.3,0.1

Type RM Length L Ch R = 1 ,507     ,326,326,326
BEGIN DESCRIPTION:
LGII3824
END DESCRIPTION:
XS GIS Cut Line= 3
      2551563.53     13584260.18      2552105.18     13584900.79
      2552490.31     13585233.88
#Sta/Elev= 30
  4272.9   209.9  4305.4  210.43  4312.9  209.18  4333.8  209.23  4341.5  208.39
  4370.1  208.68  4390.9  207.59    4449  206.87  4596.4  204.94  4731.5  201.95
  4766.7  202.19  4901.8  198.24  4965.6  197.94  4986.4  195.26  4992.1  193.21
  4992.4  192.71  4996.1  193.21  5008.4  197.47    5015   198.1  5072.1  199.54
  5148.4  203.13  5294.3  211.48  5349.1  215.49  5384.2  219.87    5405  223.45
  5447.8   227.8  5462.1  227.73  5497.2  231.29  5582.7   233.6    5621  235.59
#Mann= 6 ,-1 , 0
  4272.9     .05       0    4449     .12       0  4992.1     .05       0
  4996.1     .12       0  5148.4     .05       0  5294.3     .12       0
Bank Sta=4992.1,4996.1
XS Rating Curve= 0 ,0
Exp/Cntr=0.3,0.1

Type RM Length L Ch R = 1 ,181     ,0,0,0
BEGIN DESCRIPTION:
LGII3823
END DESCRIPTION:
XS GIS Cut Line= 4
      2551464.57     13584260.21      2551626.01     13584801.83
      2551954.14       13585156.       2552411.2     13585249.48
#Sta/Elev= 30
  4100.3  208.18  4202.1   204.8  4251.4  202.64  4339.2  200.35  4538.9  194.77
  4637.5  193.27  4917.4  195.19  4971.1  195.06  4985.2  193.82  5011.6  189.69
  5011.8  189.19  5015.6  189.69  5020.9  194.86  5063.5  194.66  5141.1  195.88
  5183.9  197.78  5283.7  203.17  5368.2   209.2  5413.6  214.02  5418.7  213.87
  5464.1  219.41  5469.2  219.08  5496.2  222.37  5514.5   225.7  5519.6  225.16
    5537  228.26    5565  231.58  5570.1  230.59  5598.3  233.04  5614.8  233.61
#Mann= 8 ,-1 , 0
  4100.3     .12       0  4202.1     .05       0  4339.2     .12       0
  4917.4      .1       0  5011.6     .05       0  5015.6      .1       0
  5183.9     .05       0  5283.7     .12       0
#XS Ineff= 2 , 0
       0    4890     202               0
Permanent Ineff=
       F       F
Bank Sta=5011.6,5015.6
XS Rating Curve= 0 ,0
Exp/Cntr=0.3,0.1

Chan Stop Cuts=-1
Use User Specified Reach Order=0
Composite Channel Slope=5