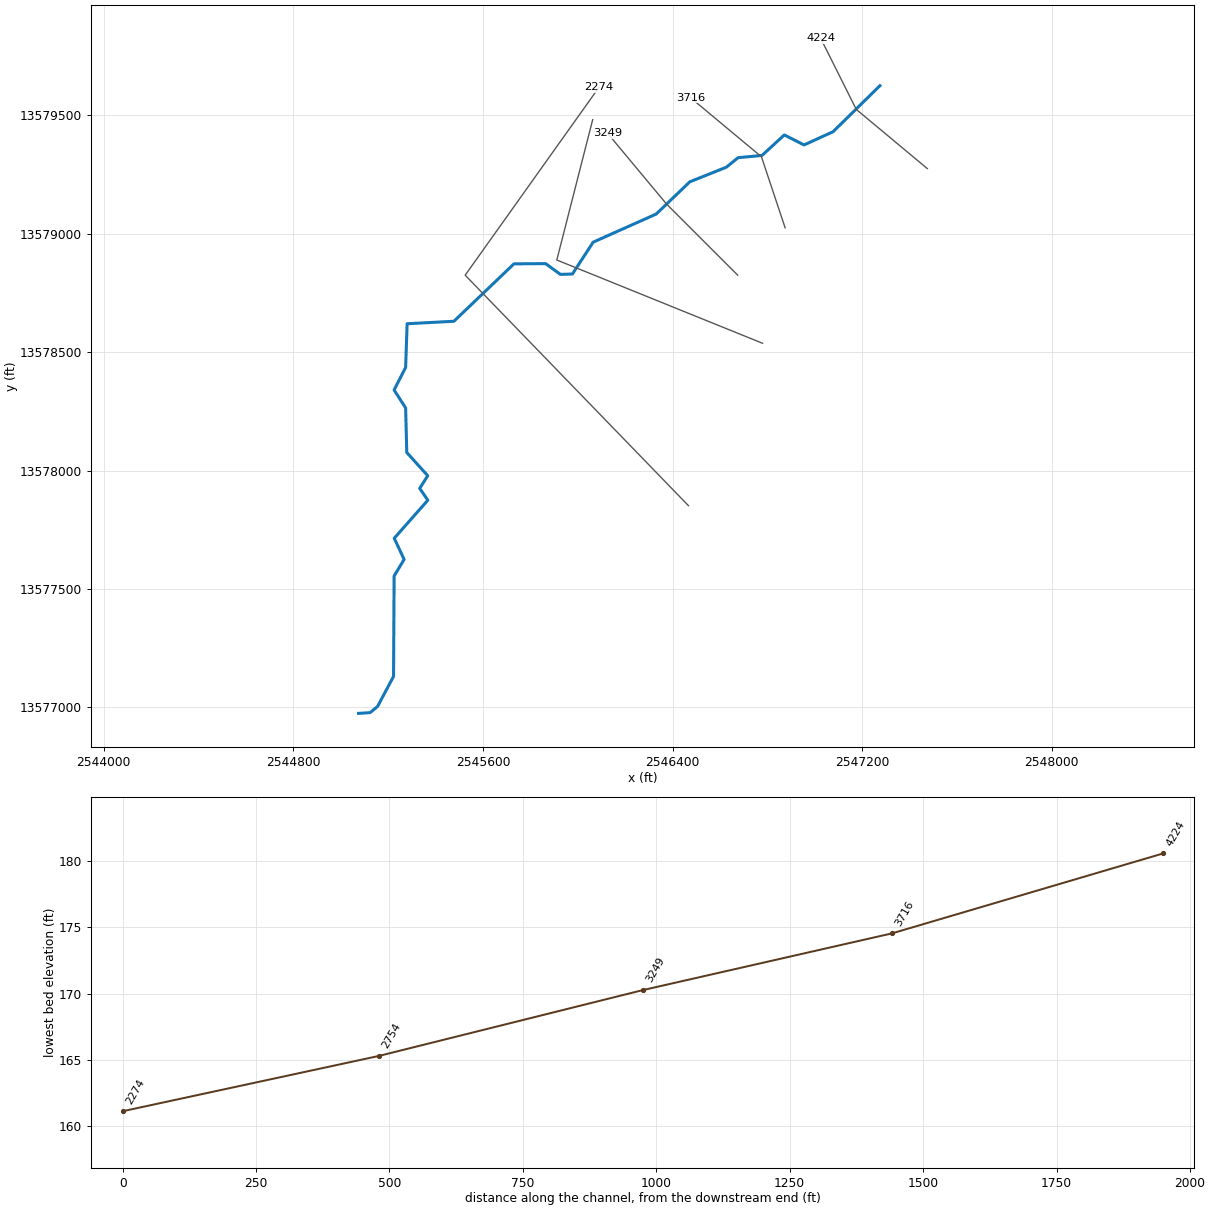
--- TRIB 2 TO IRISH CREEK.prj (project) ---

Proj Title=TRIB 2 TO IRISH CREEK Base Level Engineering
Current Plan=p01
Default Exp/Contr=0.3,0.1
English Units
Geom File=g01
Flow File=f01
Plan File=p01
BEGIN DESCRIPTION:
TRIB 2 TO IRISH CREEK
END DESCRIPTION:

--- TRIB 2 TO IRISH CREEK.p01 (plan) ---

Plan Title=Multiple Run
Short Identifier=Multiple
Geom File=g01
Flow File=f01
Subcritical Flow
K Sum by GR= 0
Std Step Tol= 0.01
Critical Tol= 0.01
Num of Std Step Trials= 20
Max Error Tol= 0.3
Flow Tol Ratio= 0.001
Split Flow NTrial= 30
Split Flow Tol= 0.02
Split Flow Ratio= 0.02
Log Output Level= 0
Friction Slope Method= 1
Unsteady Friction Slope Method= 2
Unsteady Bridges Friction Slope Method= 1
Parabolic Critical Depth
Global Vel Dist=  1 , 1 , 1
Global Log Level= 0
CheckData=True
Encroach Param= -1, 0, 0, 0
BEGIN DESCRIPTION:
Multiple Run
END DESCRIPTION:

--- TRIB 2 TO IRISH CREEK.f01 (steady flow) ---

Flow Title=Multiple
Number of Profiles=7
Profile Names=10-year,25-year,50-year,1pct_min,100-year,1pct_plu,500-year
River Rch & RM= TRIB 2 TO IRISH ,Reach-1,4224
     519     830    1110     721    1439    2872    2392
Boundary for River Rch & Prof#=TRIB 2 TO IRISH ,Reach-1,1
Up Type=0
Dn Type=3
Dn Slope=0.005
Boundary for River Rch & Prof#=TRIB 2 TO IRISH ,Reach-1,2
Up Type=0
Dn Type=3
Dn Slope=0.005
Boundary for River Rch & Prof#=TRIB 2 TO IRISH ,Reach-1,3
Up Type=0
Dn Type=3
Dn Slope=0.005
Boundary for River Rch & Prof#=TRIB 2 TO IRISH ,Reach-1,4
Up Type=0
Dn Type=3
Dn Slope=0.005
Boundary for River Rch & Prof#=TRIB 2 TO IRISH ,Reach-1,5
Up Type=0
Dn Type=3
Dn Slope=0.005
Boundary for River Rch & Prof#=TRIB 2 TO IRISH ,Reach-1,6
Up Type=0
Dn Type=3
Dn Slope=0.005
Boundary for River Rch & Prof#=TRIB 2 TO IRISH ,Reach-1,7
Up Type=0
Dn Type=3
Dn Slope=0.005

--- TRIB 2 TO IRISH CREEK.g01 (geometry) ---

Geom Title=Existing Conditions

River Reach=TRIB 2 TO IRISH ,Reach-1
Reach XY= 30
      2547275.00     13579625.00      2547077.30     13579430.83
      2546954.80     13579374.78      2546871.60     13579417.17
      2546777.43     13579330.55      2546676.59     13579321.17
      2546627.18     13579281.12      2546472.70     13579219.17
      2546331.06     13579083.14      2546065.00     13578964.37
      2545977.55     13578829.99      2545926.78     13578828.33
      2545864.50     13578873.77      2545730.86     13578872.95
      2545477.45     13578630.46      2545280.00     13578620.00
      2545273.76     13578435.50      2545225.09     13578340.39
      2545273.76     13578264.50      2545278.56     13578076.46
      2545367.00     13577978.33      2545333.05     13577925.00
      2545367.46     13577875.00      2545225.65     13577714.36
      2545267.41     13577625.01      2545225.18     13577555.02
      2545222.76     13577130.93      2545155.50     13577004.53
      2545123.97     13576978.14      2545075.00     13576975.00

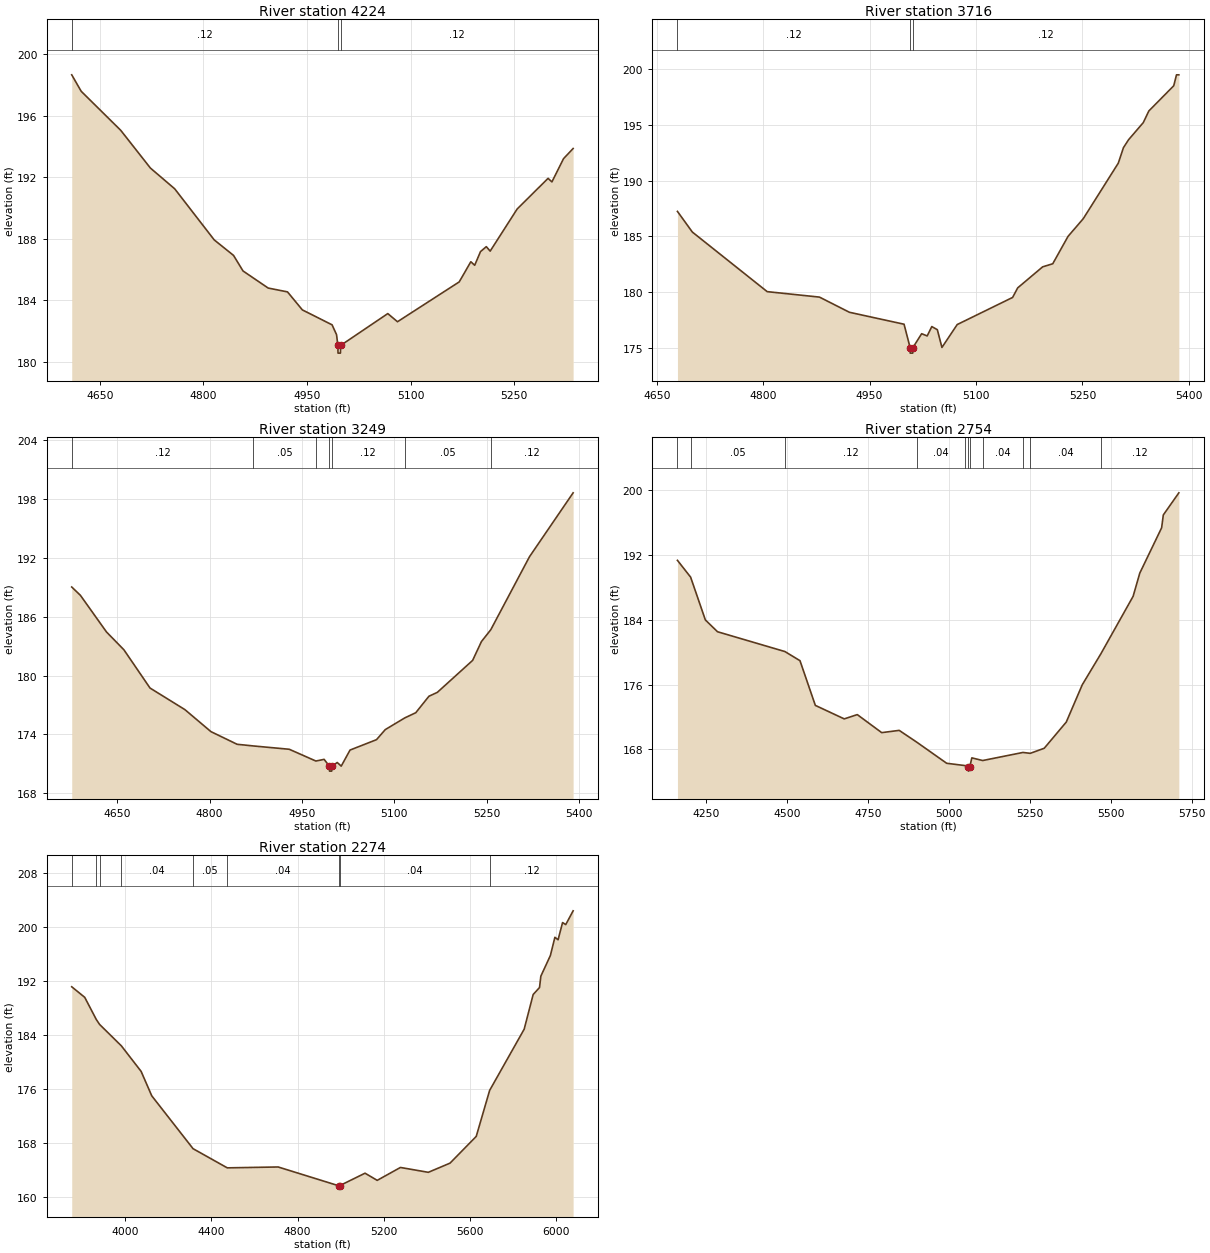
Type RM Length L Ch R = 1,4224,508,508,508
BEGIN DESCRIPTION:
TRIB 2 TO IRISH CREEK 5.0
END DESCRIPTION:
XS GIS Cut Line= 3
      2547475.01     13579274.99      2547175.00     13579525.00
      2547025.02     13579824.97
#Sta/Elev= 30
  4609.5  198.66  4623.2  197.59  4680.5  195.05  4723.4  192.60  4758.6  191.25
  4815.8  187.93  4843.8  186.92  4857.5  185.91  4893.9  184.80  4921.9  184.55
  4943.4  183.38  4986.4  182.41  4992.9  181.77  4994.8  181.07  4995.0  180.57
  4998.5  180.57  4998.8  181.07  5067.1  183.14  5081.1  182.61  5170.5  185.20
  5187.3  186.51  5192.9  186.28  5201.3  187.17  5209.7  187.49  5215.3  187.20
  5254.4  189.94  5299.1  191.93  5304.7  191.70  5321.5  193.21  5335.4  193.87
#Mann=3,-1,0
  4609.5    0.12       0  4994.8    0.05       0  4998.8    0.12       0
Bank Sta=4994.8,4998.8
Exp/Cntr=0.3,0.1

Type RM Length L Ch R = 1,3716,467,467,467
BEGIN DESCRIPTION:
TRIB 2 TO IRISH CREEK 4.0
END DESCRIPTION:
XS GIS Cut Line= 3
      2546874.99     13579025.04      2546775.00     13579325.00
      2546475.00     13579575.00
#Sta/Elev= 30
  4679.2  187.24  4700.2  185.39  4805.7  180.05  4879.4  179.56  4921.6  178.20
  4998.6  177.13  5007.1  175.04  5007.3  174.54  5010.8  174.54  5011.1  175.04
  5023.4  176.28  5031.2  176.08  5037.7  176.92  5045.5  176.64  5052.0  175.05
  5073.5  177.10  5151.6  179.53  5158.8  180.39  5193.9  182.27  5208.2  182.55
  5229.7  185.00  5251.2  186.59  5300.6  191.57  5307.8  192.95  5315.0  193.66
  5335.8  195.20  5343.6  196.24  5378.7  198.50  5382.6  199.48  5385.9  199.48
#Mann=3,-1,0
  4679.2    0.12       0  5007.1    0.05       0  5011.1    0.12       0
Bank Sta=5007.1,5011.1
Exp/Cntr=0.3,0.1

Type RM Length L Ch R = 1,3249,495,495,495
BEGIN DESCRIPTION:
TRIB 2 TO IRISH CREEK 3.0
END DESCRIPTION:
XS GIS Cut Line= 3
      2546674.97     13578825.03      2546375.00     13579125.00
      2546125.03     13579424.97
#Sta/Elev= 30
  4576.0  189.05  4590.1  188.20  4632.5  184.46  4660.8  182.64  4703.2  178.74
  4759.8  176.54  4802.2  174.29  4844.7  173.00  4871.1  172.83  4929.5  172.49
  4972.7  171.29  4986.1  171.46  4994.7  170.76  4994.9  170.26  4998.4  170.26
  4998.7  170.76  5007.4  171.14  5013.9  170.77  5028.2  172.41  5071.2  173.47
  5085.5  174.50  5117.1  175.69  5135.0  176.22  5156.4  177.90  5170.1  178.30
  5227.4  181.56  5241.7  183.48  5256.9  184.69  5319.8  192.14  5390.7  198.66
#Mann=7,-1,0
  4576.0    0.12       0  4871.1    0.05       0  4972.7    0.12       0
  4994.7    0.05       0  4998.7    0.12       0  5117.1    0.05       0
  5256.9    0.12       0
Bank Sta=4994.7,4998.7
Exp/Cntr=0.3,0.1

Type RM Length L Ch R = 1,2754,480,480,480
BEGIN DESCRIPTION:
Mapping XS bc50084b
END DESCRIPTION:
XS GIS Cut Line= 3
      2546779.68     13578537.54      2545911.64     13578889.09
      2546063.07     13579481.82
#Sta/Elev= 30
  4162.2  191.36  4202.9  189.28  4248.4  183.99  4285.9  182.53  4494.0  180.08
  4540.6  178.95  4588.0  173.42  4677.3  171.75  4717.5  172.28  4793.0  170.05
  4847.0  170.33  4901.6  168.86  4993.6  166.26  5051.4  165.97  5060.7  165.79
  5061.0  165.29  5064.7  165.79  5071.3  166.93  5104.7  166.60  5229.3  167.60
  5251.7  167.49  5294.9  168.12  5362.9  171.36  5412.3  175.97  5470.0  179.82
  5569.3  186.91  5589.9  189.78  5657.4  195.39  5662.5  196.97  5710.5  199.71
#Mann=11,-1,0
  4162.2   0.013       0  4202.9    0.05       0  4494.0    0.12       0
  4901.6    0.04       0  5051.4    0.05       0  5060.7    0.04       0
  5064.7    0.05       0  5104.7    0.04       0  5229.3    0.05       0
  5251.7    0.04       0  5470.0    0.12       0
Bank Sta=5060.7,5064.7
Exp/Cntr=0.3,0.1

Type RM Length L Ch R = 1,2274,0,0,0
BEGIN DESCRIPTION:
TRIB 2 TO IRISH CREEK 1.0
END DESCRIPTION:
XS GIS Cut Line= 3
      2546467.19     13577851.77      2545525.00     13578825.00
      2546089.62     13579618.30
#Sta/Elev= 30
  3751.5  191.09  3811.8  189.53  3865.3  186.26  3880.7  185.52  3982.0  182.34
  4073.7  178.56  4123.1  174.94  4314.9  167.11  4473.8  164.27  4710.1  164.40
  4991.0  161.62  4991.3  161.12  4995.0  161.62  5113.5  163.48  5170.0  162.42
  5277.9  164.33  5407.3  163.61  5508.2  164.97  5629.9  168.93  5692.1  175.74
  5852.5  184.81  5894.3  189.95  5923.8  190.98  5929.9  192.66  5974.2  195.72
  5995.1  198.42  6009.9  198.05  6030.8  200.60  6045.5  200.30  6079.8  202.34
#Mann=9,-1,0
  3751.5   0.013       0  3865.3    0.04       0  3880.7    0.05       0
  3982.0    0.04       0  4314.9    0.05       0  4473.8    0.04       0
  4991.0    0.04       0  4995.0    0.04       0  5692.1    0.12       0
Bank Sta=4991,4995
Exp/Cntr=0.3,0.1

Chan Stop Cuts=-1