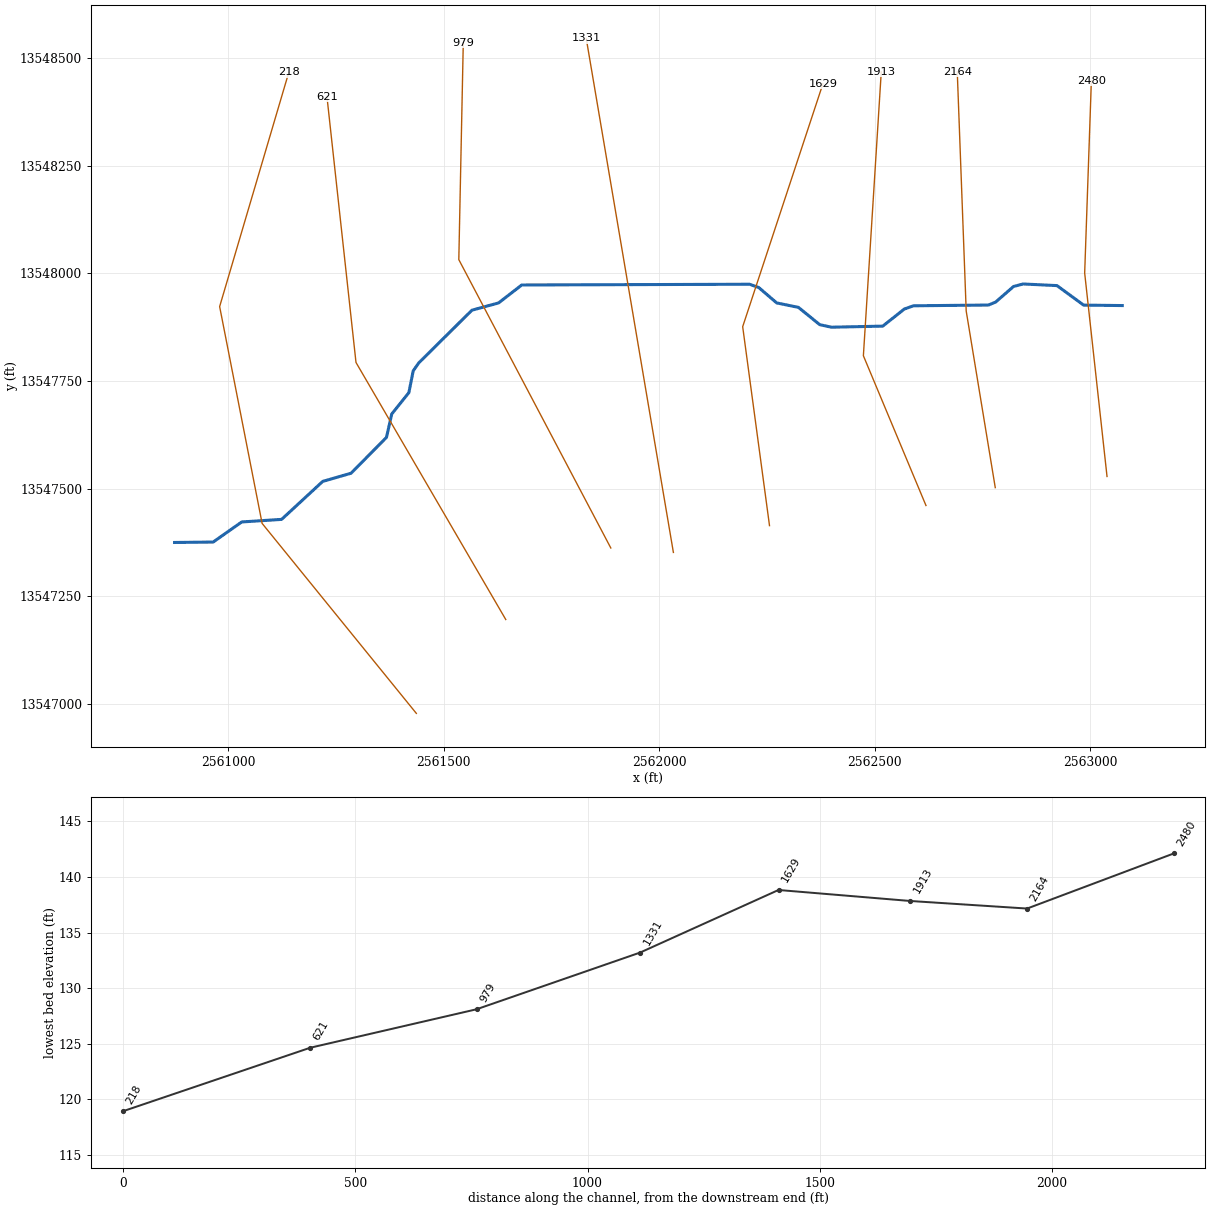
--- TRIB 2 TO PRICE CREEK.prj (project) ---

Proj Title=TRIB 2 TO PRICE CREEK Base Level Engineering
Current Plan=p01
Default Exp/Contr=0.3,0.1
English Units
Geom File=g01
Flow File=f01
Plan File=p01
BEGIN DESCRIPTION:
TRIB 2 TO PRICE CREEK
END DESCRIPTION:

--- TRIB 2 TO PRICE CREEK.p01 (plan) ---

Plan Title=Multiple Run
Short Identifier=Multiple
Geom File=g01
Flow File=f01
Subcritical Flow
K Sum by GR= 0
Std Step Tol= 0.01
Critical Tol= 0.01
Num of Std Step Trials= 20
Max Error Tol= 0.3
Flow Tol Ratio= 0.001
Split Flow NTrial= 30
Split Flow Tol= 0.02
Split Flow Ratio= 0.02
Log Output Level= 0
Friction Slope Method= 1
Unsteady Friction Slope Method= 2
Unsteady Bridges Friction Slope Method= 1
Parabolic Critical Depth
Global Vel Dist=  1 , 1 , 1
Global Log Level= 0
CheckData=True
Encroach Param= -1, 0, 0, 0
BEGIN DESCRIPTION:
Multiple Run
END DESCRIPTION:

--- TRIB 2 TO PRICE CREEK.f01 (steady flow) ---

Flow Title=Multiple
Number of Profiles=7
Profile Names=10-year,25-year,50-year,1pct_min,100-year,1pct_plu,500-year
River Rch & RM= TRIB 2 TO PRICE ,Reach-1,2480
     440     688     906     579    1156    2306    1856
Boundary for River Rch & Prof#=TRIB 2 TO PRICE ,Reach-1,1
Up Type=0
Dn Type=3
Dn Slope=0.005
Boundary for River Rch & Prof#=TRIB 2 TO PRICE ,Reach-1,2
Up Type=0
Dn Type=3
Dn Slope=0.005
Boundary for River Rch & Prof#=TRIB 2 TO PRICE ,Reach-1,3
Up Type=0
Dn Type=3
Dn Slope=0.005
Boundary for River Rch & Prof#=TRIB 2 TO PRICE ,Reach-1,4
Up Type=0
Dn Type=3
Dn Slope=0.005
Boundary for River Rch & Prof#=TRIB 2 TO PRICE ,Reach-1,5
Up Type=0
Dn Type=3
Dn Slope=0.005
Boundary for River Rch & Prof#=TRIB 2 TO PRICE ,Reach-1,6
Up Type=0
Dn Type=3
Dn Slope=0.005
Boundary for River Rch & Prof#=TRIB 2 TO PRICE ,Reach-1,7
Up Type=0
Dn Type=3
Dn Slope=0.005

--- TRIB 2 TO PRICE CREEK.g01 (geometry) ---

Geom Title=Existing Conditions

River Reach=TRIB 2 TO PRICE ,Reach-1
Reach XY= 30
      2563075.00     13547925.00      2562985.42     13547926.02
      2562923.42     13547971.33      2562845.10     13547975.10
      2562822.69     13547969.32      2562781.06     13547933.15
      2562764.50     13547926.22      2562590.22     13547924.48
      2562568.94     13547916.86      2562519.06     13547877.25
      2562399.92     13547874.76      2562372.65     13547880.70
      2562323.26     13547920.81      2562272.82     13547931.12
      2562231.08     13547966.91      2562209.79     13547974.49
      2561680.93     13547972.76      2561627.17     13547931.14
      2561565.32     13547914.24      2561441.64     13547791.68
      2561428.95     13547773.37      2561418.90     13547722.81
      2561379.19     13547673.26      2561366.87     13547618.93
      2561284.70     13547535.77      2561218.96     13547516.82
      2561123.50     13547428.62      2561030.97     13547422.66
      2560964.58     13547376.02      2560875.00     13547375.00

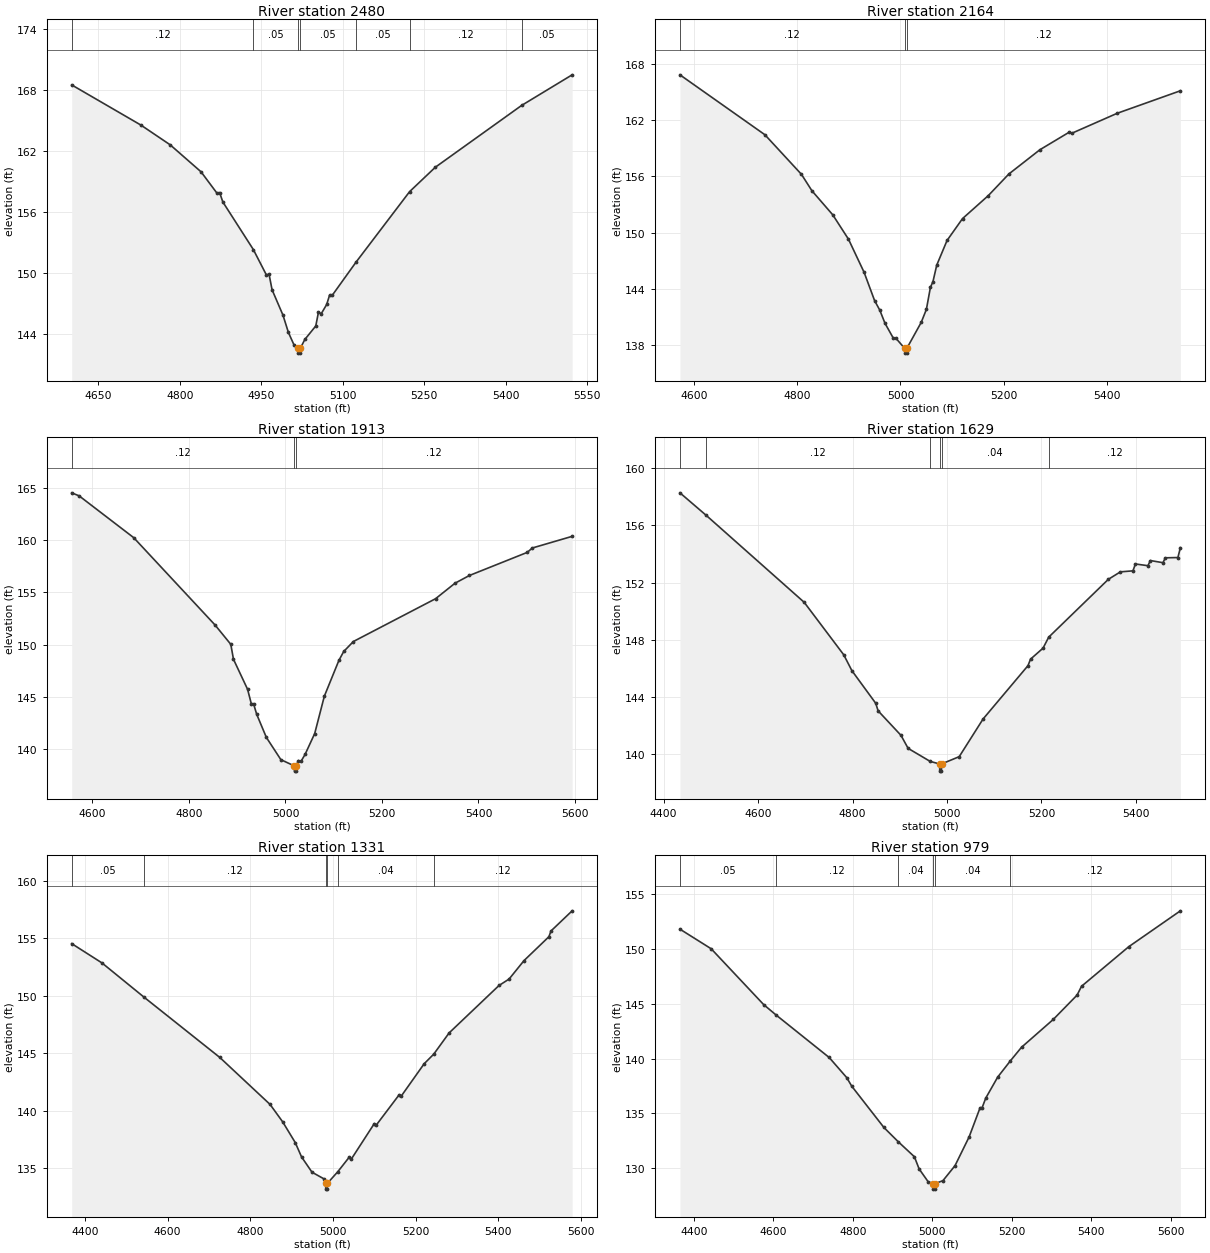
Type RM Length L Ch R = 1,2480,316,316,316
BEGIN DESCRIPTION:
LGII3037
END DESCRIPTION:
XS GIS Cut Line= 3
      2563039.65     13547528.24      2562987.76     13548000.48
      2563003.32     13548446.72
#Sta/Elev= 30
  4601.1  168.48  4728.6  164.53  4782.5  162.59  4839.3  159.94  4868.5  157.85
  4873.5  157.90  4879.5  156.97  4935.6  152.30  4959.5  149.82  4964.6  149.86
  4970.1  148.35  4990.2  145.85  5000.2  144.15  5010.3  142.95  5018.4  142.62
  5018.6  142.12  5022.1  142.12  5022.4  142.62  5030.4  143.46  5050.6  144.79
  5055.6  146.16  5060.6  145.99  5070.7  146.90  5075.9  147.80  5080.9  147.80
  5124.7  151.06  5223.4  157.99  5270.8  160.39  5429.6  166.46  5522.7  169.47
#Mann=7,-1,0
  4601.1    0.12       0  4935.6    0.05       0  5018.4    0.05       0
  5022.4    0.05       0  5124.7    0.05       0  5223.4    0.12       0
  5429.6    0.05       0
Bank Sta=5018.4,5022.4
Exp/Cntr=0.3,0.1

Type RM Length L Ch R = 1,2164,251,251,251
BEGIN DESCRIPTION:
LGII3036
END DESCRIPTION:
XS GIS Cut Line= 3
      2562780.20     13547502.32      2562712.74     13547912.27
      2562691.98     13548467.52
#Sta/Elev= 30
  4572.1  166.83  4737.0  160.44  4807.9  156.22  4828.2  154.47  4868.7  151.90
  4899.1  149.31  4929.5  145.77  4949.8  142.76  4959.9  141.74  4970.1  140.33
  4986.4  138.73  4991.4  138.73  5008.3  137.66  5008.6  137.16  5012.1  137.16
  5012.3  137.66  5040.3  140.44  5050.3  141.82  5058.1  144.16  5063.1  144.79
  5070.4  146.54  5090.4  149.17  5120.4  151.50  5170.4  153.95  5210.4  156.26
  5270.5  158.84  5327.0  160.70  5332.1  160.59  5420.6  162.73  5543.2  165.13
#Mann=3,-1,0
  4572.1    0.12       0  5008.3    0.05       0  5012.3    0.12       0
Bank Sta=5008.3,5012.3
Exp/Cntr=0.3,0.1

Type RM Length L Ch R = 1,1913,284,284,284
BEGIN DESCRIPTION:
LGII3035
END DESCRIPTION:
XS GIS Cut Line= 3
      2562619.35     13547460.79      2562474.04     13547808.49
      2562515.55     13548467.44
#Sta/Elev= 30
  4557.0  164.57  4572.4  164.28  4685.6  160.26  4854.2  151.87  4886.7  150.02
  4892.3  148.58  4921.5  145.70  4929.2  144.32  4933.8  144.32  4940.4  143.30
  4960.4  141.08  4990.5  138.94  5018.5  138.34  5018.8  137.84  5022.3  137.84
  5022.5  138.34  5027.0  138.86  5032.1  138.77  5040.6  139.44  5060.6  141.45
  5080.6  145.04  5110.7  148.47  5120.7  149.33  5140.8  150.29  5311.1  154.40
  5351.4  155.89  5381.2  156.63  5501.1  158.85  5511.5  159.27  5594.1  160.39
#Mann=3,-1,0
  4557.0    0.12       0  5018.5    0.05       0  5022.5    0.12       0
Bank Sta=5018.5,5022.5
Exp/Cntr=0.3,0.1

Type RM Length L Ch R = 1,1629,298,298,298
BEGIN DESCRIPTION:
LGII3034
END DESCRIPTION:
XS GIS Cut Line= 3
      2562256.10     13547414.14      2562193.84     13547875.95
      2562380.07     13548439.81
#Sta/Elev= 30
  4434.5  158.27  4490.0  156.70  4697.7  150.62  4781.5  146.95  4798.6  145.85
  4849.1  143.57  4854.2  143.04  4902.6  141.33  4917.7  140.42  4964.4  139.51
  4984.4  139.33  4984.7  138.83  4988.2  138.83  4988.4  139.33  5025.9  139.84
  5076.4  142.47  5171.6  146.20  5176.9  146.65  5203.4  147.42  5215.5  148.19
  5341.8  152.23  5367.3  152.75  5393.8  152.82  5399.1  153.30  5425.5  153.18
  5430.8  153.54  5457.3  153.39  5462.6  153.73  5489.0  153.75  5494.3  154.44
#Mann=6,-1,0
  4434.5    0.05       0  4490.0    0.12       0  4964.4    0.04       0
  4984.4    0.04       0  4988.4    0.04       0  5215.5    0.12       0
Bank Sta=4984.4,4988.4
Exp/Cntr=0.3,0.1

Type RM Length L Ch R = 1,1331,352,352,352
BEGIN DESCRIPTION:
LGII3033
END DESCRIPTION:
XS GIS Cut Line= 2
      2562032.97     13547351.90      2561830.60     13548545.36
#Sta/Elev= 30
  4368.0  154.54  4441.3  152.86  4543.5  149.87  4726.1  144.65  4847.9  140.56
  4878.3  139.05  4908.7  137.25  4924.0  136.00  4949.3  134.67  4979.3  134.07
  4982.4  133.70  4982.6  133.20  4986.1  133.20  4986.4  133.70  5011.6  134.71
  5039.6  135.99  5044.7  135.83  5100.0  138.90  5105.0  138.78  5160.3  141.41
  5165.4  141.30  5220.6  144.10  5243.7  144.93  5281.0  146.78  5401.6  150.90
  5426.0  151.46  5462.0  153.06  5522.3  155.14  5527.4  155.64  5578.5  157.39
#Mann=6,-1,0
  4368.0    0.05       0  4543.5    0.12       0  4982.4    0.05       0
  4986.4    0.12       0  5011.6    0.04       0  5243.7    0.12       0
Bank Sta=4982.4,4986.4
Exp/Cntr=0.3,0.1

Type RM Length L Ch R = 1,979,358,358,358
BEGIN DESCRIPTION:
LGII3032
END DESCRIPTION:
XS GIS Cut Line= 3
      2561887.70     13547362.21      2561534.84     13548031.62
      2561545.21     13548535.00
#Sta/Elev= 30
  4364.6  151.80  4443.3  150.01  4575.5  144.92  4607.5  143.95  4740.4  140.10
  4784.5  138.27  4797.3  137.48  4878.2  133.72  4914.3  132.42  4955.0  131.05
  4966.9  129.94  4989.5  128.78  5002.7  128.60  5003.0  128.10  5006.5  128.10
  5006.7  128.60  5026.8  128.87  5057.3  130.24  5092.8  132.86  5120.4  135.52
  5125.5  135.52  5134.7  136.40  5164.7  138.31  5196.6  139.79  5224.7  141.03
  5304.7  143.57  5364.7  145.79  5375.8  146.59  5494.8  150.20  5624.8  153.47
#Mann=6,-1,0
  4364.6    0.05       0  4607.5    0.12       0  4914.3    0.04       0
  5002.7    0.04       0  5006.7    0.04       0  5196.6    0.12       0
Bank Sta=5002.7,5006.7
Exp/Cntr=0.3,0.1

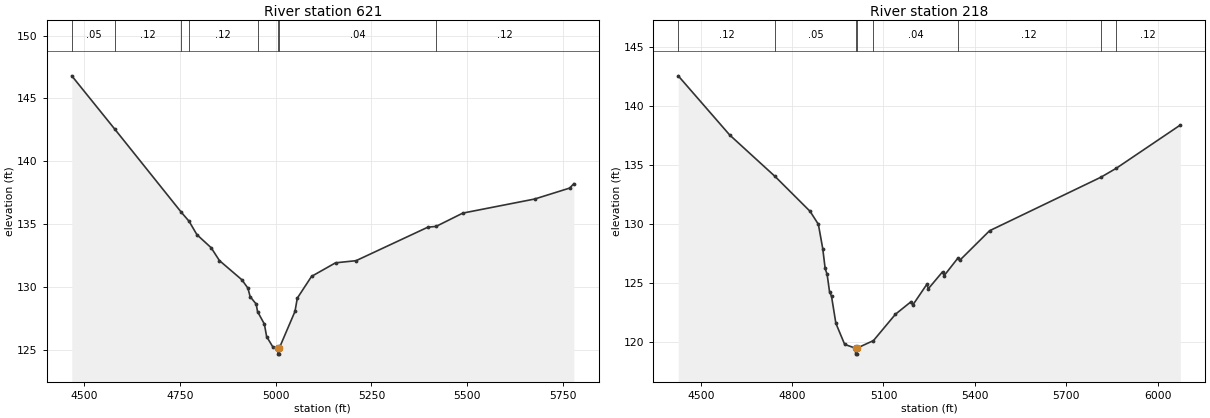
Type RM Length L Ch R = 1,621,403,403,403
BEGIN DESCRIPTION:
LGII3031
END DESCRIPTION:
XS GIS Cut Line= 3
      2561643.83     13547196.15      2561296.14     13547792.92
      2561228.71     13548410.18
#Sta/Elev= 30
  4467.3  146.80  4580.3  142.53  4753.9  135.92  4773.7  135.22  4794.3  134.15
  4831.5  133.11  4853.0  132.09  4911.7  130.56  4927.5  129.89  4933.2  129.22
  4949.0  128.63  4952.6  128.03  4970.5  127.03  4976.3  126.04  4992.0  125.24
  5005.7  125.14  5005.9  124.64  5009.4  124.64  5009.7  125.14  5050.4  128.04
  5056.5  129.10  5093.7  130.83  5156.3  131.91  5209.9  132.08  5397.6  134.75
  5419.0  134.81  5488.9  135.87  5676.5  136.99  5767.8  137.86  5778.9  138.21
#Mann=8,-1,0
  4467.3    0.05       0  4580.3    0.12       0  4753.9    0.05       0
  4773.7    0.12       0  4952.6    0.04       0  5005.7    0.04       0
  5009.7    0.04       0  5419.0    0.12       0
Bank Sta=5005.7,5009.7
Exp/Cntr=0.3,0.1

Type RM Length L Ch R = 1,218,0,0,0
BEGIN DESCRIPTION:
LGII3030
END DESCRIPTION:
XS GIS Cut Line= 4
      2561436.23     13546978.27      2561078.20     13547419.31
      2560979.61     13547922.65      2561140.23     13548466.67
#Sta/Elev= 30
  4426.2  142.57  4595.3  137.54  4744.2  134.02  4859.0  131.06  4886.2  129.96
  4900.6  127.89  4908.5  126.21  4915.0  125.70  4922.9  124.23  4929.4  123.84
  4943.7  121.55  4972.5  119.76  5008.3  119.43  5008.5  118.93  5012.0  118.93
  5012.3  119.43  5067.1  120.08  5139.3  122.32  5190.8  123.39  5195.9  123.09
  5242.3  124.86  5247.4  124.49  5293.8  125.92  5298.9  125.59  5343.4  127.06
  5350.4  126.90  5448.2  129.41  5813.9  133.96  5863.7  134.71  6074.4  138.39
#Mann=8,-1,0
  4426.2    0.12       0  4744.2    0.05       0  5008.3    0.05       0
  5012.3    0.05       0  5067.1    0.04       0  5343.4    0.12       0
  5813.9    0.05       0  5863.7    0.12       0
Bank Sta=5008.3,5012.3
Exp/Cntr=0.3,0.1

Chan Stop Cuts=-1