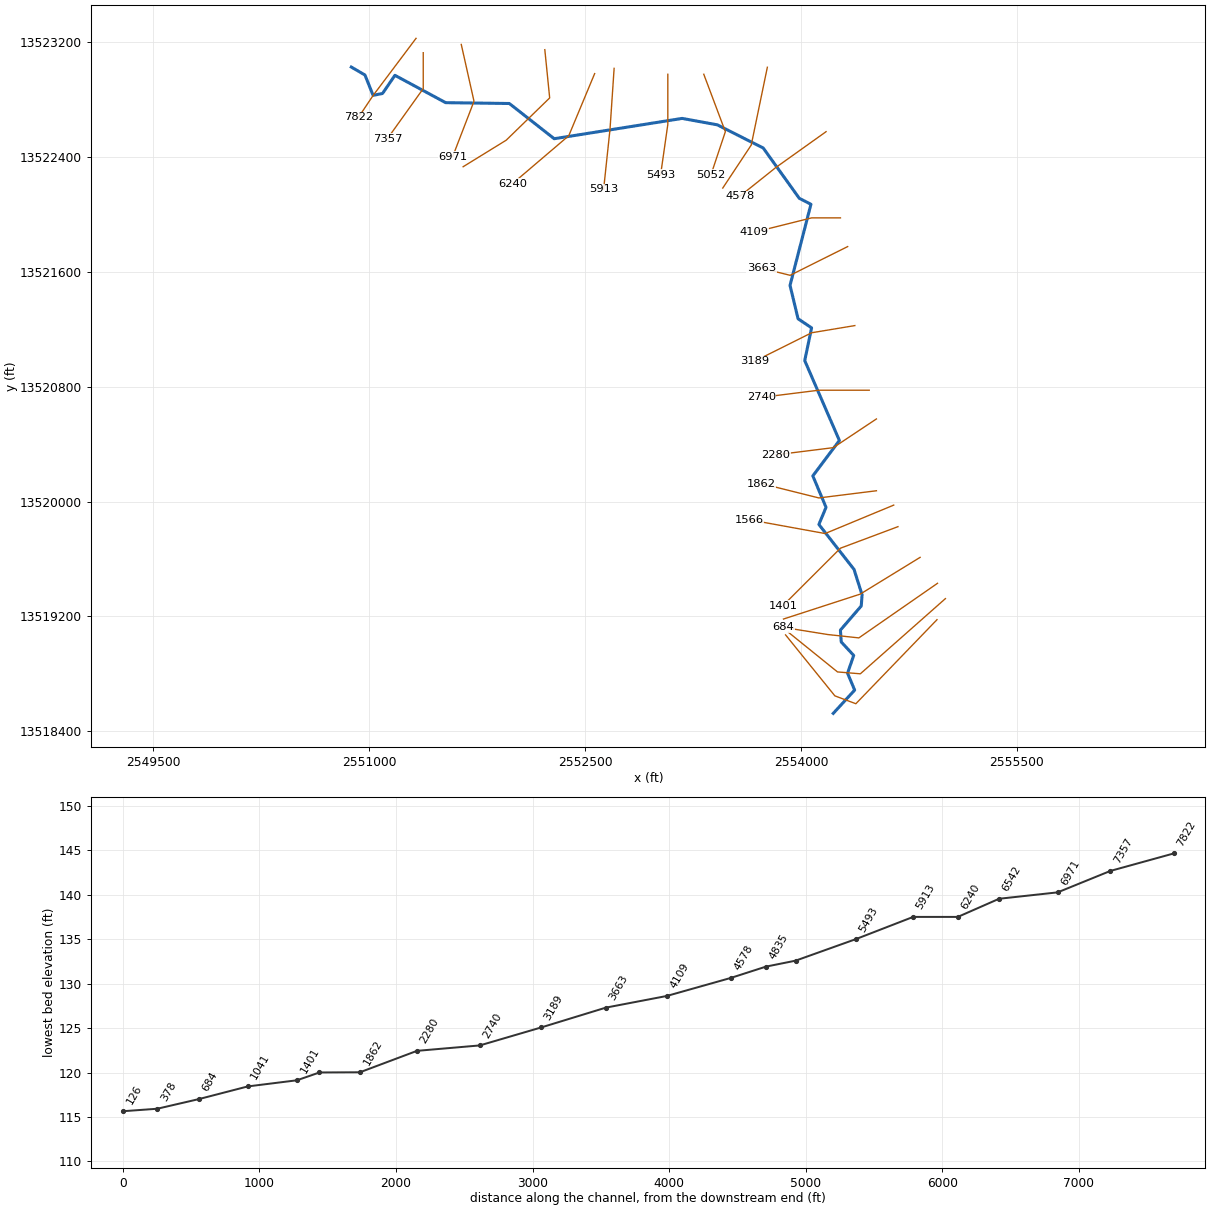
--- TRIB 2 TO ROCKY CREEK.prj (project) ---

Proj Title=TRIB 2 TO ROCKY CREEK Base Level Engineering
Current Plan=p01
Default Exp/Contr=0.3,0.1
English Units
Geom File=g01
Flow File=f01
Plan File=p01
Y Axis Title=Elevation
X Axis Title(PF)=Main Channel Distance
X Axis Title(XS)=Station
BEGIN DESCRIPTION:
TRIB 2 TO ROCKY CREEK
END DESCRIPTION:
DSS Export Rating Curves= 0
DSS Export Rating Curve Sorted= 0
DSS Export Volume Flow Curves= 0
DXF OffsetX= 0
DXF OffsetY= 0
DXF ScaleX= 1
DXF ScaleY= 10

--- TRIB 2 TO ROCKY CREEK.p01 (plan) ---

Plan Title=Multiple Run
Short Identifier=Multiple
Geom File=g01
Flow File=f01
Subcritical Flow
K Sum by GR= 0
Std Step Tol= 0.01
Critical Tol= 0.01
Num of Std Step Trials= 20
Max Error Tol= 0.3
Flow Tol Ratio= 0.001
Split Flow NTrial= 30
Split Flow Tol= 0.02
Split Flow Ratio= 0.02
Log Output Level= 0
Friction Slope Method= 1
Unsteady Friction Slope Method= 2
Unsteady Bridges Friction Slope Method= 1
Parabolic Critical Depth
Global Vel Dist=  1 , 1 , 1
Global Log Level= 0
CheckData=True
Encroach Param= -1, 0, 0, 0
BEGIN DESCRIPTION:
Multiple Run
END DESCRIPTION:

--- TRIB 2 TO ROCKY CREEK.f01 (steady flow) ---

Flow Title=Multiple
Number of Profiles=7
Profile Names=10-year,25-year,50-year,1pct_min,100-year,1pct_plu,500-year
River Rch & RM= TRIB 2 TO ROCKY ,Reach-1,7822
     757    1215    1627    1054    2103    4195    3472
River Rch & RM= TRIB 2 TO ROCKY ,Reach-1,7357
     887    1436    1933    1258    2510    5008    4185
River Rch & RM= TRIB 2 TO ROCKY ,Reach-1,4835
    1070    1741    2352    1536    3064    6113    5140
Boundary for River Rch & Prof#=TRIB 2 TO ROCKY ,Reach-1,1
Up Type=0
Dn Type=3
Dn Slope=0.005
Boundary for River Rch & Prof#=TRIB 2 TO ROCKY ,Reach-1,2
Up Type=0
Dn Type=3
Dn Slope=0.005
Boundary for River Rch & Prof#=TRIB 2 TO ROCKY ,Reach-1,3
Up Type=0
Dn Type=3
Dn Slope=0.005
Boundary for River Rch & Prof#=TRIB 2 TO ROCKY ,Reach-1,4
Up Type=0
Dn Type=3
Dn Slope=0.005
Boundary for River Rch & Prof#=TRIB 2 TO ROCKY ,Reach-1,5
Up Type=0
Dn Type=3
Dn Slope=0.005
Boundary for River Rch & Prof#=TRIB 2 TO ROCKY ,Reach-1,6
Up Type=0
Dn Type=3
Dn Slope=0.005
Boundary for River Rch & Prof#=TRIB 2 TO ROCKY ,Reach-1,7
Up Type=0
Dn Type=3
Dn Slope=0.005

--- TRIB 2 TO ROCKY CREEK.g01 (geometry) ---

Geom Title=Existing Conditions
Program Version=4.10

River Reach=TRIB 2 TO ROCKY ,Reach-1
Reach XY= 30
        2550875.       13523025.      2550969.89     13522969.73
      2551026.43     13522827.99      2551092.04     13522841.05
      2551178.15     13522967.47      2551530.86     13522777.07
      2551973.45     13522771.25      2552285.43     13522526.05
        2553175.     13522667.44      2553419.06     13522622.74
      2553738.24     13522461.38      2553988.56     13522111.47
      2554069.87     13522069.52      2553924.61     13521504.87
       2553980.4     13521272.32      2554074.34     13521209.15
       2554026.8     13520981.11      2554267.71     13520424.91
      2554083.04     13520178.32       2554174.9      13519959.6
      2554125.08     13519840.39      2554369.46     13519527.42
      2554425.41       13519350.       2554419.6     13519272.57
      2554274.78     13519104.94      2554280.43     13519022.57
      2554367.19     13518928.41      2554324.43     13518804.95
      2554373.83     13518687.01        2554225.       13518525.

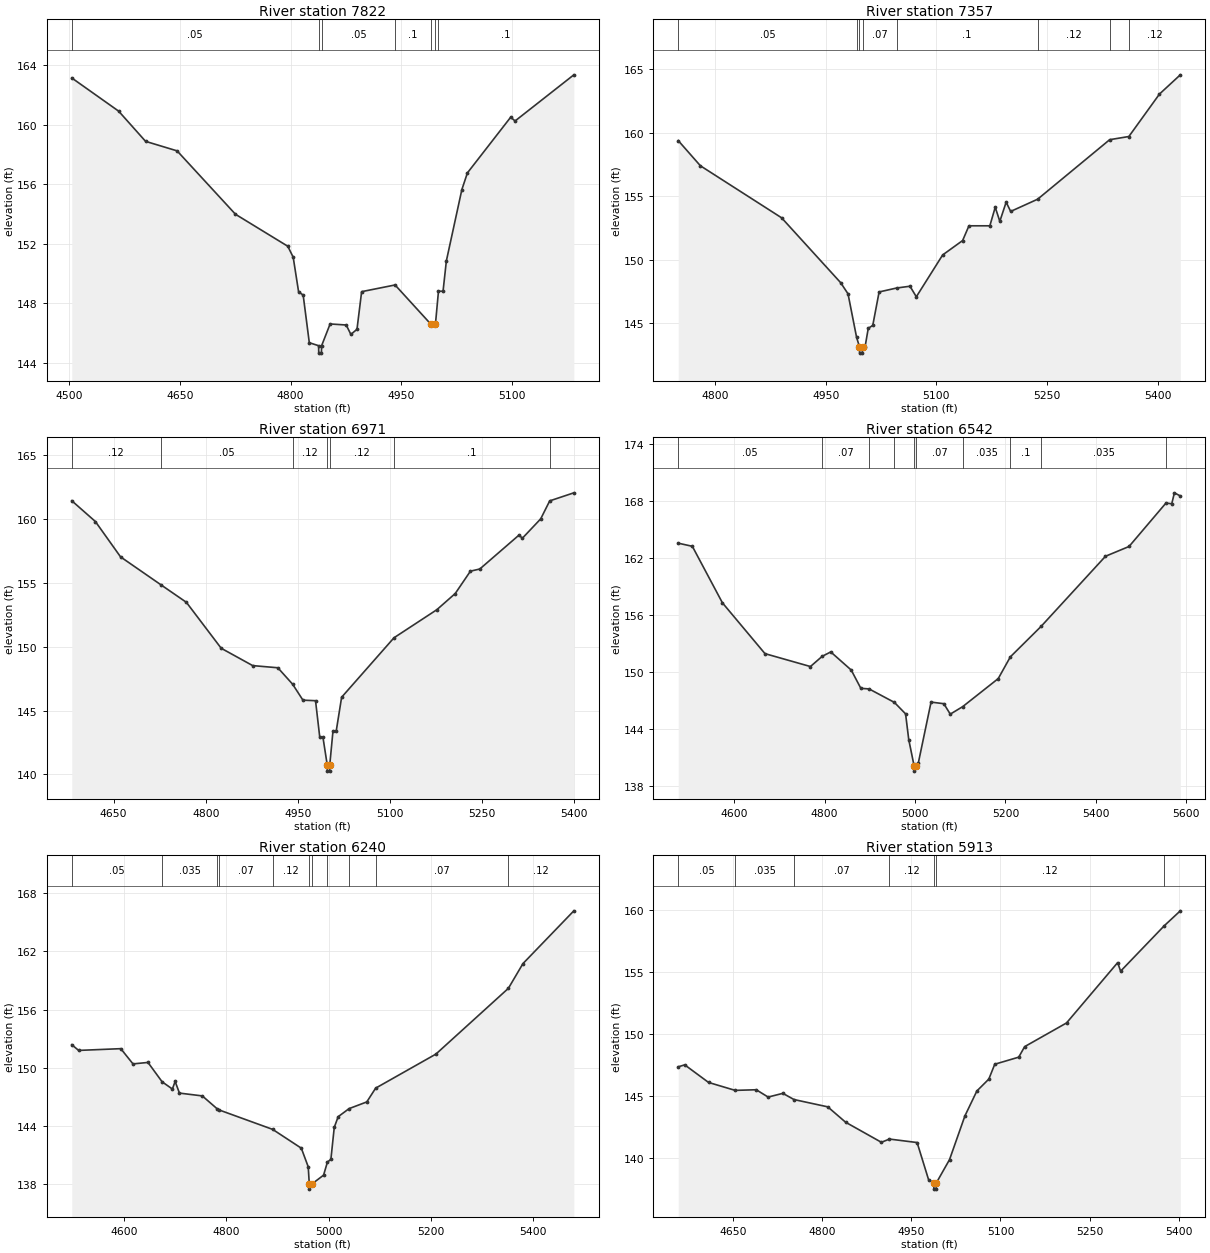
Type RM Length L Ch R = 1 ,7822    ,465,465,465
BEGIN DESCRIPTION:
TRIB 2 TO ROCKY CREEK 16.0
END DESCRIPTION:
XS GIS Cut Line= 3
      2551324.98     13523224.97        2551025.       13522825.
      2550925.02     13522675.03
#Sta/Elev= 30
  4503.5  163.13    4567   160.9  4603.5  158.87  4646.2  158.23  4725.3  153.97
  4796.2  151.82  4803.5  151.08  4810.8  148.76    4817  148.54  4825.3  145.34
  4837.9  145.14  4838.1  144.64  4841.7  144.64    4842  145.14  4853.5   146.6
  4875.3  146.53  4881.6   145.9  4889.9  146.24  4896.2  148.77  4941.5  149.22
  4989.9  146.59  4996.2  146.59  5000.3   148.8  5006.5   148.8    5011  150.84
    5032  155.63  5039.5  156.75  5098.1  160.49  5104.1  160.24  5183.7  163.34
#Mann= 7 ,-1 , 0
  4503.5     .05       0  4837.9     .07       0    4842     .05       0
  4941.5      .1       0  4989.9     .05       0  4996.2     .07       0
  5000.3      .1       0
Bank Sta=4989.9,4996.2
XS Rating Curve= 0 ,0
Exp/Cntr=0.3,0.1

Type RM Length L Ch R = 1 ,7357    ,386,386,386
BEGIN DESCRIPTION:
TRIB 2 TO ROCKY CREEK 15.0
END DESCRIPTION:
XS GIS Cut Line= 3
        2551375.     13523125.01        2551375.       13522875.
      2551125.02     13522525.02
#Sta/Elev= 30
  4750.3  159.38  4780.3   157.4  4890.3  153.31  4970.3  148.21  4980.3  147.33
  4991.9  143.91  4995.8  143.17    4996  142.67  4999.6  142.67  4999.9  143.17
  5003.4  143.17  5007.7  144.62  5013.8  144.85  5022.4  147.48  5046.2  147.79
  5064.2  147.93  5072.8   147.1  5108.5  150.39  5135.5  151.52  5144.1  152.68
  5172.4  152.68  5179.7  154.14  5185.9  153.03  5194.5  154.54  5200.6  153.81
  5237.1  154.77  5334.7  159.45  5360.7   159.7  5402.2  163.04  5430.4  164.55
#Mann= 8 ,-1 , 0
  4750.3     .05       0  4991.9     .07       0  4995.8     .05       0
  4999.9     .07       0  5046.2      .1       0  5237.1     .12       0
  5334.7      .1       0  5360.7     .12       0
Bank Sta=4995.8,4999.9
XS Rating Curve= 0 ,0
Exp/Cntr=0.3,0.1

Type RM Length L Ch R = 1 ,6971    ,429,429,429
BEGIN DESCRIPTION:
Mapping XS a3f3fbe8
END DESCRIPTION:
XS GIS Cut Line= 3
      2551639.33     13523182.56      2551727.87     13522786.71
       2551579.7     13522401.99
#Sta/Elev= 30
  4581.8  161.45  4620.3  159.82  4661.3  157.05  4726.8  154.87  4768.5  153.49
  4825.2  149.89  4876.5  148.53  4917.5  148.36  4941.6  147.07  4958.4  145.82
  4978.9  145.78  4985.8  142.91    4991  142.91  4997.9  140.76  4998.1  140.26
  5001.8  140.26  5002.1  140.76  5007.3  143.39  5012.7  143.43  5021.4  146.05
  5106.7  150.71  5176.5  152.91  5206.5  154.18  5231.2  155.93  5246.5   156.1
  5310.4  158.76  5315.8  158.51  5345.7  160.03  5360.4  161.44  5399.7  162.07
#Mann= 7 ,-1 , 0
  4581.8     .12       0  4726.8     .05       0  4941.6     .12       0
  4997.9     .05       0  5002.1     .12       0  5106.7      .1       0
  5360.4     .12       0
Bank Sta=4997.9,5002.1
XS Rating Curve= 0 ,0
Exp/Cntr=0.3,0.1

Type RM Length L Ch R = 1 ,6542    ,302,302,302
BEGIN DESCRIPTION:
Mapping XS f6c9dc0e
END DESCRIPTION:
XS GIS Cut Line= 4
      2552220.06     13523146.08      2552253.91     13522810.15
      2551951.83     13522515.87      2551652.36     13522330.99
#Sta/Elev= 30
  4475.9  163.58  4507.1  163.25  4573.7  157.29  4667.9  151.93  4768.5  150.57
  4794.6  151.65  4813.5  152.11  4858.8   150.2  4880.1  148.27  4898.3  148.21
  4954.3  146.79  4979.1  145.58  4986.1  142.87  4998.2  140.04  4998.4  139.54
  5002.4  140.04  5007.4  140.42  5035.5  146.82  5063.8  146.65    5078  145.55
  5105.5  146.34  5184.2   149.3    5211  151.59    5279   154.8  5421.6   162.2
  5473.7  163.23  5555.4  167.81  5568.3  167.74  5574.1  168.89  5587.2  168.56
#Mann= 10 ,-1 , 0
  4475.9     .05       0  4794.6     .07       0  4898.3     .05       0
  4954.3     .07       0  4998.2     .05       0  5002.4     .07       0
  5105.5    .035       0    5211      .1       0    5279    .035       0
  5555.4     .12       0
Bank Sta=4998.2,5002.4
XS Rating Curve= 0 ,0
Exp/Cntr=0.3,0.1

Type RM Length L Ch R = 1 ,6240    ,327,327,327
BEGIN DESCRIPTION:
Mapping XS 3e25b2f5
END DESCRIPTION:
XS GIS Cut Line= 3
       2552566.4     13522979.39      2552386.73     13522547.12
      2551996.13     13522213.81
#Sta/Elev= 30
  4497.5  152.39  4510.9   151.8  4593.3  151.98  4617.2  150.41  4646.5  150.56
  4674.2  148.56  4694.2  147.82  4699.6   148.6    4708   147.4  4752.7  147.11
  4782.2  145.76  4785.7  145.66  4890.2  143.66  4946.3  141.72  4959.8   139.8
  4961.9     138  4962.2   137.5  4966.2     138  4989.8  138.94  4997.3  140.29
  5004.1  140.57  5010.7  143.87  5018.4  144.97  5039.7   145.8  5074.3  146.49
  5091.6  147.91  5209.4  151.42  5351.1   158.2  5379.6  160.75  5479.1  166.19
#Mann= 11 ,-1 , 0
  4497.5     .05       0  4674.2    .035       0  4782.2     .12       0
  4785.7     .07       0  4890.2     .12       0  4961.9     .05       0
  4966.2     .12       0  4997.3     .07       0  5039.7     .12       0
  5091.6     .07       0  5351.1     .12       0
Bank Sta=4961.9,4966.2
XS Rating Curve= 0 ,0
Exp/Cntr=0.3,0.1

Type RM Length L Ch R = 1 ,5913    ,420,420,420
BEGIN DESCRIPTION:
Mapping XS f8f7958e
END DESCRIPTION:
XS GIS Cut Line= 3
      2552701.83     13523015.88      2552673.19      13522591.4
      2552628.91     13522174.69
#Sta/Elev= 30
    4558  147.37  4568.9  147.53    4609  146.11  4653.7  145.47  4689.2  145.52
  4709.2  144.93    4734  145.23  4752.7  144.73  4809.5  144.14  4839.5   142.9
  4899.7  141.28  4913.3  141.54  4959.8  141.26  4979.1  138.26  4987.7     138
    4988   137.5  4991.8   137.5  4992.1     138  5014.3  139.88  5040.2  143.41
  5060.3  145.42  5080.4  146.38  5090.4  147.58  5130.7  148.15  5140.7     149
  5211.1  150.91  5297.1  155.78  5302.1  155.09  5375.6  158.76  5402.5  159.96
#Mann= 7 ,-1 , 0
    4558     .05       0  4653.7    .035       0  4752.7     .07       0
  4913.3     .12       0  4987.7     .05       0  4992.1     .12       0
  5375.6     .07       0
Bank Sta=4987.7,4992.1
XS Rating Curve= 0 ,0
Exp/Cntr=0.3,0.1

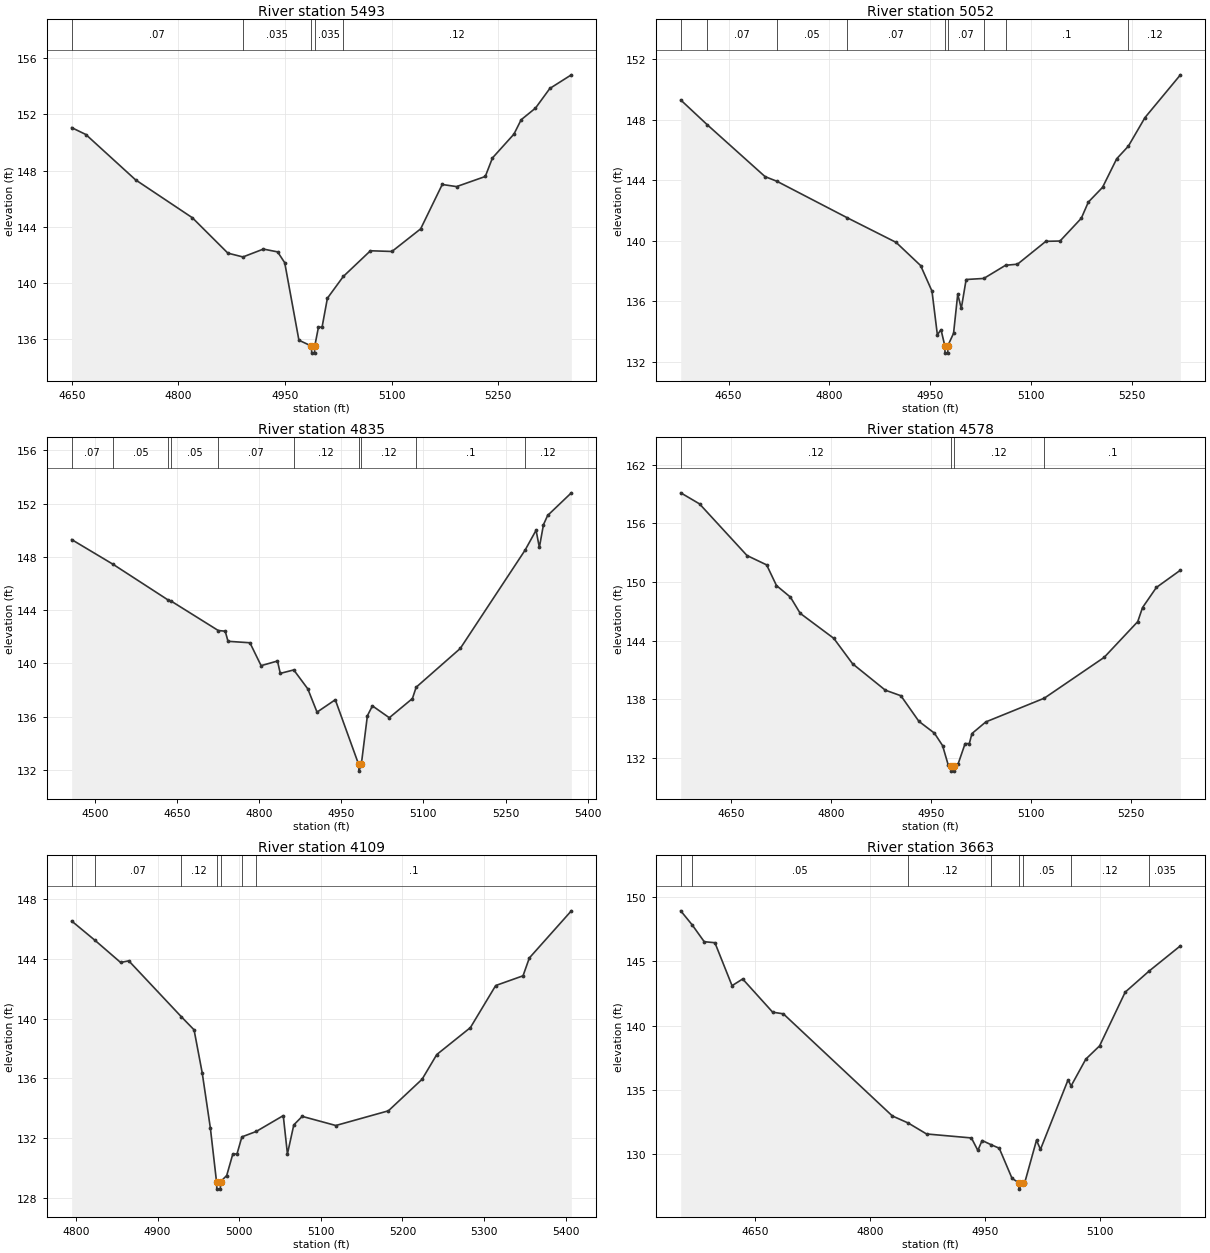
Type RM Length L Ch R = 1 ,5493    ,441,441,441
BEGIN DESCRIPTION:
TRIB 2 TO ROCKY CREEK 11.0
END DESCRIPTION:
XS GIS Cut Line= 3
        2553075.     13522975.03        2553075.       13522625.
        2553025.     13522274.98
#Sta/Elev= 30
  4649.6  151.06  4669.6  150.57  4739.6  147.34  4819.6  144.64  4869.6  142.12
  4890.8  141.85  4919.6  142.41  4939.6  142.21  4949.6  141.44  4969.6  135.92
  4987.3   135.5  4987.6     135  4991.6     135  4991.9   135.5  4997.1  136.85
  5002.2  136.85  5009.7  138.91  5032.1  140.46  5070.3  142.29  5100.6  142.24
    5141  143.85  5171.4  147.01  5191.6  146.86    5232  147.58  5242.1   148.9
  5272.4   150.6  5282.5  151.62  5302.7  152.45  5322.9  153.85  5353.2  154.82
#Mann= 5 ,-1 , 0
  4649.6     .07       0  4890.8    .035       0  4987.3    .035       0
  4991.9    .035       0  5032.1     .12       0
Bank Sta=4987.3,4991.9
XS Rating Curve= 0 ,0
Exp/Cntr=0.3,0.1

Type RM Length L Ch R = 1 ,5052    ,217,217,217
BEGIN DESCRIPTION:
TRIB 2 TO ROCKY CREEK 10.0
END DESCRIPTION:
XS GIS Cut Line= 3
      2553324.99     13522975.02        2553475.       13522575.
      2553375.02     13522275.05
#Sta/Elev= 30
  4578.9  149.29    4618  147.67  4704.4  144.23  4722.2  143.92  4826.4  141.52
  4899.3  139.89  4935.8  138.36  4952.7  136.67  4960.7  133.79  4966.1  134.13
  4971.7  133.08  4972.1  132.58  4976.1  132.58  4976.4  133.08  4984.8  133.89
    4991  136.47  4996.3  135.53  5003.5  137.44  5029.8  137.51  5062.2  138.38
  5079.9  138.45  5122.1  139.96  5143.2  139.98  5174.8  141.48  5185.3  142.55
  5206.4  143.52  5227.5  145.41  5244.8  146.24  5269.6  148.13  5322.3  150.95
#Mann= 9 ,-1 , 0
  4578.9     .12       0    4618     .07       0  4722.2     .05       0
  4826.4     .07       0  4971.7     .05       0  4976.4     .07       0
  5029.8     .12       0  5062.2      .1       0  5244.8     .12       0
Bank Sta=4971.7,4976.4
XS Rating Curve= 0 ,0
Exp/Cntr=0.3,0.1

Type RM Length L Ch R = 1 ,4835    ,257,257,257
BEGIN DESCRIPTION:
Mapping XS 991f6330
END DESCRIPTION:
XS GIS Cut Line= 3
      2553766.93     13523023.65      2553654.96     13522482.02
      2553457.02      13522182.5
#Sta/Elev= 30
  4457.9   149.3  4533.2  147.45  4634.4  144.75  4639.1  144.69  4725.5  142.47
  4738.2  142.42  4743.3  141.66  4783.3  141.55  4803.7  139.83  4833.6  140.18
  4838.7  139.25  4863.3  139.51  4888.9  138.09  4905.8  136.34  4939.1  137.27
  4981.8  132.41  4982.2  131.91  4986.6  132.41  4997.7  136.07  5006.9  136.81
  5037.7  135.92  5079.9  137.36  5086.7  138.21  5167.2  141.12  5285.6  148.51
  5305.6     150  5311.6  148.71  5319.1  150.42  5326.7  151.11    5370  152.81
#Mann= 10 ,-1 , 0
  4457.9     .07       0  4533.2     .05       0  4634.4     .07       0
  4639.1     .05       0  4725.5     .07       0  4863.3     .12       0
  4981.8     .05       0  4986.6     .12       0  5086.7      .1       0
  5285.6     .12       0
Bank Sta=4981.8,4986.6
XS Rating Curve= 0 ,0
Exp/Cntr=0.3,0.1

Type RM Length L Ch R = 1 ,4578    ,469,469,469
BEGIN DESCRIPTION:
TRIB 2 TO ROCKY CREEK 9.0
END DESCRIPTION:
XS GIS Cut Line= 3
      2554174.99     13522574.99        2553825.       13522325.
      2553574.96     13522124.97
#Sta/Elev= 30
  4574.4  159.14  4602.6  158.01  4673.9  152.72  4703.4  151.76  4718.2  149.64
  4739.1  148.46  4753.8   146.8  4804.2  144.24  4832.5  141.63  4881.6  138.93
    4905  138.36    4932  135.74  4955.3  134.53  4967.6  133.25  4976.2  131.23
  4979.9  131.14  4980.3  130.64  4984.5  130.64  4984.8  131.14    4991   131.4
  5001.4  133.46  5007.7  133.46  5011.7  134.49  5032.5  135.68  5120.3  138.11
  5210.2  142.29  5260.6  145.95  5267.8  147.39  5288.6  149.45  5324.7  151.22
#Mann= 4 ,-1 , 0
  4574.4     .12       0  4979.9     .05       0  4984.8     .12       0
  5120.3      .1       0
Bank Sta=4979.9,4984.8
XS Rating Curve= 0 ,0
Exp/Cntr=0.3,0.1

Type RM Length L Ch R = 1 ,4109    ,446,446,446
BEGIN DESCRIPTION:
TRIB 2 TO ROCKY CREEK 8.0
END DESCRIPTION:
XS GIS Cut Line= 3
      2554275.02       13521975.        2554075.       13521975.
      2553675.03     13521875.01
#Sta/Elev= 30
  4794.7  146.52  4823.5  145.22  4854.7  143.75  4864.7  143.86    4929  140.13
  4944.7  139.25  4954.7  136.37  4964.7  132.68  4972.2  129.11  4972.6  128.61
  4976.8  128.61  4977.2  129.11  4984.7  129.52  4992.2  130.96  4997.3  130.96
  5003.3   132.1  5020.8  132.46    5054  133.52  5059.1  130.96  5066.9   132.9
  5077.2  133.47  5118.4  132.86  5182.8  133.84  5224.1  135.95  5242.1   137.6
  5283.3   139.4  5314.3  142.21  5347.8  142.86  5355.5  144.05    5407   147.2
#Mann= 7 ,-1 , 0
  4794.7     .12       0  4823.5     .07       0    4929     .12       0
  4972.2     .05       0  4977.2     .12       0  5003.3     .07       0
  5020.8      .1       0
Bank Sta=4972.2,4977.2
XS Rating Curve= 0 ,0
Exp/Cntr=0.3,0.1

Type RM Length L Ch R = 1 ,3663    ,474,474,474
BEGIN DESCRIPTION:
TRIB 2 TO ROCKY CREEK 7.0
END DESCRIPTION:
XS GIS Cut Line= 3
      2554324.99     13521774.99        2553925.       13521575.
      2553724.96     13521625.01
#Sta/Elev= 30
  4552.3  148.94  4567.5  147.83    4583  146.54    4597  146.46  4619.4  143.12
  4633.3  143.64  4672.5  141.06  4686.5  140.93    4829  132.99  4849.8  132.44
  4873.7  131.59  4932.4  131.28  4940.8  130.31  4946.4  131.08  4958.3  130.75
  4968.8  130.48  4985.5  128.14  4994.2   127.8  4994.6   127.3  4999.2   127.8
  5002.1   127.8  5017.5   131.1  5022.7  130.39  5058.8   135.8  5062.7  135.32
    5082  137.41    5100  138.44  5133.5  142.62  5164.8  144.26  5205.7  146.22
#Mann= 8 ,-1 , 0
  4552.3     .12       0  4567.5     .05       0  4849.8     .12       0
  4958.3     .05       0  4994.2     .05       0  4999.2     .05       0
  5062.7     .12       0  5164.8    .035       0
Bank Sta=4994.2,4999.2
XS Rating Curve= 0 ,0
Exp/Cntr=0.3,0.1

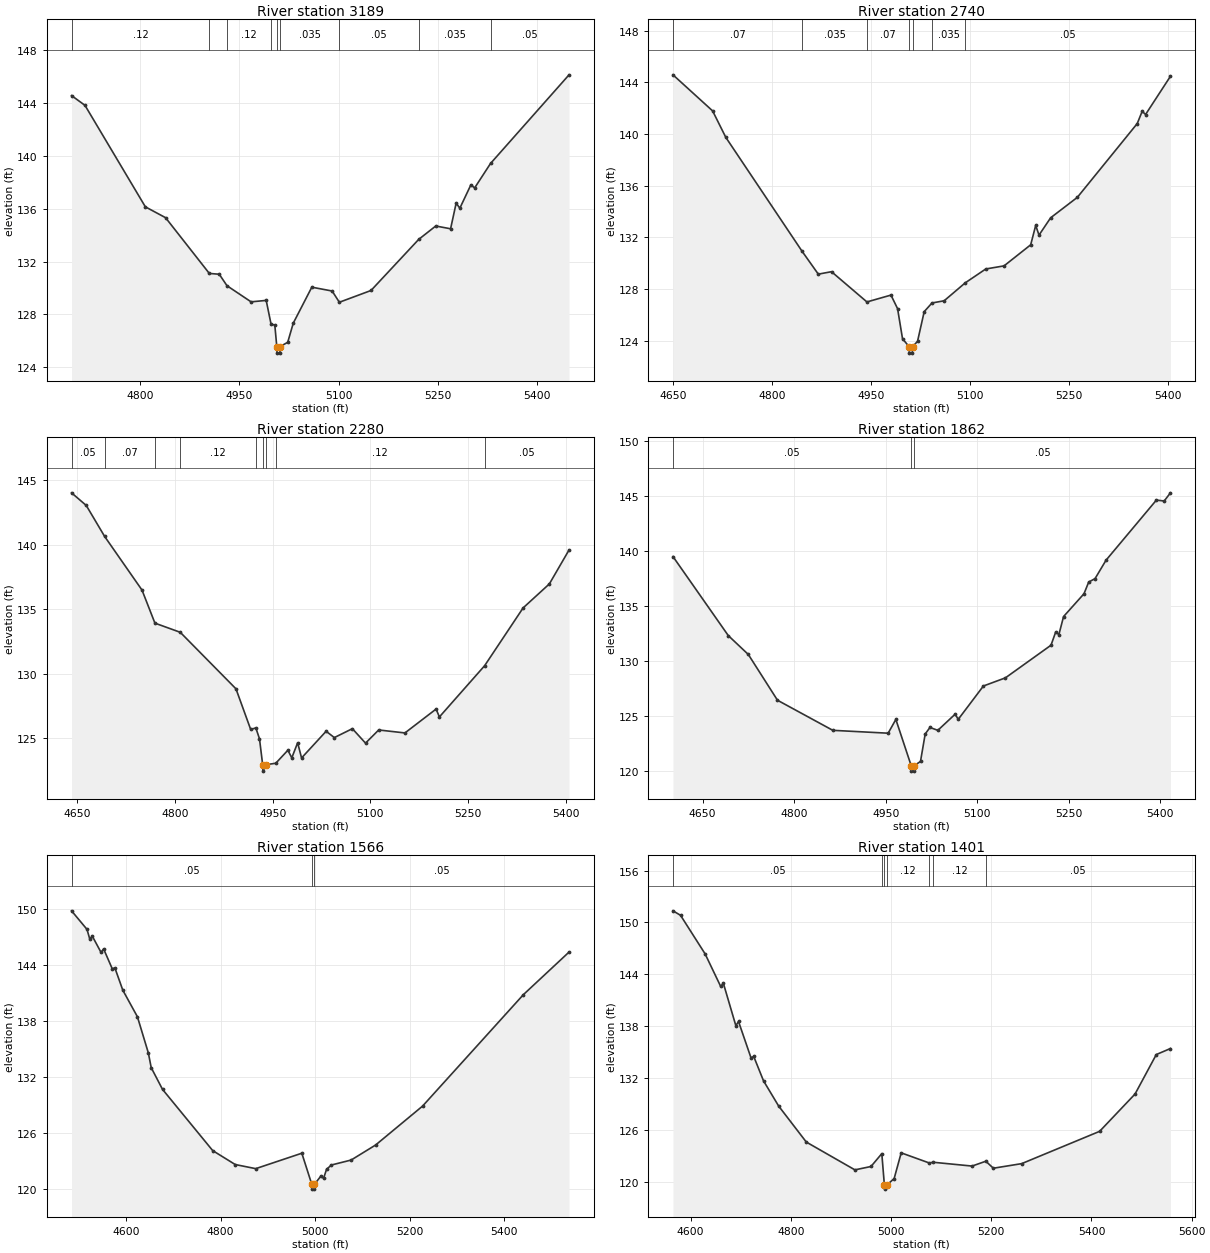
Type RM Length L Ch R = 1 ,3189    ,449,449,449
BEGIN DESCRIPTION:
TRIB 2 TO ROCKY CREEK 6.0
END DESCRIPTION:
XS GIS Cut Line= 3
      2554375.03     13521225.01        2554075.       13521175.
      2553674.99     13520974.99
#Sta/Elev= 30
  4696.5  144.56  4716.8  143.82    4808  136.14  4838.5  135.32  4904.6   131.1
  4919.6  131.04  4931.3  130.17  4967.7  128.95  4990.5  129.06  4997.9  127.25
  5003.5   127.2  5006.5  125.57  5006.9  125.07  5011.2  125.07  5011.6  125.57
    5023  125.89  5031.4  127.34  5059.4  130.06  5090.1  129.77    5101  128.92
  5148.8  129.81  5220.9  133.68  5246.6  134.69    5269  134.48  5277.4  136.42
    5283  136.04  5299.7  137.81  5305.3  137.57  5329.3  139.42  5447.9  146.13
#Mann= 9 ,-1 , 0
  4696.5     .12       0  4904.6     .05       0  4931.3     .12       0
  4997.9    .035       0  5006.5    .035       0  5011.6    .035       0
    5101     .05       0  5220.9    .035       0  5329.3     .05       0
Bank Sta=5006.5,5011.6
XS Rating Curve= 0 ,0
Exp/Cntr=0.3,0.1

Type RM Length L Ch R = 1 ,2740    ,460,460,460
BEGIN DESCRIPTION:
TRIB 2 TO ROCKY CREEK 5.0
END DESCRIPTION:
XS GIS Cut Line= 3
      2554475.03       13520775.        2554125.       13520775.
      2553725.05     13520725.01
#Sta/Elev= 30
  4650.3  144.58  4710.3  141.79  4730.3  139.74  4845.6  130.94  4870.3  129.16
  4890.3  129.35  4943.9  127.01  4980.3  127.54  4990.3  126.49  4997.8  124.16
  5007.8  123.55  5008.2  123.05  5012.6  123.05    5013  123.55  5020.5  123.96
  5030.6  126.26  5042.4  126.93  5060.8   127.1  5092.8  128.49  5123.8  129.56
  5151.5   129.8  5191.8  131.43  5199.4  132.93  5204.4  132.18    5222  133.52
  5262.4   135.1  5353.1  140.81  5360.6  141.76  5365.7  141.51  5403.4  144.47
#Mann= 7 ,-1 , 0
  4650.3     .07       0  4845.6    .035       0  4943.9     .07       0
  5007.8     .05       0    5013     .07       0  5042.4    .035       0
  5092.8     .05       0
Bank Sta=5007.8,5013
XS Rating Curve= 0 ,0
Exp/Cntr=0.3,0.1

Type RM Length L Ch R = 1 ,2280    ,418,418,418
BEGIN DESCRIPTION:
TRIB 2 TO ROCKY CREEK 4.0
END DESCRIPTION:
XS GIS Cut Line= 3
      2554525.04     13520575.03        2554225.       13520375.
      2553825.02       13520325.
#Sta/Elev= 30
  4641.3  144.01  4663.9  143.03  4692.1  140.63  4749.5  136.47  4769.3  133.91
  4808.2   133.2  4893.7  128.82  4916.3  125.67  4924.2  125.79  4929.8  124.95
  4934.7  122.94  4935.1  122.44  4939.9  122.94  4954.8  123.05  4973.4  124.06
  4979.4  123.47  4988.4  124.64  4994.4  123.46  5032.1  125.53  5044.7  125.04
  5072.4  125.73  5092.6  124.61  5112.8  125.63  5153.1   125.4  5200.9  127.25
    5206  126.64  5275.4  130.61  5334.5  135.09  5374.8  136.95    5405  139.58
#Mann= 9 ,-1 , 0
  4641.3     .05       0  4692.1     .07       0  4769.3    .035       0
  4808.2     .12       0  4924.2     .07       0  4934.7     .05       0
  4939.9     .07       0  4954.8     .12       0  5275.4     .05       0
Bank Sta=4934.7,4939.9
XS Rating Curve= 0 ,0
Exp/Cntr=0.3,0.1

Type RM Length L Ch R = 1 ,1862    ,296,296,296
BEGIN DESCRIPTION:
TRIB 2 TO ROCKY CREEK 3.0
END DESCRIPTION:
XS GIS Cut Line= 3
      2554525.02       13520075.        2554125.       13520025.
      2553725.05     13520124.99
#Sta/Elev= 30
  4601.3  139.49    4692  132.32  4724.8  130.61  4772.6  126.46  4863.3  123.73
    4954  123.47  4966.6  124.72  4991.7  120.53  4992.1  120.03  4996.6  120.03
    4997  120.53    5007  120.91  5014.7   123.4  5022.5  123.99  5035.4  123.73
  5063.7  125.19  5068.9  124.73  5110.1  127.75  5146.2  128.49  5220.9  131.45
  5228.6  132.65  5233.8  132.41  5241.5  134.05    5275  136.12  5282.7  137.18
  5293.1  137.49  5311.1  139.16  5393.6  144.61  5406.4  144.53  5416.7  145.27
#Mann= 3 ,-1 , 0
  4601.3     .05       0  4991.7     .05       0    4997     .05       0
Bank Sta=4991.7,4997
XS Rating Curve= 0 ,0
Exp/Cntr=0.3,0.1

Type RM Length L Ch R = 1 ,1566    ,165,165,165
BEGIN DESCRIPTION:
Mapping XS 1ef3187c
END DESCRIPTION:
XS GIS Cut Line= 3
      2554645.16       13519975.       2554168.6     13519777.08
      2553639.94     13519873.44
#Sta/Elev= 30
  4484.2  149.77  4516.9  147.79  4522.8  146.75  4528.2  147.06  4546.7  145.32
  4552.1   145.7  4570.5  143.56  4575.9  143.68  4592.7  141.29  4623.7  138.44
  4646.8  134.58  4652.9     133  4676.8  130.68  4783.1  124.13  4830.8  122.64
  4874.2   122.2  4971.8  123.85    4993  120.51  4993.4  120.01  4997.9  120.01
  4998.3  120.51  5012.7  121.44  5017.8  121.16  5024.2  122.13  5034.4  122.59
  5076.2  123.12  5128.1  124.73  5227.5  128.89    5441  140.81  5537.6  145.36
#Mann= 3 ,-1 , 0
  4484.2     .05       0    4993     .05       0  4998.3     .05       0
Bank Sta=4993,4998.3
XS Rating Curve= 0 ,0
Exp/Cntr=0.3,0.1

Type RM Length L Ch R = 1 ,1401    ,360,360,360
BEGIN DESCRIPTION:
TRIB 2 TO ROCKY CREEK 2.0
END DESCRIPTION:
XS GIS Cut Line= 3
      2554675.02     13519825.01        2554275.       13519675.
        2553875.       13519275.
#Sta/Elev= 30
  4564.8  151.35  4579.9  150.83  4628.9  146.37    4660   142.6  4665.4  142.96
  4690.3  138.05  4695.6  138.54  4720.6  134.32  4725.9   134.5  4745.5  131.67
  4775.7  128.75  4830.9  124.58  4927.9  121.36    4960  121.75  4981.6  123.24
  4986.7  119.63  4987.1  119.13    4992  119.63  5006.2  120.35  5020.3  123.33
  5076.2  122.16  5084.3  122.24  5161.7   121.8  5189.2  122.36  5204.2  121.55
  5260.7  122.08  5416.3  125.82    5487  130.14  5529.4  134.71  5557.7  135.41
#Mann= 7 ,-1 , 0
  4564.8     .05       0  4981.6     .12       0  4986.7     .05       0
    4992     .12       0  5076.2     .05       0  5084.3     .12       0
  5189.2     .05       0
Bank Sta=4986.7,4992
XS Rating Curve= 0 ,0
Exp/Cntr=0.3,0.1

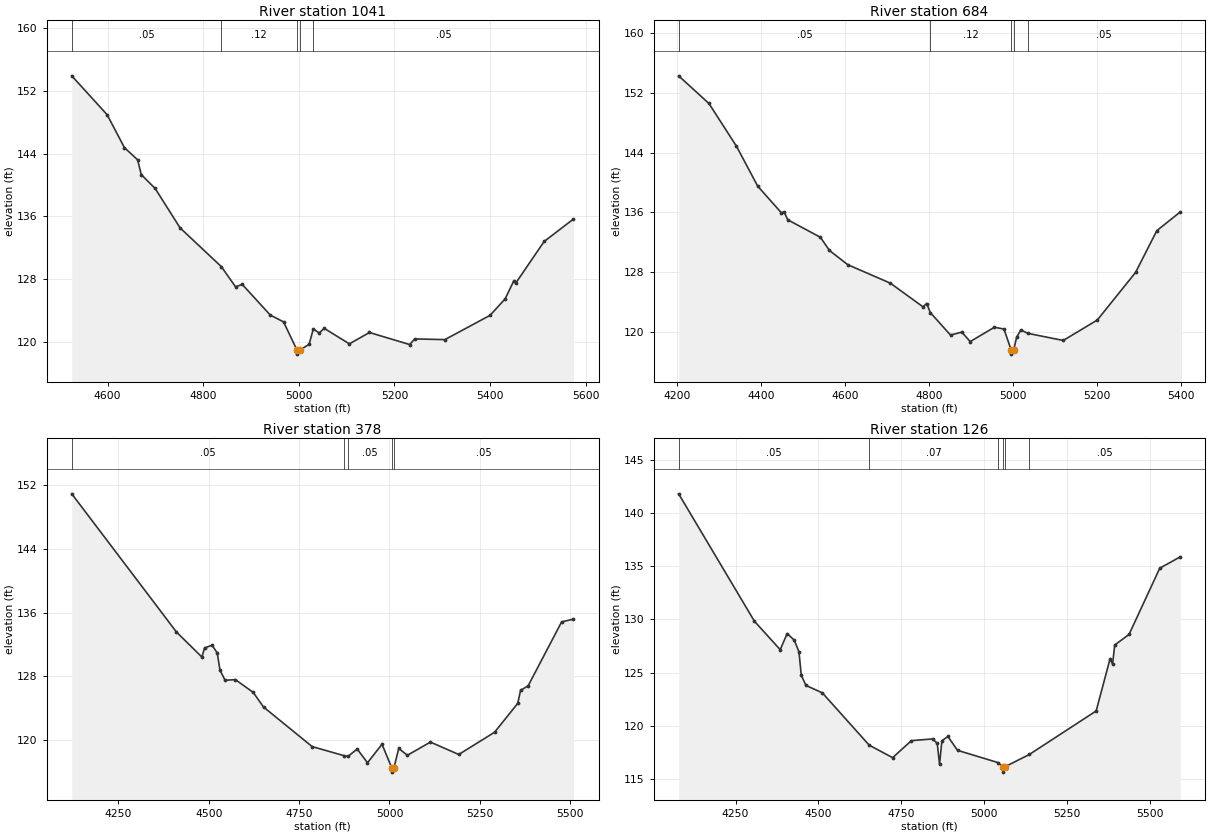
Type RM Length L Ch R = 1 ,1041    ,357,357,357
BEGIN DESCRIPTION:
Mapping XS 0935a548
END DESCRIPTION:
XS GIS Cut Line= 3
      2554828.87      13519611.3      2554412.16     13519355.19
      2553879.15     13519181.86
#Sta/Elev= 30
    4525  153.94    4599  148.98  4635.2  144.78  4662.8  143.23  4670.4  141.34
  4699.5  139.57  4751.7  134.54  4837.8  129.61  4867.7  127.03  4881.7  127.33
  4940.4  123.42  4968.2  122.55  4996.3  118.94  4996.8  118.44  5001.7  118.94
  5021.6  119.69  5030.3  121.65  5042.7  121.14  5053.2  121.73  5105.8  119.75
  5147.8   121.2    5232  119.66  5242.5  120.38  5305.6  120.29  5400.2  123.39
  5431.7  125.49  5449.4  127.73  5454.7  127.57  5513.3  132.81  5574.6  135.67
#Mann= 5 ,-1 , 0
    4525     .05       0  4837.8     .12       0  4996.3     .05       0
  5001.7     .12       0  5030.3     .05       0
Bank Sta=4996.3,5001.7
XS Rating Curve= 0 ,0
Exp/Cntr=0.3,0.1

Type RM Length L Ch R = 1 ,684     ,306,306,306
BEGIN DESCRIPTION:
Mapping XS 40f3a3b5
END DESCRIPTION:
XS GIS Cut Line= 4
      2554949.83     13519430.72      2554402.97     13519050.52
      2554186.82     13519073.95      2553879.73      13519123.4
#Sta/Elev= 30
  4204.4  154.29  4276.5  150.59    4342  144.87  4392.6  139.52  4449.3  135.93
  4455.4  136.09  4464.2  135.01  4541.9  132.67  4563.5   130.9  4607.3  128.99
  4708.6  126.52  4786.3  123.35  4794.9   123.8  4803.7  122.58  4851.8  119.57
  4878.5  119.97  4898.6   118.7  4956.2  120.62    4979  120.38  4996.5  117.52
  4996.9  117.02  5001.9  117.52  5009.2  119.29  5019.3  120.27  5035.1  119.81
  5120.1  118.85  5201.1  121.58  5292.3  127.96  5342.9  133.55  5398.9  136.07
#Mann= 5 ,-1 , 0
  4204.4     .05       0  4803.7     .12       0  4996.5     .05       0
  5001.9     .12       0  5035.1     .05       0
Bank Sta=4996.5,5001.9
XS Rating Curve= 0 ,0
Exp/Cntr=0.3,0.1

Type RM Length L Ch R = 1 ,378     ,252,252,252
BEGIN DESCRIPTION:
Mapping XS ca590589
END DESCRIPTION:
XS GIS Cut Line= 4
      2555004.54     13519323.96      2554413.39     13518800.52
      2554254.53     13518813.54       2553913.4     13519089.57
#Sta/Elev= 30
  4121.1  150.94  4410.7  133.56  4481.1  130.41  4488.5  131.56  4509.4  131.89
  4523.6  130.92  4531.1  128.77  4545.3  127.48  4573.8  127.57  4623.1  125.96
  4651.6  124.12  4786.2  119.14  4874.4     118  4884.9   117.9  4910.7  118.84
  4939.2  117.11  4979.3  119.44  5006.7  116.43  5007.2  115.93  5012.1  116.43
  5025.6  118.91  5049.5  118.05  5113.3  119.71  5191.7  118.15  5290.8  120.95
  5354.8  124.58  5362.7  126.22  5383.5  126.78  5476.2  134.83  5508.9  135.18
#Mann= 5 ,-1 , 0
  4121.1     .05       0  4874.4     .07       0  4884.9     .05       0
  5006.7     .05       0  5012.1     .05       0
Bank Sta=5006.7,5012.1
XS Rating Curve= 0 ,0
Exp/Cntr=0.3,0.1

Type RM Length L Ch R = 1 ,126     ,0,0,0
BEGIN DESCRIPTION:
TRIB 2 TO ROCKY CREEK 1.0
END DESCRIPTION:
XS GIS Cut Line= 4
      2554946.03     13519177.26      2554382.14     13518592.18
       2554236.3     13518646.87      2553893.54     13519071.45
#Sta/Elev= 30
  4078.3  141.81  4306.9  129.84  4384.8  127.16  4405.9  128.68  4427.3  128.05
  4441.4  126.96  4448.4  124.76  4462.5   123.8    4512   123.1  4653.5  118.18
  4724.1  117.01  4780.7  118.61  4844.5  118.77  4858.7  118.36  4865.6  116.39
  4872.8   118.6  4890.9     119  4919.9   117.7  5041.7  116.55  5057.4  116.15
  5057.8  115.65  5062.8  116.15  5136.7  117.31  5338.3   121.4  5379.9  126.26
  5387.9  125.82  5394.3   127.6  5437.5  128.59  5530.2  134.82  5592.3  135.89
#Mann= 6 ,-1 , 0
  4078.3     .05       0  4653.5     .07       0  5041.7     .12       0
  5057.4     .05       0  5062.8     .12       0  5136.7     .05       0
Bank Sta=5057.4,5062.8
XS Rating Curve= 0 ,0
Exp/Cntr=0.3,0.1

Chan Stop Cuts=-1
Use User Specified Reach Order=0
Composite Channel Slope=5