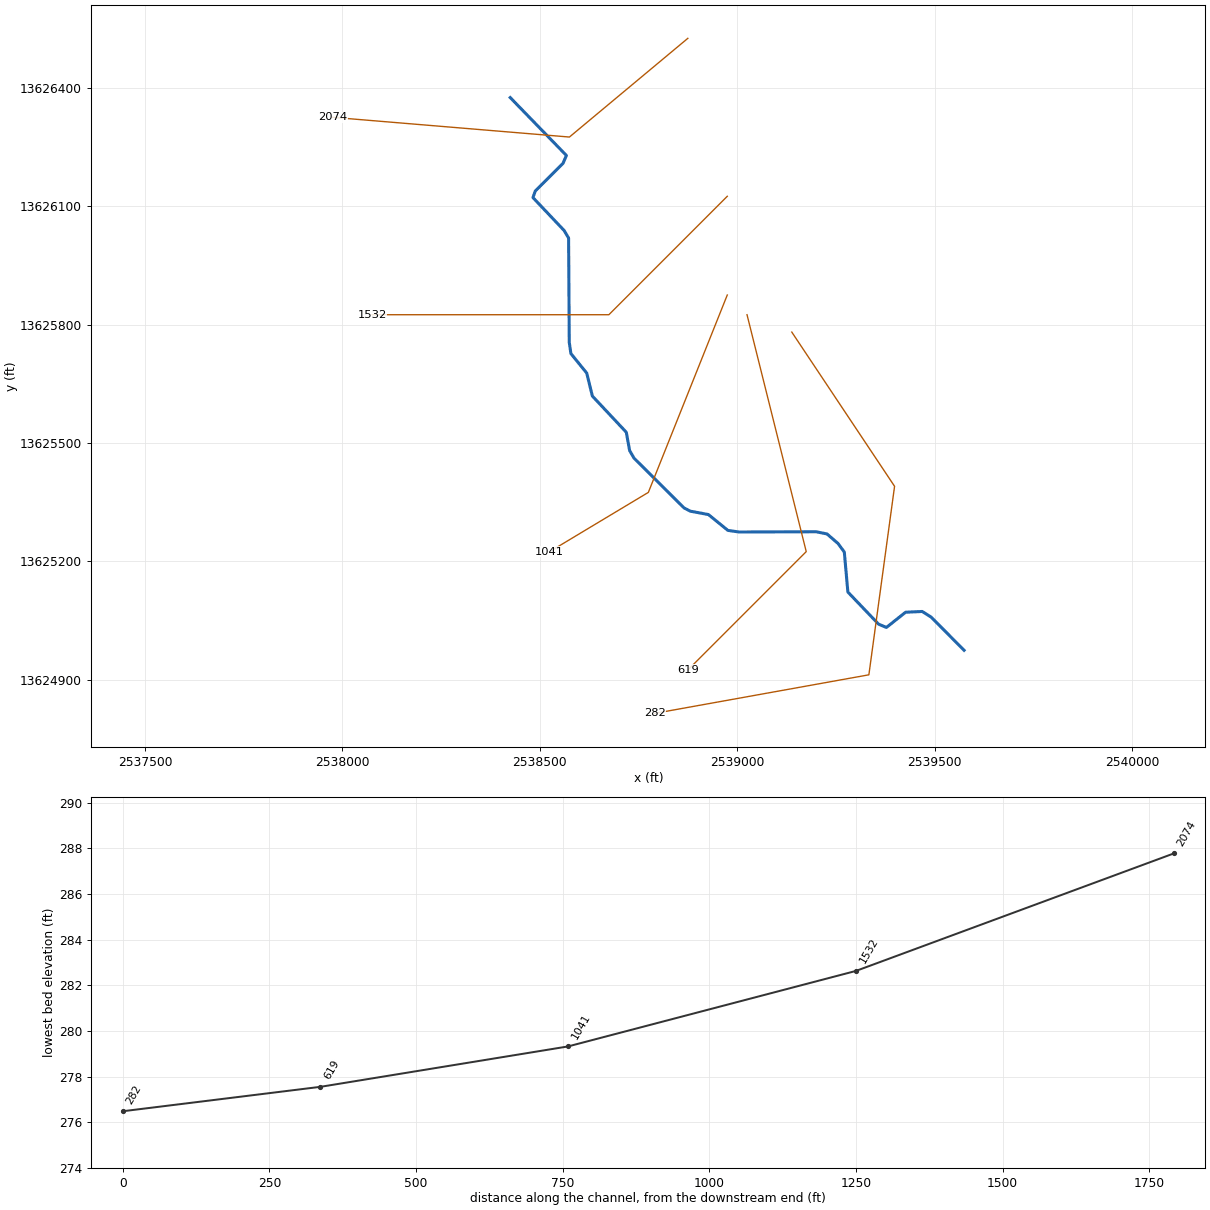
--- TRIB 20 TO IRISH CREEK.prj (project) ---

Proj Title=TRIB 20 TO IRISH CREEK Base Level Engineering
Current Plan=p01
Default Exp/Contr=0.3,0.1
English Units
Geom File=g01
Flow File=f01
Plan File=p01
BEGIN DESCRIPTION:
TRIB 20 TO IRISH CREEK
END DESCRIPTION:

--- TRIB 20 TO IRISH CREEK.p01 (plan) ---

Plan Title=Multiple Run
Short Identifier=Multiple
Geom File=g01
Flow File=f01
Subcritical Flow
K Sum by GR= 0
Std Step Tol= 0.01
Critical Tol= 0.01
Num of Std Step Trials= 20
Max Error Tol= 0.3
Flow Tol Ratio= 0.001
Split Flow NTrial= 30
Split Flow Tol= 0.02
Split Flow Ratio= 0.02
Log Output Level= 0
Friction Slope Method= 1
Unsteady Friction Slope Method= 2
Unsteady Bridges Friction Slope Method= 1
Parabolic Critical Depth
Global Vel Dist=  1 , 1 , 1
Global Log Level= 0
CheckData=True
Encroach Param= -1, 0, 0, 0
BEGIN DESCRIPTION:
Multiple Run
END DESCRIPTION:

--- TRIB 20 TO IRISH CREEK.f01 (steady flow) ---

Flow Title=Multiple
Number of Profiles=7
Profile Names=10-year,25-year,50-year,1pct_min,100-year,1pct_plu,500-year
River Rch & RM= TRIB 20 TO IRISH,Reach-1,2074
     524     827    1096     705    1407    2807    2289
Boundary for River Rch & Prof#=TRIB 20 TO IRISH,Reach-1,1
Up Type=0
Dn Type=3
Dn Slope=0.005
Boundary for River Rch & Prof#=TRIB 20 TO IRISH,Reach-1,2
Up Type=0
Dn Type=3
Dn Slope=0.005
Boundary for River Rch & Prof#=TRIB 20 TO IRISH,Reach-1,3
Up Type=0
Dn Type=3
Dn Slope=0.005
Boundary for River Rch & Prof#=TRIB 20 TO IRISH,Reach-1,4
Up Type=0
Dn Type=3
Dn Slope=0.005
Boundary for River Rch & Prof#=TRIB 20 TO IRISH,Reach-1,5
Up Type=0
Dn Type=3
Dn Slope=0.005
Boundary for River Rch & Prof#=TRIB 20 TO IRISH,Reach-1,6
Up Type=0
Dn Type=3
Dn Slope=0.005
Boundary for River Rch & Prof#=TRIB 20 TO IRISH,Reach-1,7
Up Type=0
Dn Type=3
Dn Slope=0.005

--- TRIB 20 TO IRISH CREEK.g01 (geometry) ---

Geom Title=Existing Conditions

River Reach=TRIB 20 TO IRISH,Reach-1
Reach XY= 30
      2538425.00     13626375.00      2538567.40     13626228.33
      2538558.74     13626208.33      2538488.47     13626138.34
      2538482.62     13626121.67      2538561.57     13626038.32
      2538572.92     13626019.15      2538574.64     13625754.85
      2538578.75     13625726.55      2538618.86     13625677.17
      2538633.16     13625618.95      2538719.13     13625527.28
      2538727.53     13625481.05      2538738.63     13625461.79
      2538865.32     13625335.76      2538881.03     13625327.49
      2538927.17     13625318.86      2538976.55     13625278.75
      2539004.85     13625274.64      2539200.22     13625275.33
      2539227.74     13625269.66      2539255.58     13625245.65
      2539271.49     13625223.75      2539280.53     13625122.55
      2539358.26     13625041.29      2539378.22     13625032.91
      2539426.64     13625071.42      2539468.96     13625073.40
      2539491.71     13625058.89      2539575.00     13624975.00

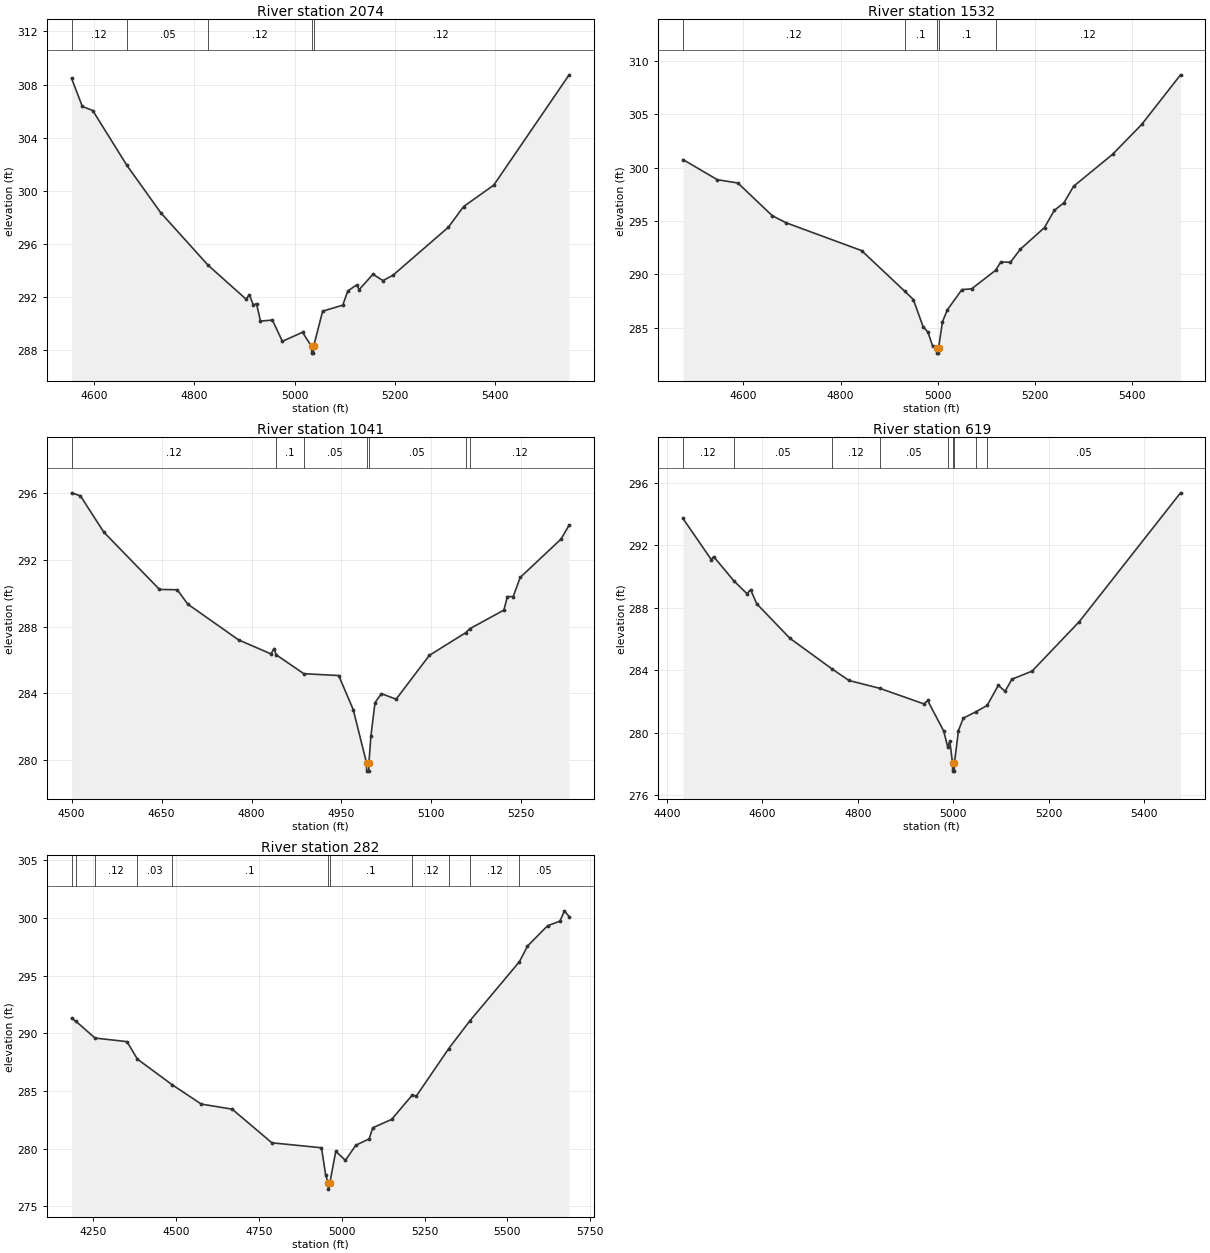
Type RM Length L Ch R = 1,2074,542,542,542
BEGIN DESCRIPTION:
TRIB 20 TO IRISH CREEK 4.0
END DESCRIPTION:
XS GIS Cut Line= 3
      2538875.01     13626525.01      2538575.00     13626275.00
      2537975.01     13626325.00
#Sta/Elev= 30
  4555.2  308.47  4576.7  306.35  4597.5  306.04  4665.7  301.91  4732.9  298.36
  4827.5  294.40  4903.4  291.84  4909.9  292.18  4917.7  291.41  4924.2  291.50
  4932.1  290.19  4955.8  290.27  4975.8  288.67  5016.0  289.35  5034.0  288.28
  5034.3  287.78  5037.8  287.78  5038.0  288.28  5056.1  290.94  5096.2  291.39
  5106.3  292.46  5123.8  292.91  5128.9  292.56  5156.5  293.72  5176.5  293.24
  5196.6  293.65  5307.0  297.26  5337.1  298.81  5397.3  300.42  5547.8  308.73
#Mann=5,-1,0
  4555.2    0.12       0  4665.7    0.05       0  4827.5    0.12       0
  5034.0    0.05       0  5038.0    0.12       0
Bank Sta=5034,5038
Exp/Cntr=0.3,0.1

Type RM Length L Ch R = 1,1532,491,491,491
BEGIN DESCRIPTION:
TRIB 20 TO IRISH CREEK 3.0
END DESCRIPTION:
XS GIS Cut Line= 3
      2538974.97     13626124.97      2538675.00     13625825.00
      2538075.02     13625825.00
#Sta/Elev= 30
  4475.7  300.76  4546.4  298.87  4588.8  298.56  4659.5  295.50  4687.8  294.84
  4843.4  292.23  4932.2  288.43  4949.9  287.65  4969.9  285.12  4979.9  284.60
  4989.9  283.26  4997.9  283.13  4998.2  282.63  5001.7  282.63  5001.9  283.13
  5009.9  285.57  5019.9  286.68  5049.9  288.58  5069.9  288.65  5119.1  290.38
  5129.9  291.16  5149.9  291.14  5169.9  292.35  5219.9  294.39  5239.9  295.99
  5259.9  296.71  5279.9  298.26  5359.9  301.24  5419.9  304.04  5499.9  308.69
#Mann=5,-1,0
  4475.7    0.12       0  4932.2     0.1       0  4997.9    0.05       0
  5001.9     0.1       0  5119.1    0.12       0
Bank Sta=4997.9,5001.9
Exp/Cntr=0.3,0.1

Type RM Length L Ch R = 1,1041,422,422,422
BEGIN DESCRIPTION:
TRIB 20 TO IRISH CREEK 2.0
END DESCRIPTION:
XS GIS Cut Line= 3
      2538974.98     13625874.96      2538775.00     13625375.00
      2538525.02     13625225.01
#Sta/Elev= 30
  4499.8  296.03  4514.6  295.85  4553.6  293.67  4646.5  290.23  4676.1  290.21
  4693.6  289.35  4778.4  287.20  4832.3  286.36  4837.7  286.68  4841.0  286.31
  4887.2  285.17  4945.4  285.06  4969.6  283.02  4991.8  279.82  4992.1  279.32
  4995.6  279.32  4995.8  279.82  4999.2  281.44  5006.0  283.43  5016.7  283.97
  5041.2  283.64  5096.6  286.27  5157.2  287.63  5164.2  287.87  5221.0  288.99
  5226.8  289.80  5236.5  289.80  5248.2  290.95  5316.2  293.25  5329.8  294.09
#Mann=7,-1,0
  4499.8    0.12       0  4841.0     0.1       0  4887.2    0.05       0
  4991.8    0.05       0  4995.8    0.05       0  5157.2    0.05       0
  5164.2    0.12       0
Bank Sta=4991.8,4995.8
Exp/Cntr=0.3,0.1

Type RM Length L Ch R = 1,619,337,337,337
BEGIN DESCRIPTION:
TRIB 20 TO IRISH CREEK 1.0
END DESCRIPTION:
XS GIS Cut Line= 3
      2539025.00     13625825.02      2539175.00     13625225.00
      2538875.04     13624925.04
#Sta/Elev= 30
  4433.4  293.72  4492.7  291.09  4497.8  291.28  4539.7  289.74  4567.4  288.91
  4575.2  289.16  4588.0  288.26  4657.6  286.05  4744.9  284.11  4781.3  283.35
  4845.7  282.85  4938.5  281.85  4946.2  282.07  4979.7  280.12  4988.4  279.08
  4992.6  279.49  4998.3  278.05  4998.6  277.55  5002.1  277.55  5002.3  278.05
  5010.7  280.15  5021.0  280.94  5047.4  281.35  5070.7  281.75  5094.3  283.04
  5108.5  282.66  5122.6  283.43  5165.0  283.95  5264.0  287.12  5476.1  295.36
#Mann=9,-1,0
  4433.4    0.12       0  4539.7    0.05       0  4744.9    0.12       0
  4845.7    0.05       0  4988.4    0.12       0  4998.3    0.05       0
  5002.3    0.12       0  5047.4     0.1       0  5070.7    0.05       0
Bank Sta=4998.3,5002.3
Exp/Cntr=0.3,0.1

Type RM Length L Ch R = 1,282,0,0,0
BEGIN DESCRIPTION:
LGII4343
END DESCRIPTION:
XS GIS Cut Line= 4
      2539138.41     13625781.01      2539398.83     13625390.38
      2539333.73     13624912.95      2538791.17     13624815.29
#Sta/Elev= 30
  4184.0  291.31  4197.8  291.03  4254.9  289.59  4351.3  289.28  4383.0  287.76
  4487.3  285.55  4575.8  283.86  4669.0  283.42  4789.0  280.50  4938.7  280.07
  4951.6  277.68  4959.7  276.98  4959.9  276.48  4963.7  276.98  4981.9  279.76
  5011.0  278.98  5042.4  280.29  5082.8  280.84  5093.4  281.80  5150.6  282.53
  5212.2  284.62  5225.5  284.57  5323.1  288.68  5386.1  291.06  5536.6  296.22
  5560.8  297.57  5621.7  299.34  5658.7  299.73  5672.5  300.63  5686.6  300.13
#Mann=11,-1,0
  4184.0    0.05       0  4197.8    0.03       0  4254.9    0.12       0
  4383.0    0.03       0  4487.3     0.1       0  4959.7    0.05       0
  4963.7     0.1       0  5212.2    0.12       0  5323.1    0.05       0
  5386.1    0.12       0  5536.6    0.05       0
Bank Sta=4959.7,4963.7
Exp/Cntr=0.3,0.1

Chan Stop Cuts=-1