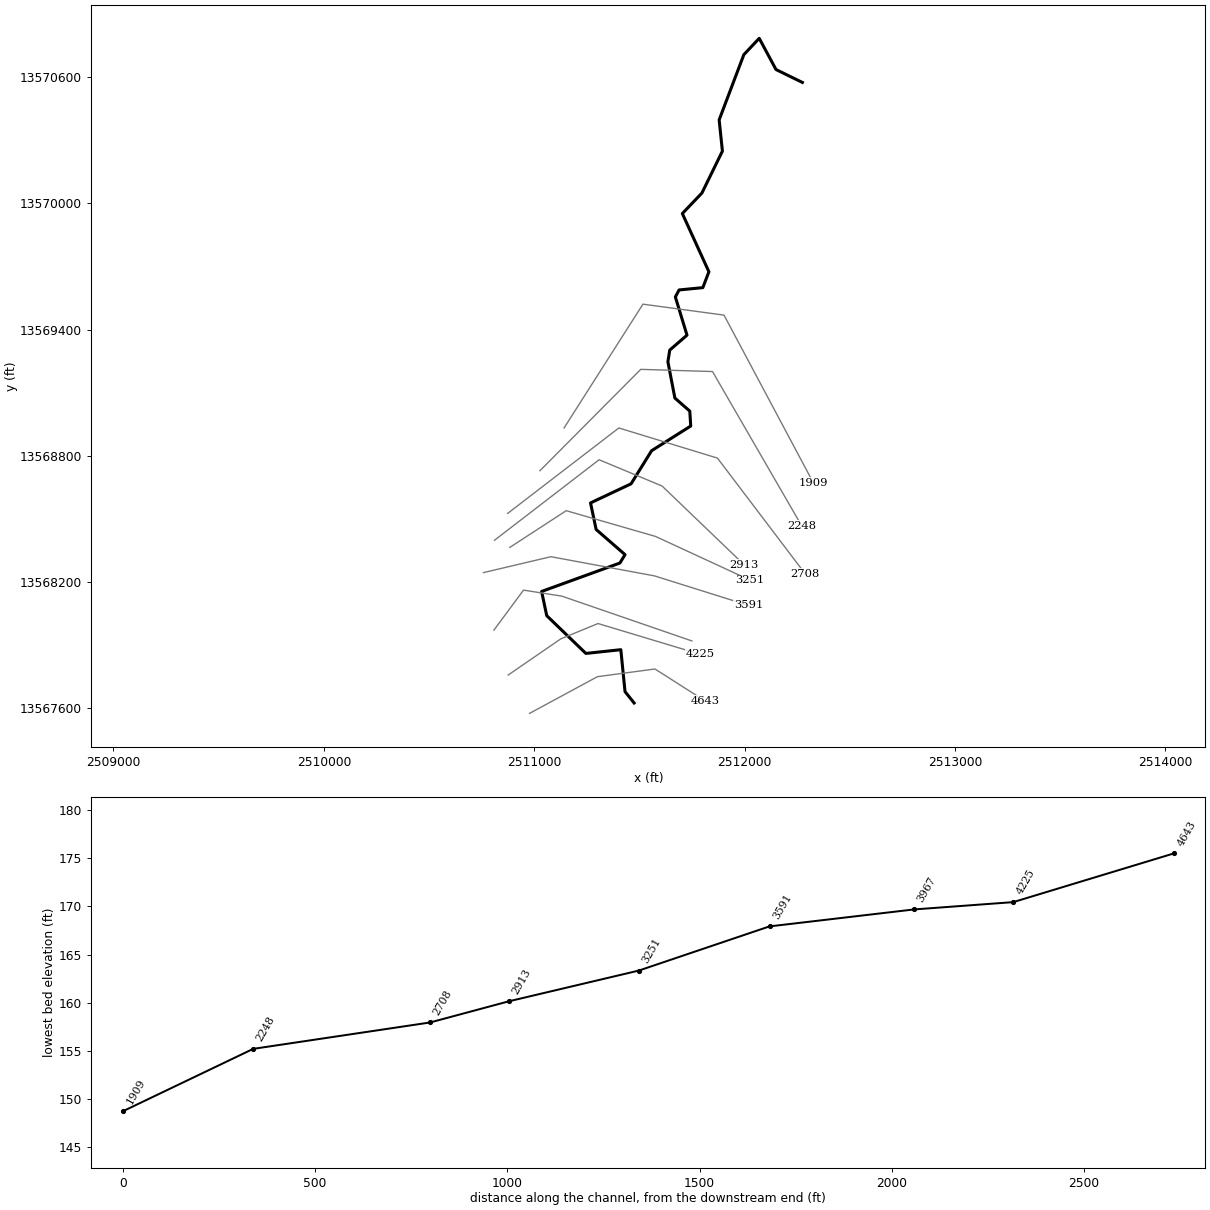
--- TRIB 20_1 TO GUADALUPE RIVER.prj (project) ---

Proj Title=TRIB 20_1 TO GUADALUPE RIVER Base Level Engineering
Current Plan=p01
Default Exp/Contr=0.3,0.1
English Units
Geom File=g01
Flow File=f01
Plan File=p01
BEGIN DESCRIPTION:
TRIB 20_1 TO GUADALUPE RIVER
END DESCRIPTION:

--- TRIB 20_1 TO GUADALUPE RIVER.p01 (plan) ---

Plan Title=Multiple Run
Short Identifier=Multiple
Geom File=g01
Flow File=f01
Subcritical Flow
K Sum by GR= 0
Std Step Tol= 0.01
Critical Tol= 0.01
Num of Std Step Trials= 20
Max Error Tol= 0.3
Flow Tol Ratio= 0.001
Split Flow NTrial= 30
Split Flow Tol= 0.02
Split Flow Ratio= 0.02
Log Output Level= 0
Friction Slope Method= 1
Unsteady Friction Slope Method= 2
Unsteady Bridges Friction Slope Method= 1
Parabolic Critical Depth
Global Vel Dist=  1 , 1 , 1
Global Log Level= 0
CheckData=True
Encroach Param= -1, 0, 0, 0
BEGIN DESCRIPTION:
Multiple Run
END DESCRIPTION:

--- TRIB 20_1 TO GUADALUPE RIVER.f01 (steady flow) ---

Flow Title=Multiple
Number of Profiles=7
Profile Names=10-year,25-year,50-year,1pct_min,100-year,1pct_plu,500-year
River Rch & RM= TRIB 20_1 TO GUA,Reach-1,4643
     322     500     655     417     833    1662    1330
Boundary for River Rch & Prof#=TRIB 20_1 TO GUA,Reach-1,1
Up Type=0
Dn Type=3
Dn Slope=0.005
Boundary for River Rch & Prof#=TRIB 20_1 TO GUA,Reach-1,2
Up Type=0
Dn Type=3
Dn Slope=0.005
Boundary for River Rch & Prof#=TRIB 20_1 TO GUA,Reach-1,3
Up Type=0
Dn Type=3
Dn Slope=0.005
Boundary for River Rch & Prof#=TRIB 20_1 TO GUA,Reach-1,4
Up Type=0
Dn Type=3
Dn Slope=0.005
Boundary for River Rch & Prof#=TRIB 20_1 TO GUA,Reach-1,5
Up Type=0
Dn Type=3
Dn Slope=0.005
Boundary for River Rch & Prof#=TRIB 20_1 TO GUA,Reach-1,6
Up Type=0
Dn Type=3
Dn Slope=0.005
Boundary for River Rch & Prof#=TRIB 20_1 TO GUA,Reach-1,7
Up Type=0
Dn Type=3
Dn Slope=0.005

--- TRIB 20_1 TO GUADALUPE RIVER.g01 (geometry) ---

Geom Title=Existing Conditions

River Reach=TRIB 20_1 TO GUA,Reach-1
Reach XY= 30
      2511475.00     13567625.00      2511431.81     13567678.96
      2511411.87     13567878.32      2511245.73     13567860.60
      2511059.66     13568040.03      2511035.29     13568155.22
      2511407.44     13568290.35      2511431.81     13568330.22
      2511294.47     13568449.84      2511267.88     13568576.10
      2511460.60     13568666.93      2511558.07     13568824.20
      2511744.15     13568941.61      2511739.72     13569012.49
      2511668.83     13569074.52      2511635.60     13569247.30
      2511644.46     13569302.68      2511726.43     13569373.57
      2511671.05     13569555.21      2511688.77     13569588.44
      2511801.74     13569599.51      2511830.54     13569674.83
      2511704.27     13569951.73      2511797.31     13570049.19
      2511894.78     13570248.56      2511879.27     13570396.98
      2511996.68     13570707.10      2512069.78     13570784.63
      2512149.52     13570636.22      2512275.00     13570575.00

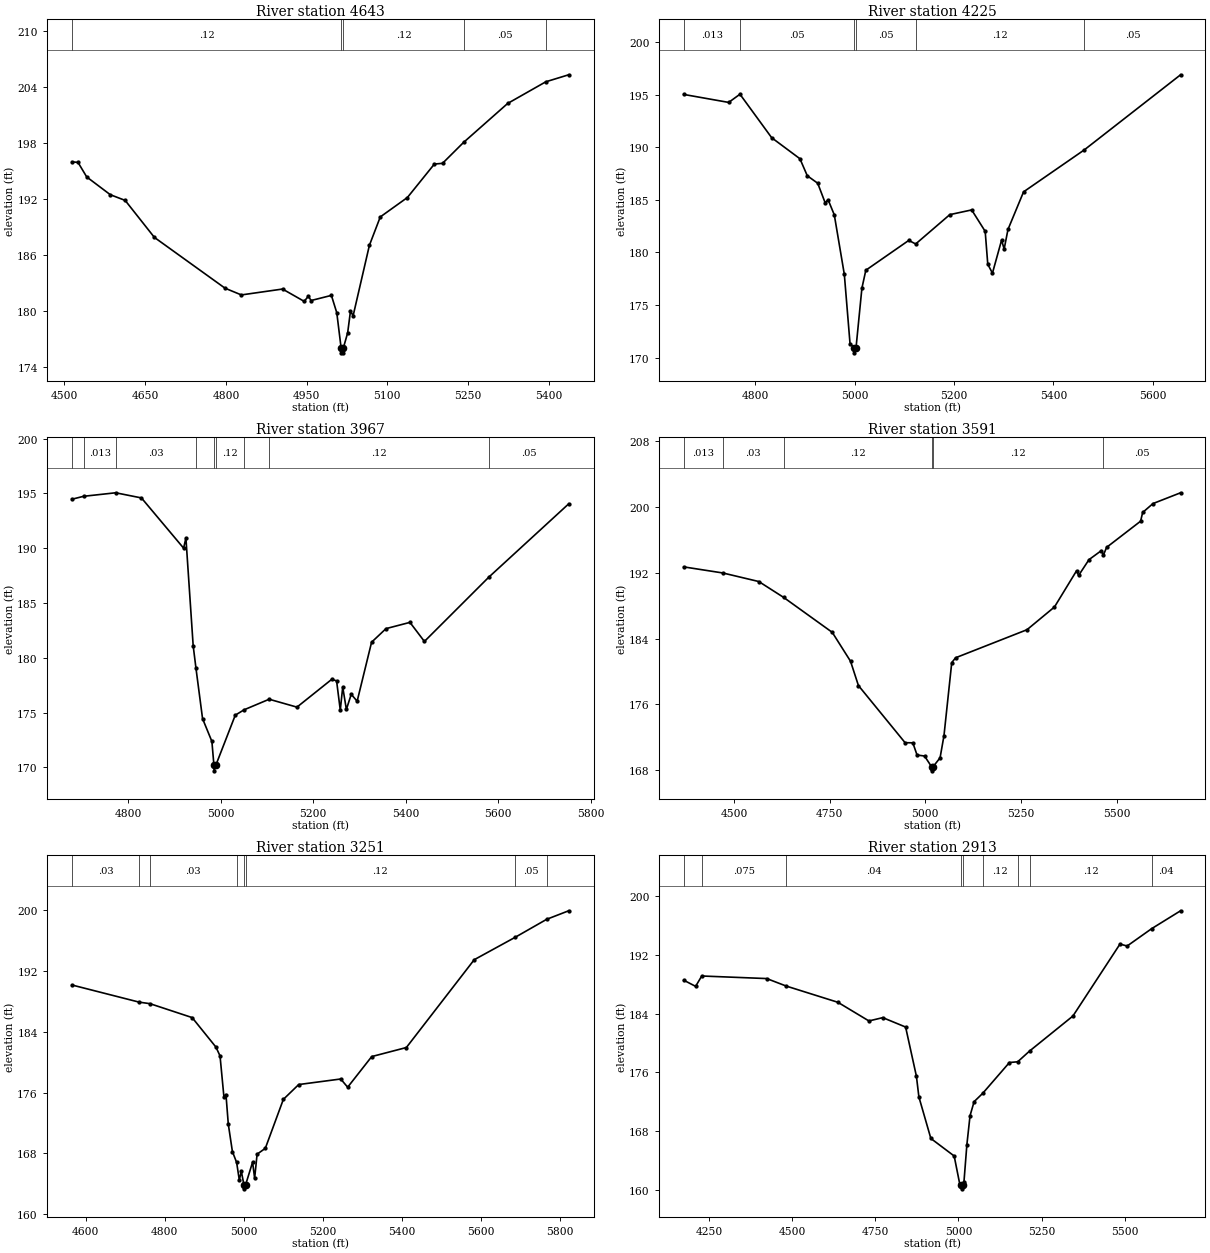
Type RM Length L Ch R = 1,4643,418,418,418
BEGIN DESCRIPTION:
Mapping XS 10e88423
END DESCRIPTION:
XS GIS Cut Line= 4
      2510977.88     13567575.59      2511300.81     13567750.08
      2511574.25     13567786.54      2511810.61     13567635.89
#Sta/Elev= 30
  4513.7  195.96  4525.2  195.90  4541.4  194.34  4585.2  192.44  4612.8  191.83
  4667.1  187.87  4798.4  182.43  4828.7  181.71  4905.2  182.34  4945.5  181.02
  4953.2  181.58  4958.2  181.11  4996.0  181.66  5006.0  179.80  5014.1  176.01
  5014.4  175.51  5017.9  175.51  5018.1  176.01  5026.2  177.65  5031.4  179.96
  5036.4  179.49  5066.6  187.02  5086.8  190.06  5137.2  192.14  5187.3  195.72
  5202.5  195.80  5241.6  198.04  5323.5  202.21  5394.4  204.53  5436.9  205.28
#Mann=5,-1,0
  4513.7    0.12       0  5014.1    0.05       0  5018.1    0.12       0
  5241.6    0.05       0  5394.4    0.12       0
Bank Sta=5014.1,5018.1
Exp/Cntr=0.3,0.1

Type RM Length L Ch R = 1,4225,258,258,258
BEGIN DESCRIPTION:
Mapping XS ab5fb29e
END DESCRIPTION:
XS GIS Cut Line= 4
      2510876.37     13567757.92      2511126.34     13567929.77
      2511303.42     13568002.68      2511787.80     13567856.85
#Sta/Elev= 30
  4655.5  195.04  4746.1  194.28  4768.8  195.06  4832.7  190.92  4889.6  188.92
  4904.4  187.30  4925.4  186.59  4940.3  184.74  4946.4  185.01  4958.8  183.58
  4979.0  177.92  4990.5  171.32  4998.6  170.95  4998.9  170.45  5002.6  170.95
  5014.4  176.60  5022.3  178.31  5108.8  181.15  5122.7  180.81  5191.4  183.60
  5235.5  184.05  5262.7  182.01  5267.9  178.88  5277.3  178.03  5295.7  181.17
  5300.9  180.33  5308.6  182.19  5340.0  185.77  5462.5  189.77  5656.2  196.91
#Mann=6,-1,0
  4655.5   0.013       0  4768.8    0.05       0  4998.6    0.05       0
  5002.6    0.05       0  5122.7    0.12       0  5462.5    0.05       0
Bank Sta=4998.6,5002.6
Exp/Cntr=0.3,0.1

Type RM Length L Ch R = 1,3967,376,376,376
BEGIN DESCRIPTION:
Mapping XS 0c6b7e6e
END DESCRIPTION:
XS GIS Cut Line= 4
      2510808.63     13567971.44      2510949.25     13568161.54
      2511131.54     13568132.89      2511749.70     13567919.91
#Sta/Elev= 30
  4677.8  194.46  4703.4  194.73  4772.7  195.05  4828.4  194.58  4919.6  190.00
  4924.6  190.93  4940.3  181.10  4946.4  179.03  4960.6  174.45  4980.8  172.37
  4985.2  170.19  4985.5  169.69  4989.2  170.19  5031.4  174.77  5050.6  175.26
  5104.7  176.22  5164.8  175.50  5239.9  178.03  5250.5  177.90  5258.5  175.23
  5263.8  177.33  5271.7  175.29  5282.2  176.67  5295.0  176.04  5326.2  181.42
  5357.4  182.66  5409.2  183.23  5440.5  181.49  5579.7  187.35  5752.6  194.04
#Mann=9,-1,0
  4677.8    0.03       0  4703.4   0.013       0  4772.7    0.03       0
  4946.4    0.12       0  4985.2    0.05       0  4989.2    0.12       0
  5050.6    0.05       0  5104.7    0.12       0  5579.7    0.05       0
Bank Sta=4985.2,4989.2
Exp/Cntr=0.3,0.1

Type RM Length L Ch R = 1,3591,340,340,340
BEGIN DESCRIPTION:
Mapping XS f5929953
END DESCRIPTION:
XS GIS Cut Line= 4
      2510759.16     13568244.87      2511079.46     13568320.39
      2511571.65     13568229.25      2512019.55     13568088.63
#Sta/Elev= 30
  4368.3  192.70  4470.7  191.96  4564.7  190.92  4629.7  188.99  4756.7  184.75
  4804.5  181.24  4825.1  178.29  4947.1  171.35  4967.4  171.33  4978.4  169.85
  4998.0  169.73  5016.3  168.43  5016.5  167.93  5020.3  168.43  5038.6  169.51
  5048.8  172.20  5069.1  181.07  5079.1  181.66  5265.9  185.07  5337.7  187.83
  5395.5  192.23  5400.8  191.66  5428.0  193.58  5460.4  194.68  5465.7  194.14
  5474.0  195.07  5562.9  198.25  5568.3  199.31  5595.3  200.39  5667.4  201.70
#Mann=6,-1,0
  4368.3   0.013       0  4470.7    0.03       0  4629.7    0.12       0
  5016.3    0.05       0  5020.3    0.12       0  5465.7    0.05       0
Bank Sta=5016.3,5020.3
Exp/Cntr=0.3,0.1

Type RM Length L Ch R = 1,3251,338,338,338
BEGIN DESCRIPTION:
Mapping XS 2a201bc7
END DESCRIPTION:
XS GIS Cut Line= 4
      2510884.15     13568364.67      2511152.38     13568539.14
      2511576.86     13568416.75      2512025.64     13568209.22
#Sta/Elev= 30
  4565.3  190.16  4735.6  187.90  4762.9  187.70  4869.5  185.87  4929.6  181.99
  4940.0  180.83  4949.8  175.46  4955.0  175.75  4960.9  171.85  4971.3  168.24
  4982.0  166.81  4988.7  164.51  4993.9  165.63  5000.5  163.84  5000.7  163.34
  5004.5  163.84  5022.3  166.85  5027.5  164.73  5033.7  167.90  5054.5  168.67
  5100.1  175.11  5138.9  177.06  5245.1  177.79  5262.7  176.71  5323.5  180.74
  5411.1  181.93  5582.6  193.48  5685.8  196.42  5765.9  198.80  5821.5  199.92
#Mann=8,-1,0
  4565.3    0.03       0  4735.6   0.075       0  4762.9    0.03       0
  4982.0    0.12       0  5000.5    0.05       0  5004.5    0.12       0
  5685.8    0.05       0  5765.9    0.04       0
Bank Sta=5000.5,5004.5
Exp/Cntr=0.3,0.1

Type RM Length L Ch R = 1,2913,205,205,205
BEGIN DESCRIPTION:
Mapping XS 4046ef5e
END DESCRIPTION:
XS GIS Cut Line= 4
      2510811.20     13568398.49      2511308.63     13568781.33
      2511608.11     13568656.33      2511998.73     13568281.33
#Sta/Elev= 30
  4174.2  188.56  4210.0  187.72  4228.5  189.13  4423.8  188.78  4482.4  187.76
  4637.7  185.55  4731.0  183.01  4772.7  183.46  4841.3  182.18  4873.8  175.48
  4881.2  172.67  4917.2  167.01  4987.3  164.62  5003.9  160.84  5009.2  160.65
  5009.4  160.15  5013.2  160.65  5016.6  161.03  5025.5  166.17  5035.0  170.11
  5047.2  172.02  5073.0  173.15  5153.4  177.35  5178.3  177.45  5213.9  178.91
  5344.3  183.68  5485.8  193.48  5507.2  193.21  5580.8  195.57  5667.9  198.01
#Mann=9,-1,0
  4174.2    0.03       0  4228.5   0.075       0  4482.4    0.04       0
  5009.2    0.04       0  5013.2    0.04       0  5073.0    0.12       0
  5178.3    0.04       0  5213.9    0.12       0  5580.8    0.04       0
Bank Sta=5009.2,5013.2
Exp/Cntr=0.3,0.1

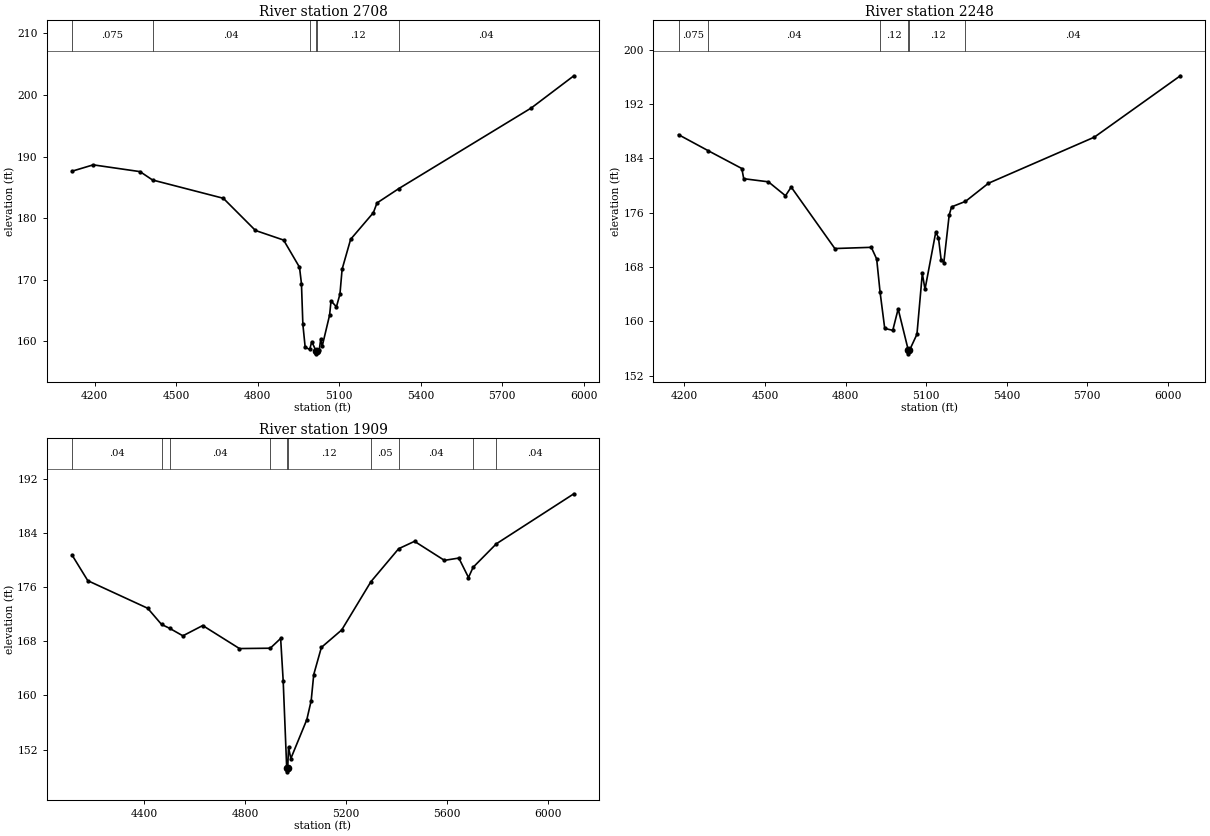
Type RM Length L Ch R = 1,2708,460,460,460
BEGIN DESCRIPTION:
Mapping XS f9637f7a
END DESCRIPTION:
XS GIS Cut Line= 4
      2510873.72     13568526.11      2511402.38     13568932.37
      2511871.13     13568789.14      2512287.69     13568239.80
#Sta/Elev= 30
  4116.8  187.62  4194.6  188.65  4366.8  187.55  4412.9  186.19  4673.3  183.22
  4791.6  177.99  4895.2  176.43  4953.6  172.02  4960.8  169.36  4966.0  162.74
  4974.5  159.02  4991.0  158.67  4998.8  159.92  5014.3  158.45  5014.6  157.95
  5018.3  158.45  5026.4  158.64  5031.6  160.29  5037.2  159.20  5064.4  164.25
  5069.6  166.55  5089.5  165.59  5102.4  167.64  5110.4  171.70  5141.8  176.56
  5225.4  180.88  5238.8  182.46  5319.2  184.80  5806.8  197.90  5963.1  203.12
#Mann=6,-1,0
  4116.8   0.075       0  4412.9    0.04       0  4991.0    0.12       0
  5014.3    0.05       0  5018.3    0.12       0  5319.2    0.04       0
Bank Sta=5014.3,5018.3
Exp/Cntr=0.3,0.1

Type RM Length L Ch R = 1,2248,339,339,339
BEGIN DESCRIPTION:
Mapping XS 41ddc703
END DESCRIPTION:
XS GIS Cut Line= 4
      2511027.39     13568729.25      2511506.54     13569211.02
      2511847.69     13569200.60      2512272.16     13568466.23
#Sta/Elev= 30
  4178.1  187.47  4289.6  185.09  4413.8  182.49  4420.9  180.99  4512.8  180.53
  4576.5  178.48  4597.7  179.76  4760.3  170.71  4896.1  170.89  4916.1  169.17
  4928.7  164.32  4946.1  158.95  4976.1  158.67  4996.1  161.82  5034.1  155.71
  5034.4  155.21  5038.1  155.71  5066.1  158.09  5086.1  167.05  5096.1  164.71
  5136.2  173.13  5146.2  172.30  5156.2  169.06  5166.2  168.64  5186.2  175.64
  5195.0  176.84  5246.9  177.65  5332.4  180.32  5727.0  187.11  6047.1  196.14
#Mann=6,-1,0
  4178.1   0.075       0  4289.6    0.04       0  4928.7    0.12       0
  5034.1    0.05       0  5038.1    0.12       0  5246.9    0.04       0
Bank Sta=5034.1,5038.1
Exp/Cntr=0.3,0.1

Type RM Length L Ch R = 1,1909,0,0,0
BEGIN DESCRIPTION:
Mapping XS 49b27b2a
END DESCRIPTION:
XS GIS Cut Line= 4
      2511141.98     13568932.41      2511516.96     13569520.91
      2511902.38     13569468.83      2512326.85     13568671.97
#Sta/Elev= 30
  4113.4  180.73  4175.8  176.95  4413.2  172.88  4468.2  170.49  4500.7  169.91
  4552.8  168.81  4631.5  170.33  4777.1  166.93  4899.2  166.98  4940.4  168.42
  4950.5  162.15  4964.5  149.23  4964.8  148.73  4968.5  149.23  4971.6  152.36
  4980.8  150.69  5044.2  156.44  5061.5  159.24  5071.6  163.09  5101.9  167.10
  5182.6  169.68  5298.3  176.80  5408.3  181.67  5471.2  182.76  5589.7  179.95
  5646.9  180.29  5685.2  177.42  5703.6  178.93  5795.5  182.39  6103.0  189.78
#Mann=10,-1,0
  4113.4    0.04       0  4468.2   0.013       0  4500.7    0.04       0
  4899.2    0.12       0  4964.5    0.05       0  4968.5    0.12       0
  5298.3    0.05       0  5408.3    0.04       0  5703.6    0.12       0
  5795.5    0.04       0
Bank Sta=4964.5,4968.5
Exp/Cntr=0.3,0.1

Chan Stop Cuts=-1