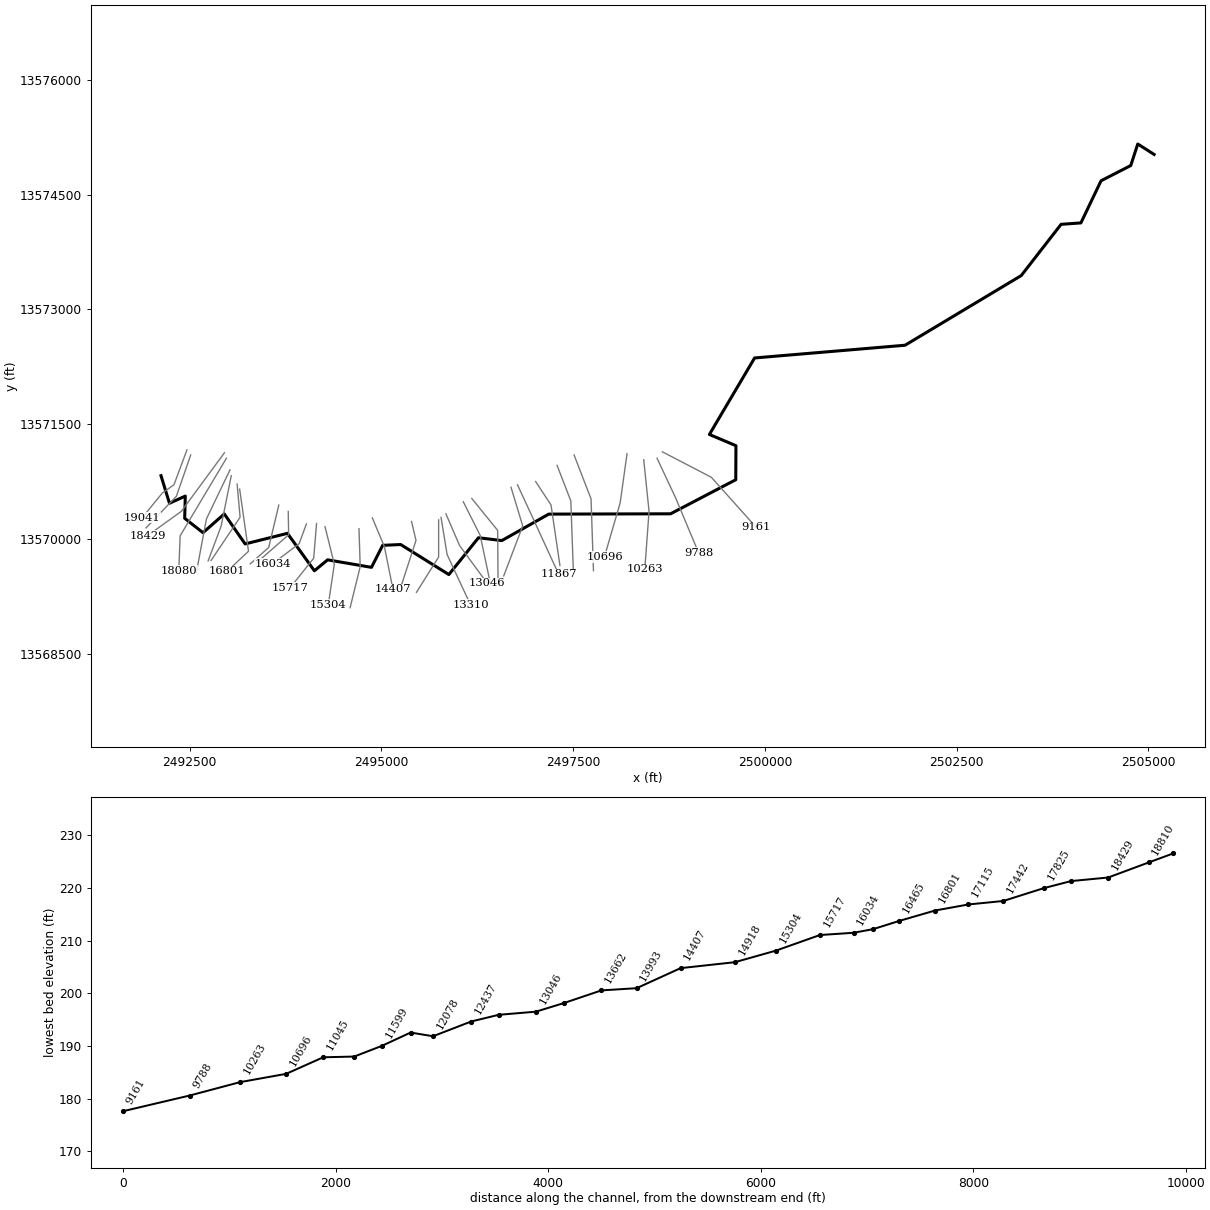
--- TRIB 22 TO GUADALUPE RIVER.prj (project) ---

Proj Title=TRIB 22 TO GUADALUPE RIVER Base Level Engineering
Current Plan=p01
Default Exp/Contr=0.3,0.1
English Units
Geom File=g01
Flow File=f01
Plan File=p01
Y Axis Title=Elevation
X Axis Title(PF)=Main Channel Distance
X Axis Title(XS)=Station
BEGIN DESCRIPTION:
TRIB 22 TO GUADALUPE RIVER
END DESCRIPTION:
DSS Export Rating Curves= 0
DSS Export Rating Curve Sorted= 0
DSS Export Volume Flow Curves= 0
DXF OffsetX= 0
DXF OffsetY= 0
DXF ScaleX= 1
DXF ScaleY= 10

--- TRIB 22 TO GUADALUPE RIVER.p01 (plan) ---

Plan Title=Multiple Run
Short Identifier=Multiple
Geom File=g01
Flow File=f01
Subcritical Flow
K Sum by GR= 0
Std Step Tol= 0.01
Critical Tol= 0.01
Num of Std Step Trials= 20
Max Error Tol= 0.3
Flow Tol Ratio= 0.001
Split Flow NTrial= 30
Split Flow Tol= 0.02
Split Flow Ratio= 0.02
Log Output Level= 0
Friction Slope Method= 1
Unsteady Friction Slope Method= 2
Unsteady Bridges Friction Slope Method= 1
Parabolic Critical Depth
Global Vel Dist=  1 , 1 , 1
Global Log Level= 0
CheckData=True
Encroach Param= -1, 0, 0, 0
BEGIN DESCRIPTION:
Multiple Run
END DESCRIPTION:

--- TRIB 22 TO GUADALUPE RIVER.f01 (steady flow) ---

Flow Title=Multiple
Number of Profiles=7
Profile Names=10-year,25-year,50-year,1pct_min,100-year,1pct_plu,500-year
River Rch & RM= TRIB 22 TO GUADA,Reach-1,19041
    1001    1670    2295    1527    3048    6081    5324
River Rch & RM= TRIB 22 TO GUADA,Reach-1,15717
    1109    1858    2561    1708    3408    6800    5981
River Rch & RM= TRIB 22 TO GUADA,Reach-1,13310
    1550    2641    3680    2479    4946    9868    8855
River Rch & RM= TRIB 22 TO GUADA,Reach-1,10696
    1721    2943    4112    2775    5537   11049    9958
River Rch & RM= TRIB 22 TO GUADA,Reach-1,7254
    1858    3183    4451    3007    5999   11970   10805
River Rch & RM= TRIB 22 TO GUADA,Reach-1,2093
    1872    3205    4481    3026    6037   12045   10863
Boundary for River Rch & Prof#=TRIB 22 TO GUADA,Reach-1,1
Up Type=0
Dn Type=3
Dn Slope=0.005
Boundary for River Rch & Prof#=TRIB 22 TO GUADA,Reach-1,2
Up Type=0
Dn Type=3
Dn Slope=0.005
Boundary for River Rch & Prof#=TRIB 22 TO GUADA,Reach-1,3
Up Type=0
Dn Type=3
Dn Slope=0.005
Boundary for River Rch & Prof#=TRIB 22 TO GUADA,Reach-1,4
Up Type=0
Dn Type=3
Dn Slope=0.005
Boundary for River Rch & Prof#=TRIB 22 TO GUADA,Reach-1,5
Up Type=0
Dn Type=3
Dn Slope=0.005
Boundary for River Rch & Prof#=TRIB 22 TO GUADA,Reach-1,6
Up Type=0
Dn Type=3
Dn Slope=0.005
Boundary for River Rch & Prof#=TRIB 22 TO GUADA,Reach-1,7
Up Type=0
Dn Type=3
Dn Slope=0.005

--- TRIB 22 TO GUADALUPE RIVER.g01 (geometry) ---

Geom Title=Existing Conditions
Program Version=4.10

River Reach=TRIB 22 TO GUADA,Reach-1
Reach XY= 30
        2492125.       13570825.      2492235.31     13570464.78
      2492441.61     13570558.86      2492433.84     13570268.05
      2492672.74     13570080.05      2492950.18     13570325.59
       2493221.7     13569933.08       2493773.5     13570071.54
      2494124.99     13569582.07      2494297.66     13569725.22
      2494869.35     13569626.97      2495015.17     13569914.53
      2495250.12      13569925.3      2495878.41     13569532.81
      2496264.57     13570014.04       2496569.1     13569976.98
      2497180.86     13570322.93      2498769.32     13570326.97
      2499619.55     13570772.53      2499621.93     13571217.39
       2499275.7     13571364.29       2499865.2     13572364.52
       2501827.3     13572530.83      2503342.05     13573441.49
      2503861.68     13574111.63      2504119.92     13574130.03
      2504382.86     13574681.17      2504769.99     13574880.01
      2504861.31     13575161.74        2505075.       13575025.

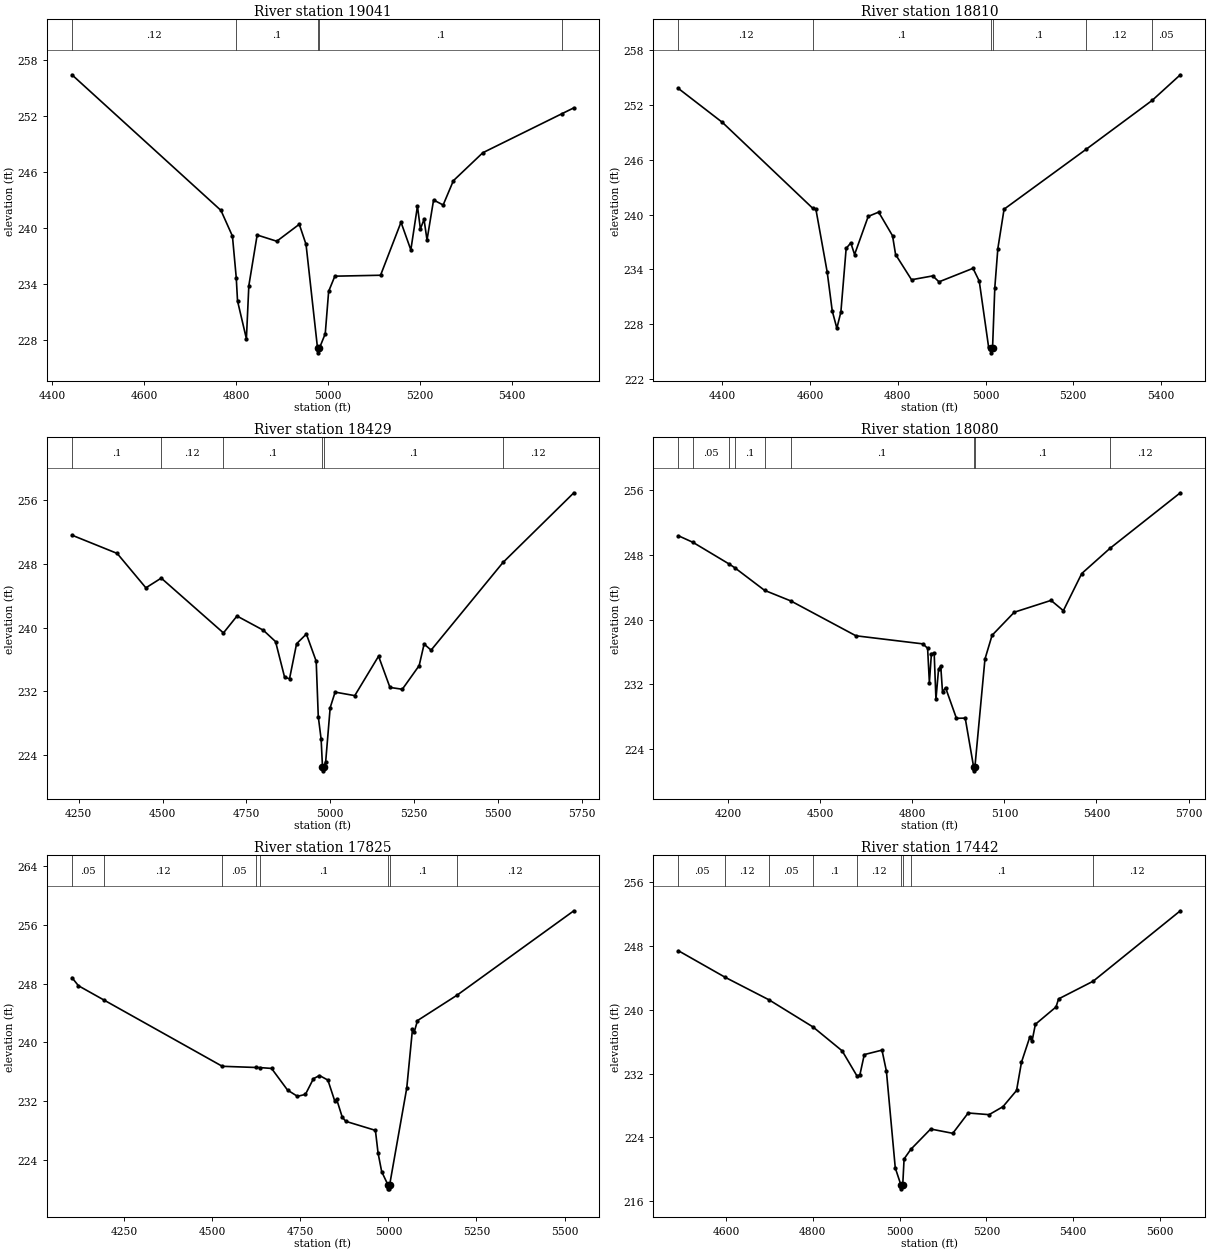
Type RM Length L Ch R = 1 ,19041   ,231,231,231
BEGIN DESCRIPTION:
LGII4495
END DESCRIPTION:
XS GIS Cut Line= 4
      2492463.34     13571162.87      2492294.07     13570707.15
      2492142.16     13570598.65      2491877.41     13570273.14
#Sta/Elev= 30
  4442.7  256.44    4767  241.88    4792  239.12  4800.3  234.66  4803.1  232.16
  4822.4   228.1  4827.7   233.8  4845.8  239.24  4888.5  238.57  4937.5  240.39
  4952.2  238.23  4977.2  227.09  4977.5  226.59  4981.3  227.09    4994  228.64
  5001.4  233.19  5014.9  234.82  5114.4  234.92  5158.9  240.61  5180.3  237.64
  5194.7  242.34  5201.1  239.89    5209  240.92  5215.5  238.71  5229.8     243
  5250.6  242.46  5272.9  245.07  5336.9  248.07  5509.9  252.28  5535.1  252.89
#Mann= 5 ,-1 , 0
  4442.7     .12       0  4800.3      .1       0  4977.2     .05       0
  4981.3      .1       0  5509.9     .05       0
Bank Sta=4977.2,4981.3
XS Rating Curve= 0 ,0
Exp/Cntr=0.3,0.1

Type RM Length L Ch R = 1 ,18810   ,381,381,381
BEGIN DESCRIPTION:
LGII4494
END DESCRIPTION:
XS GIS Cut Line= 3
      2492512.33      13571096.5      2492325.41     13570555.89
      2491929.31     13570142.56
#Sta/Elev= 30
  4299.6   253.8  4400.1  250.08  4605.9  240.69    4613  240.61  4638.9   233.7
  4650.4  229.45  4660.9  227.56  4670.1  229.35  4682.1   236.3  4692.7   236.9
  4701.3  235.63  4732.4   239.8  4756.2  240.27  4787.9  237.68  4794.8  235.63
  4831.2  232.87  4879.6  233.29  4893.8  232.64  4971.4  234.12  4985.6  232.72
    5007  225.48  5011.8  225.37  5012.1  224.87  5015.9  225.37  5021.1  232.02
    5028  236.28  5042.2  240.59  5228.9  247.13    5380   252.5  5444.1   255.3
#Mann= 6 ,-1 , 0
  4299.6     .12       0  4605.9      .1       0  5011.8     .05       0
  5015.9      .1       0  5228.9     .12       0    5380     .05       0
Bank Sta=5011.8,5015.9
XS Rating Curve= 0 ,0
Exp/Cntr=0.3,0.1

Type RM Length L Ch R = 1 ,18429   ,349,349,349
BEGIN DESCRIPTION:
LGII4493
END DESCRIPTION:
XS GIS Cut Line= 3
      2492952.27     13571125.25      2492391.54     13570360.36
      2491947.05     13570039.18
#Sta/Elev= 30
  4229.7  251.59  4364.5   249.3  4450.2  244.98    4496   246.2  4681.5  239.32
  4721.9  241.44  4800.4  239.66  4836.9  238.23    4864  233.74  4878.6  233.57
  4899.6  237.96  4928.8  239.18  4958.1  235.77  4964.3  228.83  4972.8  225.98
  4976.9  222.51  4977.2  222.01    4981  222.51  4986.4  223.16  4999.8  229.94
  5014.5  231.89  5073.1  231.45  5144.1   236.4  5178.1  232.48  5214.9  232.25
  5265.2  235.22  5279.9  237.92  5300.8  237.16  5515.1  248.16  5726.5  256.91
#Mann= 6 ,-1 , 0
  4229.7      .1       0    4496     .12       0  4681.5      .1       0
  4976.9     .05       0    4981      .1       0  5515.1     .12       0
Bank Sta=4976.9,4981
XS Rating Curve= 0 ,0
Exp/Cntr=0.3,0.1

Type RM Length L Ch R = 1 ,18080   ,255,255,255
BEGIN DESCRIPTION:
LGII4492
END DESCRIPTION:
XS GIS Cut Line= 4
      2492978.14     13571053.36      2492503.68     13570256.85
      2492374.29     13570038.32      2492357.04     13569584.03
#Sta/Elev= 30
  4037.6  250.36    4085  249.55  4201.7   246.9  4220.6  246.43  4318.4  243.62
  4404.1  242.31    4616  238.01  4834.1  237.01  4849.7  236.47  4855.5  232.23
  4862.1   235.8  4871.1  235.86  4876.9  230.17  4885.4  233.88  4892.5  234.28
  4898.3  231.05  4908.1  231.61  4943.6  227.82  4972.3  227.84  4999.6  221.83
  4999.9  221.33  5003.9  221.83  5036.6  235.13  5059.8  238.07  5132.2  240.92
    5252  242.38  5292.1  241.11  5352.1   245.7  5443.8   248.8  5673.3  255.67
#Mann= 9 ,-1 , 0
  4037.6      .1       0    4085     .05       0  4201.7     .12       0
  4220.6      .1       0  4318.4     .12       0  4404.1      .1       0
  4999.6     .05       0  5003.9      .1       0  5443.8     .12       0
Bank Sta=4999.6,5003.9
XS Rating Curve= 0 ,0
Exp/Cntr=0.3,0.1

Type RM Length L Ch R = 1 ,17825   ,383,383,383
BEGIN DESCRIPTION:
LGII4491
END DESCRIPTION:
XS GIS Cut Line= 3
      2493024.42     13570901.64      2492717.16      13570259.7
      2492585.72      13569558.7
#Sta/Elev= 30
  4101.6  248.82  4120.1  247.71  4192.9  245.75  4528.4  236.72  4623.1  236.56
  4636.5  236.54  4668.3  236.43  4713.6  233.48  4741.8  232.62  4764.5  232.89
  4787.2  235.03  4804.3  235.46  4828.2  234.84  4847.8  231.97  4852.9  232.25
  4868.9  229.79  4879.1  229.21  4963.1  227.98  4970.7  224.88  4980.9  222.35
  4999.1   220.5  4999.4     220  5003.1     220  5003.4   220.5  5052.1  233.75
  5068.3  241.75  5073.3  241.39  5082.6  242.96  5194.5  246.41  5526.5  257.94
#Mann= 8 ,-1 , 0
  4101.6     .05       0  4192.9     .12       0  4528.4     .05       0
  4623.1     .12       0  4636.5      .1       0  4999.1     .05       0
  5003.4      .1       0  5194.5     .12       0
Bank Sta=4999.1,5003.4
XS Rating Curve= 0 ,0
Exp/Cntr=0.3,0.1

Type RM Length L Ch R = 1 ,17442   ,327,327,327
BEGIN DESCRIPTION:
LGII4490
END DESCRIPTION:
XS GIS Cut Line= 3
      2493040.89     13570824.85      2492909.21     13570166.42
      2492739.57     13569712.24
#Sta/Elev= 30
  4490.4   247.4  4598.5  244.06  4699.6  241.23  4800.6  237.84  4867.6  234.85
  4901.7  231.71  4908.4  231.82  4918.6  234.38  4959.4  234.94  4969.6  232.29
    4990  220.17  5002.9  218.05  5003.2  217.55  5007.2  218.05  5010.3   221.3
  5025.8   222.5  5071.5  225.05  5122.5  224.51    5158  227.06  5206.1  226.85
  5238.1  227.85  5269.4  229.88  5280.8  233.43  5299.7  236.54    5305  236.04
  5312.8  238.18  5360.3  240.35  5366.2  241.36  5445.9  243.58  5646.7  252.41
#Mann= 9 ,-1 , 0
  4490.4     .05       0  4598.5     .12       0  4699.6     .05       0
  4800.6      .1       0  4901.7     .12       0  5002.9     .05       0
  5007.2     .12       0  5025.8      .1       0  5445.9     .12       0
Bank Sta=5002.9,5007.2
XS Rating Curve= 0 ,0
Exp/Cntr=0.3,0.1

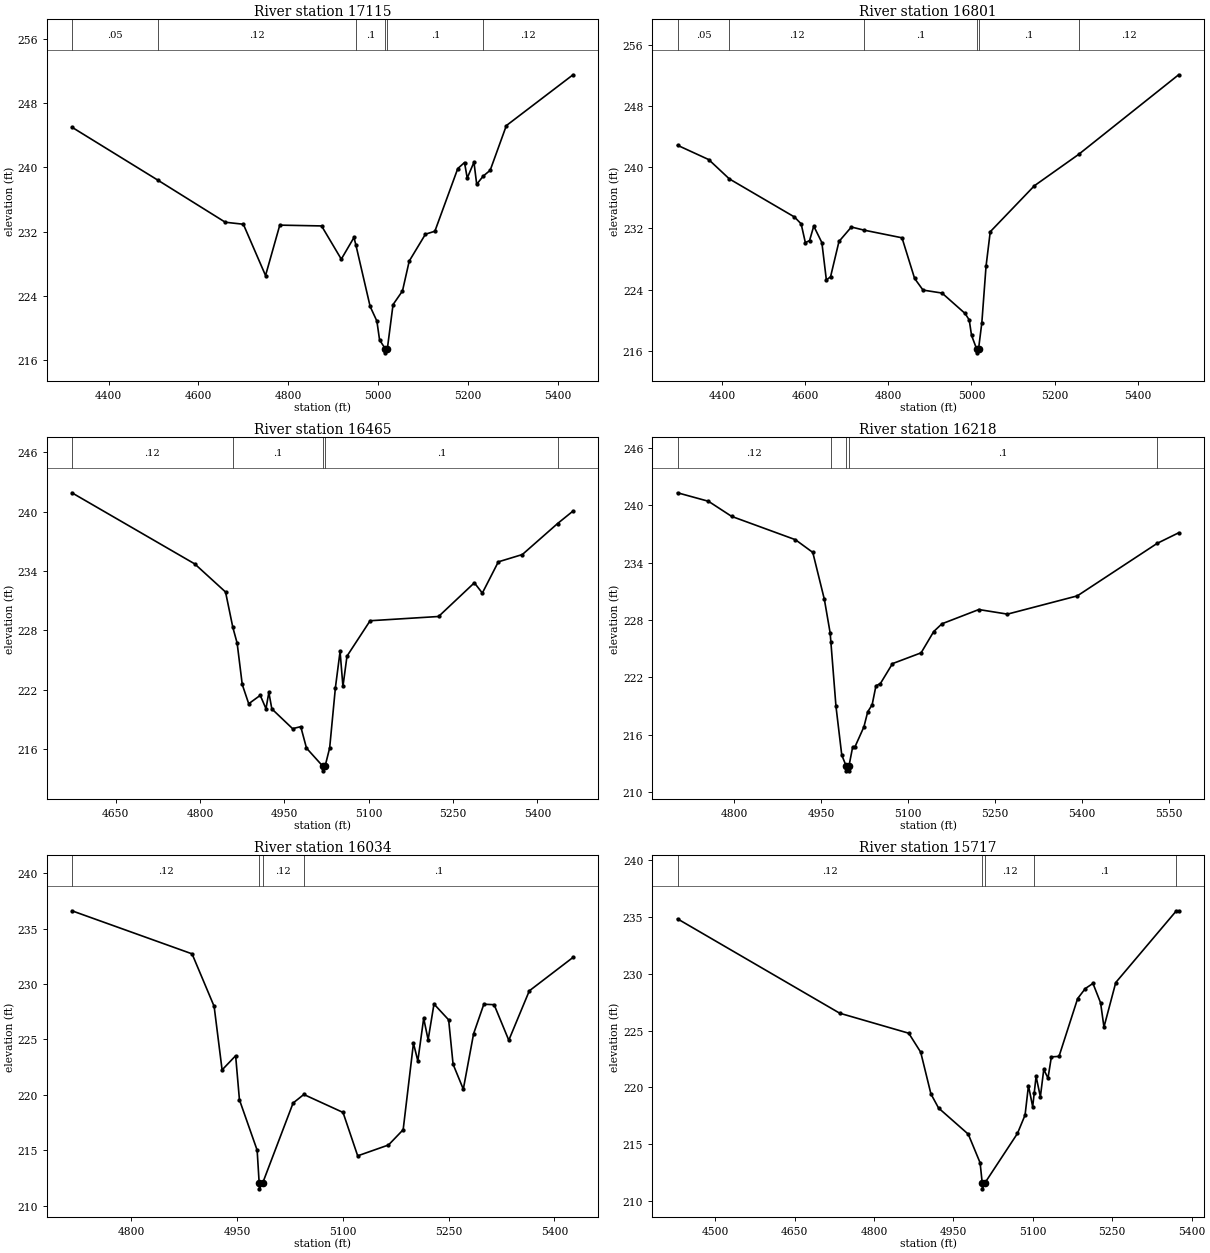
Type RM Length L Ch R = 1 ,17115   ,314,314,314
BEGIN DESCRIPTION:
LGII4489
END DESCRIPTION:
XS GIS Cut Line= 3
      2493117.71     13570715.11      2493156.12     13570281.65
      2492777.53      13569716.5
#Sta/Elev= 30
  4318.4     245  4509.2  238.42  4659.8  233.16    4700  232.91  4749.4  226.52
  4781.1   232.8  4874.1   232.7    4918  228.56  4946.2  231.26  4950.3  230.37
  4982.2  222.67  4997.2  220.85  5003.2   218.5    5016  217.39  5016.3  216.89
  5020.5  217.39  5033.2   222.9  5054.2   224.6  5069.2  228.32  5105.3  231.67
  5126.3  232.04  5177.3  239.85  5192.3   240.6  5198.3  238.66  5213.3  240.64
  5219.4  237.89  5234.1  238.92  5249.4  239.63  5285.4   245.2  5433.8  251.53
#Mann= 6 ,-1 , 0
  4318.4     .05       0  4509.2     .12       0  4950.3      .1       0
    5016     .05       0  5020.5      .1       0  5234.1     .12       0
Bank Sta=5016,5020.5
XS Rating Curve= 0 ,0
Exp/Cntr=0.3,0.1

Type RM Length L Ch R = 1 ,16801   ,336,336,336
BEGIN DESCRIPTION:
LGII4488
END DESCRIPTION:
XS GIS Cut Line= 3
      2493150.64     13570649.23      2493265.86      13569837.2
      2492985.99     13569573.79
#Sta/Elev= 30
  4293.4  242.86  4368.4  240.99  4417.9  238.47  4574.5  233.49  4590.6  232.59
  4600.7  230.14  4610.8  230.41  4620.9   232.3  4640.4  230.14  4651.2  225.26
  4661.3  225.68  4681.5  230.29  4711.3  232.18  4741.9  231.77    4833  230.77
  4863.3  225.46  4883.5  223.94  4929.2  223.55  4984.5  220.89  4994.6  220.04
  5000.1  218.03  5012.5  216.24  5012.8  215.74    5017  216.24  5024.9  219.67
    5035  227.05  5045.1  231.56  5151.2  237.57  5257.4  241.66  5497.9  252.07
#Mann= 6 ,-1 , 0
  4293.4     .05       0  4417.9     .12       0  4741.9      .1       0
  5012.5     .05       0    5017      .1       0  5257.4     .12       0
Bank Sta=5012.5,5017
XS Rating Curve= 0 ,0
Exp/Cntr=0.3,0.1

Type RM Length L Ch R = 1 ,16465   ,247,247,247
BEGIN DESCRIPTION:
LGII4487
END DESCRIPTION:
XS GIS Cut Line= 3
      2493660.92     13570440.75      2493529.24     13569886.58
      2493288.87     13569673.52
#Sta/Elev= 30
  4572.4  241.91  4790.8  234.71  4845.5  231.87  4858.5  228.28  4866.1   226.7
  4875.2  222.51  4886.7  220.56  4907.2  221.41  4917.4  220.06  4922.5   221.7
  4927.8  220.04  4964.7  218.04  4979.2  218.24  4989.4  216.07  5017.9  214.27
  5018.2  213.77  5022.6  214.27  5030.6  216.09  5040.8  222.19  5049.1  225.85
  5054.2  222.31  5061.4  225.38  5102.5  228.96  5224.2  229.39  5287.8   232.8
    5302  231.76  5330.4  234.92  5373.1  235.66  5435.8   238.8  5463.2  240.06
#Mann= 5 ,-1 , 0
  4572.4     .12       0  4858.5      .1       0  5017.9     .05       0
  5022.6      .1       0  5435.8     .12       0
Bank Sta=5017.9,5022.6
XS Rating Curve= 0 ,0
Exp/Cntr=0.3,0.1

Type RM Length L Ch R = 1 ,16218   ,184,184,184
BEGIN DESCRIPTION:
Mapping XS f5c6c804
END DESCRIPTION:
XS GIS Cut Line= 3
      2493783.98     13570358.41      2493789.25     13570052.62
      2493368.73     13569684.67
#Sta/Elev= 30
  4702.5   241.3  4755.9  240.41  4795.9  238.83  4905.9  236.39  4935.9  235.06
  4955.9  230.14  4965.9  226.62  4967.1   225.7  4975.9  218.95  4985.9  213.85
  4993.5   212.7  4993.9   212.2    4998   212.2  4998.3   212.7  5004.6  214.66
  5008.3  214.66  5024.1   216.8  5030.7  218.38  5038.3  219.11  5044.9   221.1
  5052.5  221.33  5073.4  223.42  5122.8  224.55  5144.6  226.78  5158.8  227.59
  5222.4  229.08  5271.8   228.6  5392.3  230.51  5530.2  236.01  5567.1  237.11
#Mann= 5 ,-1 , 0
  4702.5     .12       0  4967.1      .1       0  4993.5     .05       0
  4998.3      .1       0  5530.2     .12       0
Bank Sta=4993.5,4998.3
XS Rating Curve= 0 ,0
Exp/Cntr=0.3,0.1

Type RM Length L Ch R = 1 ,16034   ,317,317,317
BEGIN DESCRIPTION:
Mapping XS 3e5bdbed
END DESCRIPTION:
XS GIS Cut Line= 3
      2494021.19     13570194.93      2493926.31     13569936.65
      2493579.15     13569673.64
#Sta/Elev= 30
  4715.8  236.62  4886.2  232.73  4917.5  227.99  4928.8  222.25    4948  223.53
  4953.4  219.55  4978.5     215  4981.4  212.01  4981.8  211.51  4986.2  212.01
  5029.5  219.26  5044.7  220.03  5100.3  218.41  5121.1  214.49  5164.8  215.47
  5185.6  216.85  5200.2  224.66  5206.4  223.06  5214.7  226.91    5221  224.97
  5229.3   228.2  5250.1  226.77  5256.4  222.76  5270.9  220.51  5285.5  225.52
    5300  228.18  5314.6  228.14  5335.4  224.93  5364.5  229.39  5426.5  232.41
#Mann= 4 ,-1 , 0
  4715.8     .12       0  4981.4     .05       0  4986.2     .12       0
  5044.7      .1       0
Bank Sta=4981.4,4986.2
XS Rating Curve= 0 ,0
Exp/Cntr=0.3,0.1

Type RM Length L Ch R = 1 ,15717   ,413,413,413
BEGIN DESCRIPTION:
Mapping XS 9a1551c7
END DESCRIPTION:
XS GIS Cut Line= 3
        2494153.     13570200.26      2494116.09     13569746.87
      2493810.34     13569362.04
#Sta/Elev= 30
  4428.9  234.83  4735.2  226.53  4865.6  224.77  4888.2   223.1  4907.5  219.43
  4921.9  218.19    4978  215.89  5000.4  213.37  5004.4  211.58  5004.8  211.08
  5009.2  211.58  5070.9  215.95  5085.3  217.57  5091.7  220.16  5099.7   218.3
  5102.5  219.47  5106.1  220.97  5114.2  219.18  5120.6  221.58  5128.6  220.82
    5135  222.69  5149.4  222.73  5184.6  227.82  5199.1   228.7  5213.5  229.15
  5227.9  227.45  5234.3  225.31  5256.6  229.23  5371.1  235.54  5375.3  235.54
#Mann= 5 ,-1 , 0
  4428.9     .12       0  5004.4     .05       0  5009.2     .12       0
  5102.5      .1       0  5371.1     .12       0
Bank Sta=5004.4,5009.2
XS Rating Curve= 0 ,0
Exp/Cntr=0.3,0.1

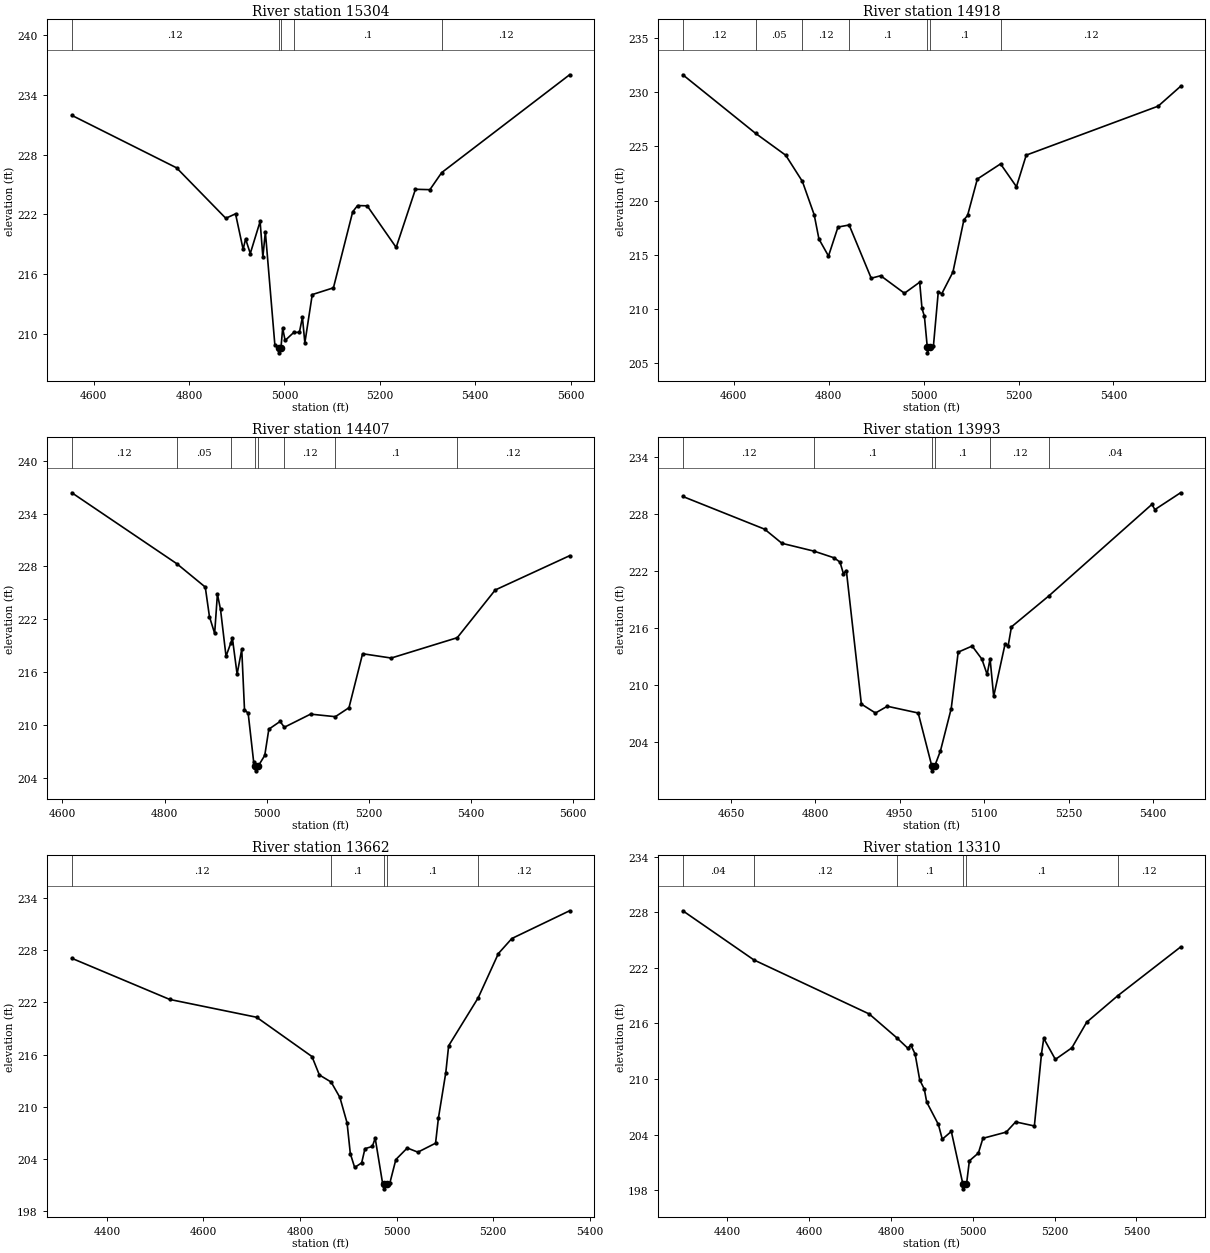
Type RM Length L Ch R = 1 ,15304   ,386,386,386
BEGIN DESCRIPTION:
Mapping XS 6fe0ef31
END DESCRIPTION:
XS GIS Cut Line= 3
       2494263.7     13570158.06      2494384.95     13569667.79
      2494305.88     13569135.38
#Sta/Elev= 30
  4554.4  231.93  4773.9  226.67  4877.1  221.61  4897.5  222.06  4913.4   218.5
  4918.6  219.54  4928.4  218.08    4949  221.29  4954.8  217.72    4960  220.26
  4979.9  208.93  4987.8  208.62  4988.1  208.12  4992.7  208.62  4996.3  210.59
  5001.4  209.36  5019.4  210.16  5031.4  210.18  5037.7  211.69  5042.8  209.12
  5058.3  213.96  5102.7  214.64  5143.1  222.26  5153.3  222.89  5173.5  222.86
  5234.2  218.69  5274.6  224.52  5304.9  224.48  5329.6  226.19  5597.7     236
#Mann= 5 ,-1 , 0
  4554.4     .12       0  4987.8     .05       0  4992.7     .12       0
  5019.4      .1       0  5329.6     .12       0
Bank Sta=4987.8,4992.7
XS Rating Curve= 0 ,0
Exp/Cntr=0.3,0.1

Type RM Length L Ch R = 1 ,14918   ,511,511,511
BEGIN DESCRIPTION:
Mapping XS 5b2e7aab
END DESCRIPTION:
XS GIS Cut Line= 3
      2494706.52      13570131.7      2494722.34     13569636.16
      2494590.74     13569099.24
#Sta/Elev= 30
  4492.7  231.63  4646.1  226.21  4709.5  224.19  4744.6  221.77  4769.5  218.68
  4779.5  216.44  4799.6  214.87  4819.6  217.55  4843.1  217.74  4889.6  212.82
  4909.6  213.05  4959.6  211.43  4991.7  212.45  4996.6  210.03  5001.7  209.29
  5007.8  206.42  5008.1  205.92  5012.8  206.42  5020.6  206.51  5030.9  211.56
  5038.2  211.38  5061.8  213.39  5084.9  218.22  5092.6  218.62  5113.2  221.99
  5162.1  223.39  5195.6  221.28  5216.2   224.2  5494.2  228.73  5541.3  230.56
#Mann= 7 ,-1 , 0
  4492.7     .12       0  4646.1     .05       0  4744.6     .12       0
  4843.1      .1       0  5007.8     .05       0  5012.8      .1       0
  5162.1     .12       0
Bank Sta=5007.8,5012.8
XS Rating Curve= 0 ,0
Exp/Cntr=0.3,0.1

Type RM Length L Ch R = 1 ,14407   ,414,414,414
BEGIN DESCRIPTION:
Mapping XS 63d7e0e1
END DESCRIPTION:
XS GIS Cut Line= 3
      2494880.51     13570273.99      2495038.64     13569894.47
      2495149.34     13569340.98
#Sta/Elev= 30
  4618.4  236.37  4824.2  228.31  4879.9  225.66  4888.1   222.3  4898.3   220.4
  4903.7  224.86  4909.8  223.12  4920.6   217.8  4929.7  219.27    4933  219.89
  4942.3  215.77  4951.4  218.59  4956.8  211.74    4964  211.33  4974.8  205.78
  4978.1  205.29  4978.5  204.79  4983.2  205.29  4996.5  206.54  5004.5  209.52
  5026.6   210.4  5034.9  209.74  5086.3  211.23  5134.9  210.94  5161.6  211.96
  5188.3  218.09  5244.4   217.6  5373.8  219.91  5448.3  225.33    5594  229.22
#Mann= 8 ,-1 , 0
  4618.4     .12       0  4824.2     .05       0  4929.7      .1       0
  4978.1     .05       0  4983.2      .1       0  5034.9     .12       0
  5134.9      .1       0  5373.8     .12       0
Bank Sta=4978.1,4983.2
XS Rating Curve= 0 ,0
Exp/Cntr=0.3,0.1

Type RM Length L Ch R = 1 ,13993   ,331,331,331
BEGIN DESCRIPTION:
Mapping XS fec58029
END DESCRIPTION:
XS GIS Cut Line= 3
      2495391.85     13570226.56      2495449.83     13569978.82
      2495255.14     13569378.96
#Sta/Elev= 30
  4564.1  229.87  4709.5  226.43  4740.3  224.94  4797.6  224.11  4833.1  223.41
  4843.6  222.96  4849.6  221.76  4854.9  222.07  4881.6  208.01  4906.7  207.07
  4927.7  207.78  4982.7  207.07  5006.9  201.48  5007.3  200.98    5012  201.48
  5022.3  203.09  5041.4  207.54  5053.8  213.48  5078.6  214.12  5095.9  212.75
  5105.3  211.13  5110.5  212.79  5116.9  208.82  5137.3  214.37  5142.6  214.12
  5148.5  216.14    5215   219.4  5398.3  229.04  5403.6  228.49  5449.2  230.26
#Mann= 6 ,-1 , 0
  4564.1     .12       0  4797.6      .1       0  5006.9     .05       0
    5012      .1       0  5110.5     .12       0    5215     .04       0
Bank Sta=5006.9,5012
XS Rating Curve= 0 ,0
Exp/Cntr=0.3,0.1

Type RM Length L Ch R = 1 ,13662   ,352,352,352
BEGIN DESCRIPTION:
Mapping XS 2fc2d46c
END DESCRIPTION:
XS GIS Cut Line= 3
      2495745.05     13570247.63      2495745.05     13569762.68
      2495455.85     13569299.97
#Sta/Elev= 30
  4327.6  227.08  4530.2  222.35  4710.2   220.3  4824.8  215.78  4840.1  213.66
  4864.4  212.85  4882.6  211.08  4897.5  208.14  4904.2  204.61  4913.2  203.02
  4927.7  203.55  4934.5  205.18  4949.8  205.44  4955.7  206.39    4971   201.2
  4974.3  201.06  4974.7  200.56  4979.6  201.06  4986.3  201.28  4998.5  203.93
  5022.1  205.26  5044.1  204.78  5080.7  205.81  5086.6  208.69  5101.9  213.93
  5107.8  217.02    5169  222.54  5210.8  227.63  5238.7  229.36  5358.2  232.55
#Mann= 5 ,-1 , 0
  4327.6     .12       0  4864.4      .1       0  4974.3     .05       0
  4979.6      .1       0    5169     .12       0
Bank Sta=4974.3,4979.6
XS Rating Curve= 0 ,0
Exp/Cntr=0.3,0.1

Type RM Length L Ch R = 1 ,13310   ,264,264,264
BEGIN DESCRIPTION:
Mapping XS c0d73fb6
END DESCRIPTION:
XS GIS Cut Line= 3
      2495776.68      13570279.3      2495855.75     13569794.31
      2496160.74     13569137.01
#Sta/Elev= 30
  4291.6  228.15  4465.2  222.85    4747  217.02  4814.4  214.45  4841.7  213.31
  4848.4   213.7  4859.1   212.7  4870.4   209.9  4881.5  208.93  4887.5  207.51
    4916   205.1  4925.5  203.51  4947.6  204.35  4975.9  198.66  4976.4  198.16
  4982.4  198.66  4984.7  198.66  4991.7  201.18  5013.7  202.02  5024.8  203.61
  5081.8  204.28  5104.7  205.38  5150.5  204.94  5167.9  212.73  5173.4  214.39
  5201.8  212.12  5242.1  213.37  5278.3  216.13  5353.7  218.97  5507.6  224.24
#Mann= 6 ,-1 , 0
  4291.6     .04       0  4465.2     .12       0  4814.4      .1       0
  4975.9     .05       0  4982.4      .1       0  5353.7     .12       0
Bank Sta=4975.9,4982.4
XS Rating Curve= 0 ,0
Exp/Cntr=0.3,0.1

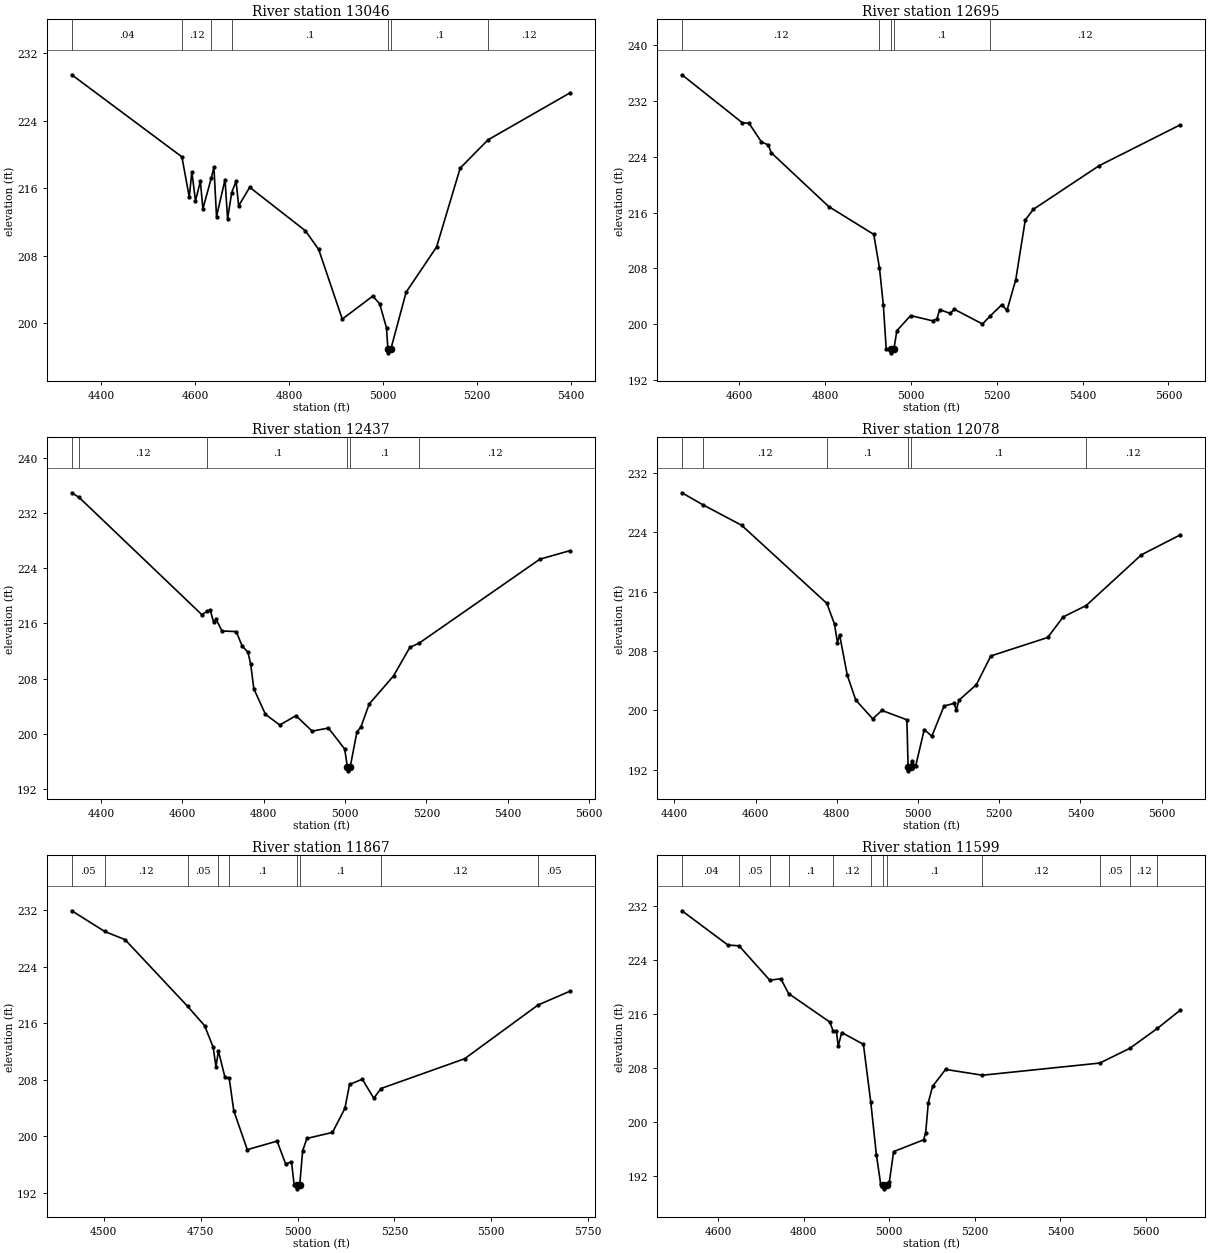
Type RM Length L Ch R = 1 ,13046   ,351,351,351
BEGIN DESCRIPTION:
Mapping XS 584e8657
END DESCRIPTION:
XS GIS Cut Line= 3
      2495839.92     13570326.79      2496019.17     13569910.29
      2496377.66     13569420.01
#Sta/Elev= 30
  4337.7  229.42    4572  219.71  4587.7  214.95  4593.2  217.94  4600.9   214.5
  4611.3  216.82  4616.7  213.56  4634.5  217.19  4640.2  218.47  4645.7  212.64
  4663.8  217.02  4669.2  212.39    4678  215.47  4687.3  216.84  4692.8  213.91
  4716.3  216.11  4834.9  210.96  4863.1  208.75  4913.3  200.51  4978.1  203.23
  4992.8  202.33  5007.4  199.47  5010.3  197.02  5010.8  196.52  5016.9  197.02
  5049.2   203.7    5114  209.05  5164.2  218.38  5223.4  221.72  5398.5   227.3
#Mann= 7 ,-1 , 0
  4337.7     .04       0    4572     .12       0  4634.5     .04       0
    4678      .1       0  5010.3     .05       0  5016.9      .1       0
  5223.4     .12       0
Bank Sta=5010.3,5016.9
XS Rating Curve= 0 ,0
Exp/Cntr=0.3,0.1

Type RM Length L Ch R = 1 ,12695   ,258,258,258
BEGIN DESCRIPTION:
Mapping XS 307a6572
END DESCRIPTION:
XS GIS Cut Line= 3
      2496066.61     13570484.93      2496288.03     13570042.08
      2496424.92      13569389.2
#Sta/Elev= 30
    4466  235.73  4606.7  228.86  4622.4  228.78  4651.4   226.1  4667.2   225.7
  4673.8  224.59    4808  216.87  4913.1  212.88  4926.4  208.09  4935.5  202.72
  4942.1  196.52  4953.4  196.42  4953.9  195.92    4960  196.42    4967  199.09
    4999  201.25  5050.1  200.51  5060.3  200.77  5066.8  202.11    5091  201.57
  5101.2  202.15  5166.6  200.05  5183.8  201.15  5211.4   202.8  5223.8  202.01
  5244.2   206.4  5266.4  214.95  5285.1  216.46  5438.4  222.71  5628.2  228.58
#Mann= 5 ,-1 , 0
    4466     .12       0  4926.4      .1       0  4953.4     .05       0
    4960      .1       0  5183.8     .12       0
Bank Sta=4953.4,4960
XS Rating Curve= 0 ,0
Exp/Cntr=0.3,0.1

Type RM Length L Ch R = 1 ,12437   ,359,359,359
BEGIN DESCRIPTION:
Mapping XS 088044ce
END DESCRIPTION:
XS GIS Cut Line= 3
      2496177.35     13570527.04      2496514.71     13570110.61
      2496519.98     13569420.06
#Sta/Elev= 30
  4327.7  234.93  4345.7  234.26  4647.6  217.28  4660.9  217.77  4668.4  217.95
  4676.4  216.22  4682.8  216.59  4697.2  214.91  4732.4  214.82  4746.8  212.73
  4761.1  211.84  4767.9  210.11  4775.5  206.55  4804.3  202.82  4839.5  201.29
  4879.2  202.64  4919.2   200.4  4959.2  200.85  4999.2   197.8  5005.9  195.15
  5006.4  194.65  5012.5  195.15  5029.2  200.27  5039.2  201.02  5059.3  204.32
  5119.3   208.4  5159.3  212.52  5183.1  213.18  5479.3  225.31  5554.2  226.56
#Mann= 6 ,-1 , 0
  4327.7     .05       0  4345.7     .12       0  4660.9      .1       0
  5005.9     .05       0  5012.5      .1       0  5183.1     .12       0
Bank Sta=5005.9,5012.5
XS Rating Curve= 0 ,0
Exp/Cntr=0.3,0.1

Type RM Length L Ch R = 1 ,12078   ,211,211,211
BEGIN DESCRIPTION:
Mapping XS df30f9ba
END DESCRIPTION:
XS GIS Cut Line= 3
      2496688.68     13570674.67      2496841.56      13570168.6
       2496593.8     13569514.94
#Sta/Elev= 30
  4418.6  229.32  4469.2  227.73  4565.6  224.94  4775.5  214.41  4794.3   211.6
  4801.5  209.13  4806.8  210.17  4825.7  204.74  4846.6  201.39  4888.3  198.86
  4910.9  199.99  4972.5  198.73  4975.5  192.35    4976  191.85  4982.3  192.35
  4984.2  193.16  4993.9  192.44  5015.3  197.42  5033.8  196.51    5064  200.58
  5088.8  200.95  5094.1  200.04  5100.8  201.37  5143.6  203.46  5179.2  207.33
  5319.2  209.82  5357.5  212.59  5414.1  214.13    5550  220.96  5646.3  223.66
#Mann= 6 ,-1 , 0
  4418.6     .05       0  4469.2     .12       0  4775.5      .1       0
  4975.5     .05       0  4982.3      .1       0  5414.1     .12       0
Bank Sta=4975.5,4982.3
XS Rating Curve= 0 ,0
Exp/Cntr=0.3,0.1

Type RM Length L Ch R = 1 ,11867   ,268,268,268
BEGIN DESCRIPTION:
Mapping XS 8d795516
END DESCRIPTION:
XS GIS Cut Line= 3
      2496773.02     13570706.32      2496936.45     13570353.11
      2497310.39     13569536.77
#Sta/Elev= 30
  4417.2  231.93  4502.2     229  4554.6  227.85  4716.6  218.38  4760.2  215.65
  4782.3   212.6  4789.4  209.87  4795.9  212.06  4812.4  208.41  4823.7  208.21
  4835.4  203.62  4870.3   198.1  4947.3  199.31  4969.3  196.08  4984.4  196.38
  4991.3  193.13  4998.2  193.05  4998.7  192.55  5005.6  193.05  5013.3  197.95
  5024.3  199.69  5090.3  200.54  5122.4  203.95  5134.3  207.33  5167.3  208.08
  5196.9  205.38  5215.5  206.76  5431.3  210.97  5621.1  218.59  5704.3  220.56
#Mann= 9 ,-1 , 0
  4417.2     .05       0  4502.2     .12       0  4716.6     .05       0
  4795.9     .12       0  4823.7      .1       0  4998.2     .05       0
  5005.6      .1       0  5215.5     .12       0  5621.1     .05       0
Bank Sta=4998.2,5005.6
XS Rating Curve= 0 ,0
Exp/Cntr=0.3,0.1

Type RM Length L Ch R = 1 ,11599   ,262,262,262
BEGIN DESCRIPTION:
Mapping XS 88f19b6a
END DESCRIPTION:
XS GIS Cut Line= 3
      2497010.26     13570748.48      2497210.58     13570442.73
      2497326.55     13569652.01
#Sta/Elev= 30
  4515.8  231.25  4623.2  226.17  4649.1  226.06    4721  220.96  4746.8  221.18
  4764.8  218.99  4861.4  214.75  4869.1   213.4  4876.5  213.46  4880.8  211.18
  4889.1   213.2  4939.7  211.46  4956.9  202.88    4970  195.09  4980.1  190.72
  4986.5  190.54    4987  190.04    4994  190.54  5000.3  191.08  5010.3  195.56
  5080.1   197.3  5085.2  198.33  5091.3  202.83  5101.4  205.24  5131.7  207.74
  5217.8  206.88  5491.9  208.68    5562  210.86  5626.4  213.81  5680.5  216.55
#Mann= 12 ,-1 , 0
  4515.8     .04       0  4649.1     .05       0    4721     .04       0
  4764.8      .1       0  4869.1     .12       0  4956.9      .1       0
  4986.5     .05       0    4994      .1       0  5217.8     .12       0
  5491.9     .05       0    5562     .12       0  5626.4     .05       0
Bank Sta=4986.5,4994
XS Rating Curve= 0 ,0
Exp/Cntr=0.3,0.1

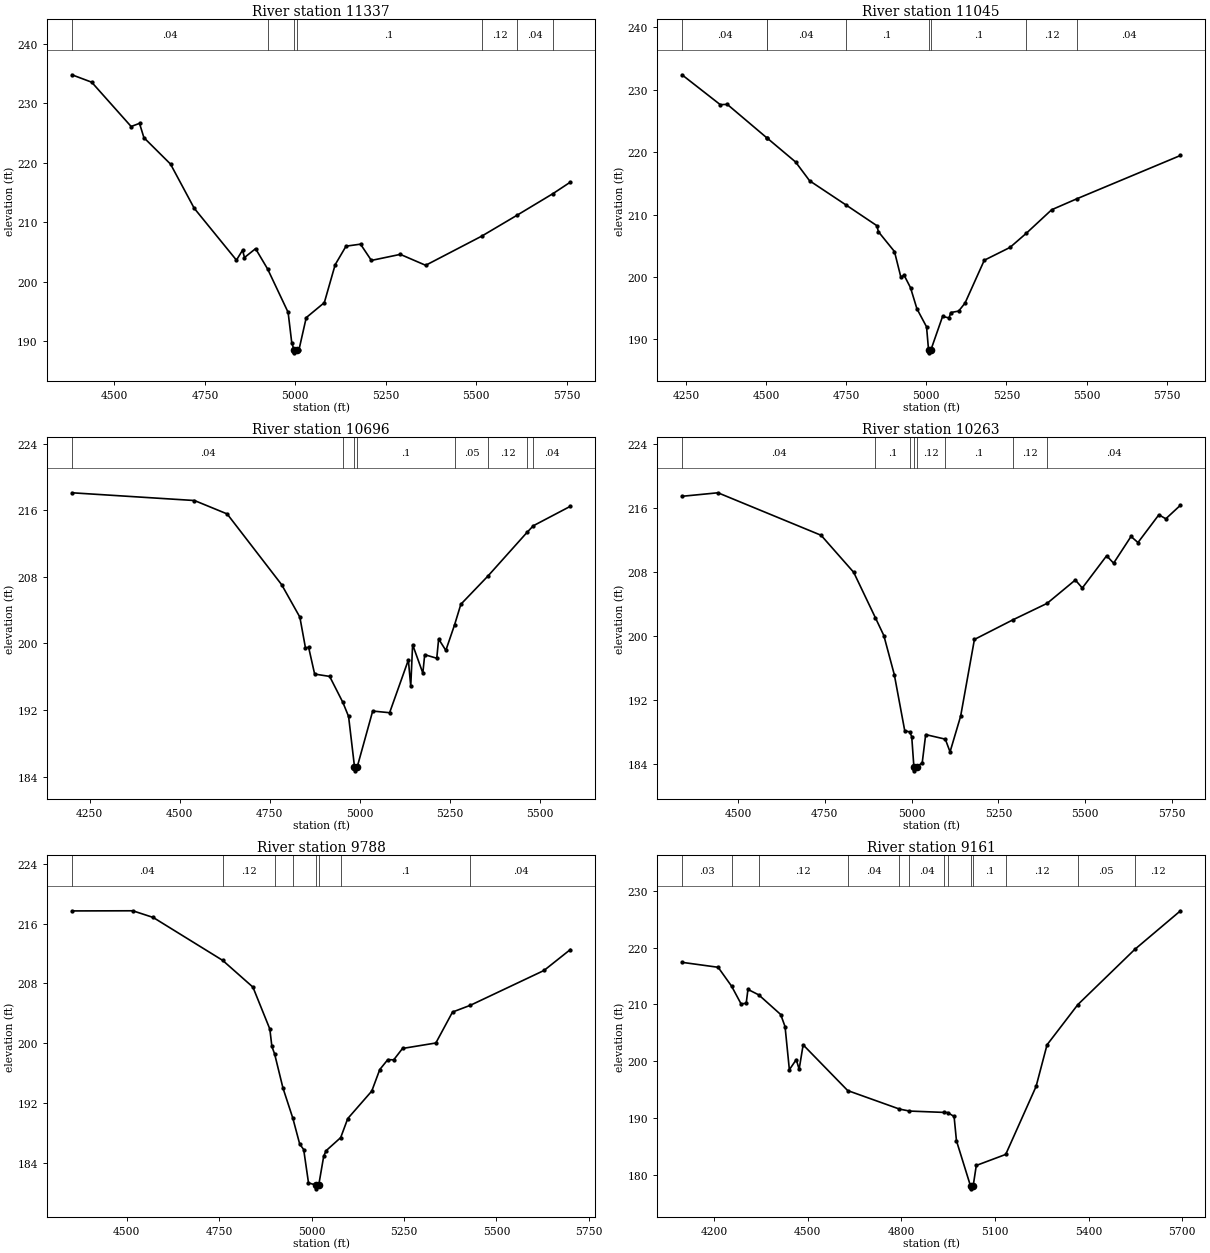
Type RM Length L Ch R = 1 ,11337   ,292,292,292
BEGIN DESCRIPTION:
Mapping XS 0bc02177
END DESCRIPTION:
XS GIS Cut Line= 3
      2497289.65     13570959.35      2497468.89     13570495.45
      2497500.52     13569615.04
#Sta/Elev= 30
  4382.3  234.81    4437  233.56  4546.1   226.1  4569.2  226.63  4581.4  224.22
    4655  219.77  4720.4  212.34  4837.2   203.6  4854.1  205.27  4859.5  204.04
  4890.1  205.53  4923.4  202.11  4980.1  194.81  4990.1  189.72  4996.4  188.49
  4996.9  187.99  5003.9  188.49  5010.2  188.53  5030.2  193.92  5080.2  196.44
  5110.2  202.83  5140.2  205.95  5180.3  206.29  5210.3  203.55  5290.3  204.57
  5360.4  202.73  5515.4  207.64  5613.9  211.19  5712.4   214.8  5760.6  216.74
#Mann= 7 ,-1 , 0
  4382.3     .04       0  4923.4      .1       0  4996.4     .05       0
  5003.9      .1       0  5515.4     .12       0  5613.9     .04       0
  5712.4     .05       0
Bank Sta=4996.4,5003.9
XS Rating Curve= 0 ,0
Exp/Cntr=0.3,0.1

Type RM Length L Ch R = 1 ,11045   ,349,349,349
BEGIN DESCRIPTION:
Mapping XS e455c439
END DESCRIPTION:
XS GIS Cut Line= 3
      2497511.05     13571096.44      2497732.47      13570521.8
       2497764.1     13569583.46
#Sta/Elev= 30
    4238  232.41  4357.4  227.62  4379.2  227.67  4503.4  222.27  4503.8  222.26
  4592.2  218.44  4636.1  215.42    4748   211.6    4846  208.22  4850.4  207.27
  4900.7  204.08  4920.7  199.96  4930.7  200.29  4950.7  198.29  4970.7  194.91
  5000.7  192.02  5006.9  188.35  5007.4  187.85  5014.5  188.35  5050.7  193.68
  5070.8  193.45  5076.5  194.31  5100.8  194.54  5120.8  195.83  5180.8  202.69
  5260.9  204.74  5311.4  206.99  5390.9  210.78  5469.6  212.54  5792.7  219.48
#Mann= 8 ,-1 , 0
    4238     .04       0  4503.4     .12       0  4503.8     .04       0
    4748      .1       0  5006.9     .05       0  5014.5      .1       0
  5311.4     .12       0  5469.6     .04       0
Bank Sta=5006.9,5014.5
XS Rating Curve= 0 ,0
Exp/Cntr=0.3,0.1

Type RM Length L Ch R = 1 ,10696   ,433,433,433
BEGIN DESCRIPTION:
Mapping XS 159a07a5
END DESCRIPTION:
XS GIS Cut Line= 3
      2498201.65      13571112.2      2498112.03     13570469.09
      2497906.45     13569762.72
#Sta/Elev= 30
  4200.6  218.09  4541.1  217.16  4631.9  215.55  4783.4  207.05  4833.9  203.16
  4849.5  199.47  4858.3  199.53    4875  196.32  4916.7  196.04  4953.5  192.91
  4969.3  191.23  4985.7   185.2  4986.2   184.7  4993.5   185.2  5036.3  191.88
  5083.3  191.68  5135.4  198.01    5142  194.86  5147.2  199.85  5175.6  196.44
  5180.8  198.65  5214.3  198.22  5219.5  200.53  5239.5  199.16    5264  202.26
  5281.2   204.7  5357.1  208.12  5465.2  213.34  5482.6  214.13  5585.6  216.47
#Mann= 8 ,-1 , 0
  4200.6     .04       0  4953.5      .1       0  4985.7     .05       0
  4993.5      .1       0    5264     .05       0  5357.1     .12       0
  5465.2     .05       0  5482.6     .04       0
Bank Sta=4985.7,4993.5
XS Rating Curve= 0 ,0
Exp/Cntr=0.3,0.1

Type RM Length L Ch R = 1 ,10263   ,475,475,475
BEGIN DESCRIPTION:
Mapping XS 2232d887
END DESCRIPTION:
XS GIS Cut Line= 3
      2498419.41     13571033.45      2498488.86      13570359.8
       2498433.3     13569602.86
#Sta/Elev= 30
  4338.5  217.44  4442.1  217.88  4739.2  212.57  4833.2  207.94  4895.5  202.28
    4920  200.04  4950.2  195.15  4980.3  188.13  4994.3     188  5000.4   187.4
  5006.6  183.63  5007.1  183.13  5014.4  183.63  5030.6  184.13  5040.6  187.66
  5097.1  187.09  5110.8   185.5  5141.3  189.96    5181  199.55  5291.3  201.99
  5390.4  204.06  5471.7  206.98  5491.8  205.98    5562  210.01    5582  209.08
  5632.2  212.42  5652.2  211.66  5712.4  215.13  5732.4  214.63  5774.7  216.33
#Mann= 8 ,-1 , 0
  4338.5     .04       0  4895.5      .1       0  4994.3     .12       0
  5006.6     .05       0  5014.4     .12       0  5097.1      .1       0
  5291.3     .12       0  5390.4     .04       0
Bank Sta=5006.6,5014.4
XS Rating Curve= 0 ,0
Exp/Cntr=0.3,0.1

Type RM Length L Ch R = 1 ,9788    ,627,627,627
BEGIN DESCRIPTION:
Mapping XS 985bff64
END DESCRIPTION:
XS GIS Cut Line= 3
      2498593.02     13571054.25      2498836.08     13570533.41
      2499134.31     13569819.03
#Sta/Elev= 30
  4351.3  217.68    4516   217.7  4571.2  216.81  4759.2  211.08  4841.1  207.51
  4886.9  201.91  4892.4  199.59  4899.8  198.59  4922.4  194.04  4949.1  190.01
  4967.7  186.56  4978.5  185.82  4991.5  181.38  5011.3  181.08  5011.8  180.58
  5019.2  181.08  5032.7  184.95  5039.1  185.67  5078.6  187.42  5097.7  189.96
  5162.7  193.63  5184.4  196.51  5206.1  197.83  5222.1   197.8  5245.9  199.32
  5336.1  200.05  5381.2  204.18  5429.8  205.09  5628.7  209.73  5700.2  212.53
#Mann= 8 ,-1 , 0
  4351.3     .04       0  4759.2     .12       0  4899.8     .04       0
  4949.1     .12       0  5011.3     .05       0  5019.2     .12       0
  5078.6      .1       0  5429.8     .04       0
Bank Sta=5011.3,5019.2
XS Rating Curve= 0 ,0
Exp/Cntr=0.3,0.1

Type RM Length L Ch R = 1 ,9161    ,411,411,411
BEGIN DESCRIPTION:
Mapping XS ee61a61f
END DESCRIPTION:
XS GIS Cut Line= 3
      2498662.46     13571137.58      2499301.36     13570804.24
      2499884.71     13570151.44
#Sta/Elev= 30
  4097.9  217.41  4213.6  216.54  4256.7  213.22  4287.1   210.1  4303.5  210.22
  4309.1  212.65  4343.7  211.69  4413.9  208.24  4427.9  206.11  4441.7  198.54
  4463.8  200.31    4473  198.62  4485.8  202.91  4628.5  194.87  4794.1  191.62
  4826.2  191.27  4937.9  191.03  4948.3  191.01  4969.1  190.32  4976.7  186.05
  5021.7   178.1  5022.2   177.6  5030.2   178.1  5040.2  181.71  5134.4  183.65
  5231.6  195.59  5266.7  202.91  5365.5  209.99  5547.6  219.68    5694  226.47
#Mann= 13 ,-1 , 0
  4097.9     .03       0  4256.7     .04       0  4343.7     .12       0
  4628.5     .04       0  4794.1     .12       0  4826.2     .04       0
  4937.9     .12       0  4948.3      .1       0  5021.7     .05       0
  5030.2      .1       0  5134.4     .12       0  5365.5     .05       0
  5547.6     .12       0
Bank Sta=5021.7,5030.2
XS Rating Curve= 0 ,0
Exp/Cntr=0.3,0.1