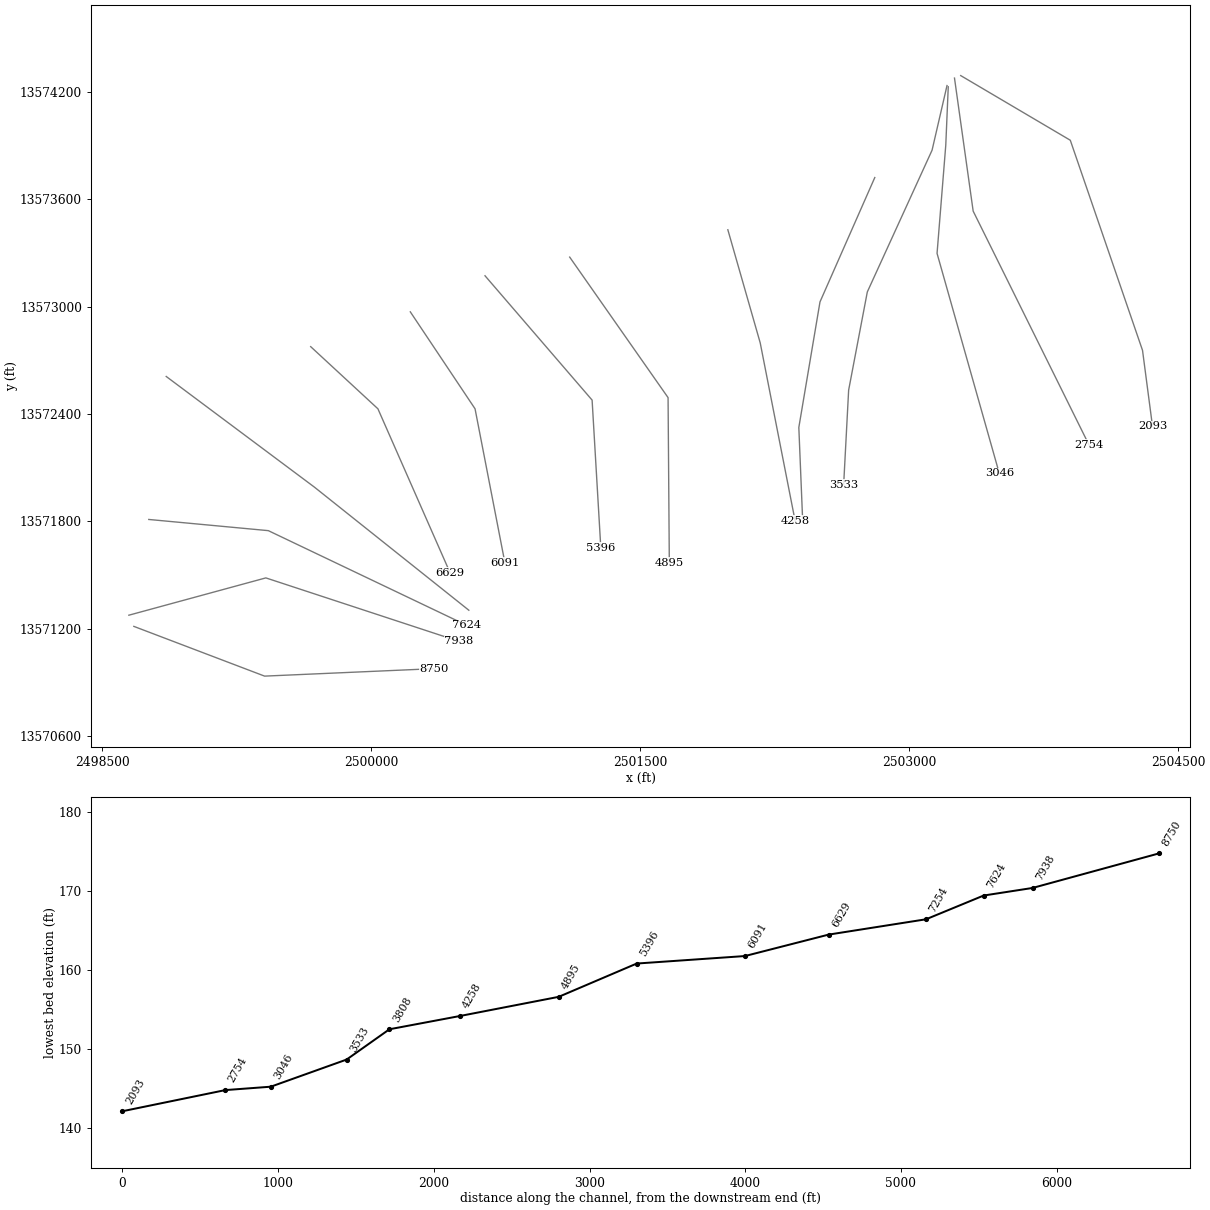
HEC-RAS study TRIB 22 TO GUADALUPE RIVER.prj: TRIB 22 TO GUADALUPE RIVER Base Level Engineering

--- TRIB 22 TO GUADALUPE RIVER.g01 (geometry) --- (continued)

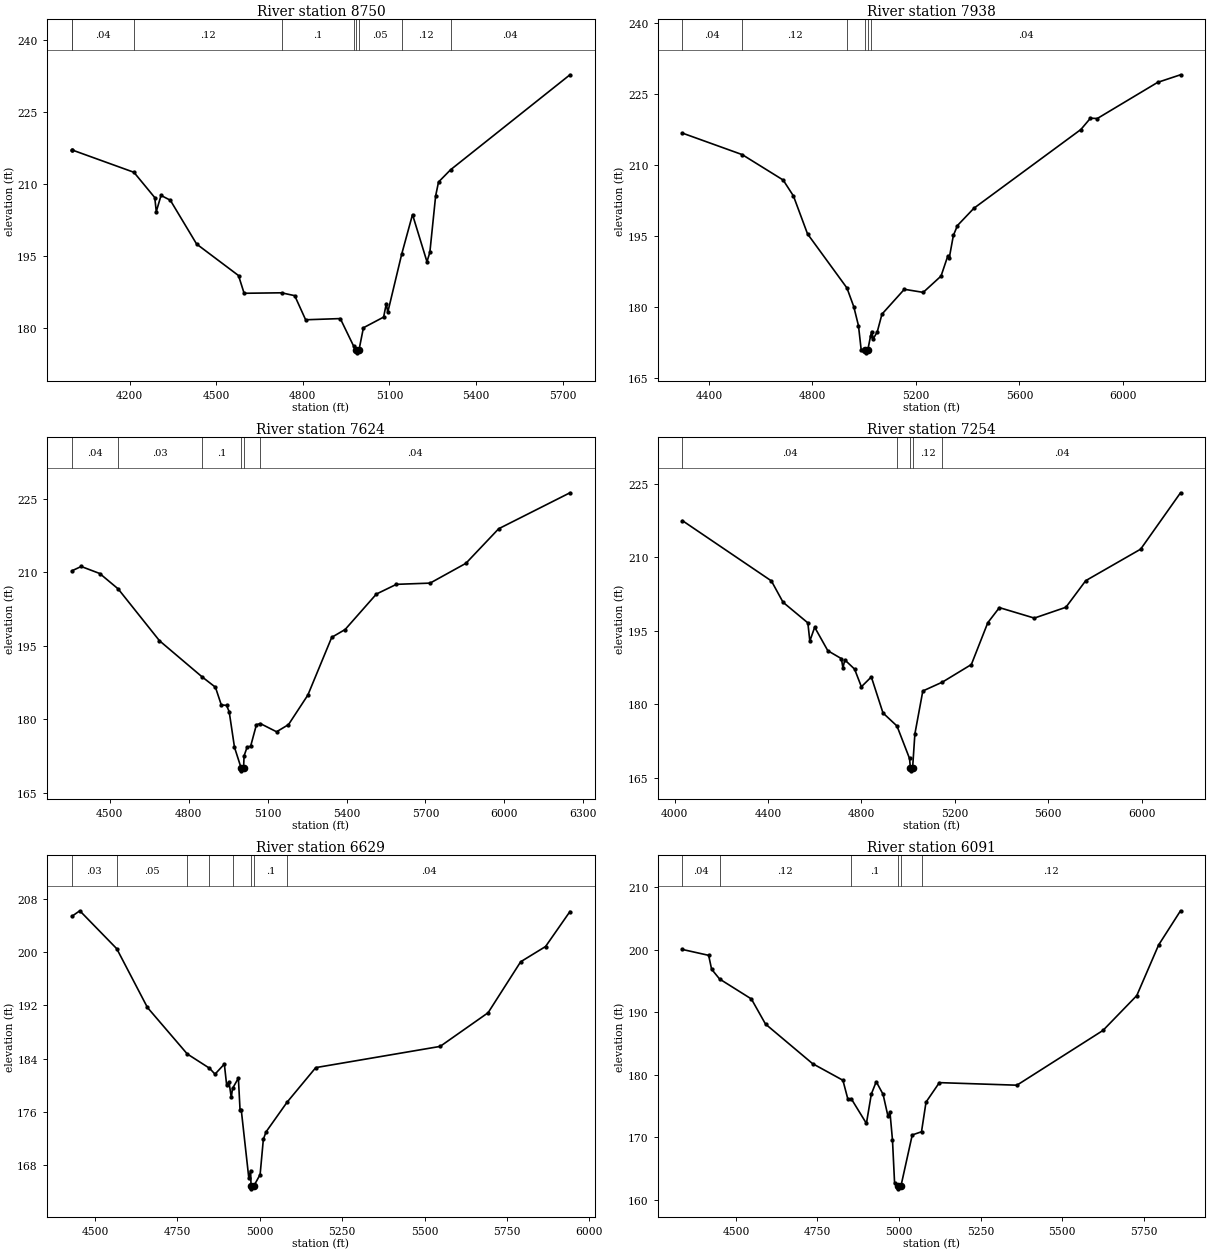
Type RM Length L Ch R = 1 ,8750    ,812,812,812
BEGIN DESCRIPTION:
Mapping XS d277546f
END DESCRIPTION:
XS GIS Cut Line= 3
      2498676.36     13571213.96      2499405.52     13570936.19
      2500349.93     13570977.85
#Sta/Elev= 30
    4000  217.13  4002.1  217.09  4214.9  212.46  4287.1  207.18  4292.4  204.26
  4308.9  207.63    4341  206.63  4432.2  197.48  4577.3  190.91  4596.7  187.21
  4726.5  187.31    4772  186.71  4809.8  181.68  4929.9  181.93  4975.9  176.21
  4985.6  175.28  4986.1  174.78  4994.4  175.28    5010  180.01    5080  182.24
  5089.4  185.07  5094.4  183.24  5142.7  195.39  5180.1  203.64  5230.2  193.79
  5240.2  195.76  5260.2  207.52  5270.2  210.43    5312  212.99  5725.6  232.81
#Mann= 9 ,-1 , 0
    4000     .03       0  4002.1     .04       0  4214.9     .12       0
  4726.5      .1       0  4975.9     .05       0  4985.6     .05       0
  4994.4     .05       0  5142.7     .12       0    5312     .04       0
Bank Sta=4985.6,4994.4
XS Rating Curve= 0 ,0
Exp/Cntr=0.3,0.1

Type RM Length L Ch R = 1 ,7938    ,314,314,314
BEGIN DESCRIPTION:
Mapping XS 25c3b05c
END DESCRIPTION:
XS GIS Cut Line= 3
      2498648.55     13571276.46      2499412.47      13571484.8
      2500488.88     13571130.62
#Sta/Elev= 30
  4297.6  216.77  4528.7  212.23  4686.9  206.87  4726.6  203.51  4781.1   195.5
  4933.4  184.09  4959.8  180.14    4978  176.13  4988.4  171.04  5004.7   170.9
  5005.2   170.4  5013.6   170.9  5024.8  173.96  5028.9   174.9  5034.1  173.27
  5050.6  174.83  5068.7  178.56  5155.2  183.81  5228.2  183.16  5297.1   186.6
  5323.6  190.91  5328.8  190.41  5344.7  195.17  5360.6  197.27  5424.2  200.92
  5837.5  217.53  5874.5  219.92    5901  219.85  6134.3  227.48  6222.6  229.08
#Mann= 6 ,-1 , 0
  4297.6     .04       0  4528.7     .12       0  4933.4      .1       0
  5004.7     .05       0  5013.6      .1       0  5024.8     .04       0
Bank Sta=5004.7,5013.6
XS Rating Curve= 0 ,0
Exp/Cntr=0.3,0.1

Type RM Length L Ch R = 1 ,7624    ,370,370,370
BEGIN DESCRIPTION:
Mapping XS 5e8e9ccc
END DESCRIPTION:
XS GIS Cut Line= 3
      2498759.67     13571811.19      2499426.36     13571748.69
      2500530.22     13571221.05
#Sta/Elev= 30
    4356  210.25  4391.5  211.13  4461.8   209.7  4531.9  206.56    4689  195.98
  4851.4  188.59  4901.6   186.5  4923.8   182.9  4943.9  182.79  4953.9   181.5
    4974  174.25  4999.7  169.94  5000.2  169.44  5008.6  169.94  5010.4  172.49
  5022.4  174.33  5035.2  174.42  5057.4  178.85  5072.1  179.09    5134  177.41
  5179.3  178.87  5252.9   184.9  5343.6  196.68  5394.5  198.27  5513.4  205.51
  5589.4  207.49  5717.5  207.74  5853.6  211.78  5978.1  218.83  6249.1  226.17
#Mann= 6 ,-1 , 0
    4356     .04       0  4531.9     .03       0  4851.4      .1       0
  4999.7     .05       0  5008.6      .1       0  5072.1     .04       0
Bank Sta=4999.7,5008.6
XS Rating Curve= 0 ,0
Exp/Cntr=0.3,0.1

Type RM Length L Ch R = 1 ,7254    ,625,625,625
BEGIN DESCRIPTION:
Mapping XS 0171f6b7
END DESCRIPTION:
XS GIS Cut Line= 3
      2498856.89     13572609.82       2499683.3     13571991.74
      2500544.43     13571304.23
#Sta/Elev= 30
  4033.1   217.5  4414.2   205.2  4464.2  200.84  4570.5  196.63  4578.9  192.92
  4599.7  195.74    4656  190.95  4714.3  189.33  4720.6  187.45  4728.9  189.07
  4770.6   187.2  4799.8  183.59  4842.4   185.6  4892.4  178.24  4952.3  175.58
  5006.1  168.95  5009.9  166.93  5010.4  166.43  5019.1  166.93    5029  173.97
    5063  182.73  5146.8  184.54  5270.9  188.13  5341.4  196.67    5391  199.75
  5540.7  197.61    5676  199.82  5760.9  205.25  5996.2  211.68    6167  223.19
#Mann= 5 ,-1 , 0
  4033.1     .04       0  4952.3     .12       0  5009.9     .05       0
  5019.1     .12       0  5146.8     .04       0
Bank Sta=5009.9,5019.1
XS Rating Curve= 0 ,0
Exp/Cntr=0.3,0.1

Type RM Length L Ch R = 1 ,6629    ,538,538,538
BEGIN DESCRIPTION:
Mapping XS cb2cf596
END DESCRIPTION:
XS GIS Cut Line= 3
       2499662.5     13572776.43      2500037.47     13572429.24
      2500440.14     13571512.82
#Sta/Elev= 30
  4429.4  205.36  4453.4  206.19  4565.6   200.5  4658.7  191.69  4779.6  184.72
  4847.1  182.58  4863.9  181.69  4892.2   183.2  4899.1  180.11  4906.4  180.52
  4913.2   178.2  4917.2  179.55  4934.8  181.09  4939.9  176.32  4943.6  176.32
  4966.5   166.1    4972  167.24  4973.2  164.99  4973.7  164.49  4982.5  164.99
  5000.8  166.63  5010.6  171.91  5018.7  173.02  5082.6  177.48  5169.7  182.67
  5547.3  185.85  5692.9   190.9  5791.7  198.54  5867.3  200.83  5941.4  206.08
#Mann= 8 ,-1 , 0
  4429.4     .03       0  4565.6     .05       0  4779.6     .03       0
  4847.1     .04       0  4917.2      .1       0  4973.2     .05       0
  4982.5      .1       0  5082.6     .04       0
Bank Sta=4973.2,4982.5
XS Rating Curve= 0 ,0
Exp/Cntr=0.3,0.1

Type RM Length L Ch R = 1 ,6091    ,695,695,695
BEGIN DESCRIPTION:
Mapping XS 2a6400a2
END DESCRIPTION:
XS GIS Cut Line= 3
      2500218.05     13572970.87      2500579.13     13572429.24
      2500745.62     13571569.06
#Sta/Elev= 30
    4336  200.02  4416.4  199.08  4425.4  196.87  4449.9   195.3  4547.4  192.11
  4590.7   188.1  4734.9  181.78    4828  179.12  4843.1  176.13  4853.6  176.17
  4900.1  172.22  4915.2  176.92  4930.2  178.89  4951.2  176.87  4966.2  173.37
  4972.3  174.01    4980  169.58  4986.5  162.64  4996.8  162.27  4997.3  161.77
  5006.2  162.27  5040.6  170.38    5069  170.89  5082.9  175.63  5123.7  178.74
  5361.5  178.33  5625.4  187.08    5729  192.65  5795.9  200.73  5863.1   206.2
#Mann= 6 ,-1 , 0
    4336     .04       0  4449.9     .12       0  4853.6      .1       0
  4996.8     .05       0  5006.2      .1       0    5069     .12       0
Bank Sta=4996.8,5006.2
XS Rating Curve= 0 ,0
Exp/Cntr=0.3,0.1

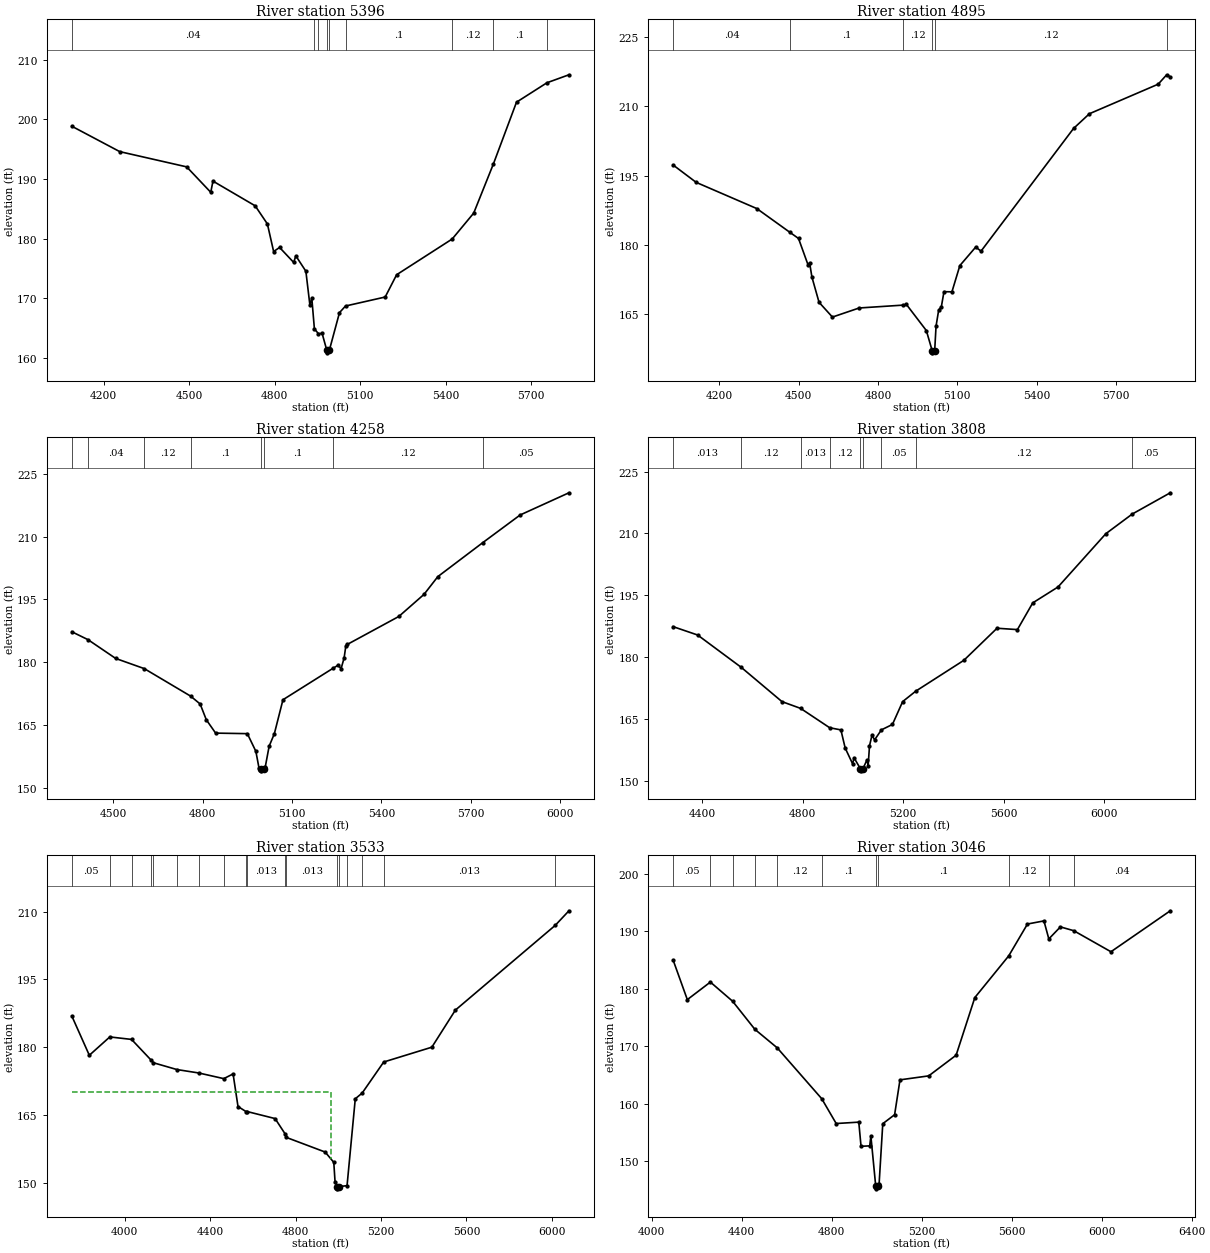
Type RM Length L Ch R = 1 ,5396    ,501,501,501
BEGIN DESCRIPTION:
Mapping XS 821b226a
END DESCRIPTION:
XS GIS Cut Line= 3
       2500634.7     13573172.29      2501231.91     13572477.85
      2501280.52     13571651.49
#Sta/Elev= 30
  4088.8  198.86  4256.8   194.6  4491.6  192.04  4576.1  187.77  4583.8  189.65
  4731.9   185.5  4774.7  182.46  4796.6  177.83  4817.5  178.51  4866.9     176
  4874.5   177.1  4909.7  174.52  4923.9  168.79  4930.5  170.02  4939.6  164.83
  4953.8  164.04  4966.7  164.08  4982.7  161.32  4983.2  160.82  4992.4  161.32
  5027.6  167.57  5048.7  168.68  5187.9  170.19    5228  173.93  5422.9  179.93
  5498.4  184.28  5567.6  192.55  5648.5   202.9  5755.3  206.16  5832.5   207.5
#Mann= 9 ,-1 , 0
  4088.8     .04       0  4939.6     .05       0  4953.8     .12       0
  4982.7     .05       0  4992.4     .12       0  5048.7      .1       0
  5422.9     .12       0  5567.6      .1       0  5755.3     .12       0
Bank Sta=4982.7,4992.4
XS Rating Curve= 0 ,0
Exp/Cntr=0.3,0.1

Type RM Length L Ch R = 1 ,4895    ,637,637,637
BEGIN DESCRIPTION:
Mapping XS 2e7ce691
END DESCRIPTION:
XS GIS Cut Line= 3
       2501106.9     13573276.49      2501655.52     13572491.74
      2501662.46     13571569.07
#Sta/Elev= 30
  4025.5  197.29  4112.4  193.54  4341.8  187.86  4467.7  182.68  4499.6  181.38
  4535.4  175.69  4541.5  176.13  4550.2  173.03  4577.2  167.55  4627.8  164.35
    4729  166.32  4895.2  166.94  4907.7  167.08    4983  161.43  5004.9   157.1
  5005.4   156.6  5014.6   157.1  5019.7  162.37  5029.7  165.88  5039.7  166.56
  5049.7  169.85  5079.8  169.82  5109.8  175.51  5169.8  179.52  5189.8  178.63
  5539.8  205.22  5599.8  208.41  5859.8  214.81    5892  216.85  5905.7  216.38
#Mann= 6 ,-1 , 0
  4025.5     .04       0  4467.7      .1       0  4895.2     .12       0
  5004.9     .05       0  5014.6     .12       0    5892     .05       0
Bank Sta=5004.9,5014.6
XS Rating Curve= 0 ,0
Exp/Cntr=0.3,0.1

Type RM Length L Ch R = 1 ,4258    ,450,450,450
BEGIN DESCRIPTION:
Mapping XS c1d83d87
END DESCRIPTION:
XS GIS Cut Line= 3
      2501988.85     13573429.26      2502169.41      13572797.3
      2502363.86      13571804.2
#Sta/Elev= 30
  4360.3   187.3  4414.5  185.42  4507.6  180.94  4603.5  178.52  4759.2  171.96
  4791.1  170.09  4811.9  166.32  4843.1  163.15  4949.6  163.02  4978.2  158.81
  4988.7  154.85  4994.2  154.66  4994.7  154.16  5004.1  154.66  5009.5  154.99
  5022.8  160.03  5040.3  163.01  5069.2   171.1  5236.6  178.57  5254.3  179.33
  5264.4  178.51  5274.6  181.09  5280.3  183.92  5285.4  184.29  5458.1  190.94
  5542.8  196.21  5589.2  200.44  5740.7  208.57  5865.6  215.13  6029.5  220.42
#Mann= 8 ,-1 , 0
  4360.3     .05       0  4414.5     .04       0  4603.5     .12       0
  4759.2      .1       0  4994.2     .05       0  5004.1      .1       0
  5236.6     .12       0  5740.7     .05       0
Bank Sta=4994.2,5004.1
XS Rating Curve= 0 ,0
Exp/Cntr=0.3,0.1

Type RM Length L Ch R = 1 ,3808    ,275,275,275
BEGIN DESCRIPTION:
Mapping XS 50713ed3
END DESCRIPTION:
XS GIS Cut Line= 4
       2502808.3     13573720.91      2502502.75     13573026.47
      2502384.69     13572325.08      2502405.49     13571819.06
#Sta/Elev= 30
  4285.3  187.42  4382.5   185.4    4556  177.56  4717.8  169.26    4792  167.62
  4907.5  162.93  4952.1  162.41  4969.1  158.02  4998.8  154.17  5004.3  155.67
  5029.7  152.99  5030.2  152.49  5039.7  152.99  5055.5  155.12  5060.6  153.78
  5065.8  158.55  5075.9  161.15    5086  159.99  5113.2  162.42    5157  163.73
  5197.6  169.26  5249.6  171.79    5441  179.27  5572.8  187.04  5653.9  186.71
  5714.8  193.18  5815.4  197.04  6005.5  209.95  6110.5  214.71  6261.7  219.86
#Mann= 9 ,-1 , 0
  4285.3    .013       0    4556     .12       0    4792    .013       0
  4907.5     .12       0  5029.7     .05       0  5039.7     .12       0
  5113.2     .05       0  5249.6     .12       0  6110.5     .05       0
Bank Sta=5029.7,5039.7
XS Rating Curve= 0 ,0
Exp/Cntr=0.3,0.1

Type RM Length L Ch R = 1 ,3533    ,487,487,487
BEGIN DESCRIPTION:
Mapping XS 4b5bc419
END DESCRIPTION:
XS GIS Cut Line= 5
      2503211.08     13574234.78      2503127.75     13573873.69
      2502766.63     13573082.02      2502662.47     13572533.41
      2502634.69     13572005.67
#Sta/Elev= 30
  3752.2  186.89  3834.1  178.21    3930  182.27  4031.8  181.72  4123.5  177.13
  4134.4  176.55  4244.2  175.05  4346.7  174.29  4463.6  173.04  4507.2  174.08
  4530.2  166.87  4569.8  165.69  4572.8  165.76  4703.9   164.2  4751.6  160.75
  4757.1  160.02  4938.4  156.79  4978.7  154.51  4984.5  150.27    4995  149.15
  4995.5  148.65  5005.1  149.15  5040.8  149.36  5079.3  168.58  5111.6  169.85
  5212.4  176.72  5437.8     180    5548  188.21  6015.2  206.95  6079.8  210.19
#Mann= 18 ,-1 , 0
  3752.2     .05       0    3930    .075       0  4031.8     .05       0
  4123.5    .075       0  4134.4     .05       0  4244.2    .013       0
  4346.7     .05       0  4463.6    .013       0  4569.8     .05       0
  4572.8    .013       0  4751.6    .075       0  4757.1    .013       0
    4995     .03       0  5005.1    .013       0  5040.8    .075       0
  5111.6     .05       0  5212.4    .013       0  6015.2     .05       0
#XS Ineff= 2 , 0
       0    4965     170               0
Permanent Ineff=
       F       F
Bank Sta=4995,5005.1
XS Rating Curve= 0 ,0
Exp/Cntr=0.3,0.1

Type RM Length L Ch R = 1 ,3046    ,292,292,292
BEGIN DESCRIPTION:
Mapping XS ef5e12df
END DESCRIPTION:
XS GIS Cut Line= 4
      2503218.02     13574227.85      2503204.13     13573901.47
      2503155.52      13573297.3      2503502.48     13572069.07
#Sta/Elev= 30
  4095.7  184.94  4158.6  178.09    4261  181.14  4359.8  177.81  4458.7  172.93
  4557.8  169.72  4755.9  160.87  4820.1  156.56  4920.5   156.8  4930.5   152.6
  4969.1  152.68  4974.2  154.39  4995.7  145.71  4996.2  145.21  5005.8  145.71
  5010.7     146  5027.1  156.53  5079.7  158.09  5103.6  164.15  5231.2  164.84
    5353  168.43  5436.2  178.45  5586.9   185.7  5670.1  191.23  5743.3  191.77
    5765  188.64  5816.4  190.73  5875.7  190.07  6041.1  186.41  6304.8  193.53
#Mann= 11 ,-1 , 0
  4095.7     .05       0    4261    .075       0  4359.8     .05       0
  4458.7    .013       0  4557.8     .12       0  4755.9      .1       0
  4995.7     .05       0  5005.8      .1       0  5586.9     .12       0
    5765    .013       0  5875.7     .04       0
Bank Sta=4995.7,5005.8
XS Rating Curve= 0 ,0
Exp/Cntr=0.3,0.1

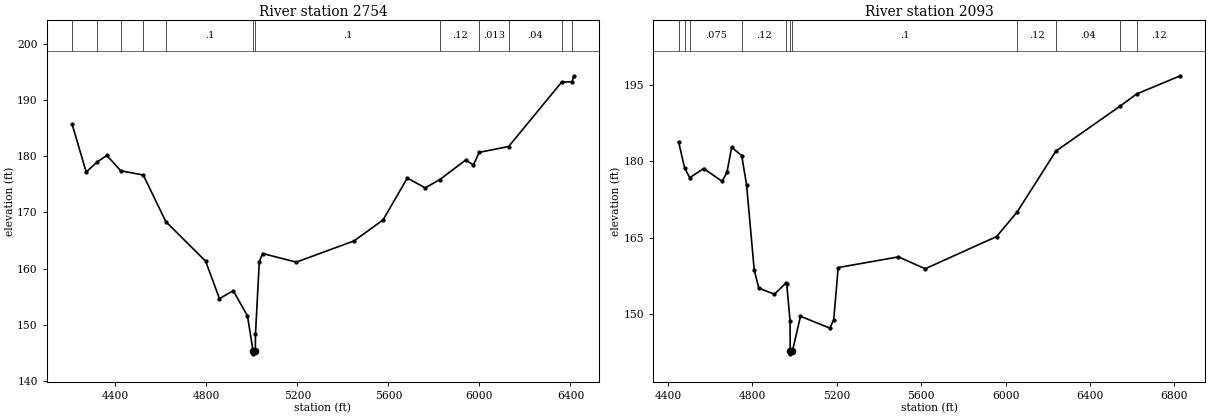
Type RM Length L Ch R = 1 ,2754    ,661,661,661
BEGIN DESCRIPTION:
Mapping XS 39023bc0
END DESCRIPTION:
XS GIS Cut Line= 3
      2503252.74      13574276.5      2503356.91     13573533.41
      2504002.21     13572228.95
#Sta/Elev= 30
  4209.1  185.78  4271.2  177.21  4320.8  179.07  4362.1  180.17    4423  177.44
  4522.1  176.68  4621.2  168.37  4796.3   161.3  4856.9  154.63  4917.5  156.04
    4980  151.57  5004.7  145.28  5005.2  144.78  5014.8  145.28  5015.3  148.24
  5032.1  161.22  5046.9  162.68  5194.7  161.14  5448.6  164.93  5576.1  168.67
  5682.7  176.15  5761.2  174.39  5825.3  175.87  5940.6  179.39  5972.9  178.45
    5999  180.73  6128.2  181.77  6361.3  193.27  6406.7  193.32  6414.8  194.39
#Mann= 12 ,-1 , 0
  4209.1     .05       0  4320.8    .075       0    4423     .05       0
  4522.1    .013       0  4621.2      .1       0  5004.7     .05       0
  5014.8      .1       0  5825.3     .12       0    5999    .013       0
  6128.2     .04       0  6361.3    .013       0  6406.7     .04       0
Bank Sta=5004.7,5014.8
XS Rating Curve= 0 ,0
Exp/Cntr=0.3,0.1

Type RM Length L Ch R = 1 ,2093    ,0,0,0
BEGIN DESCRIPTION:
Mapping XS 1975de2d
END DESCRIPTION:
XS GIS Cut Line= 4
      2503287.46     13574290.36      2503898.58     13573929.24
      2504301.36     13572755.63      2504356.91     13572332.01
#Sta/Elev= 30
  4450.3  183.91  4479.7  178.62  4503.6   176.8  4569.2  178.61  4656.5   176.1
  4679.8  177.85  4701.9   182.8  4749.6  181.16  4772.7  175.39  4809.1  158.58
  4830.8  155.05  4904.7  153.84  4957.6  155.99  4963.2  155.78  4978.8  148.54
  4979.6   142.6  4980.1   142.1  4989.8   142.6  5028.2   149.5  5167.2  147.17
  5185.8  148.82  5206.9   159.1  5492.4   161.2  5619.2  158.86  5957.6  165.21
  6054.7  170.03  6238.3  182.03    6542  190.88  6621.8  193.31  6828.2  196.88
#Mann= 11 ,-1 , 0
  4450.3     .05       0  4479.7    .013       0  4503.6    .075       0
  4749.6     .12       0  4957.6      .1       0  4979.6     .05       0
  4989.8      .1       0  6054.7     .12       0  6238.3     .04       0
    6542    .013       0  6621.8     .12       0
Bank Sta=4979.6,4989.8
XS Rating Curve= 0 ,0
Exp/Cntr=0.3,0.1

Chan Stop Cuts=-1
Use User Specified Reach Order=0
Composite Channel Slope=5