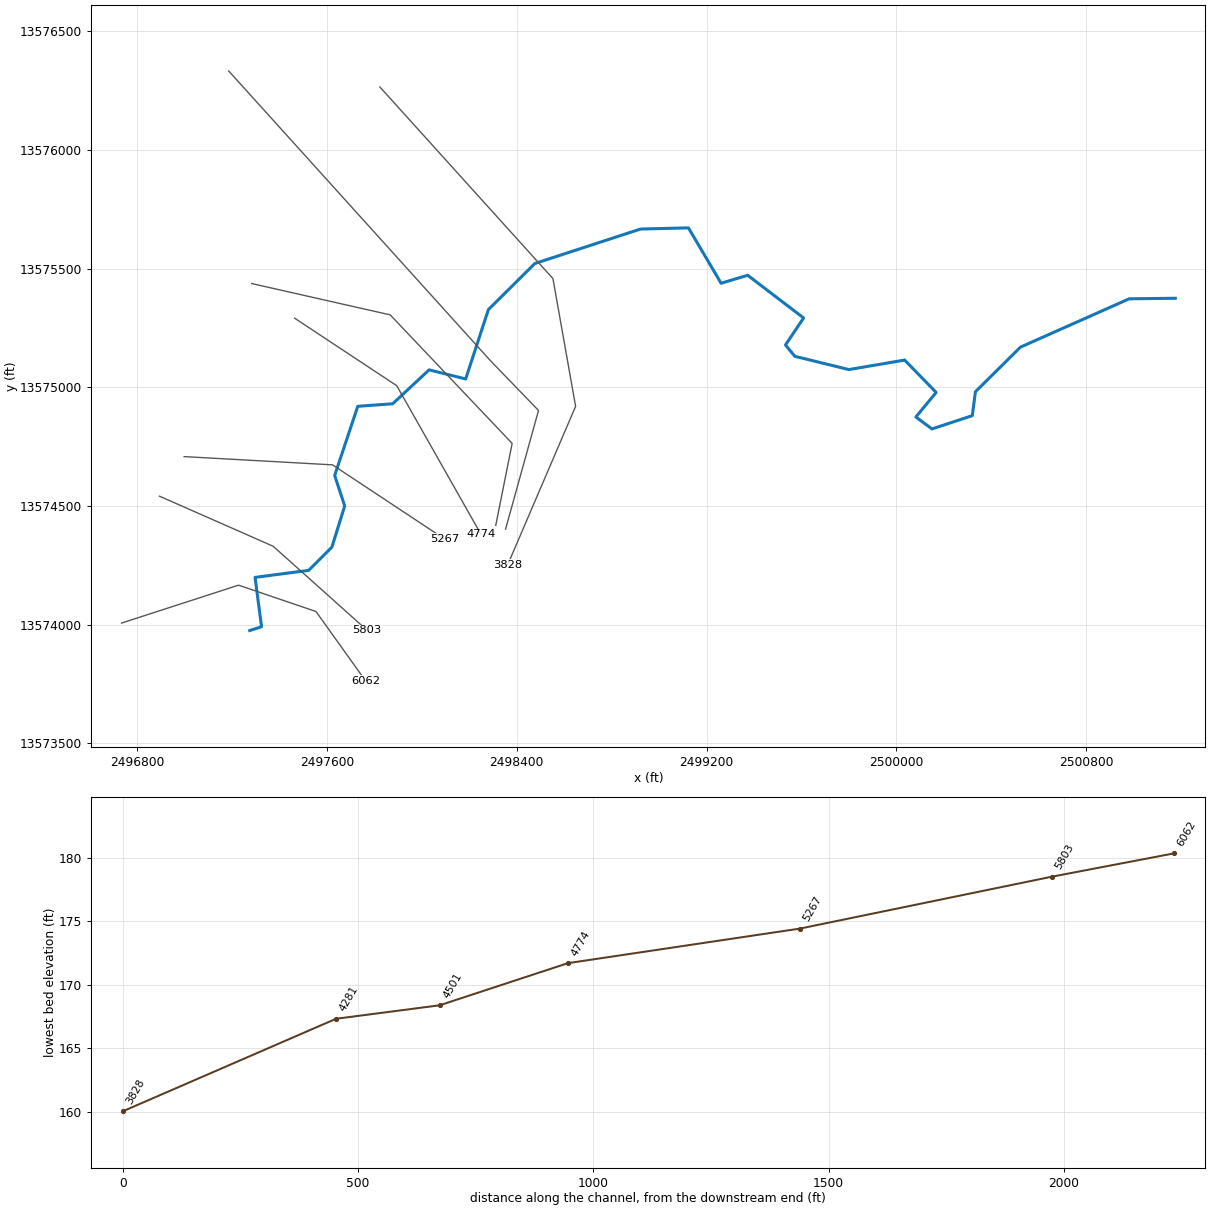
--- TRIB 23 TO GUADALUPE RIVER.prj (project) ---

Proj Title=TRIB 23 TO GUADALUPE RIVER Base Level Engineering
Current Plan=p01
Default Exp/Contr=0.3,0.1
English Units
Geom File=g01
Flow File=f01
Plan File=p01
BEGIN DESCRIPTION:
TRIB 23 TO GUADALUPE RIVER
END DESCRIPTION:

--- TRIB 23 TO GUADALUPE RIVER.p01 (plan) ---

Plan Title=Multiple Run
Short Identifier=Multiple
Geom File=g01
Flow File=f01
Subcritical Flow
K Sum by GR= 0
Std Step Tol= 0.01
Critical Tol= 0.01
Num of Std Step Trials= 20
Max Error Tol= 0.3
Flow Tol Ratio= 0.001
Split Flow NTrial= 30
Split Flow Tol= 0.02
Split Flow Ratio= 0.02
Log Output Level= 0
Friction Slope Method= 1
Unsteady Friction Slope Method= 2
Unsteady Bridges Friction Slope Method= 1
Parabolic Critical Depth
Global Vel Dist=  1 , 1 , 1
Global Log Level= 0
CheckData=True
Encroach Param= -1, 0, 0, 0
BEGIN DESCRIPTION:
Multiple Run
END DESCRIPTION:

--- TRIB 23 TO GUADALUPE RIVER.f01 (steady flow) ---

Flow Title=Multiple
Number of Profiles=7
Profile Names=10-year,25-year,50-year,1pct_min,100-year,1pct_plu,500-year
River Rch & RM= TRIB 23 TO GUADA,Reach-1,6062
     599     976    1320     867    1730    3451    2939
Boundary for River Rch & Prof#=TRIB 23 TO GUADA,Reach-1,1
Up Type=0
Dn Type=3
Dn Slope=0.005
Boundary for River Rch & Prof#=TRIB 23 TO GUADA,Reach-1,2
Up Type=0
Dn Type=3
Dn Slope=0.005
Boundary for River Rch & Prof#=TRIB 23 TO GUADA,Reach-1,3
Up Type=0
Dn Type=3
Dn Slope=0.005
Boundary for River Rch & Prof#=TRIB 23 TO GUADA,Reach-1,4
Up Type=0
Dn Type=3
Dn Slope=0.005
Boundary for River Rch & Prof#=TRIB 23 TO GUADA,Reach-1,5
Up Type=0
Dn Type=3
Dn Slope=0.005
Boundary for River Rch & Prof#=TRIB 23 TO GUADA,Reach-1,6
Up Type=0
Dn Type=3
Dn Slope=0.005
Boundary for River Rch & Prof#=TRIB 23 TO GUADA,Reach-1,7
Up Type=0
Dn Type=3
Dn Slope=0.005

--- TRIB 23 TO GUADALUPE RIVER.g01 (geometry) ---

Geom Title=Existing Conditions

River Reach=TRIB 23 TO GUADA,Reach-1
Reach XY= 30
      2497275.00     13573975.00      2497325.09     13573990.91
      2497297.63     13574199.02      2497523.55     13574228.53
      2497621.39     13574326.48      2497675.39     13574500.00
      2497633.08     13574628.30      2497730.41     13574919.82
      2497877.44     13574930.47      2498031.04     13575073.38
      2498185.06     13575035.03      2498280.83     13575327.30
      2498476.46     13575521.46      2498921.78     13575666.72
      2499123.72     13575671.63      2499261.27     13575438.40
      2499373.35     13575471.84      2499608.96     13575292.04
      2499532.53     13575178.13      2499571.98     13575130.47
      2499800.00     13575074.60      2500034.79     13575114.57
      2500167.39     13574978.33      2500081.99     13574874.75
      2500149.77     13574824.50      2500319.75     13574880.44
      2500332.88     13574981.12      2500522.70     13575169.17
      2500980.92     13575372.77      2501175.00     13575375.00

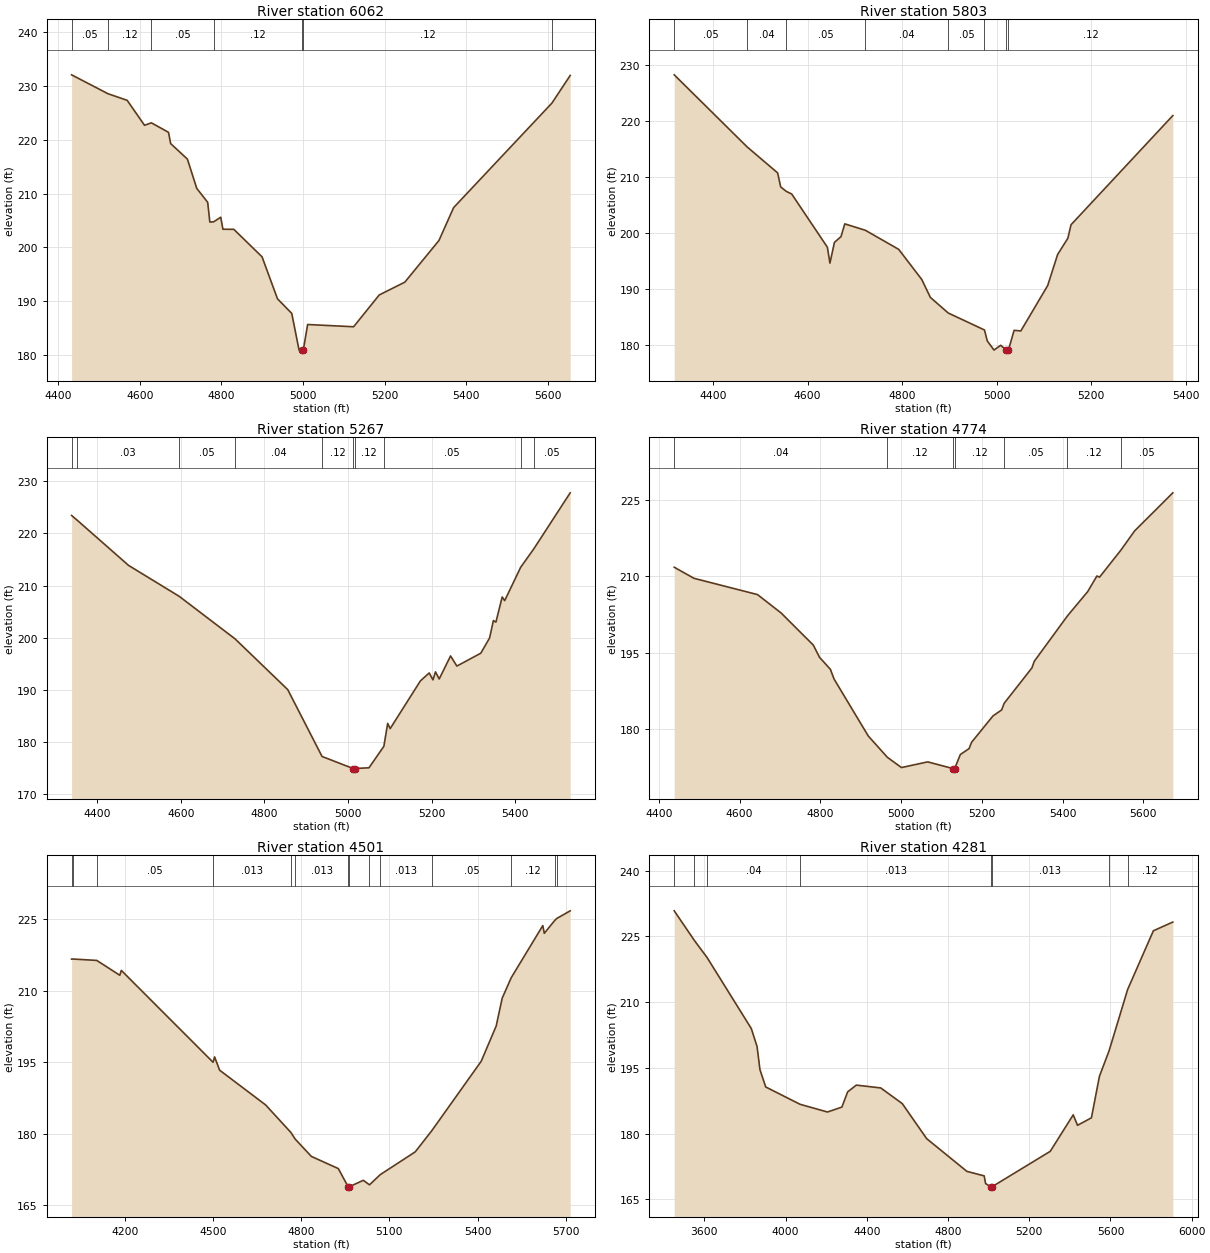
Type RM Length L Ch R = 1,6062,259,259,259
BEGIN DESCRIPTION:
Mapping XS 53098cb0
END DESCRIPTION:
XS GIS Cut Line= 4
      2496735.12     13574006.50      2497228.13     13574166.21
      2497554.52     13574055.10      2497762.88     13573763.39
#Sta/Elev= 30
  4432.8  232.08  4521.9  228.57  4569.0  227.34  4611.5  222.70  4628.2  223.16
  4670.2  221.40  4675.5  219.30  4716.5  216.42  4739.5  210.97  4766.2  208.39
  4771.5  204.73  4780.5  204.75  4798.2  205.62  4803.5  203.38  4830.2  203.37
  4899.4  198.26  4937.2  190.46  4972.2  187.74  4990.0  180.96  4996.3  180.86
  4996.5  180.36  5000.3  180.86  5011.1  185.68  5123.7  185.26  5186.5  191.17
  5249.2  193.55  5332.8  201.29  5368.8  207.41  5609.7  226.84  5654.3  231.96
#Mann=7,-1,0
  4432.8    0.05       0  4521.9    0.12       0  4628.2    0.05       0
  4780.5    0.12       0  4996.3    0.05       0  5000.3    0.12       0
  5609.7    0.05       0
Bank Sta=4996.3,5000.3
Exp/Cntr=0.3,0.1

Type RM Length L Ch R = 1,5803,536,536,536
BEGIN DESCRIPTION:
Mapping XS 2fe7a518
END DESCRIPTION:
XS GIS Cut Line= 3
      2496894.75     13574541.23      2497374.10     13574330.04
      2497769.97     13573975.85
#Sta/Elev= 30
  4318.0  228.31  4472.1  215.43  4536.8  210.77  4543.3  208.26  4555.0  207.47
  4566.6  206.99  4642.1  197.47  4647.5  194.63  4657.0  198.34  4670.9  199.37
  4678.9  201.65  4722.6  200.50  4793.0  197.09  4841.8  191.70  4860.0  188.50
  4897.7  185.71  4974.5  182.67  4980.4  180.72  4994.6  179.08  5008.8  179.93
  5021.0  179.03  5021.2  178.53  5025.0  179.03  5037.2  182.61  5051.4  182.50
  5108.2  190.61  5129.2  196.16  5150.9  199.08  5157.6  201.49  5373.0  221.02
#Mann=8,-1,0
  4318.0    0.05       0  4472.1    0.04       0  4555.0    0.05       0
  4722.6    0.04       0  4897.7    0.05       0  4974.5    0.12       0
  5021.0    0.05       0  5025.0    0.12       0
Bank Sta=5021,5025
Exp/Cntr=0.3,0.1

Type RM Length L Ch R = 1,5267,493,493,493
BEGIN DESCRIPTION:
Mapping XS 82392d92
END DESCRIPTION:
XS GIS Cut Line= 3
      2496998.96     13574707.87      2497623.96     13574673.15
      2498096.16     13574360.67
#Sta/Elev= 30
  4338.8  223.45  4350.9  222.63  4475.0  213.88  4596.1  207.95  4729.6  199.80
  4855.6  190.07  4937.7  177.25  5012.0  174.94  5012.2  174.44  5016.0  174.94
  5049.9  175.08  5085.5  179.20  5094.6  183.59  5100.6  182.59  5172.8  191.73
  5193.9  193.26  5202.9  191.94  5208.9  193.47  5217.8  192.11  5245.0  196.52
  5260.1  194.58  5317.3  197.05  5338.3  199.97  5347.4  203.31  5353.4  203.00
  5368.4  207.83  5374.4  207.12  5412.5  213.50  5444.3  217.08  5531.0  227.79
#Mann=10,-1,0
  4338.8    0.05       0  4350.9    0.03       0  4596.1    0.05       0
  4729.6    0.04       0  4937.7    0.12       0  5012.0    0.05       0
  5016.0    0.12       0  5085.5    0.05       0  5412.5    0.12       0
  5444.3    0.05       0
Bank Sta=5012,5016
Exp/Cntr=0.3,0.1

Type RM Length L Ch R = 1,4774,273,273,273
BEGIN DESCRIPTION:
Mapping XS 578b2901
END DESCRIPTION:
XS GIS Cut Line= 3
      2497464.24     13575291.21      2497894.80     13575006.49
      2498248.98     13574381.45
#Sta/Elev= 30
  4438.2  211.82  4487.1  209.64  4644.4  206.44  4702.9  202.82  4782.8  196.49
  4797.9  194.11  4824.9  191.74  4834.0  189.83  4918.7  178.63  4966.1  174.43
  5000.9  172.42  5065.8  173.54  5128.7  172.22  5129.0  171.72  5132.7  172.22
  5146.6  174.98  5168.3  176.15  5174.5  177.39  5227.4  182.57  5249.0  183.76
  5255.1  185.05  5323.9  192.02  5329.8  193.33  5412.0  202.26  5461.8  207.00
  5484.8  210.09  5491.4  209.87  5544.5  215.21  5578.0  218.94  5672.8  226.45
#Mann=7,-1,0
  4438.2    0.04       0  4966.1    0.12       0  5128.7    0.05       0
  5132.7    0.12       0  5255.1    0.05       0  5412.0    0.12       0
  5544.5    0.05       0
Bank Sta=5128.7,5132.7
Exp/Cntr=0.3,0.1

Type RM Length L Ch R = 1,4501,220,220,220
BEGIN DESCRIPTION:
Mapping XS d6b05cf1
END DESCRIPTION:
XS GIS Cut Line= 4
      2497283.69     13575437.04      2497867.02     13575305.10
      2498380.91     13574763.43      2498311.84     13574418.08
#Sta/Elev= 30
  4018.4  216.59  4022.7  216.61  4104.0  216.32  4182.5  213.21  4187.6  214.23
  4499.9  194.98  4505.2  196.10  4522.1  193.33  4678.8  186.04  4764.8  180.27
  4779.3  178.89  4834.5  175.25  4926.3  172.70  4959.5  168.90  4959.8  168.40
  4963.5  168.90  5011.3  170.25  5032.2  169.30  5069.0  171.44  5188.0  176.21
  5244.0  180.62  5412.5  195.19  5463.5  202.58  5483.9  208.41  5514.6  212.69
  5622.1  223.62  5627.2  222.00  5662.9  224.71  5670.2  225.13  5715.3  226.71
#Mann=14,-1,0
  4018.4    0.05       0  4022.7    0.04       0  4104.0    0.05       0
  4499.9   0.013       0  4764.8    0.04       0  4779.3   0.013       0
  4959.5    0.03       0  4963.5   0.013       0  5032.2    0.04       0
  5069.0   0.013       0  5244.0    0.05       0  5514.6    0.12       0
  5662.9    0.05       0  5670.2    0.12       0
Bank Sta=4959.5,4963.5
Exp/Cntr=0.3,0.1

Type RM Length L Ch R = 1,4281,453,453,453
BEGIN DESCRIPTION:
Mapping XS f7bf386e
END DESCRIPTION:
XS GIS Cut Line= 4
      2497186.49     13576332.84      2498290.63     13575110.65
      2498492.02     13574902.32      2498353.12     13574402.29
#Sta/Elev= 30
  3451.4  230.81  3550.8  224.05  3613.1  220.17  3831.1  203.96  3859.5  199.85
  3873.7  194.59  3902.0  190.64  4071.6  186.68  4206.2  184.93  4277.2  186.05
  4305.6  189.52  4348.2  191.06  4468.5  190.42  4574.6  186.85  4694.9  178.85
  4892.9  171.39  4978.1  170.36  4984.9  168.62  5011.3  167.84  5011.5  167.34
  5015.3  167.84  5303.5  175.96  5416.6  184.28  5437.8  181.90  5506.3  183.60
  5545.8  193.08  5593.3  198.89  5684.7  212.87  5811.5  226.26  5907.2  228.25
#Mann=8,-1,0
  3451.4    0.04       0  3550.8   0.013       0  3613.1    0.04       0
  4071.6   0.013       0  5011.3    0.03       0  5015.3   0.013       0
  5593.3    0.05       0  5684.7    0.12       0
Bank Sta=5011.3,5015.3
Exp/Cntr=0.3,0.1

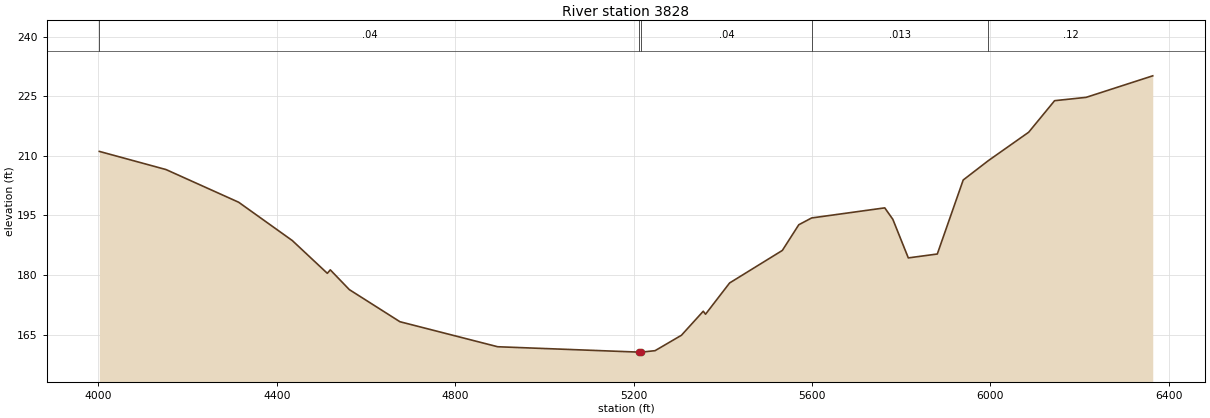
Type RM Length L Ch R = 1,3828,0,0,0
BEGIN DESCRIPTION:
Mapping XS a5e2b17b
END DESCRIPTION:
XS GIS Cut Line= 4
      2497823.65     13576265.13      2498552.78     13575457.87
      2498648.27     13574919.68      2498361.81     13574251.27
#Sta/Elev= 30
  4002.4  211.11  4151.8  206.54  4314.7  198.31  4435.1  188.65  4513.5  180.41
  4520.2  181.28  4562.8  176.31  4676.3  168.22  4895.4  161.92  5213.0  160.56
  5213.2  160.06  5217.0  160.56  5248.3  160.93  5307.4  164.81  5356.3  170.86
  5361.4  170.11  5415.4  177.98  5533.6  186.17  5570.5  192.64  5599.3  194.35
  5763.2  196.89  5781.3  194.01  5816.0  184.29  5881.0  185.27  5939.1  203.91
  5995.4  208.78  6085.9  215.94  6144.0  223.88  6214.7  224.72  6364.0  230.14
#Mann=5,-1,0
  4002.4    0.04       0  5213.0    0.04       0  5217.0    0.04       0
  5599.3   0.013       0  5995.4    0.12       0
Bank Sta=5213,5217
Exp/Cntr=0.3,0.1

Chan Stop Cuts=-1