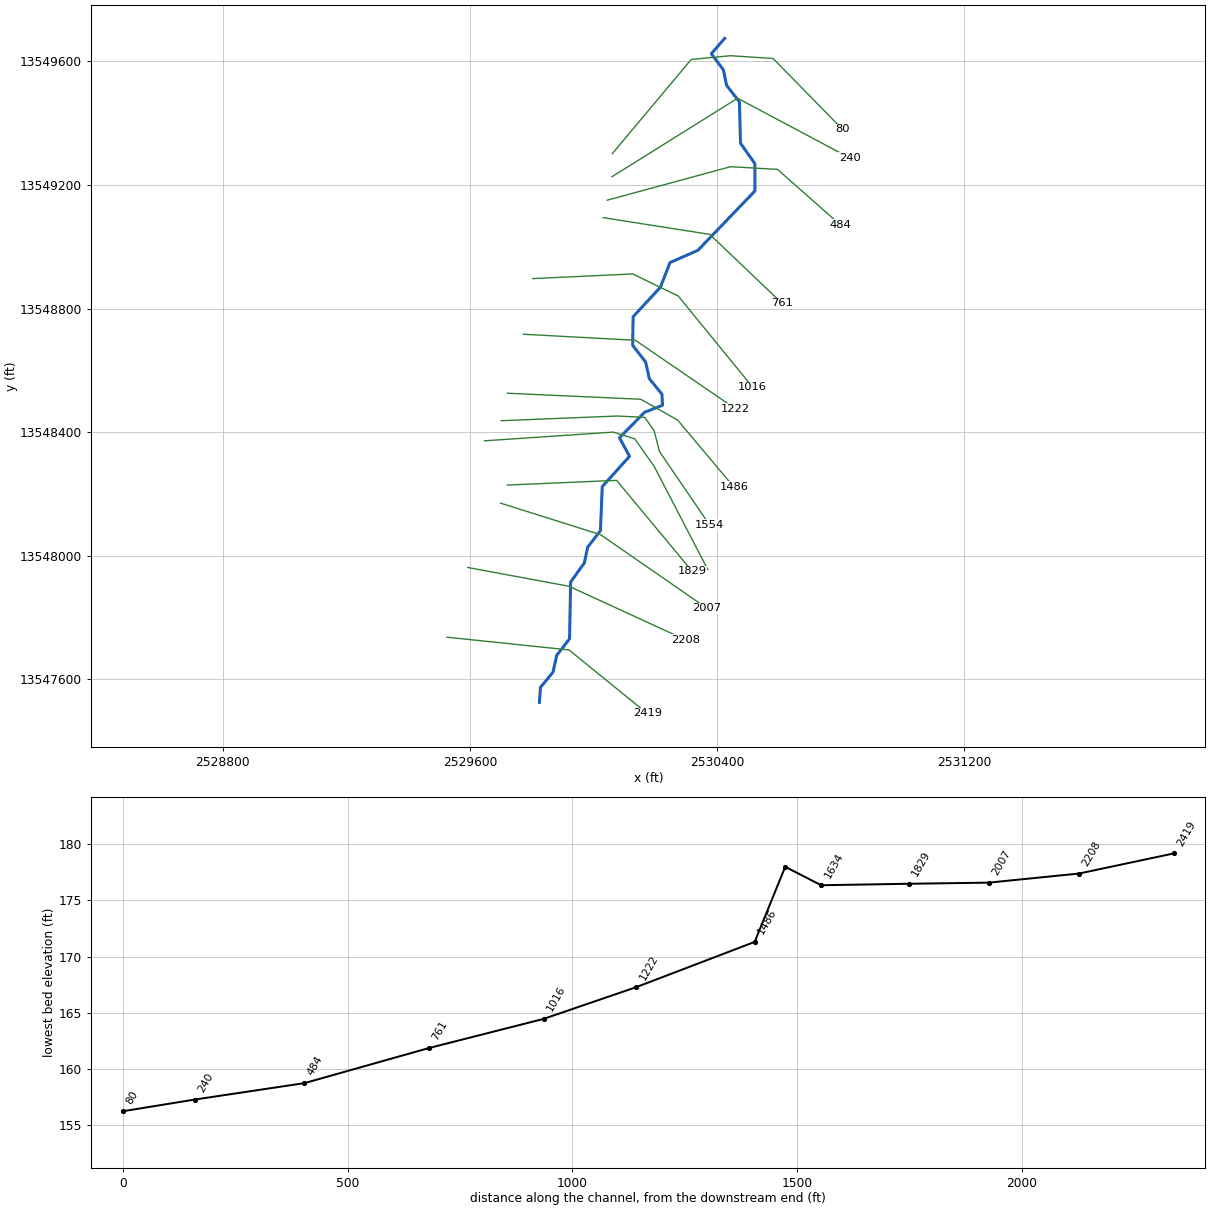
--- TRIB 3 TO CARLISLE CREEK.prj (project) ---

Proj Title=TRIB 3 TO CARLISLE CREEK Base Level Engineering
Current Plan=p01
Default Exp/Contr=0.3,0.1
English Units
Geom File=g01
Flow File=f01
Plan File=p01
BEGIN DESCRIPTION:
TRIB 3 TO CARLISLE CREEK
END DESCRIPTION:

--- TRIB 3 TO CARLISLE CREEK.p01 (plan) ---

Plan Title=Multiple Run
Short Identifier=Multiple
Geom File=g01
Flow File=f01
Subcritical Flow
K Sum by GR= 0
Std Step Tol= 0.01
Critical Tol= 0.01
Num of Std Step Trials= 20
Max Error Tol= 0.3
Flow Tol Ratio= 0.001
Split Flow NTrial= 30
Split Flow Tol= 0.02
Split Flow Ratio= 0.02
Log Output Level= 0
Friction Slope Method= 1
Unsteady Friction Slope Method= 2
Unsteady Bridges Friction Slope Method= 1
Parabolic Critical Depth
Global Vel Dist=  1 , 1 , 1
Global Log Level= 0
CheckData=True
Encroach Param= -1, 0, 0, 0
BEGIN DESCRIPTION:
Multiple Run
END DESCRIPTION:

--- TRIB 3 TO CARLISLE CREEK.f01 (steady flow) ---

Flow Title=Multiple
Number of Profiles=7
Profile Names=10-year,25-year,50-year,1pct_min,100-year,1pct_plu,500-year
River Rch & RM= TRIB 3 TO CARLIS,Reach-1,2419
     382     596     785     502    1002    1999    1610
Boundary for River Rch & Prof#=TRIB 3 TO CARLIS,Reach-1,1
Up Type=0
Dn Type=3
Dn Slope=0.005
Boundary for River Rch & Prof#=TRIB 3 TO CARLIS,Reach-1,2
Up Type=0
Dn Type=3
Dn Slope=0.005
Boundary for River Rch & Prof#=TRIB 3 TO CARLIS,Reach-1,3
Up Type=0
Dn Type=3
Dn Slope=0.005
Boundary for River Rch & Prof#=TRIB 3 TO CARLIS,Reach-1,4
Up Type=0
Dn Type=3
Dn Slope=0.005
Boundary for River Rch & Prof#=TRIB 3 TO CARLIS,Reach-1,5
Up Type=0
Dn Type=3
Dn Slope=0.005
Boundary for River Rch & Prof#=TRIB 3 TO CARLIS,Reach-1,6
Up Type=0
Dn Type=3
Dn Slope=0.005
Boundary for River Rch & Prof#=TRIB 3 TO CARLIS,Reach-1,7
Up Type=0
Dn Type=3
Dn Slope=0.005

--- TRIB 3 TO CARLISLE CREEK.g01 (geometry) ---

Geom Title=Existing Conditions

River Reach=TRIB 3 TO CARLIS,Reach-1
Reach XY= 30
      2529825.00     13547525.00      2529828.60     13547573.51
      2529869.05     13547622.75      2529881.11     13547677.18
      2529922.76     13547730.93      2529926.20     13547914.50
      2529970.81     13547976.74      2529981.12     13548027.18
      2530022.75     13548080.93      2530028.57     13548223.53
      2530116.98     13548321.67      2530084.30     13548381.68
      2530165.62     13548464.11      2530223.83     13548487.01
      2530221.84     13548522.90      2530181.17     13548572.77
      2530168.88     13548627.18      2530127.14     13548680.97
      2530128.47     13548773.50      2530216.81     13548868.98
      2530247.86     13548948.84      2530338.20     13548988.64
      2530523.04     13549180.89      2530522.84     13549269.02
      2530476.23     13549335.51      2530472.75     13549469.07
      2530431.09     13549522.83      2530420.67     13549573.38
      2530381.87     13549625.12      2530425.00     13549675.00

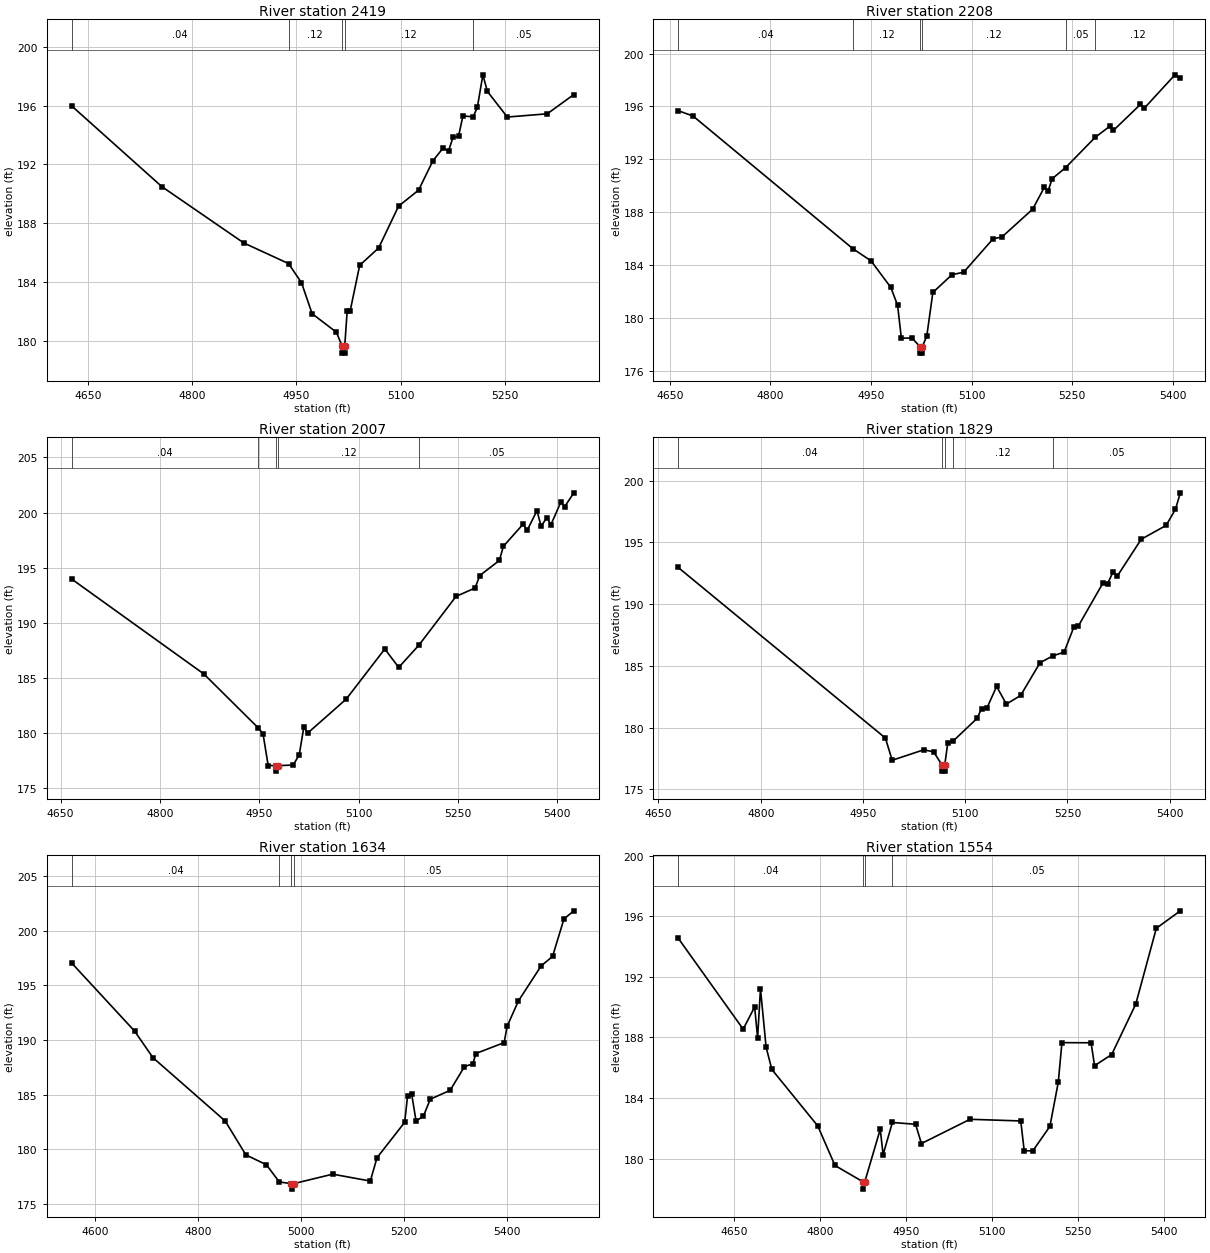
Type RM Length L Ch R = 1,2419,211,211,211
BEGIN DESCRIPTION:
Mapping XS 5c2d4cfa
END DESCRIPTION:
XS GIS Cut Line= 3
      2529525.99     13547735.97      2529920.97     13547694.73
      2530173.95     13547489.31
#Sta/Elev= 30
  4626.5  195.97  4756.2  190.49  4874.2  186.66  4938.6  185.26  4957.3  183.96
  4972.6  181.85  5007.6  180.59  5015.6  179.67  5015.9  179.17  5019.4  179.17
  5019.6  179.67  5023.1  182.04  5027.4  182.04  5041.1  185.14  5068.4  186.32
  5097.1  189.16  5125.9  190.25  5146.7  192.26  5161.1  193.10  5169.0  192.91
  5175.4  193.83  5183.4  193.90  5189.8  195.30  5204.6  195.23  5210.6  195.90
  5218.5  198.09  5225.0  196.96  5253.7  195.22  5311.2  195.44  5349.5  196.75
#Mann=5,-1,0
  4626.5    0.04       0  4938.6    0.12       0  5015.6    0.05       0
  5019.6    0.12       0  5204.6    0.05       0
Bank Sta=5015.6,5019.6
Exp/Cntr=0.3,0.1

Type RM Length L Ch R = 1,2208,201,201,201
BEGIN DESCRIPTION:
Mapping XS c1f6ca8e
END DESCRIPTION:
XS GIS Cut Line= 3
      2529593.24     13547961.67      2529920.97     13547900.90
      2530298.56     13547727.29
#Sta/Elev= 30
  4662.5  195.68  4684.6  195.28  4923.3  185.25  4950.0  184.35  4979.6  182.34
  4989.7  180.99  4995.3  178.51  5011.3  178.52  5022.8  177.88  5023.1  177.38
  5026.6  177.38  5026.8  177.88  5033.3  178.69  5042.3  181.96  5070.8  183.30
  5088.3  183.49  5132.3  186.02  5145.2  186.14  5191.2  188.25  5208.6  189.90
  5214.1  189.62  5220.4  190.55  5240.4  191.39  5284.2  193.66  5306.0  194.50
  5311.5  194.19  5352.0  196.16  5357.5  195.86  5403.4  198.39  5411.4  198.14
#Mann=6,-1,0
  4662.5    0.04       0  4923.3    0.12       0  5022.8    0.05       0
  5026.8    0.12       0  5240.4    0.05       0  5284.2    0.12       0
Bank Sta=5022.8,5026.8
Exp/Cntr=0.3,0.1

Type RM Length L Ch R = 1,2007,178,178,178
BEGIN DESCRIPTION:
Mapping XS 9823b578
END DESCRIPTION:
XS GIS Cut Line= 3
      2529699.66     13548169.98      2530022.96     13548068.00
      2530367.53     13547829.61
#Sta/Elev= 30
  4666.8  193.97  4866.3  185.37  4948.1  180.50  4955.5  179.97  4963.3  177.08
  4974.5  177.07  4974.7  176.57  4978.5  177.07  5000.9  177.12  5010.1  178.02
  5017.1  180.54  5023.2  180.03  5081.2  183.10  5139.4  187.64  5160.4  185.97
  5190.8  187.98  5246.9  192.40  5275.8  193.17  5282.7  194.29  5312.3  195.66
  5318.5  196.95  5348.2  198.95  5354.3  198.39  5369.2  200.18  5375.3  198.75
  5384.1  199.55  5390.1  198.89  5405.0  200.92  5411.1  200.55  5424.8  201.79
#Mann=5,-1,0
  4666.8    0.04       0  4948.1    0.12       0  4974.5    0.05       0
  4978.5    0.12       0  5190.8    0.05       0
Bank Sta=4974.5,4978.5
Exp/Cntr=0.3,0.1

Type RM Length L Ch R = 1,1829,195,195,195
BEGIN DESCRIPTION:
Mapping XS bb334b88
END DESCRIPTION:
XS GIS Cut Line= 3
      2529721.36     13548228.59      2530075.05     13548243.78
      2530319.55     13547949.51
#Sta/Elev= 30
  4679.0  192.97  4982.9  179.15  4992.9  177.35  5039.3  178.20  5053.7  178.03
  5066.0  176.97  5066.2  176.47  5069.7  176.47  5070.0  176.97  5074.5  178.78
  5082.0  178.89  5117.5  180.75  5124.0  181.54  5131.8  181.57  5146.1  183.33
  5160.4  181.90  5181.3  182.60  5209.9  185.26  5229.1  185.82  5245.1  186.11
  5259.4  188.14  5265.9  188.22  5302.4  191.74  5308.9  191.66  5316.7  192.58
  5323.2  192.28  5358.3  195.26  5394.8  196.38  5408.5  197.69  5415.6  199.02
#Mann=5,-1,0
  4679.0    0.04       0  5066.0    0.04       0  5070.0    0.04       0
  5082.0    0.12       0  5229.1    0.05       0
Bank Sta=5066,5070
Exp/Cntr=0.3,0.1

Type RM Length L Ch R = 1,1634,80,80,80
BEGIN DESCRIPTION:
Mapping XS 71bccfca
END DESCRIPTION:
XS GIS Cut Line= 5
      2529647.52     13548371.81      2530064.20     13548400.03
      2530133.64     13548378.33      2530196.57     13548289.35
      2530370.10     13547955.30
#Sta/Elev= 30
  4554.0  197.04  4676.0  190.82  4711.8  188.38  4852.2  182.58  4892.3  179.48
  4932.3  178.57  4957.3  177.00  4981.0  176.84  4981.2  176.34  4985.0  176.84
  5061.1  177.71  5134.2  177.08  5147.3  179.22  5201.0  182.46  5206.6  184.85
  5214.6  185.04  5223.1  182.59  5237.2  183.00  5250.8  184.58  5289.4  185.39
  5317.2  187.56  5333.6  187.82  5339.3  188.76  5394.4  189.76  5400.0  191.24
  5422.1  193.58  5466.3  196.79  5488.4  197.65  5510.6  201.09  5529.8  201.83
#Mann=4,-1,0
  4554.0    0.04       0  4957.3    0.05       0  4981.0    0.05       0
  4985.0    0.05       0
Bank Sta=4981,4985
Exp/Cntr=0.3,0.1

Type RM Length L Ch R = 1,1554,68,68,68
BEGIN DESCRIPTION:
Mapping XS 10f812e7
END DESCRIPTION:
XS GIS Cut Line= 6
      2529701.80     13548436.92      2530077.22     13548452.11
      2530166.19     13548447.77      2530196.57     13548404.37
      2530213.93     13548337.09      2530376.13     13548099.21
#Sta/Elev= 30
  4553.0  194.54  4666.2  188.54  4686.2  190.00  4691.4  187.97  4696.4  191.20
  4706.2  187.35  4716.2  185.88  4796.3  182.15  4826.3  179.54  4874.4  178.48
  4874.7  177.98  4878.4  178.48  4905.2  181.93  4910.2  180.26  4926.4  182.38
  4966.8  182.26  4977.0  180.99  5061.8  182.59  5150.2  182.48  5156.2  180.52
  5171.1  180.50  5201.0  182.12  5215.6  185.03  5222.0  187.65  5272.8  187.64
  5278.9  186.13  5308.7  186.86  5350.7  190.19  5386.6  195.20  5428.4  196.35
#Mann=4,-1,0
  4553.0    0.04       0  4874.4    0.05       0  4878.4    0.04       0
  4926.4    0.05       0
Bank Sta=4874.4,4878.4
Exp/Cntr=0.3,0.1

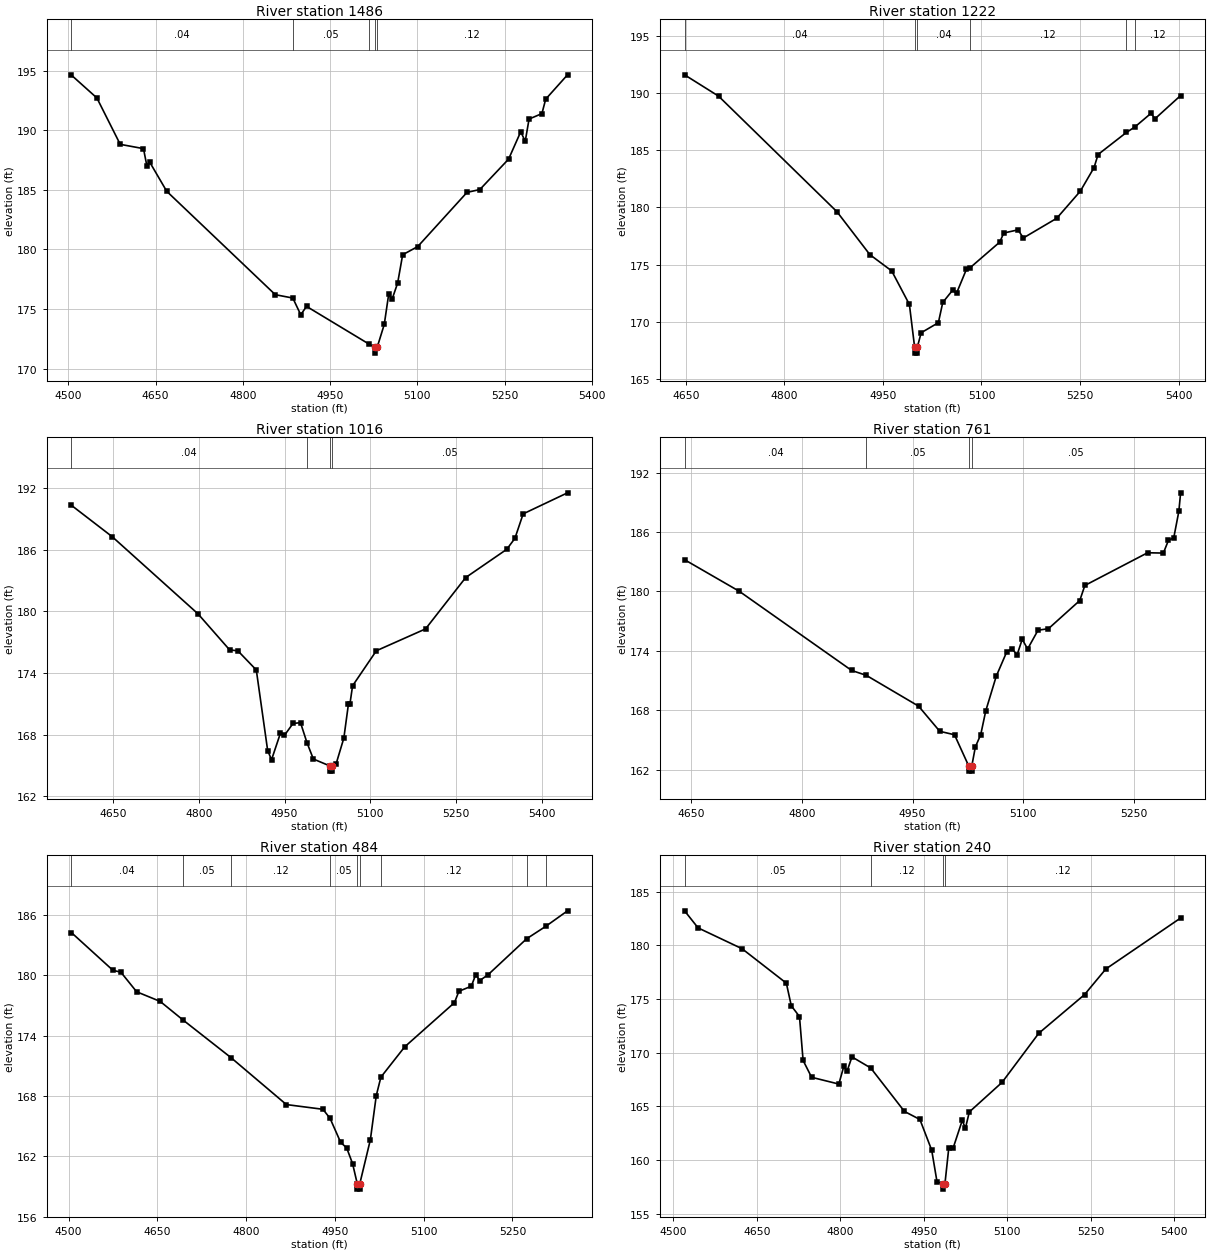
Type RM Length L Ch R = 1,1486,264,264,264
BEGIN DESCRIPTION:
Mapping XS fdf2c90c
END DESCRIPTION:
XS GIS Cut Line= 4
      2529721.33     13548525.89      2530153.17     13548506.36
      2530272.53     13548439.09      2530454.81     13548222.09
#Sta/Elev= 30
  4505.5  194.61  4549.2  192.70  4589.3  188.81  4629.3  188.45  4635.1  187.01
  4640.1  187.31  4669.3  184.87  4855.9  176.20  4886.0  175.92  4899.6  174.52
  4909.6  175.22  5016.9  172.06  5027.1  171.80  5027.3  171.30  5031.1  171.80
  5043.2  173.71  5050.8  176.24  5056.5  175.80  5066.2  177.18  5074.8  179.55
  5100.8  180.24  5185.4  184.78  5207.5  185.02  5256.9  187.57  5277.8  189.87
  5285.5  189.06  5292.1  190.93  5314.2  191.39  5320.7  192.60  5358.2  194.64
#Mann=5,-1,0
  4505.5    0.04       0  4886.0    0.05       0  5016.9    0.12       0
  5027.1    0.05       0  5031.1    0.12       0
Bank Sta=5027.1,5031.1
Exp/Cntr=0.3,0.1

Type RM Length L Ch R = 1,1222,206,206,206
BEGIN DESCRIPTION:
Mapping XS b643d066
END DESCRIPTION:
XS GIS Cut Line= 3
      2529773.42     13548716.87      2530135.81     13548697.34
      2530459.18     13548475.97
#Sta/Elev= 30
  4648.2  191.58  4699.9  189.72  4880.1  179.62  4930.2  175.87  4963.4  174.45
  4990.3  171.52  4998.3  167.77  4998.5  167.27  5002.0  167.27  5002.3  167.77
  5008.2  169.05  5034.4  169.93  5041.1  171.70  5056.0  172.76  5062.1  172.51
  5077.0  174.58  5082.3  174.71  5127.8  176.97  5133.9  177.76  5155.6  178.04
  5163.7  177.33  5214.5  179.05  5250.3  181.41  5271.3  183.48  5277.4  184.62
  5320.6  186.55  5333.5  187.03  5358.0  188.22  5364.0  187.74  5403.0  189.77
#Mann=6,-1,0
  4648.2    0.04       0  4998.3    0.04       0  5002.3    0.04       0
  5082.3    0.12       0  5320.6    0.05       0  5333.5    0.12       0
Bank Sta=4998.3,5002.3
Exp/Cntr=0.3,0.1

Type RM Length L Ch R = 1,1016,255,255,255
BEGIN DESCRIPTION:
Mapping XS e63660be
END DESCRIPTION:
XS GIS Cut Line= 4
      2529803.78     13548896.99      2530127.13     13548912.18
      2530274.70     13548840.57      2530515.59     13548545.42
#Sta/Elev= 30
  4576.8  190.33  4648.1  187.28  4798.3  179.77  4853.7  176.26  4868.3  176.16
  4900.5  174.30  4920.4  166.45  4927.2  165.56  4942.6  168.12  4949.7  167.93
  4964.8  169.09  4977.9  169.17  4989.3  167.21  5000.4  165.63  5029.5  164.95
  5029.8  164.45  5033.3  164.45  5033.5  164.95  5040.0  165.11  5053.8  167.67
  5061.9  171.01  5064.5  171.01  5069.1  172.76  5110.7  176.17  5196.9  178.30
  5267.2  183.30  5339.1  186.05  5353.4  187.12  5367.8  189.50  5445.5  191.55
#Mann=4,-1,0
  4576.8    0.04       0  4989.3    0.05       0  5029.5    0.05       0
  5033.5    0.05       0
Bank Sta=5029.5,5033.5
Exp/Cntr=0.3,0.1

Type RM Length L Ch R = 1,761,277,277,277
BEGIN DESCRIPTION:
Mapping XS 3ff41b9d
END DESCRIPTION:
XS GIS Cut Line= 3
      2530031.65     13549094.47      2530376.70     13549040.22
      2530610.52     13548817.22
#Sta/Elev= 30
  4641.0  183.20  4715.2  180.01  4867.5  172.02  4887.3  171.53  4958.2  168.42
  4986.9  165.88  5006.9  165.53  5026.3  162.36  5026.5  161.86  5030.0  161.86
  5030.3  162.36  5035.2  164.31  5042.4  165.53  5049.3  167.95  5063.5  171.44
  5077.6  173.88  5084.7  174.22  5091.8  173.60  5098.7  175.17  5106.0  174.19
  5120.1  176.08  5134.3  176.24  5176.7  179.08  5183.6  180.60  5268.6  183.90
  5290.0  183.87  5296.9  185.15  5304.1  185.41  5311.0  188.08  5313.4  189.95
#Mann=4,-1,0
  4641.0    0.04       0  4887.3    0.05       0  5026.3    0.05       0
  5030.3    0.05       0
Bank Sta=5026.3,5030.3
Exp/Cntr=0.3,0.1

Type RM Length L Ch R = 1,484,244,244,244
BEGIN DESCRIPTION:
Mapping XS 1b374a59
END DESCRIPTION:
XS GIS Cut Line= 4
      2530044.62     13549150.88      2530443.97     13549259.40
      2530595.88     13549250.72      2530799.86     13549070.61
#Sta/Elev= 30
  4504.9  184.25  4575.2  180.49  4588.2  180.33  4615.0  178.37  4654.8  177.41
  4693.0  175.58  4774.4  171.82  4868.0  167.15  4929.8  166.68  4941.8  165.78
  4959.8  163.38  4969.8  162.85  4979.9  161.27  4987.9  159.24  4988.1  158.74
  4991.6  158.74  4991.9  159.24  5009.9  163.65  5019.9  168.05  5027.7  169.88
  5067.9  172.89  5152.0  177.29  5159.5  178.42  5180.4  178.92  5188.0  180.08
  5194.6  179.48  5208.9  180.07  5273.9  183.64  5306.3  184.88  5343.0  186.42
#Mann=9,-1,0
  4504.9    0.04       0  4693.0    0.05       0  4774.4    0.12       0
  4941.8    0.05       0  4987.9    0.05       0  4991.9    0.05       0
  5027.7    0.12       0  5273.9    0.05       0  5306.3    0.12       0
Bank Sta=4987.9,4991.9
Exp/Cntr=0.3,0.1

Type RM Length L Ch R = 1,240,160,160,160
BEGIN DESCRIPTION:
TRIB 3 TO CARLISLE CREEK 1.0
END DESCRIPTION:
XS GIS Cut Line= 3
      2530059.86     13549226.85      2530466.81     13549481.04
      2530830.15     13549287.67
#Sta/Elev= 30
  4520.0  183.21  4544.3  181.62  4623.3  179.68  4702.9  176.47  4711.8  174.36
  4726.5  173.36  4733.0  169.27  4748.3  167.70  4797.2  167.07  4806.1  168.71
  4812.0  168.27  4820.8  169.60  4854.5  168.57  4915.1  164.52  4942.9  163.77
  4964.1  160.91  4973.6  157.98  4983.9  157.78  4984.1  157.28  4987.9  157.78
  4994.8  161.12  5002.7  161.12  5019.0  163.68  5024.7  162.95  5031.7  164.47
  5090.6  167.23  5156.5  171.80  5238.7  175.40  5277.0  177.79  5411.4  182.54
#Mann=4,-1,0
  4520.0    0.05       0  4854.5    0.12       0  4983.9    0.05       0
  4987.9    0.12       0
Bank Sta=4983.9,4987.9
Exp/Cntr=0.3,0.1

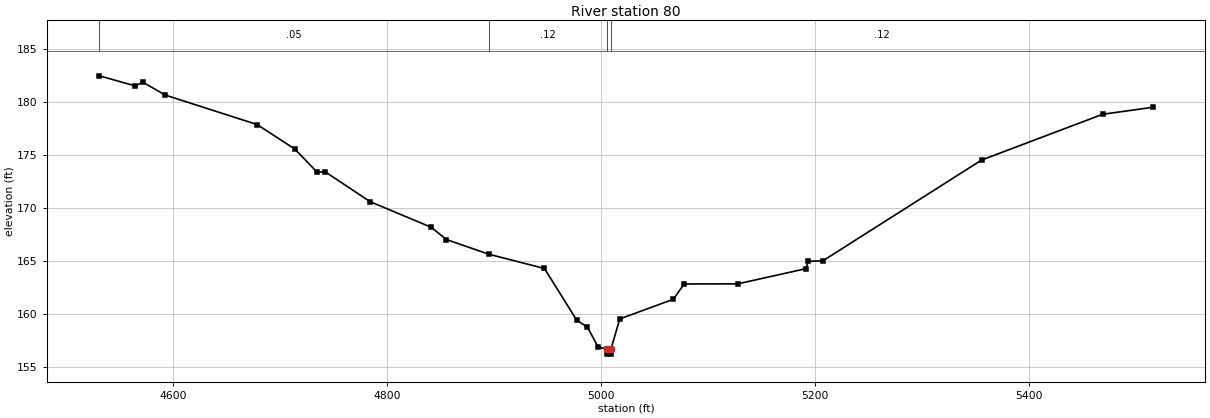
Type RM Length L Ch R = 1,80,0,0,0
BEGIN DESCRIPTION:
LGII3444
END DESCRIPTION:
XS GIS Cut Line= 5
      2530061.19     13549301.60      2530316.53     13549606.48
      2530443.50     13549618.73      2530581.71     13549609.70
      2530806.60     13549380.29
#Sta/Elev= 30
  4530.8  182.50  4564.0  181.56  4571.8  181.88  4592.6  180.68  4678.4  177.90
  4713.6  175.59  4734.4  173.41  4742.2  173.43  4783.9  170.63  4841.1  168.21
  4855.4  167.05  4894.9  165.67  4947.0  164.32  4977.2  159.44  4987.2  158.79
  4997.3  156.89  5005.3  156.74  5005.6  156.24  5009.1  156.24  5009.3  156.74
  5017.4  159.56  5067.6  161.42  5077.6  162.86  5127.7  162.87  5191.4  164.30
  5193.7  165.00  5207.3  165.04  5355.7  174.55  5468.9  178.87  5515.8  179.53
#Mann=4,-1,0
  4530.8    0.05       0  4894.9    0.12       0  5005.3    0.05       0
  5009.3    0.12       0
Bank Sta=5005.3,5009.3
Exp/Cntr=0.3,0.1

Chan Stop Cuts=-1