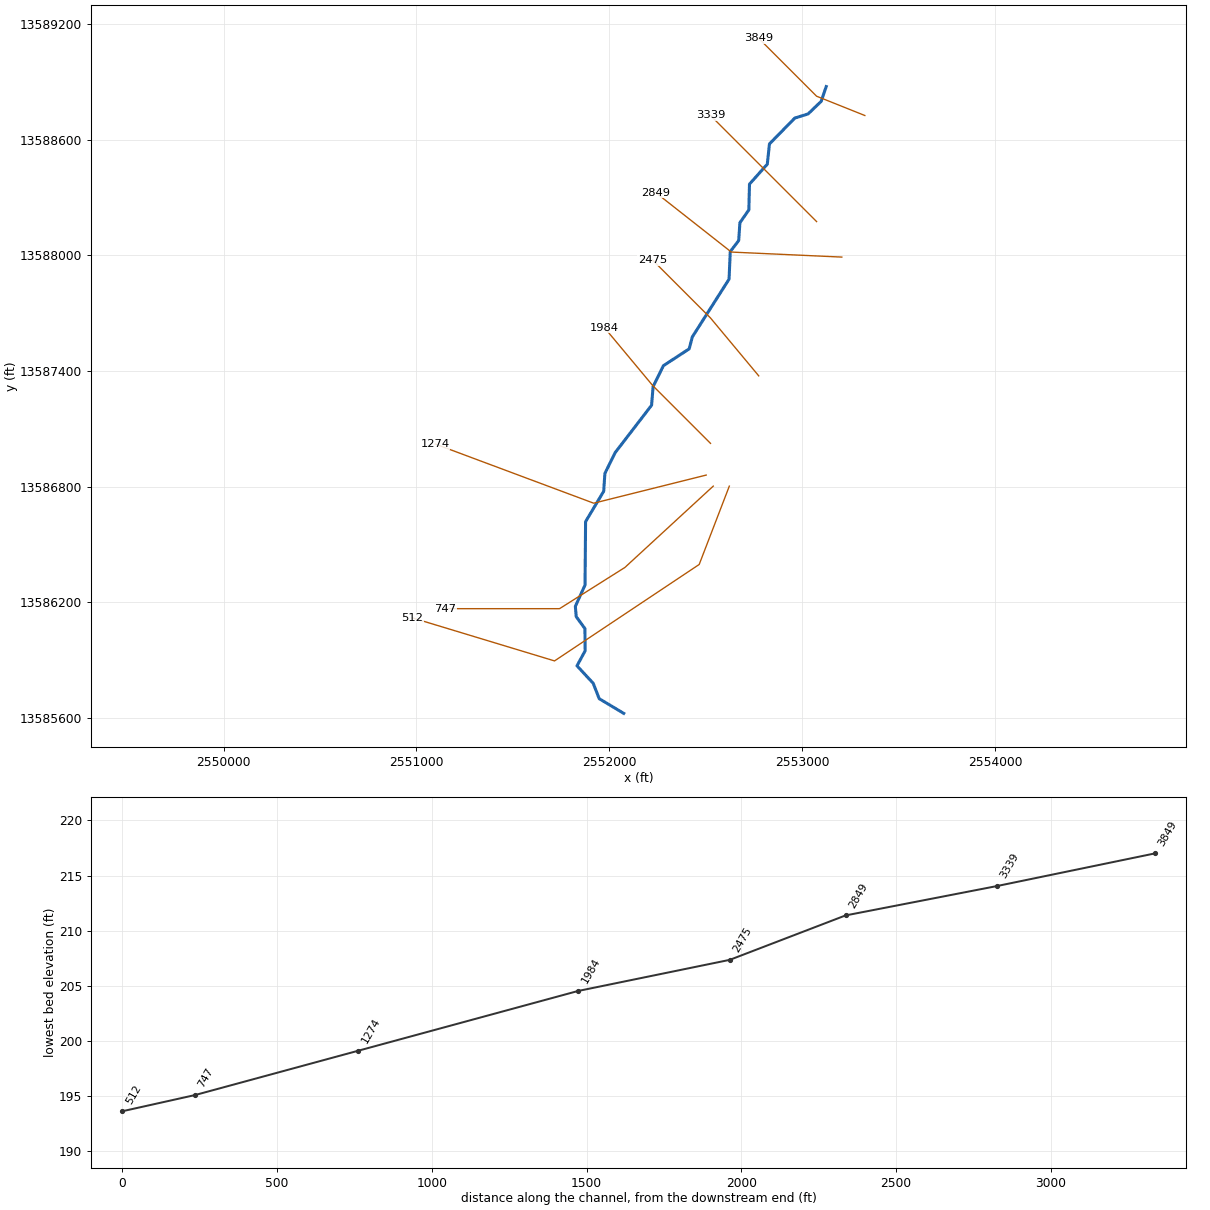
--- TRIB 3 TO CRITTENOON HOLLOW.prj (project) ---

Proj Title=TRIB 3 TO CRITTENOON HOLLOW Base Level Engineering
Current Plan=p01
Default Exp/Contr=0.3,0.1
English Units
Geom File=g01
Flow File=f01
Plan File=p01
Y Axis Title=Elevation
X Axis Title(PF)=Main Channel Distance
X Axis Title(XS)=Station
BEGIN DESCRIPTION:
TRIB 3 TO CRITTENOON HOLLOW
END DESCRIPTION:
DSS Export Rating Curves= 0
DSS Export Rating Curve Sorted= 0
DSS Export Volume Flow Curves= 0
DXF OffsetX= 0
DXF OffsetY= 0
DXF ScaleX= 1
DXF ScaleY= 10

--- TRIB 3 TO CRITTENOON HOLLOW.p01 (plan) ---

Plan Title=Multiple Run
Short Identifier=Multiple
Geom File=g01
Flow File=f01
Subcritical Flow
K Sum by GR= 0
Std Step Tol= 0.01
Critical Tol= 0.01
Num of Std Step Trials= 20
Max Error Tol= 0.3
Flow Tol Ratio= 0.001
Split Flow NTrial= 30
Split Flow Tol= 0.02
Split Flow Ratio= 0.02
Log Output Level= 0
Friction Slope Method= 1
Unsteady Friction Slope Method= 2
Unsteady Bridges Friction Slope Method= 1
Parabolic Critical Depth
Global Vel Dist=  1 , 1 , 1
Global Log Level= 0
CheckData=True
Encroach Param= -1, 0, 0, 0
BEGIN DESCRIPTION:
Multiple Run
END DESCRIPTION:

--- TRIB 3 TO CRITTENOON HOLLOW.f01 (steady flow) ---

Flow Title=Multiple
Number of Profiles=7
Profile Names=10-year,25-year,50-year,1pct_min,100-year,1pct_plu,500-year
River Rch & RM= TRIB 3 TO CRITTE,Reach-1,3849
     432     675     889     568    1133    2261    1821
River Rch & RM= TRIB 3 TO CRITTE,Reach-1,1274
     487     767    1015     652    1301    2596    2111
Boundary for River Rch & Prof#=TRIB 3 TO CRITTE,Reach-1,1
Up Type=0
Dn Type=3
Dn Slope=0.005
Boundary for River Rch & Prof#=TRIB 3 TO CRITTE,Reach-1,2
Up Type=0
Dn Type=3
Dn Slope=0.005
Boundary for River Rch & Prof#=TRIB 3 TO CRITTE,Reach-1,3
Up Type=0
Dn Type=3
Dn Slope=0.005
Boundary for River Rch & Prof#=TRIB 3 TO CRITTE,Reach-1,4
Up Type=0
Dn Type=3
Dn Slope=0.005
Boundary for River Rch & Prof#=TRIB 3 TO CRITTE,Reach-1,5
Up Type=0
Dn Type=3
Dn Slope=0.005
Boundary for River Rch & Prof#=TRIB 3 TO CRITTE,Reach-1,6
Up Type=0
Dn Type=3
Dn Slope=0.005
Boundary for River Rch & Prof#=TRIB 3 TO CRITTE,Reach-1,7
Up Type=0
Dn Type=3
Dn Slope=0.005

--- TRIB 3 TO CRITTENOON HOLLOW.g01 (geometry) ---

Geom Title=Existing Conditions

River Reach=TRIB 3 TO CRITTE,Reach-1
Reach XY= 30
      2553125.00     13588875.00      2553098.68     13588798.13
      2553031.07     13588733.14      2552961.79     13588711.37
      2552830.52     13588577.43      2552819.46     13588472.58
      2552727.08     13588369.14      2552723.77     13588235.51
      2552677.36     13588169.02      2552671.14     13588076.60
      2552627.27     13588019.06      2552621.24     13587876.56
      2552430.88     13587577.26      2552414.35     13587515.01
      2552280.73     13587427.55      2552227.33     13587319.03
      2552219.46     13587222.58      2552030.84     13586977.29
      2551977.33     13586869.03      2551971.17     13586776.58
      2551877.24     13586619.07      2551874.48     13586290.22
      2551824.19     13586180.03      2551828.71     13586126.60
      2551873.79     13586064.49      2551875.13     13585949.89
      2551832.81     13585871.59      2551916.80     13585781.03
      2551947.84     13585701.14      2552075.00     13585625.00

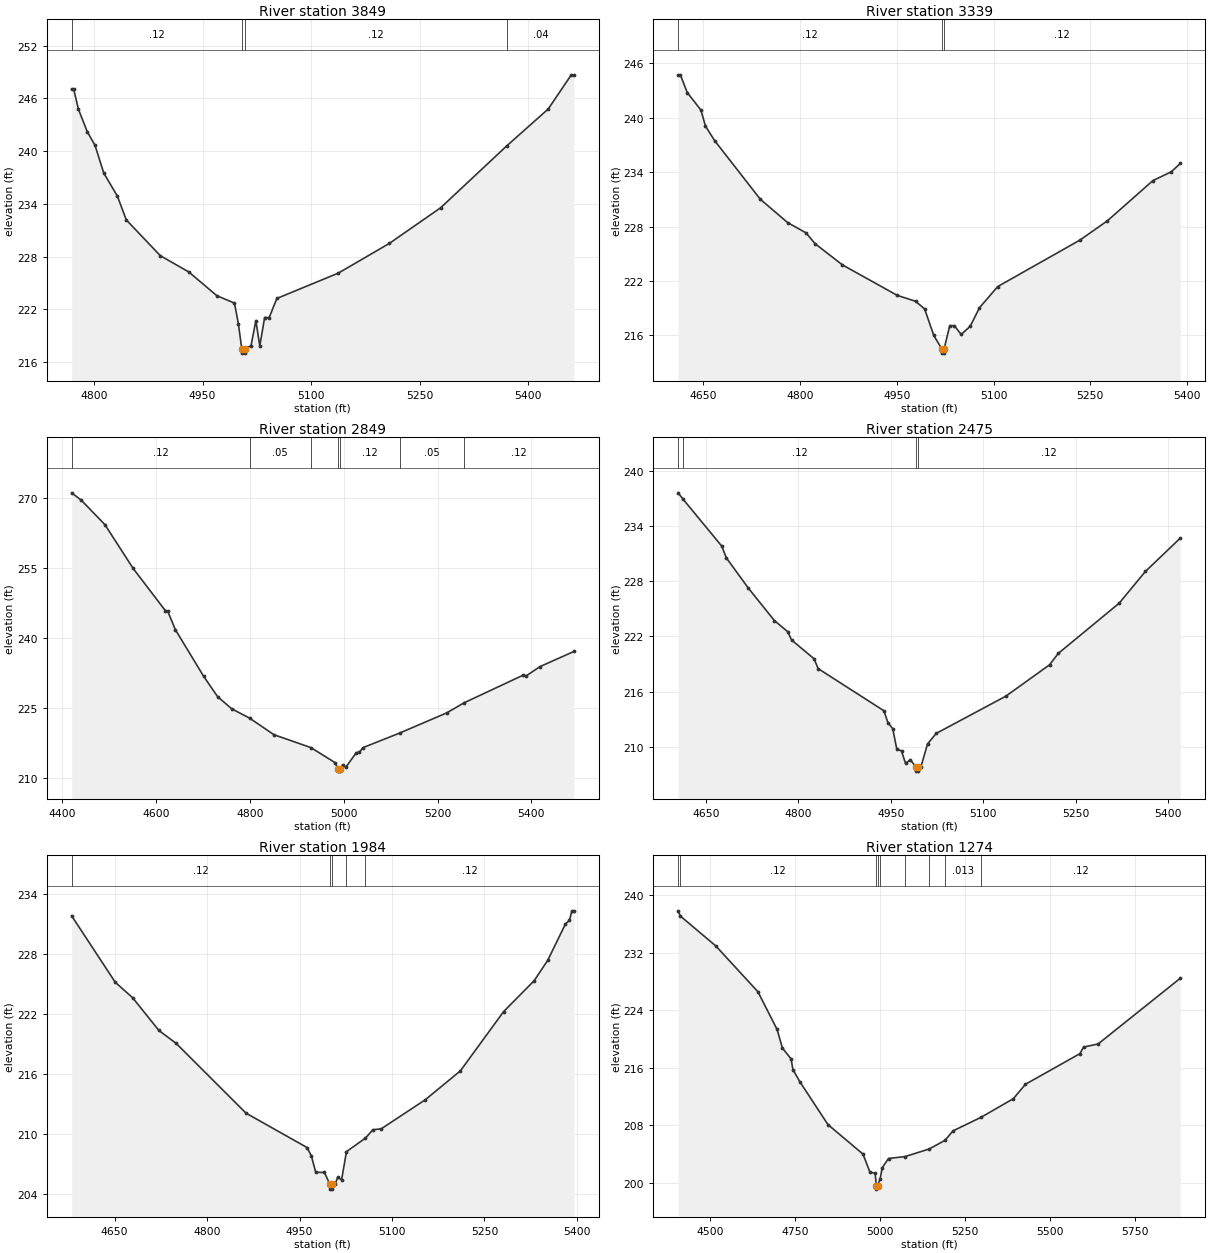
Type RM Length L Ch R = 1,3849,510,510,510
BEGIN DESCRIPTION:
TRIB 3 TO CRITTENOON HOLLOW 8.0
END DESCRIPTION:
XS GIS Cut Line= 3
      2553324.97     13588725.01      2553075.00     13588825.00
      2552774.99     13589125.01
#Sta/Elev= 30
  4769.2  247.08  4771.9  247.08  4778.6  244.75  4790.7  242.21  4801.5  240.64
  4813.6  237.48  4832.4  234.87  4844.6  232.17  4891.7  228.09  4930.7  226.26
  4969.8  223.54  4994.0  222.70  4999.4  220.38  5004.1  217.51  5004.4  217.01
  5007.9  217.01  5008.1  217.51  5016.9  217.85  5023.6  220.72  5029.0  217.82
  5035.7  221.06  5042.0  221.06  5052.6  223.23  5137.4  226.11  5208.1  229.50
  5278.8  233.55  5370.2  240.60  5427.3  244.78  5459.2  248.67  5462.7  248.67
#Mann=4,-1,0
  4769.2    0.12       0  5004.1    0.05       0  5008.1    0.12       0
  5370.2    0.04       0
Bank Sta=5004.1,5008.1
Exp/Cntr=0.3,0.1

Type RM Length L Ch R = 1,3339,490,490,490
BEGIN DESCRIPTION:
TRIB 3 TO CRITTENOON HOLLOW 7.0
END DESCRIPTION:
XS GIS Cut Line= 3
      2553074.99     13588175.01      2552775.00     13588475.00
      2552525.00     13588725.00
#Sta/Elev= 30
  4611.5  244.74  4615.0  244.74  4625.6  242.79  4646.8  240.86  4653.9  239.08
  4668.1  237.48  4738.8  231.02  4781.2  228.44  4809.5  227.32  4823.6  226.12
  4866.0  223.78  4950.9  220.42  4979.2  219.77  4993.3  218.92  5007.5  216.00
  5019.6  214.55  5019.9  214.05  5023.4  214.05  5023.6  214.55  5032.2  217.08
  5039.3  217.08  5049.9  216.11  5064.0  217.02  5078.2  219.05  5106.5  221.39
  5233.7  226.51  5276.2  228.63  5346.9  233.08  5375.2  234.04  5389.3  234.97
#Mann=3,-1,0
  4611.5    0.12       0  5019.6    0.05       0  5023.6    0.12       0
Bank Sta=5019.6,5023.6
Exp/Cntr=0.3,0.1

Type RM Length L Ch R = 1,2849,374,374,374
BEGIN DESCRIPTION:
Mapping XS 9b6a57d2
END DESCRIPTION:
XS GIS Cut Line= 3
      2553205.81     13587990.79      2552632.93     13588016.83
      2552242.28     13588324.13
#Sta/Elev= 30
  4420.1  271.16  4440.9  269.55  4491.0  264.33  4551.0  254.95  4619.6  245.88
  4624.6  245.81  4641.1  241.78  4701.2  231.79  4731.2  227.38  4761.3  224.77
  4799.4  222.77  4851.4  219.20  4930.2  216.43  4981.5  213.21  4988.0  211.88
  4988.3  211.38  4991.8  211.38  4992.0  211.88  4998.0  212.76  5004.4  212.20
  5026.9  215.35  5033.3  215.43  5041.3  216.43  5119.3  219.56  5219.4  223.88
  5257.5  226.10  5382.9  232.01  5389.3  231.85  5418.2  233.82  5490.6  237.08
#Mann=7,-1,0
  4420.1    0.12       0  4799.4    0.05       0  4930.2    0.12       0
  4988.0    0.05       0  4992.0    0.12       0  5119.3    0.05       0
  5257.5    0.12       0
Bank Sta=4988,4992
Exp/Cntr=0.3,0.1

Type RM Length L Ch R = 1,2475,491,491,491
BEGIN DESCRIPTION:
TRIB 3 TO CRITTENOON HOLLOW 5.0
END DESCRIPTION:
XS GIS Cut Line= 3
      2552775.00     13587375.00      2552525.00     13587675.00
      2552224.99     13587975.01
#Sta/Elev= 30
  4604.7  237.59  4613.1  236.87  4675.6  231.79  4682.8  230.54  4718.6  227.24
  4760.9  223.71  4782.4  222.51  4788.9  221.59  4825.3  219.56  4831.9  218.49
  4938.6  213.91  4945.1  212.62  4952.9  211.96  4959.4  209.78  4967.2  209.53
  4973.7  208.19  4981.5  208.59  4990.0  207.85  4990.2  207.35  4993.7  207.35
  4994.0  207.85  4998.8  207.85  5009.4  210.31  5023.5  211.45  5136.6  215.50
  5207.3  218.90  5221.5  220.14  5320.5  225.61  5362.9  229.05  5419.5  232.67
#Mann=4,-1,0
  4604.7    0.05       0  4613.1    0.12       0  4990.0    0.05       0
  4994.0    0.12       0
Bank Sta=4990,4994
Exp/Cntr=0.3,0.1

Type RM Length L Ch R = 1,1984,710,710,710
BEGIN DESCRIPTION:
TRIB 3 TO CRITTENOON HOLLOW 4.0
END DESCRIPTION:
XS GIS Cut Line= 3
      2552525.03     13587024.97      2552225.00     13587325.00
      2551975.01     13587624.99
#Sta/Elev= 30
  4580.3  231.78  4651.1  225.15  4679.3  223.61  4721.8  220.35  4750.0  219.05
  4863.2  212.10  4962.2  208.67  4969.3  207.83  4976.3  206.20  4990.5  206.18
  4999.1  205.02  4999.3  204.52  5002.8  204.52  5003.1  205.02  5007.9  205.02
  5011.8  205.68  5018.3  205.46  5026.2  208.26  5057.0  209.61  5069.0  210.44
  5082.7  210.54  5153.7  213.42  5210.9  216.31  5281.2  222.23  5330.7  225.31
  5352.8  227.35  5381.5  230.97  5388.0  231.34  5391.9  232.28  5395.1  232.28
#Mann=5,-1,0
  4580.3    0.12       0  4999.1    0.05       0  5003.1    0.12       0
  5026.2    0.05       0  5057.0    0.12       0
Bank Sta=4999.1,5003.1
Exp/Cntr=0.3,0.1

Type RM Length L Ch R = 1,1274,527,527,527
BEGIN DESCRIPTION:
Mapping XS db39c460
END DESCRIPTION:
XS GIS Cut Line= 3
      2552502.69     13586860.57      2551919.39     13586714.74
      2551098.23     13587021.38
#Sta/Elev= 30
  4406.8  237.82  4413.5  237.09  4517.8  232.93  4641.5  226.57  4698.0  221.32
  4713.7  218.73  4739.2  217.22  4744.6  215.74  4765.2  214.03  4847.7  208.08
  4950.7  203.98  4971.4  201.45  4986.6  201.32  4990.0  199.60  4990.2  199.10
  4994.0  199.60  5001.2  200.52  5007.7  202.10  5025.9  203.36  5074.7  203.63
  5145.4  204.68  5192.0  205.88  5215.6  207.20  5298.1  209.09  5393.2  211.68
  5429.0  213.69  5589.2  217.95  5600.0  218.87  5642.5  219.29  5884.6  228.44
#Mann=9,-1,0
  4406.8    0.05       0  4413.5    0.12       0  4990.0    0.05       0
  4994.0    0.12       0  5001.2    0.05       0  5074.7    0.12       0
  5145.4    0.04       0  5192.0   0.013       0  5298.1    0.12       0
Bank Sta=4990,4994
Exp/Cntr=0.3,0.1

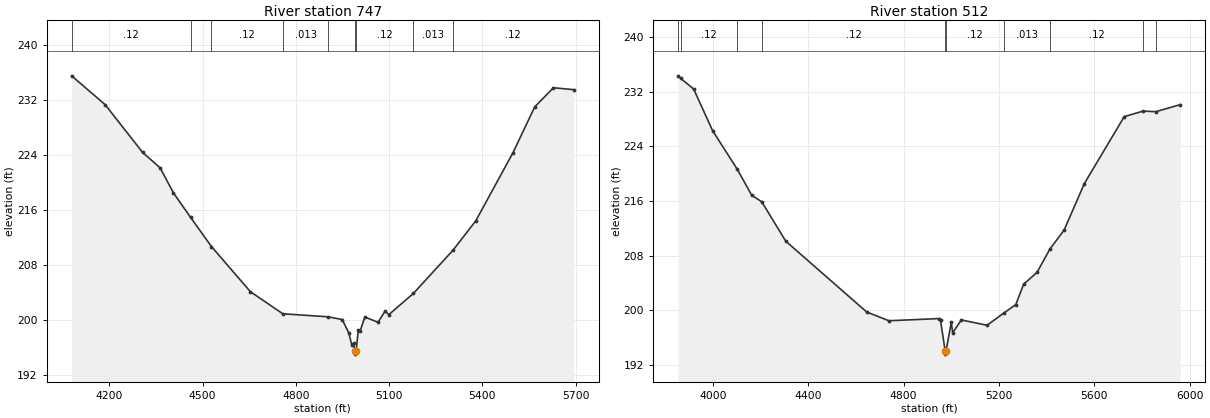
Type RM Length L Ch R = 1,747,235,235,235
BEGIN DESCRIPTION:
Mapping XS 4480cdaa
END DESCRIPTION:
XS GIS Cut Line= 4
      2552539.18     13586803.29      2552080.85     13586381.41
      2551742.30     13586167.87      2551149.30     13586167.87
#Sta/Elev= 30
  4078.4  235.50  4186.3  231.31  4306.5  224.39  4363.3  222.13  4405.8  218.51
  4461.0  214.95  4528.4  210.70  4653.6  204.15  4757.9  200.94  4904.2  200.50
  4949.1  200.10  4970.3  198.17  4979.7  196.44  4985.6  196.68  4990.0  195.58
  4990.3  195.08  4994.0  195.58  5000.9  198.60  5006.8  198.44  5022.1  200.47
  5064.5  199.70  5086.6  201.29  5099.6  200.83  5178.1  203.89  5305.3  210.15
  5378.9  214.43  5498.9  224.35  5568.9  231.00  5628.9  233.77  5694.6  233.49
#Mann=9,-1,0
  4078.4    0.12       0  4461.0   0.013       0  4528.4    0.12       0
  4757.9   0.013       0  4904.2    0.12       0  4990.0    0.05       0
  4994.0    0.12       0  5178.1   0.013       0  5305.3    0.12       0
Bank Sta=4990,4994
Exp/Cntr=0.3,0.1

Type RM Length L Ch R = 1,512,0,0,0
BEGIN DESCRIPTION:
Mapping XS 4226a358
END DESCRIPTION:
XS GIS Cut Line= 4
      2552622.52     13586803.29      2552466.26     13586397.03
      2551716.26     13585897.03      2550979.94     13586120.01
#Sta/Elev= 30
  3854.6  234.31  3864.8  233.96  3919.9  232.37  3999.2  226.29  4102.6  220.65
  4163.1  216.85  4205.1  215.90  4306.0  210.13  4645.5  199.77  4738.6  198.49
  4949.0  198.81  4955.0  198.55  4974.4  194.11  4974.7  193.61  4978.4  194.11
  5000.1  198.24  5006.1  196.72  5042.1  198.61  5150.3  197.83  5219.5  199.59
  5270.7  200.85  5303.6  203.83  5359.8  205.57  5413.8  208.98  5473.5  211.76
  5558.3  218.56  5725.4  228.34  5804.1  229.15  5858.3  229.07  5960.6  230.10
#Mann=10,-1,0
  3854.6    0.05       0  3864.8    0.12       0  4102.6   0.013       0
  4205.1    0.12       0  4974.4    0.05       0  4978.4    0.12       0
  5219.5   0.013       0  5413.8    0.12       0  5804.1    0.05       0
  5858.3    0.12       0
Bank Sta=4974.4,4978.4
Exp/Cntr=0.3,0.1

Chan Stop Cuts=-1