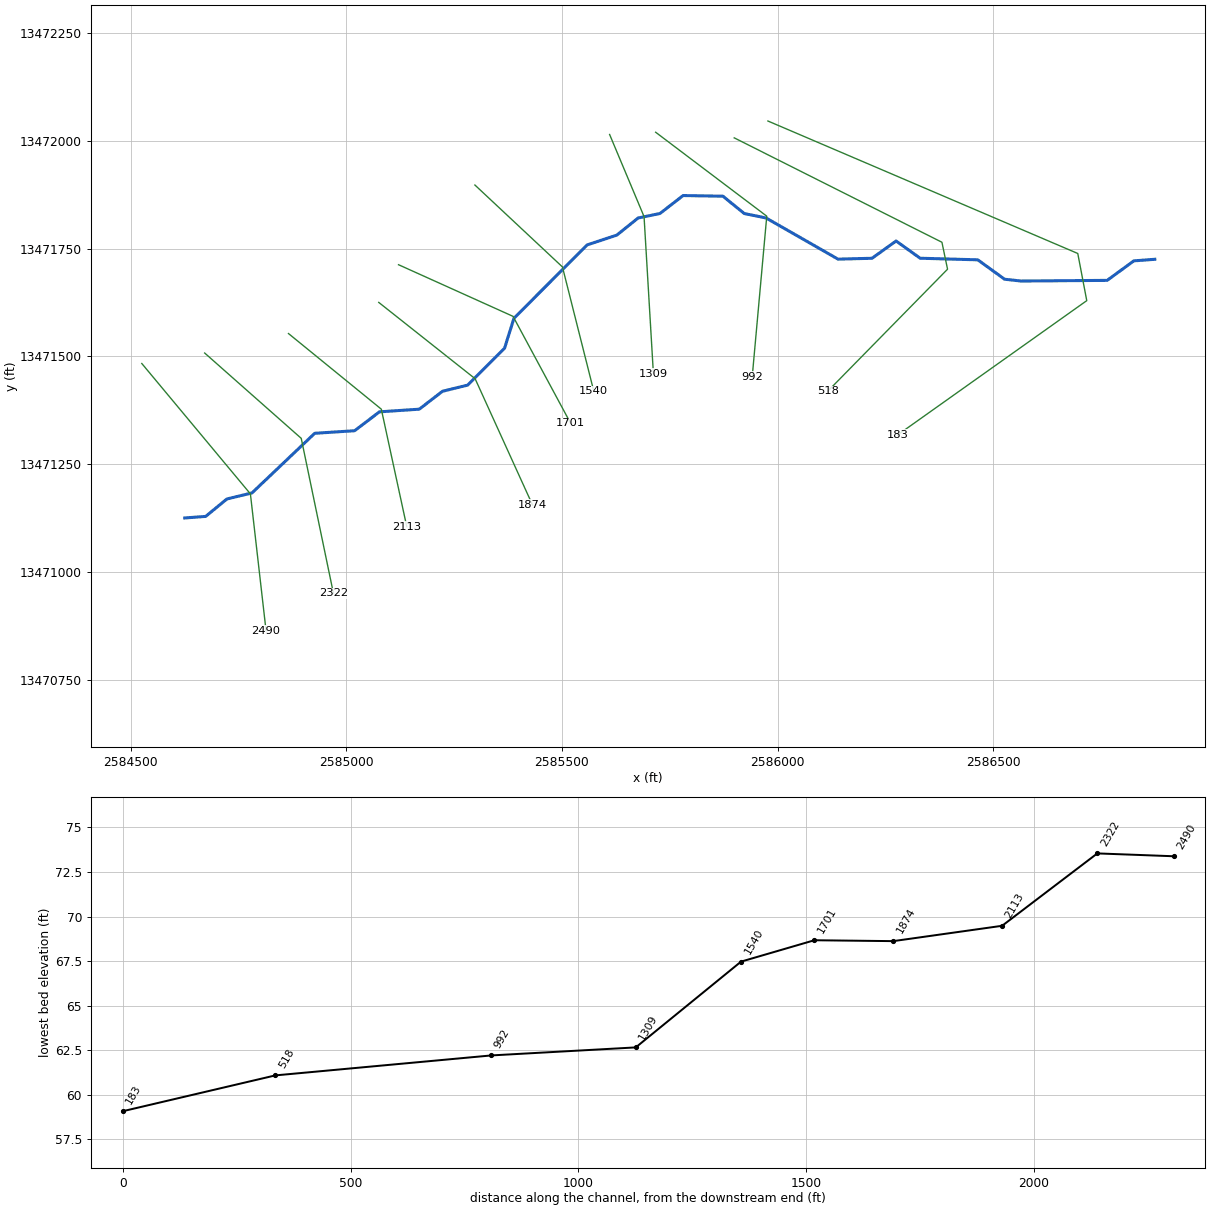
--- TRIB 3 TO DRY CREEK.prj (project) ---

Proj Title=TRIB 3 TO DRY CREEK Base Level Engineering
Current Plan=p01
Default Exp/Contr=0.3,0.1
English Units
Geom File=g01
Flow File=f01
Plan File=p01
Y Axis Title=Elevation
X Axis Title(PF)=Main Channel Distance
X Axis Title(XS)=Station
BEGIN DESCRIPTION:
TRIB 3 TO DRY CREEK
END DESCRIPTION:
DSS Export Rating Curves= 0
DSS Export Rating Curve Sorted= 0
DSS Export Volume Flow Curves= 0
DXF OffsetX= 0
DXF OffsetY= 0
DXF ScaleX= 1
DXF ScaleY= 10

--- TRIB 3 TO DRY CREEK.p01 (plan) ---

Plan Title=Multiple Run
Short Identifier=Multiple
Geom File=g01
Flow File=f01
Subcritical Flow
K Sum by GR= 0
Std Step Tol= 0.01
Critical Tol= 0.01
Num of Std Step Trials= 20
Max Error Tol= 0.3
Flow Tol Ratio= 0.001
Split Flow NTrial= 30
Split Flow Tol= 0.02
Split Flow Ratio= 0.02
Log Output Level= 0
Friction Slope Method= 1
Unsteady Friction Slope Method= 2
Unsteady Bridges Friction Slope Method= 1
Parabolic Critical Depth
Global Vel Dist=  1 , 1 , 1
Global Log Level= 0
CheckData=True
Encroach Param= -1, 0, 0, 0
BEGIN DESCRIPTION:
Multiple Run
END DESCRIPTION:

--- TRIB 3 TO DRY CREEK.f01 (steady flow) ---

Flow Title=Multiple
Number of Profiles=7
Profile Names=10-year,25-year,50-year,1pct_min,100-year,1pct_plu,500-year
River Rch & RM= TRIB 3 TO DRY CR,Reach-1,2490
     746    1179    1563    1002    1998    3987    3228
River Rch & RM= TRIB 3 TO DRY CR,Reach-1,2322
     847    1352    1802    1162    2318    4625    3789
Boundary for River Rch & Prof#=TRIB 3 TO DRY CR,Reach-1,1
Up Type=0
Dn Type=3
Dn Slope=0.005
Boundary for River Rch & Prof#=TRIB 3 TO DRY CR,Reach-1,2
Up Type=0
Dn Type=3
Dn Slope=0.005
Boundary for River Rch & Prof#=TRIB 3 TO DRY CR,Reach-1,3
Up Type=0
Dn Type=3
Dn Slope=0.005
Boundary for River Rch & Prof#=TRIB 3 TO DRY CR,Reach-1,4
Up Type=0
Dn Type=3
Dn Slope=0.005
Boundary for River Rch & Prof#=TRIB 3 TO DRY CR,Reach-1,5
Up Type=0
Dn Type=3
Dn Slope=0.005
Boundary for River Rch & Prof#=TRIB 3 TO DRY CR,Reach-1,6
Up Type=0
Dn Type=3
Dn Slope=0.005
Boundary for River Rch & Prof#=TRIB 3 TO DRY CR,Reach-1,7
Up Type=0
Dn Type=3
Dn Slope=0.005

--- TRIB 3 TO DRY CREEK.g01 (geometry) ---

Geom Title=Existing Conditions
Program Version=4.10

River Reach=TRIB 3 TO DRY CR,Reach-1
Reach XY= 30
        2584625.       13471125.      2584673.51      13471128.6
      2584722.76     13471169.03      2584781.06     13471183.13
       2584926.5     13471321.39      2585019.02     13471327.36
       2585076.6     13471371.15      2585169.03     13471377.33
      2585222.83     13471418.86      2585281.07     13471433.13
      2585366.85     13471518.93      2585388.63     13471588.21
      2585558.32     13471758.36      2585627.19      13471781.1
      2585676.72     13471820.84      2585727.18     13471831.12
      2585780.97     13471872.86      2585873.42     13471871.33
      2585922.82     13471831.12      2585973.28     13471820.84
      2586140.27     13471725.37      2586219.11     13471727.36
        2586275.     13471767.44      2586330.86     13471727.47
      2586464.49     13471723.77      2586526.57     13471678.78
      2586564.81     13471674.55      2586764.54     13471676.12
      2586826.51     13471721.35        2586875.       13471725.

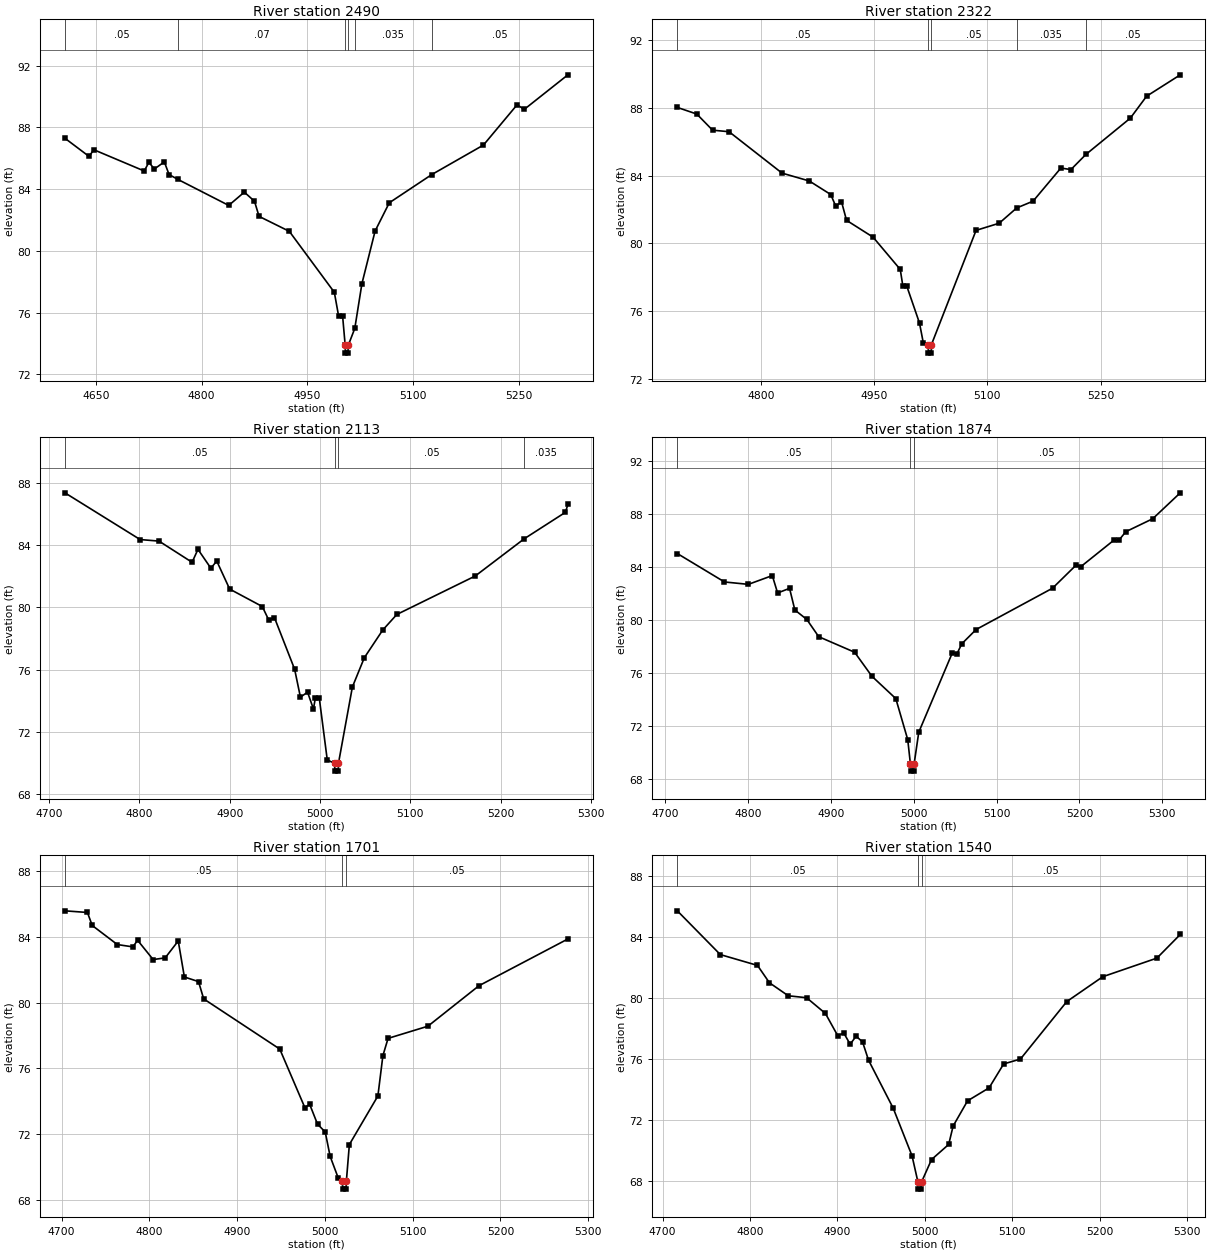
Type RM Length L Ch R = 1 ,2490    ,168,168,168
BEGIN DESCRIPTION:
TRIB 3 TO DRY CREEK 5.0
END DESCRIPTION:
XS GIS Cut Line= 3
      2584525.42     13471483.26      2584777.31     13471180.82
      2584813.61     13470863.49
#Sta/Elev= 30
  4606.4    87.3  4640.7   86.12  4647.2   86.56  4718.8   85.18  4725.4   85.74
  4733.2   85.31  4747.3   85.77    4754   84.95  4766.7   84.63  4838.6   82.95
  4860.7   83.81  4875.1   83.22  4881.6   82.24  4924.5   81.27  4988.3   77.32
  4994.3    75.8    5000    75.8  5003.7   73.88    5004   73.38  5007.7   73.38
    5008   73.88  5017.3   74.98  5027.4   77.88  5046.1   81.29  5066.2   83.12
  5126.5   84.95  5199.7   86.86  5247.4   89.47  5257.5   89.17  5319.4   91.41
#Mann= 6 ,-1 , 0
  4606.4     .05       0  4766.7     .07       0  5003.7     .05       0
    5008     .07       0  5017.3    .035       0  5126.5     .05       0
Bank Sta=5003.7,5008
XS Rating Curve= 0 ,0
Exp/Cntr=0.3,0.1

Type RM Length L Ch R = 1 ,2322    ,209,209,209
BEGIN DESCRIPTION:
Mapping XS a3270c64
END DESCRIPTION:
XS GIS Cut Line= 3
      2584671.22      13471507.6      2584895.21     13471309.65
      2584969.87     13470950.25
#Sta/Elev= 30
  4689.4   88.01  4715.2   87.62  4736.1   86.67  4757.9   86.58  4828.1   84.14
  4864.1   83.68  4892.6   82.88  4899.2   82.19  4906.8   82.46  4913.5   81.36
  4948.6   80.37  4984.6   78.47  4988.1   77.48  4993.3   77.48  5010.1   75.31
  5015.2   74.13  5021.6   74.04  5021.9   73.54  5025.6   73.54  5025.9   74.04
    5085   80.77  5115.6   81.19  5138.8   82.09  5160.5   82.49  5197.3   84.44
  5210.6   84.35  5230.4   85.24  5289.3   87.38  5310.8   88.67  5355.4   89.93
#Mann= 5 ,-1 , 0
  4689.4     .05       0  5021.6     .05       0  5025.9     .05       0
  5138.8    .035       0  5230.4     .05       0
Bank Sta=5021.6,5025.9
XS Rating Curve= 0 ,0
Exp/Cntr=0.3,0.1

Type RM Length L Ch R = 1 ,2113    ,239,239,239
BEGIN DESCRIPTION:
Mapping XS d42fef07
END DESCRIPTION:
XS GIS Cut Line= 3
      2584865.66     13471552.74      2585080.97     13471377.36
        2585140.     13471104.78
#Sta/Elev= 30
  4717.7   87.35  4800.9   84.35  4821.8   84.25  4858.4   82.89  4864.9   83.72
  4879.2   82.51  4885.7   82.97    4900   81.17  4936.1   80.05  4943.1    79.2
  4949.6   79.33  4971.9   76.02  4978.3   74.23  4986.2   74.55  4992.7   73.47
  4994.8   74.16  4999.2   74.16    5008    70.2  5016.1   69.98  5016.4   69.48
  5020.2   69.48  5020.4   69.98  5035.8   74.88    5049   76.76  5069.4   78.54
    5085   79.54  5171.8   82.01    5226    84.4  5271.6    86.1  5274.3   86.61
#Mann= 4 ,-1 , 0
  4717.7     .05       0  5016.1     .05       0  5020.4     .05       0
    5226    .035       0
Bank Sta=5016.1,5020.4
XS Rating Curve= 0 ,0
Exp/Cntr=0.3,0.1

Type RM Length L Ch R = 1 ,1874    ,173,173,173
BEGIN DESCRIPTION:
TRIB 3 TO DRY CREEK 4.0
END DESCRIPTION:
XS GIS Cut Line= 3
      2585075.02     13471624.99      2585298.52     13471447.99
      2585431.67     13471155.14
#Sta/Elev= 30
  4714.9      85  4771.8   82.86  4800.6   82.68  4829.5   83.34  4835.9   82.03
  4850.3   82.38  4856.7   80.75  4871.1   80.04  4885.5   78.74  4928.8   77.57
  4949.7   75.76  4978.5   74.08  4992.9   70.99  4996.2   69.12  4996.5   68.62
  5000.3   68.62  5000.5   69.12  5006.2   71.55  5046.8   77.54  5052.3   77.46
  5058.2   78.21  5075.4   79.28  5167.6   82.39  5196.2   84.14  5201.7   84.01
  5242.3   86.04  5247.8   86.01  5255.9   86.64  5288.5   87.62  5321.7   89.57
#Mann= 3 ,-1 , 0
  4714.9     .05       0  4996.2     .05       0  5000.5     .05       0
Bank Sta=4996.2,5000.5
XS Rating Curve= 0 ,0
Exp/Cntr=0.3,0.1

Type RM Length L Ch R = 1 ,1701    ,161,161,161
BEGIN DESCRIPTION:
Mapping XS 6d6535b2
END DESCRIPTION:
XS GIS Cut Line= 3
       2585120.9     13471712.43      2585386.53     13471592.64
      2585520.08     13471344.61
#Sta/Elev= 30
  4703.8   85.58  4729.4   85.48  4734.9   84.69  4763.5   83.53  4781.2   83.39
  4786.6   83.79  4804.3   82.62    4818   82.72  4832.9   83.75  4839.9   81.56
    4856   81.28  4861.9   80.23  4948.6   77.18  4977.2   73.62  4982.7   73.82
  4991.6   72.62  5000.4   72.14    5006   70.66  5015.2   69.35    5020   69.17
  5020.3   68.67  5024.2   68.67  5024.5   69.17  5027.9   71.38  5060.4   74.33
  5066.1   76.78    5072   77.83  5117.4   78.57  5175.6   81.03  5276.9   83.87
#Mann= 3 ,-1 , 0
  4703.8     .05       0    5020     .05       0  5024.5     .05       0
Bank Sta=5020,5024.5
XS Rating Curve= 0 ,0
Exp/Cntr=0.3,0.1

Type RM Length L Ch R = 1 ,1540    ,231,231,231
BEGIN DESCRIPTION:
Mapping XS f6b00d34
END DESCRIPTION:
XS GIS Cut Line= 3
      2585298.02     13471897.29      2585501.11     13471707.22
      2585573.79     13471419.11
#Sta/Elev= 30
  4716.9   85.72  4766.1   82.85  4808.6   82.14  4822.3      81  4843.8   80.15
  4864.8   80.02  4886.3   78.99  4900.4   77.53  4907.3   77.71  4914.6   76.97
  4921.4    77.5  4928.8   77.12  4935.6   75.93  4963.9   72.77  4985.4   69.65
    4992   67.97  4992.3   67.47  4996.2   67.47  4996.5   67.97  5007.7   69.41
  5027.3    70.4  5032.4   71.61  5048.9   73.26  5073.5   74.11  5090.2   75.68
  5109.4      76  5162.4   79.77  5203.6    81.4  5265.5   82.62  5292.2   84.17
#Mann= 3 ,-1 , 0
  4716.9     .05       0    4992     .05       0  4996.5     .05       0
Bank Sta=4992,4996.5
XS Rating Curve= 0 ,0
Exp/Cntr=0.3,0.1

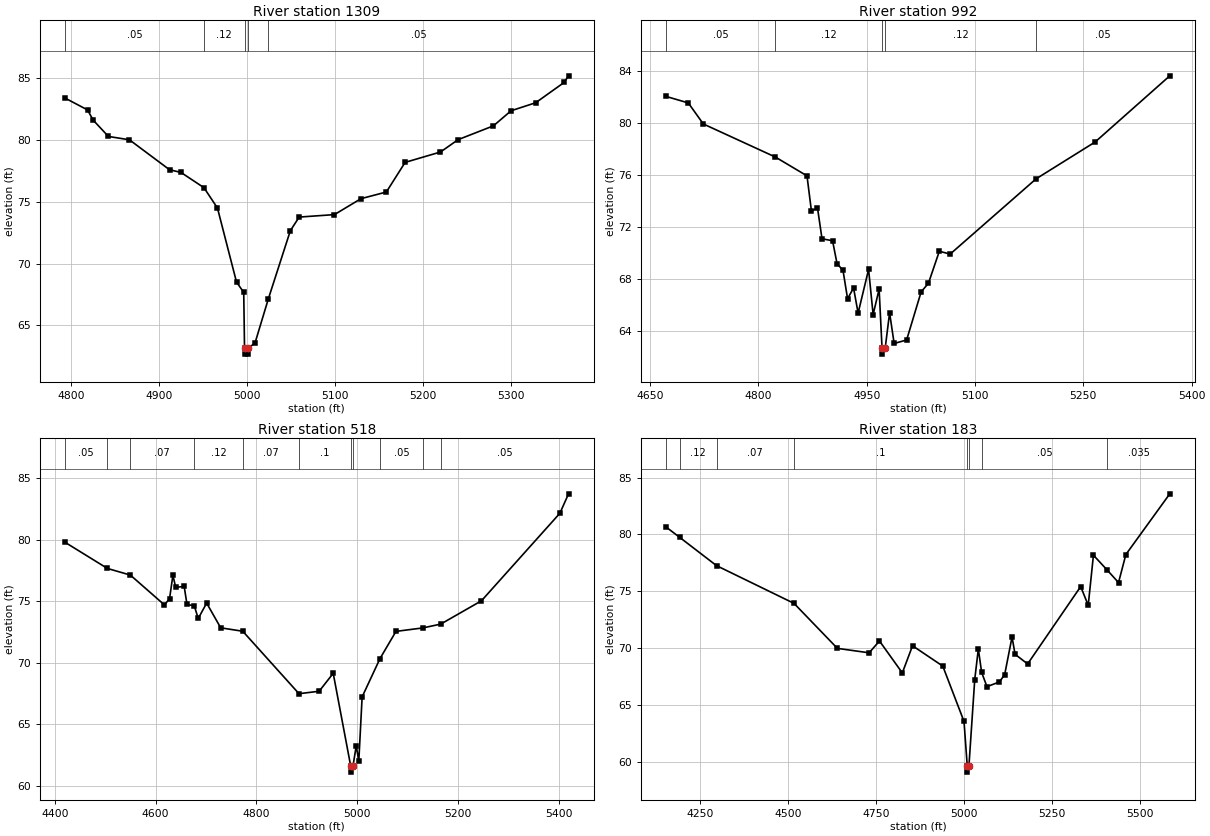
Type RM Length L Ch R = 1 ,1309    ,317,317,317
BEGIN DESCRIPTION:
TRIB 3 TO DRY CREEK 3.0
END DESCRIPTION:
XS GIS Cut Line= 3
       2585610.5     13472014.49      2585690.39     13471824.06
      2585712.04     13471459.91
#Sta/Elev= 30
  4793.5    83.4  4819.1   82.44  4825.5   81.61  4842.8   80.29  4866.6   80.02
  4912.2   77.59    4925   77.38  4951.2   76.14  4966.5   74.49  4988.1    68.5
  4996.3   67.66  4997.2   63.16  4997.5   62.66  5001.4   62.66  5001.7   63.16
  5009.1   63.56  5024.2   67.13  5049.2   72.66  5059.2   73.76  5099.2   73.96
  5129.3   75.25  5158.1   75.79  5179.4   78.19  5219.5   79.03  5239.5   80.03
  5279.6   81.15  5299.6   82.37  5327.5   83.02  5359.7   84.66  5364.8    85.2
#Mann= 5 ,-1 , 0
  4793.5     .05       0  4951.2     .12       0  4997.2     .05       0
  5001.7     .12       0  5024.2     .05       0
Bank Sta=4997.2,5001.7
XS Rating Curve= 0 ,0
Exp/Cntr=0.3,0.1

Type RM Length L Ch R = 1 ,992     ,474,474,474
BEGIN DESCRIPTION:
TRIB 3 TO DRY CREEK 2.0
END DESCRIPTION:
XS GIS Cut Line= 3
      2585717.29      13472019.7        2585975.       13471825.
      2585941.22     13471452.02
#Sta/Elev= 30
  4672.2   82.07  4702.8   81.57  4723.6   79.95  4823.4    77.4  4867.2   75.95
  4873.4   73.21  4881.7    73.5    4888    71.1  4902.6   70.95  4908.8   69.19
  4917.1   68.66  4923.4   66.48  4931.7   67.31    4938   65.37  4952.5   68.74
  4958.8   65.26  4967.1   67.22  4971.1   62.71  4971.4   62.21  4975.6   62.71
  4981.6    65.4  4987.9   63.03  5005.2    63.3  5025.3   67.01  5035.4   67.67
  5050.5   70.14  5065.5   69.92  5184.5   75.72  5266.3   78.56  5369.7   83.66
#Mann= 5 ,-1 , 0
  4672.2     .05       0  4823.4     .12       0  4971.1     .05       0
  4975.6     .12       0  5184.5     .05       0
Bank Sta=4971.1,4975.6
XS Rating Curve= 0 ,0
Exp/Cntr=0.3,0.1

Type RM Length L Ch R = 1 ,518     ,335,335,335
BEGIN DESCRIPTION:
Mapping XS fb5f81ed
END DESCRIPTION:
XS GIS Cut Line= 4
      2585899.55      13472006.7      2586381.32     13471764.51
      2586394.34     13471702.01      2586116.62     13471419.11
#Sta/Elev= 30
  4420.3   79.79  4504.5   77.66  4550.1   77.12  4617.8   74.69  4627.9   75.21
  4634.5    77.1  4640.1   76.12  4656.9    76.2  4662.5   74.73  4676.9   74.62
  4684.8   73.59  4701.5   74.84  4729.4   72.83  4773.2   72.55  4884.8   67.47
  4924.8   67.67  4952.7   69.13  4987.4   61.59  4987.7   61.09    4992   61.59
  4998.4   63.23  5003.5   61.99  5010.1   67.21  5045.6   70.33  5077.3   72.54
  5130.4   72.82    5166   73.13    5247   75.03  5402.6   82.15  5419.8   83.73
#Mann= 11 ,-1 , 0
  4420.3     .05       0  4504.5     .12       0  4550.1     .07       0
  4676.9     .12       0  4773.2     .07       0  4884.8      .1       0
  4987.4     .05       0    4992      .1       0  5045.6     .05       0
  5130.4     .12       0    5166     .05       0
Bank Sta=4987.4,4992
XS Rating Curve= 0 ,0
Exp/Cntr=0.3,0.1

Type RM Length L Ch R = 1 ,183     ,0,0,0
BEGIN DESCRIPTION:
TRIB 3 TO DRY CREEK 1.0
END DESCRIPTION:
XS GIS Cut Line= 4
      2585977.66     13472045.77      2586696.42     13471738.47
      2586717.26      13471629.1      2586278.54     13471317.58
#Sta/Elev= 30
  4153.4   80.64  4192.1   79.73  4296.4   77.25  4516.6   73.93  4639.9   69.97
    4730   69.58  4759.5   70.62  4824.4   67.81  4853.4    70.2  4939.4   68.41
  4999.7   63.54    5009   59.58  5009.4   59.08  5013.6   59.58  5030.2   67.23
  5040.4   69.92  5049.8   67.86  5064.9    66.6  5100.5   67.02  5115.3   67.67
  5136.2   70.97  5144.8   69.45  5180.5    68.6  5331.3   75.41  5352.7   73.76
  5367.5   78.17    5407   76.85  5438.8   75.76  5459.7   78.23  5584.5   83.57
#Mann= 8 ,-1 , 0
  4153.4     .05       0  4192.1     .12       0  4296.4     .07       0
  4516.6      .1       0    5009     .05       0  5013.6      .1       0
  5049.8     .05       0    5407    .035       0
Bank Sta=5009,5013.6
XS Rating Curve= 0 ,0
Exp/Cntr=0.3,0.1

Chan Stop Cuts=-1
Use User Specified Reach Order=0
Composite Channel Slope=5