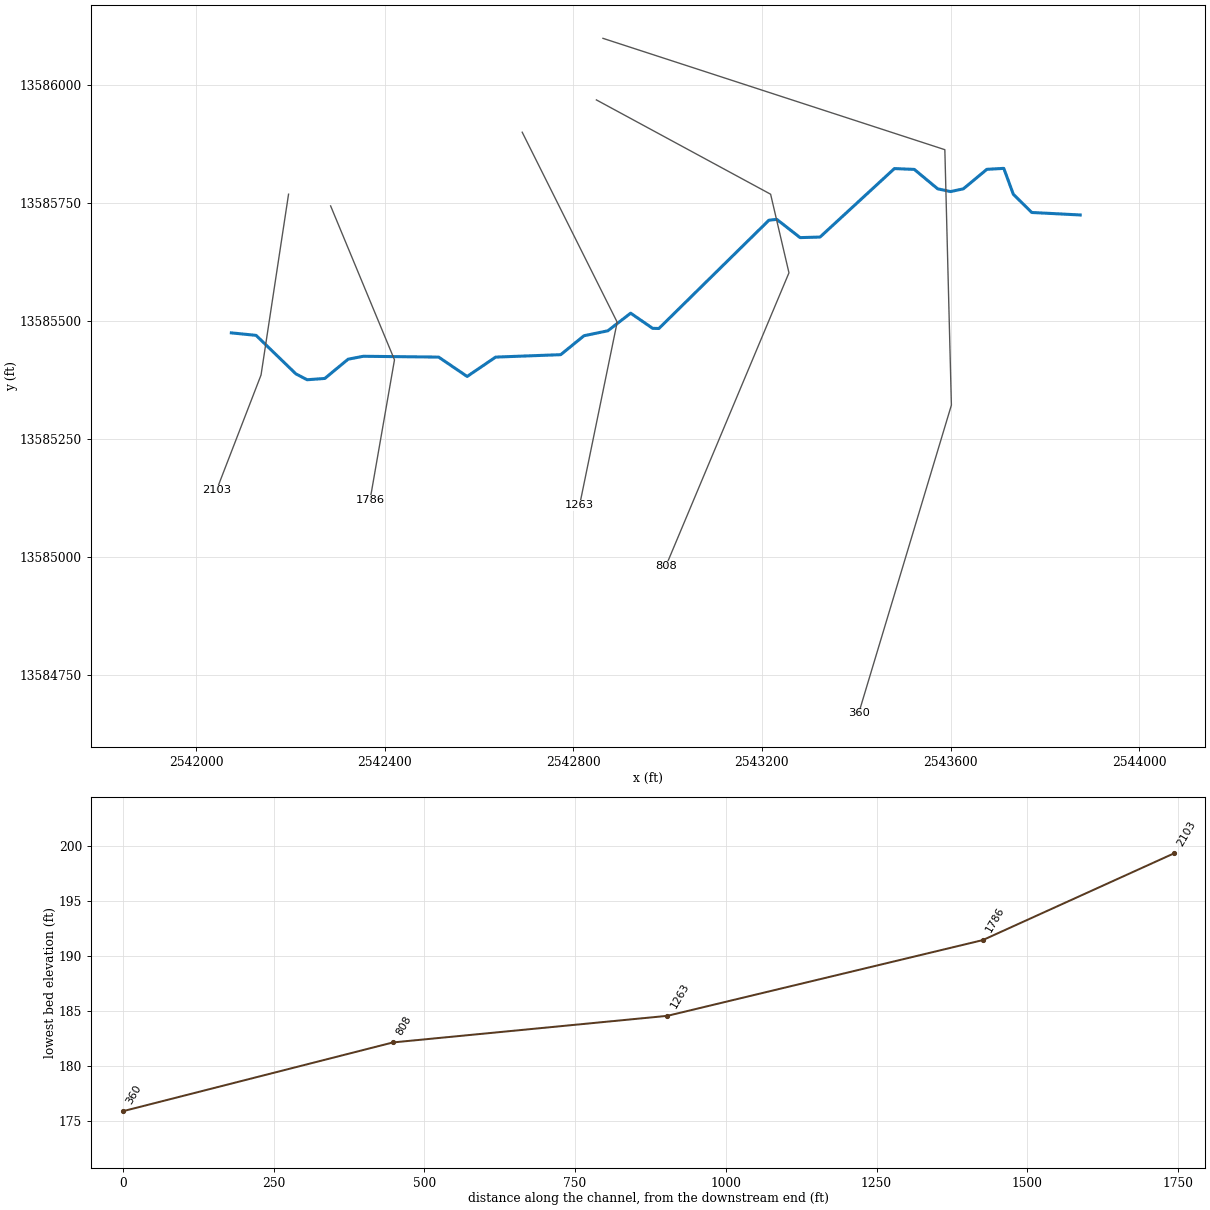
--- TRIB 3 TO IRISH CREEK.prj (project) ---

Proj Title=TRIB 3 TO IRISH CREEK Base Level Engineering
Current Plan=p01
Default Exp/Contr=0.3,0.1
English Units
Geom File=g01
Flow File=f01
Plan File=p01
BEGIN DESCRIPTION:
TRIB 3 TO IRISH CREEK
END DESCRIPTION:

--- TRIB 3 TO IRISH CREEK.p01 (plan) ---

Plan Title=Multiple Run
Short Identifier=Multiple
Geom File=g01
Flow File=f01
Subcritical Flow
K Sum by GR= 0
Std Step Tol= 0.01
Critical Tol= 0.01
Num of Std Step Trials= 20
Max Error Tol= 0.3
Flow Tol Ratio= 0.001
Split Flow NTrial= 30
Split Flow Tol= 0.02
Split Flow Ratio= 0.02
Log Output Level= 0
Friction Slope Method= 1
Unsteady Friction Slope Method= 2
Unsteady Bridges Friction Slope Method= 1
Parabolic Critical Depth
Global Vel Dist=  1 , 1 , 1
Global Log Level= 0
CheckData=True
Encroach Param= -1, 0, 0, 0
BEGIN DESCRIPTION:
Multiple Run
END DESCRIPTION:

--- TRIB 3 TO IRISH CREEK.f01 (steady flow) ---

Flow Title=Multiple
Number of Profiles=7
Profile Names=10-year,25-year,50-year,1pct_min,100-year,1pct_plu,500-year
River Rch & RM= TRIB 3 TO IRISH ,Reach-1,2103
     239     362     467     293     585    1167     905
Boundary for River Rch & Prof#=TRIB 3 TO IRISH ,Reach-1,1
Up Type=0
Dn Type=3
Dn Slope=0.005
Boundary for River Rch & Prof#=TRIB 3 TO IRISH ,Reach-1,2
Up Type=0
Dn Type=3
Dn Slope=0.005
Boundary for River Rch & Prof#=TRIB 3 TO IRISH ,Reach-1,3
Up Type=0
Dn Type=3
Dn Slope=0.005
Boundary for River Rch & Prof#=TRIB 3 TO IRISH ,Reach-1,4
Up Type=0
Dn Type=3
Dn Slope=0.005
Boundary for River Rch & Prof#=TRIB 3 TO IRISH ,Reach-1,5
Up Type=0
Dn Type=3
Dn Slope=0.005
Boundary for River Rch & Prof#=TRIB 3 TO IRISH ,Reach-1,6
Up Type=0
Dn Type=3
Dn Slope=0.005
Boundary for River Rch & Prof#=TRIB 3 TO IRISH ,Reach-1,7
Up Type=0
Dn Type=3
Dn Slope=0.005

--- TRIB 3 TO IRISH CREEK.g01 (geometry) ---

Geom Title=Existing Conditions

River Reach=TRIB 3 TO IRISH ,Reach-1
Reach XY= 30
      2542075.00     13585475.00      2542127.51     13585469.67
      2542211.79     13585388.12      2542235.62     13585375.59
      2542273.25     13585378.34      2542322.65     13585419.21
      2542354.85     13585425.35      2542514.56     13585423.62
      2542575.00     13585382.56      2542635.44     13585423.60
      2542773.44     13585428.76      2542822.83     13585468.91
      2542873.37     13585479.41      2542921.77     13585516.75
      2542968.34     13585484.60      2542981.67     13585484.30
      2543214.95     13585713.89      2543231.55     13585715.67
      2543281.05     13585676.99      2543323.35     13585678.16
      2543481.04     13585823.38      2543523.26     13585821.63
      2543572.81     13585780.42      2543600.01     13585774.62
      2543627.23     13585780.43      2543677.10     13585821.78
      2543712.98     13585823.81      2543733.14     13585769.04
      2543772.23     13585730.28      2543875.00     13585725.00

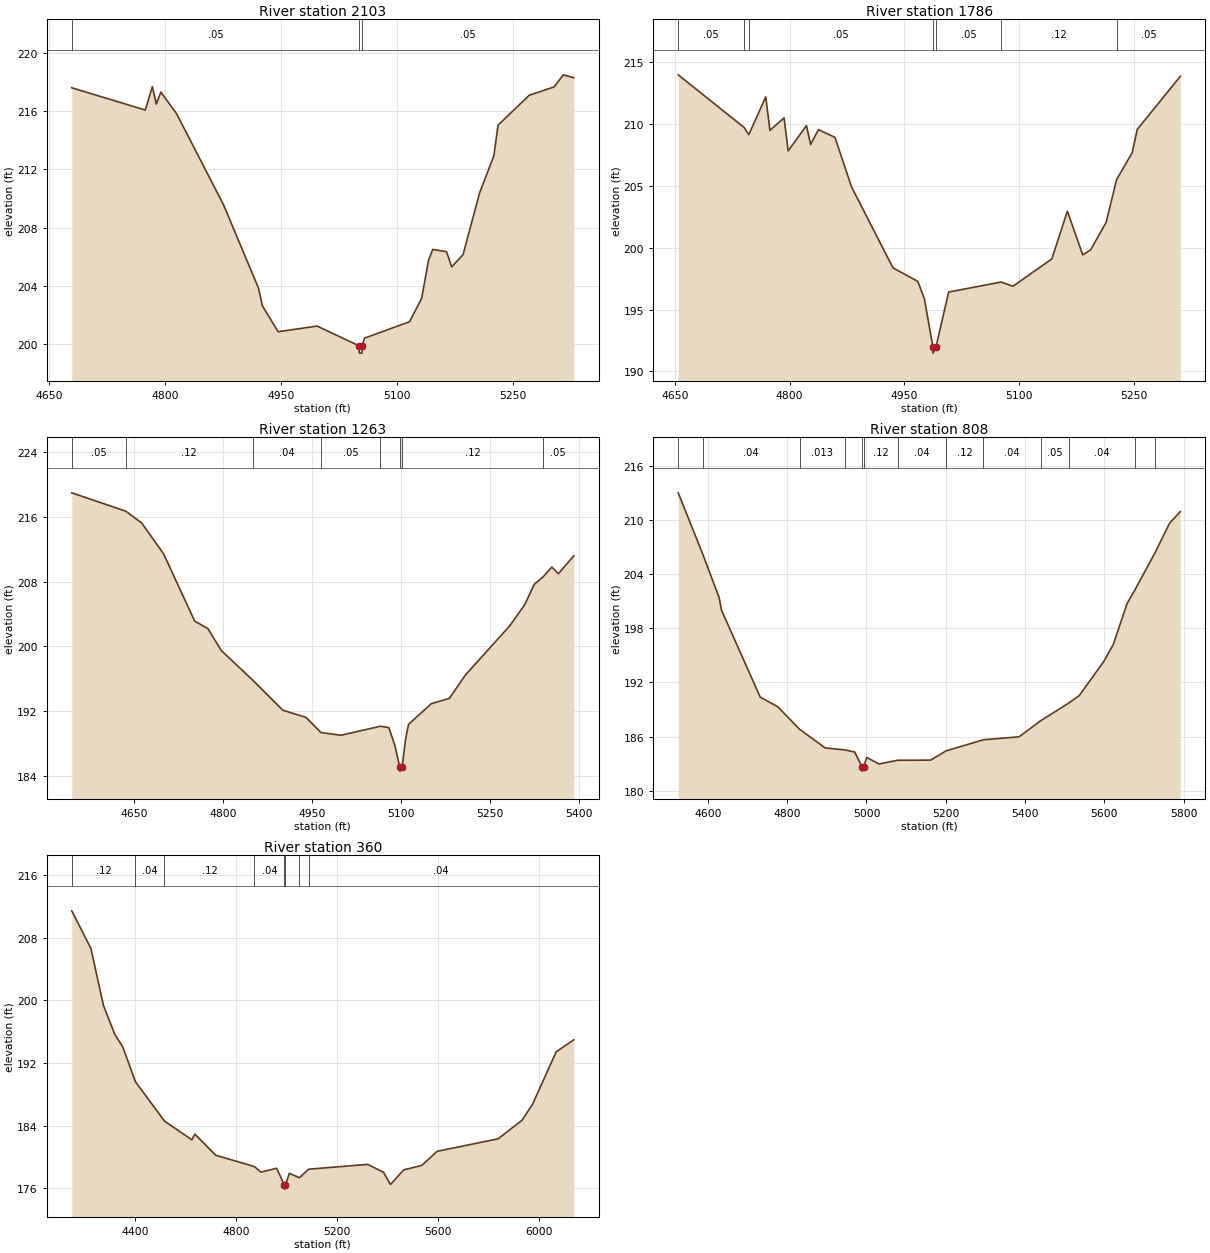
Type RM Length L Ch R = 1,2103,317,317,317
BEGIN DESCRIPTION:
TRIB 3 TO IRISH CREEK 4.0
END DESCRIPTION:
XS GIS Cut Line= 3
      2542196.32     13585769.02      2542137.98     13585385.66
      2542043.55     13585141.24
#Sta/Elev= 30
  4679.5  217.61  4774.6  216.08  4783.8  217.69  4788.9  216.49  4794.8  217.31
  4815.1  215.83  4875.8  209.58  4921.1  203.85  4926.3  202.61  4946.6  200.84
  4997.1  201.23  5051.3  199.87  5051.6  199.37  5055.1  199.37  5055.3  199.87
  5058.4  200.40  5116.7  201.53  5132.3  203.13  5141.3  205.76  5146.7  206.50
  5164.5  206.34  5171.2  205.30  5185.9  206.14  5207.3  210.38  5225.8  212.94
  5231.2  215.04  5271.7  217.10  5303.8  217.67  5315.7  218.50  5329.3  218.30
#Mann=3,-1,0
  4679.5    0.05       0  5051.3    0.05       0  5055.3    0.05       0
Bank Sta=5051.3,5055.3
Exp/Cntr=0.3,0.1

Type RM Length L Ch R = 1,1786,523,523,523
BEGIN DESCRIPTION:
Mapping XS 83b41585
END DESCRIPTION:
XS GIS Cut Line= 3
      2542285.53     13585744.20      2542420.94     13585417.82
      2542368.92     13585119.58
#Sta/Elev= 30
  4654.6  213.99  4740.7  209.73  4746.8  209.15  4769.0  212.21  4774.4  209.50
  4792.9  210.51  4798.3  207.84  4822.2  209.88  4827.6  208.35  4837.8  209.56
  4859.4  208.93  4881.1  204.92  4935.2  198.38  4967.7  197.28  4976.3  195.87
  4987.4  191.98  4987.6  191.48  4991.4  191.98  5008.0  196.42  5076.5  197.23
  5092.0  196.89  5142.8  199.10  5163.1  202.96  5183.2  199.43  5193.5  199.83
  5213.8  202.06  5227.4  205.51  5247.8  207.69  5254.4  209.57  5310.7  213.87
#Mann=7,-1,0
  4654.6    0.05       0  4740.7    0.04       0  4746.8    0.05       0
  4987.4    0.05       0  4991.4    0.05       0  5076.5    0.12       0
  5227.4    0.05       0
Bank Sta=4987.4,4991.4
Exp/Cntr=0.3,0.1

Type RM Length L Ch R = 1,1263,455,455,455
BEGIN DESCRIPTION:
Mapping XS e1acd9cb
END DESCRIPTION:
XS GIS Cut Line= 3
      2542691.78     13585900.45      2542893.17     13585497.68
      2542813.43     13585109.40
#Sta/Elev= 30
  4544.9  218.96  4635.8  216.70  4662.8  215.24  4699.7  211.43  4752.2  203.12
  4774.6  202.18  4797.0  199.49  4850.6  195.79  4900.9  192.11  4940.1  191.22
  4965.0  189.36  4999.1  189.02  5065.2  190.13  5079.6  189.97  5089.8  187.76
  5098.0  185.09  5098.3  184.59  5102.0  185.09  5107.8  188.54  5112.9  190.37
  5151.1  192.91  5181.7  193.58  5208.5  196.44  5283.8  202.56  5309.3  205.21
  5324.6  207.64  5339.0  208.53  5354.5  209.80  5365.5  208.97  5391.6  211.19
#Mann=8,-1,0
  4544.9    0.05       0  4635.8    0.12       0  4850.6    0.04       0
  4965.0    0.05       0  5065.2    0.12       0  5098.0    0.05       0
  5102.0    0.12       0  5339.0    0.05       0
Bank Sta=5098,5102
Exp/Cntr=0.3,0.1

Type RM Length L Ch R = 1,808,448,448,448
BEGIN DESCRIPTION:
TRIB 3 TO IRISH CREEK 1.0
END DESCRIPTION:
XS GIS Cut Line= 4
      2542849.09     13585969.00      2543218.54     13585768.99
      2543257.43     13585602.33      2542996.34     13584980.15
#Sta/Elev= 30
  4525.4  212.98  4587.4  206.17  4628.6  201.37  4634.5  199.98  4732.2  190.36
  4776.0  189.31  4831.3  186.81  4895.9  184.74  4944.8  184.52  4970.2  184.29
  4988.7  182.67  4988.9  182.17  4992.7  182.67  5001.0  183.68  5031.8  182.96
  5078.3  183.37  5162.1  183.39  5201.0  184.42  5295.1  185.64  5384.9  185.97
  5439.3  187.75  5511.4  189.74  5536.7  190.54  5598.7  194.33  5622.5  196.20
  5657.1  200.71  5677.6  202.29  5727.7  206.35  5764.5  209.63  5791.4  210.90
#Mann=13,-1,0
  4525.4    0.12       0  4587.4    0.04       0  4831.3   0.013       0
  4944.8    0.12       0  4988.7    0.05       0  4992.7    0.12       0
  5078.3    0.04       0  5201.0    0.12       0  5295.1    0.04       0
  5439.3    0.05       0  5511.4    0.04       0  5677.6   0.013       0
  5727.7    0.04       0
Bank Sta=4988.7,4992.7
Exp/Cntr=0.3,0.1

Type RM Length L Ch R = 1,360,0,0,0
BEGIN DESCRIPTION:
LGII3959
END DESCRIPTION:
XS GIS Cut Line= 4
      2542862.99     13586099.55      2543587.98     13585863.44
      2543601.87     13585321.77      2543405.23     13584668.13
#Sta/Elev= 30
  4149.2  211.41  4224.9  206.61  4274.6  199.34  4319.6  195.64  4351.1  194.05
  4401.0  189.62  4516.1  184.59  4624.6  182.20  4636.2  182.93  4719.2  180.23
  4871.8  178.79  4898.0  178.08  4960.1  178.57  4990.7  176.41  4991.0  175.91
  4994.7  176.41  5010.1  177.93  5050.0  177.36  5086.5  178.45  5320.2  179.07
  5382.9  178.06  5410.3  176.49  5462.9  178.37  5534.2  178.93  5595.0  180.73
  5836.5  182.33  5930.5  184.68  5972.3  186.71  6066.3  193.43  6136.1  194.96
#Mann=8,-1,0
  4149.2    0.12       0  4401.0    0.04       0  4516.1    0.12       0
  4871.8    0.04       0  4990.7    0.04       0  4994.7    0.04       0
  5050.0    0.12       0  5086.5    0.04       0
Bank Sta=4990.7,4994.7
Exp/Cntr=0.3,0.1

Chan Stop Cuts=-1