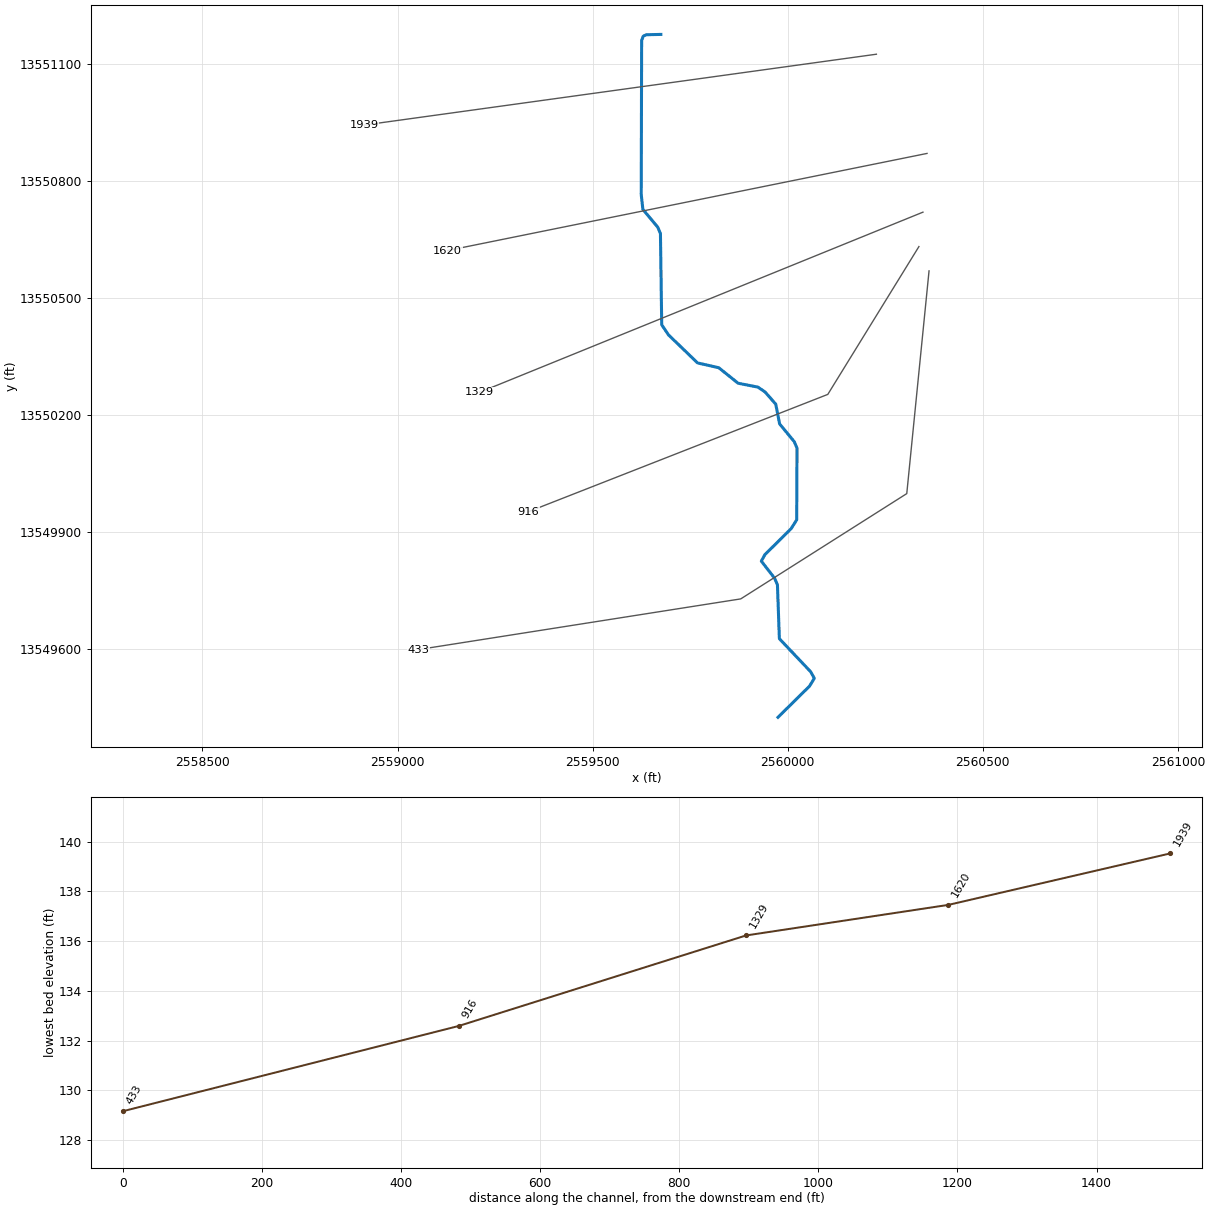
--- TRIB 3 TO PRICE CREEK.prj (project) ---

Proj Title=TRIB 3 TO PRICE CREEK Base Level Engineering
Current Plan=p01
Default Exp/Contr=0.3,0.1
English Units
Geom File=g01
Flow File=f01
Plan File=p01
BEGIN DESCRIPTION:
TRIB 3 TO PRICE CREEK
END DESCRIPTION:

--- TRIB 3 TO PRICE CREEK.p01 (plan) ---

Plan Title=Multiple Run
Short Identifier=Multiple
Geom File=g01
Flow File=f01
Subcritical Flow
K Sum by GR= 0
Std Step Tol= 0.01
Critical Tol= 0.01
Num of Std Step Trials= 20
Max Error Tol= 0.3
Flow Tol Ratio= 0.001
Split Flow NTrial= 30
Split Flow Tol= 0.02
Split Flow Ratio= 0.02
Log Output Level= 0
Friction Slope Method= 1
Unsteady Friction Slope Method= 2
Unsteady Bridges Friction Slope Method= 1
Parabolic Critical Depth
Global Vel Dist=  1 , 1 , 1
Global Log Level= 0
CheckData=True
Encroach Param= -1, 0, 0, 0
BEGIN DESCRIPTION:
Multiple Run
END DESCRIPTION:

--- TRIB 3 TO PRICE CREEK.f01 (steady flow) ---

Flow Title=Multiple
Number of Profiles=7
Profile Names=10-year,25-year,50-year,1pct_min,100-year,1pct_plu,500-year
River Rch & RM= TRIB 3 TO PRICE ,Reach-1,1939
     440     690     911     585    1166    2327    1887
Boundary for River Rch & Prof#=TRIB 3 TO PRICE ,Reach-1,1
Up Type=0
Dn Type=3
Dn Slope=0.005
Boundary for River Rch & Prof#=TRIB 3 TO PRICE ,Reach-1,2
Up Type=0
Dn Type=3
Dn Slope=0.005
Boundary for River Rch & Prof#=TRIB 3 TO PRICE ,Reach-1,3
Up Type=0
Dn Type=3
Dn Slope=0.005
Boundary for River Rch & Prof#=TRIB 3 TO PRICE ,Reach-1,4
Up Type=0
Dn Type=3
Dn Slope=0.005
Boundary for River Rch & Prof#=TRIB 3 TO PRICE ,Reach-1,5
Up Type=0
Dn Type=3
Dn Slope=0.005
Boundary for River Rch & Prof#=TRIB 3 TO PRICE ,Reach-1,6
Up Type=0
Dn Type=3
Dn Slope=0.005
Boundary for River Rch & Prof#=TRIB 3 TO PRICE ,Reach-1,7
Up Type=0
Dn Type=3
Dn Slope=0.005

--- TRIB 3 TO PRICE CREEK.g01 (geometry) ---

Geom Title=Existing Conditions

River Reach=TRIB 3 TO PRICE ,Reach-1
Reach XY= 30
      2559675.00     13551175.00      2559637.43     13551174.17
      2559629.63     13551170.37      2559625.61     13551159.39
      2559624.55     13550764.81      2559628.78     13550726.57
      2559666.86     13550681.06      2559673.78     13550664.50
      2559677.05     13550430.84      2559694.59     13550404.80
      2559768.93     13550333.13      2559823.26     13550320.81
      2559872.84     13550281.11      2559923.58     13550271.14
      2559942.06     13550258.51      2559969.27     13550227.55
      2559979.23     13550176.78      2560016.91     13550131.08
      2560023.80     13550114.50      2560022.93     13549930.85
      2560008.50     13549908.24      2559941.33     13549841.69
      2559932.33     13549825.10      2559966.52     13549781.19
      2559973.60     13549764.56      2559978.57     13549626.47
      2560058.78     13549541.65      2560068.02     13549524.99
      2560056.00     13549505.00      2559975.00     13549425.00

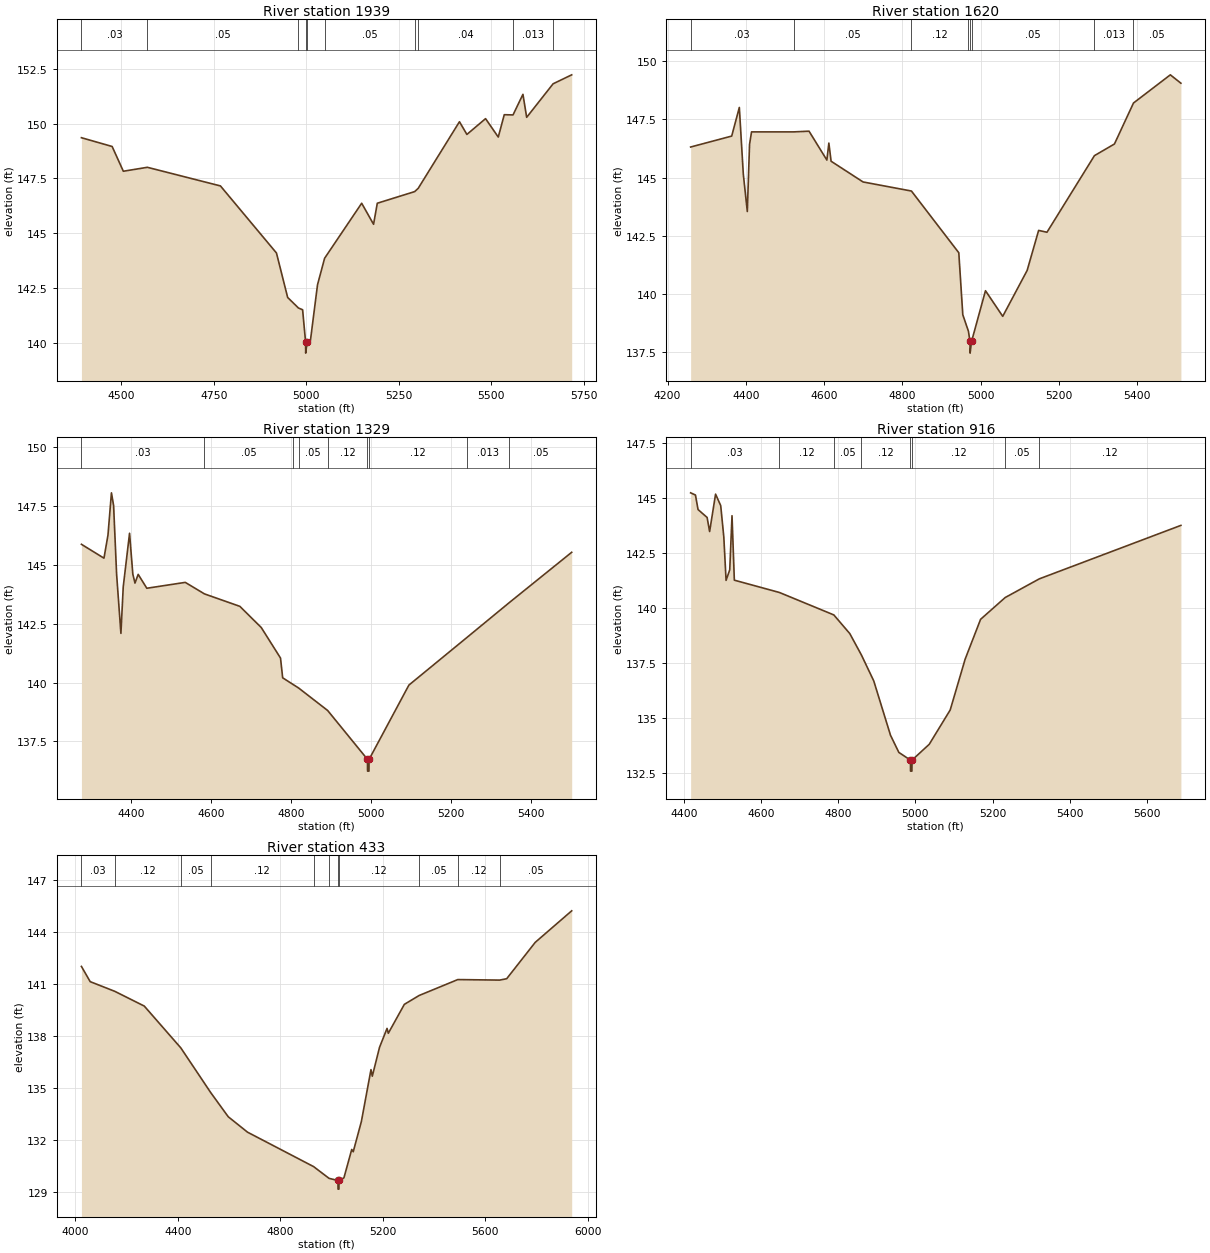
Type RM Length L Ch R = 1,1939,319,319,319
BEGIN DESCRIPTION:
LGII3042
END DESCRIPTION:
XS GIS Cut Line= 2
      2560227.22     13551124.26      2558914.42     13550942.65
#Sta/Elev= 30
  4392.0  149.36  4475.0  148.96  4505.3  147.83  4570.2  148.01  4767.8  147.16
  4919.2  144.10  4949.5  142.07  4978.6  141.59  4989.9  141.51  4998.0  140.03
  4998.2  139.53  5002.0  140.03  5011.0  140.10  5030.2  142.65  5049.4  143.86
  5149.6  146.37  5181.7  145.41  5191.8  146.37  5292.7  146.90  5302.4  147.05
  5413.9  150.09  5434.0  149.51  5484.5  150.23  5518.8  149.39  5535.0  150.41
  5558.7  150.40  5585.5  151.34  5595.6  150.29  5667.0  151.82  5717.3  152.23
#Mann=10,-1,0
  4392.0    0.03       0  4570.2    0.05       0  4978.6    0.12       0
  4998.0    0.05       0  5002.0    0.12       0  5049.4    0.05       0
  5292.7   0.013       0  5302.4    0.04       0  5558.7   0.013       0
  5667.0    0.05       0
Bank Sta=4998,5002
Exp/Cntr=0.3,0.1

Type RM Length L Ch R = 1,1620,291,291,291
BEGIN DESCRIPTION:
LGII3041
END DESCRIPTION:
XS GIS Cut Line= 2
      2560356.98     13550870.01      2559128.52     13550621.21
#Sta/Elev= 30
  4258.9  146.31  4363.9  146.78  4383.4  148.01  4393.6  145.14  4403.8  143.54
  4409.5  146.42  4414.6  146.96  4522.7  146.96  4561.6  146.99  4607.2  145.75
  4612.3  146.48  4618.0  145.70  4699.7  144.81  4823.4  144.42  4944.5  141.77
  4954.7  139.11  4969.1  138.40  4973.1  137.96  4973.4  137.46  4977.1  137.96
  5012.7  140.14  5056.8  139.04  5119.2  141.01  5148.6  142.73  5169.9  142.65
  5291.3  145.94  5342.4  146.44  5391.1  148.20  5485.3  149.41  5512.3  149.05
#Mann=8,-1,0
  4258.9    0.03       0  4522.7    0.05       0  4823.4    0.12       0
  4969.1    0.05       0  4973.1    0.05       0  4977.1    0.05       0
  5291.3   0.013       0  5391.1    0.05       0
Bank Sta=4973.1,4977.1
Exp/Cntr=0.3,0.1

Type RM Length L Ch R = 1,1329,413,413,413
BEGIN DESCRIPTION:
LGII3040
END DESCRIPTION:
XS GIS Cut Line= 2
      2560346.53     13550719.51      2559210.18     13550257.70
#Sta/Elev= 30
  4275.0  145.88  4331.4  145.29  4341.4  146.27  4350.1  148.07  4355.5  147.53
  4363.0  144.61  4373.8  142.09  4379.6  144.07  4395.4  146.35  4403.6  144.61
  4409.0  144.23  4417.0  144.60  4438.6  144.01  4534.8  144.26  4582.9  143.77
  4671.4  143.24  4724.9  142.34  4773.1  141.04  4778.5  140.20  4805.1  139.91
  4818.1  139.77  4891.0  138.81  4990.7  136.73  4990.9  136.23  4994.4  136.23
  4994.7  136.73  5094.3  139.89  5240.5  141.93  5345.5  143.40  5501.6  145.54
#Mann=9,-1,0
  4275.0    0.03       0  4582.9    0.05       0  4805.1    0.12       0
  4818.1    0.05       0  4891.0    0.12       0  4990.7    0.05       0
  4994.7    0.12       0  5240.5   0.013       0  5345.5    0.05       0
Bank Sta=4990.7,4994.7
Exp/Cntr=0.3,0.1

Type RM Length L Ch R = 1,916,483,483,483
BEGIN DESCRIPTION:
LGII3039
END DESCRIPTION:
XS GIS Cut Line= 3
      2560336.19     13550631.32      2560102.67     13550252.51
      2559334.74     13549951.56
#Sta/Elev= 30
  4417.8  145.24  4430.3  145.14  4437.0  144.48  4460.5  144.12  4467.0  143.48
  4482.4  145.18  4495.7  144.66  4503.7  143.24  4509.6  141.26  4519.1  141.74
  4525.0  144.20  4531.0  141.27  4647.8  140.71  4788.7  139.69  4830.1  138.84
  4860.1  137.87  4892.1  136.69  4935.5  134.22  4957.1  133.44  4987.2  133.09
  4987.4  132.59  4990.9  132.59  4991.2  133.09  5035.8  133.81  5090.1  135.37
  5128.8  137.68  5168.8  139.49  5232.5  140.48  5320.9  141.33  5687.6  143.76
#Mann=8,-1,0
  4417.8    0.03       0  4647.8    0.12       0  4788.7    0.05       0
  4860.1    0.12       0  4987.2    0.05       0  4991.2    0.12       0
  5232.5    0.05       0  5320.9    0.12       0
Bank Sta=4987.2,4991.2
Exp/Cntr=0.3,0.1

Type RM Length L Ch R = 1,433,0,0,0
BEGIN DESCRIPTION:
LGII3038
END DESCRIPTION:
XS GIS Cut Line= 4
      2560362.12     13550569.00      2560305.04     13549998.25
      2559879.55     13549728.42      2559054.52     13549598.70
#Sta/Elev= 30
  4024.1  142.02  4058.3  141.14  4154.5  140.58  4269.3  139.73  4412.1  137.31
  4528.7  134.73  4596.8  133.34  4671.9  132.45  4929.9  130.46  4990.3  129.78
  5024.9  129.66  5025.2  129.16  5028.7  129.16  5028.9  129.66  5048.1  129.81
  5078.6  131.45  5084.5  131.32  5116.3  133.07  5153.7  136.06  5158.8  135.68
  5187.1  137.35  5216.3  138.44  5221.3  138.16  5283.9  139.83  5341.4  140.34
  5492.3  141.26  5655.8  141.23  5683.1  141.31  5794.5  143.41  5936.7  145.23
#Mann=11,-1,0
  4024.1    0.03       0  4154.5    0.12       0  4412.1    0.05       0
  4528.7    0.12       0  4929.9    0.05       0  4990.3    0.12       0
  5024.9    0.05       0  5028.9    0.12       0  5341.4    0.05       0
  5492.3    0.12       0  5655.8    0.05       0
Bank Sta=5024.9,5028.9
Exp/Cntr=0.3,0.1

Chan Stop Cuts=-1