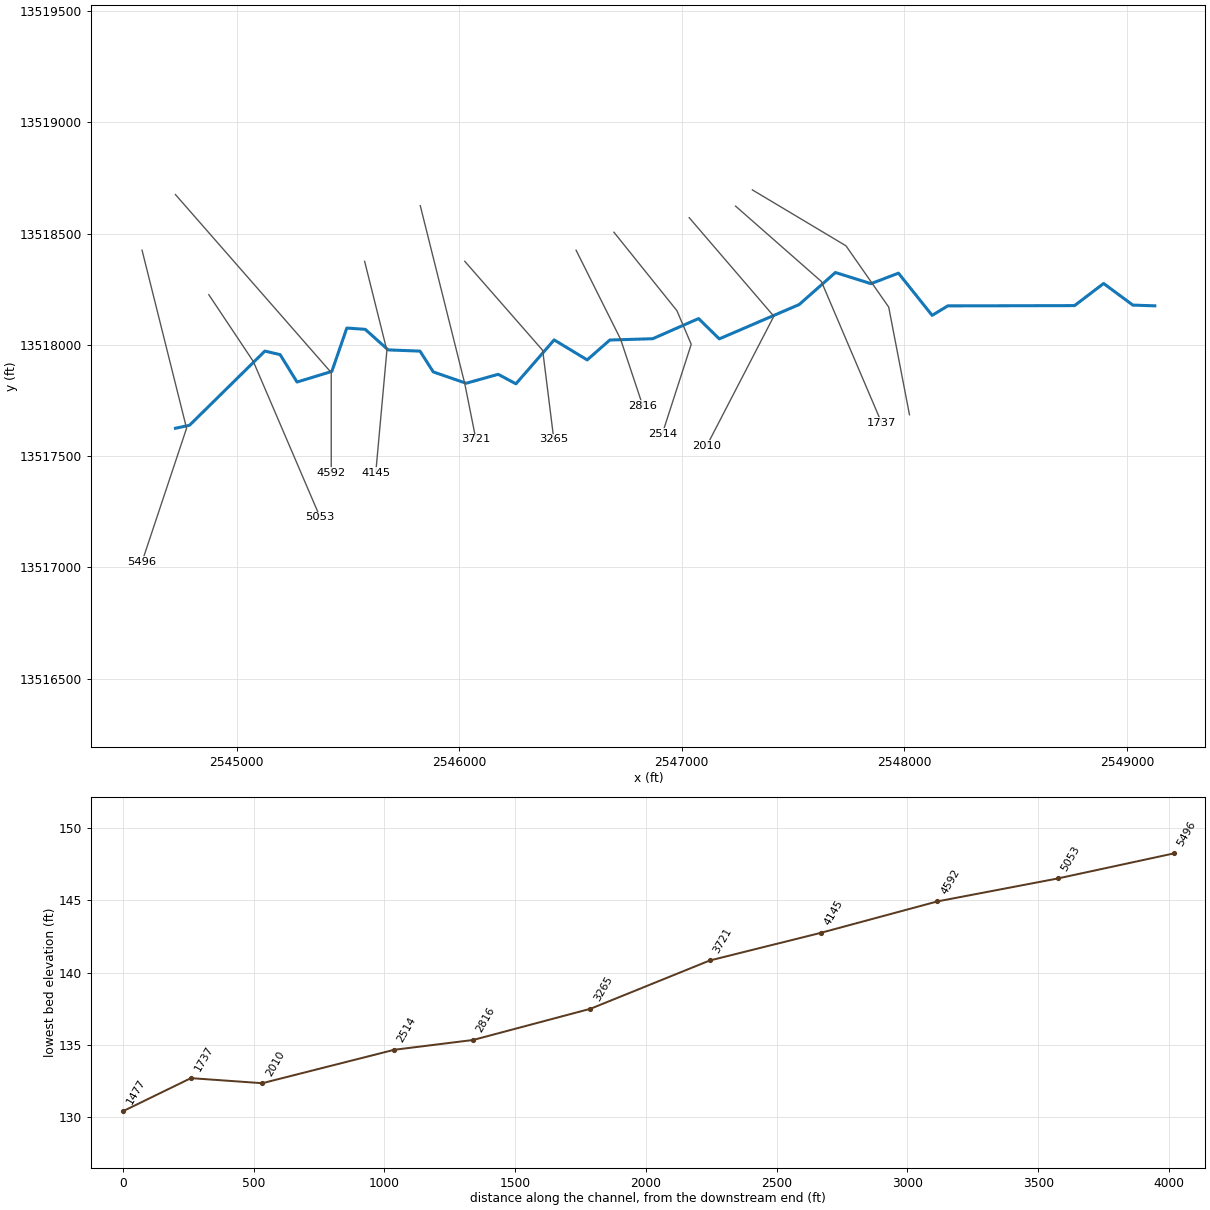
--- TRIB 3 TO ROCKY CREEK.prj (project) ---

Proj Title=TRIB 3 TO ROCKY CREEK Base Level Engineering
Current Plan=p01
Default Exp/Contr=0.3,0.1
English Units
Geom File=g01
Flow File=f01
Plan File=p01
Y Axis Title=Elevation
X Axis Title(PF)=Main Channel Distance
X Axis Title(XS)=Station
BEGIN DESCRIPTION:
TRIB 3 TO ROCKY CREEK
END DESCRIPTION:
DSS Export Rating Curves= 0
DSS Export Rating Curve Sorted= 0
DSS Export Volume Flow Curves= 0
DXF OffsetX= 0
DXF OffsetY= 0
DXF ScaleX= 1
DXF ScaleY= 10

--- TRIB 3 TO ROCKY CREEK.p01 (plan) ---

Plan Title=Multiple Run
Short Identifier=Multiple
Geom File=g01
Flow File=f01
Subcritical Flow
K Sum by GR= 0
Std Step Tol= 0.01
Critical Tol= 0.01
Num of Std Step Trials= 20
Max Error Tol= 0.3
Flow Tol Ratio= 0.001
Split Flow NTrial= 30
Split Flow Tol= 0.02
Split Flow Ratio= 0.02
Log Output Level= 0
Friction Slope Method= 1
Unsteady Friction Slope Method= 2
Unsteady Bridges Friction Slope Method= 1
Parabolic Critical Depth
Global Vel Dist=  1 , 1 , 1
Global Log Level= 0
CheckData=True
Encroach Param= -1, 0, 0, 0
BEGIN DESCRIPTION:
Multiple Run
END DESCRIPTION:

--- TRIB 3 TO ROCKY CREEK.f01 (steady flow) ---

Flow Title=Multiple
Number of Profiles=7
Profile Names=10-year,25-year,50-year,1pct_min,100-year,1pct_plu,500-year
River Rch & RM= TRIB 3 TO ROCKY ,Reach-1,5496
     942    1541    2090    1372    2737    5461    4639
River Rch & RM= TRIB 3 TO ROCKY ,Reach-1,5053
    1214    2008    2742    1810    3611    7205    6192
Boundary for River Rch & Prof#=TRIB 3 TO ROCKY ,Reach-1,1
Up Type=0
Dn Type=3
Dn Slope=0.005
Boundary for River Rch & Prof#=TRIB 3 TO ROCKY ,Reach-1,2
Up Type=0
Dn Type=3
Dn Slope=0.005
Boundary for River Rch & Prof#=TRIB 3 TO ROCKY ,Reach-1,3
Up Type=0
Dn Type=3
Dn Slope=0.005
Boundary for River Rch & Prof#=TRIB 3 TO ROCKY ,Reach-1,4
Up Type=0
Dn Type=3
Dn Slope=0.005
Boundary for River Rch & Prof#=TRIB 3 TO ROCKY ,Reach-1,5
Up Type=0
Dn Type=3
Dn Slope=0.005
Boundary for River Rch & Prof#=TRIB 3 TO ROCKY ,Reach-1,6
Up Type=0
Dn Type=3
Dn Slope=0.005
Boundary for River Rch & Prof#=TRIB 3 TO ROCKY ,Reach-1,7
Up Type=0
Dn Type=3
Dn Slope=0.005

--- TRIB 3 TO ROCKY CREEK.g01 (geometry) ---

Geom Title=Existing Conditions
Program Version=4.10

River Reach=TRIB 3 TO ROCKY ,Reach-1
Reach XY= 30
        2544725.       13517625.      2544788.27     13517638.47
      2545126.76      13517971.7      2545195.47     13517955.73
      2545271.33     13517832.69      2545427.71      13517880.4
      2545495.02     13518075.23      2545577.36     13518069.62
      2545680.86     13517977.08      2545823.73     13517971.51
      2545883.35     13517878.19      2546030.97     13517827.17
      2546175.01      13517867.4      2546254.84     13517824.67
      2546426.43     13518021.99        2546575.      13517932.1
      2546676.46     13518021.44      2546869.06     13518027.26
       2547075.3     13518117.74      2547168.49     13518026.61
       2547527.3     13518180.83      2547690.22     13518324.76
        2547850.     13518274.61      2547973.38     13518321.87
      2548124.68     13518132.23      2548194.98     13518174.81
      2548764.56     13518176.06      2548895.16     13518275.47
      2549026.41      13518178.4        2549125.       13518175.

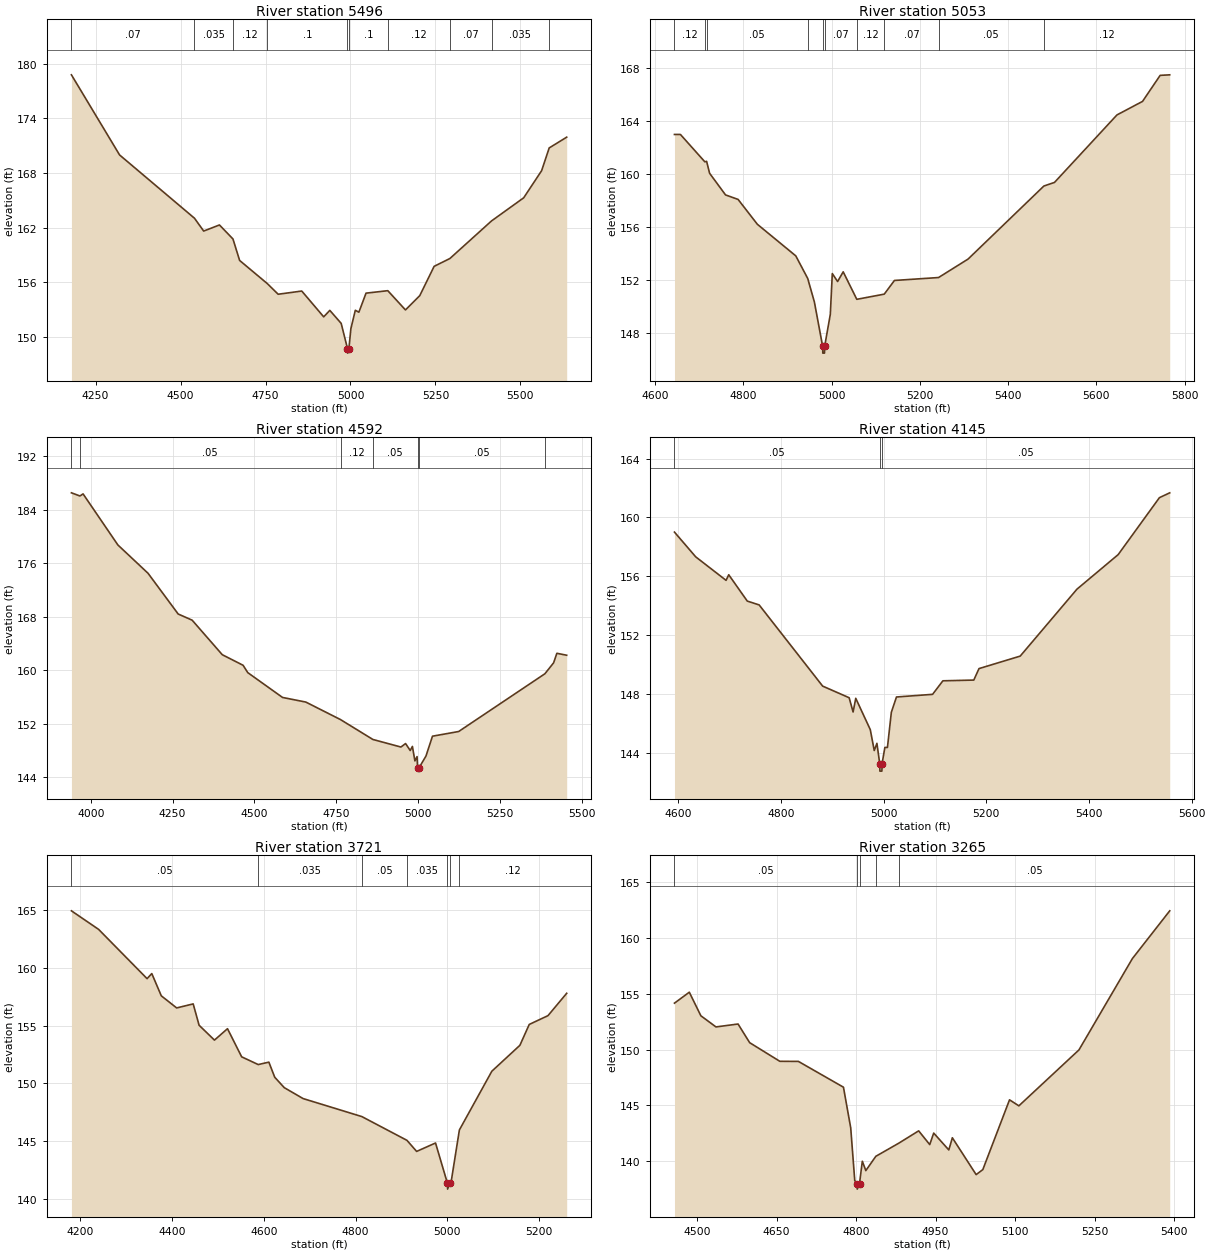
Type RM Length L Ch R = 1 ,5496    ,443,443,443
BEGIN DESCRIPTION:
TRIB 3 TO ROCKY CREEK 9.0
END DESCRIPTION:
XS GIS Cut Line= 3
        2544575.     13518425.01        2544775.       13517625.
        2544575.     13517024.99
#Sta/Elev= 30
    4179  178.78  4320.7  169.99    4541  163.05  4568.1  161.64  4614.5  162.31
  4654.3  160.77  4673.8  158.42  4755.2  155.88  4787.2  154.71  4856.7  155.06
  4921.2  152.23  4939.2  152.94  4972.7  151.51  4991.2  148.75  4991.5  148.25
  4995.4  148.75  5001.1  150.92  5014.2  152.95  5024.7  152.74  5045.8  154.83
  5109.8   155.1  5161.7  152.99  5203.9  154.56  5246.1  157.77  5292.5  158.63
  5414.9  162.75  5509.6  165.29  5562.3  168.26  5584.6  170.76  5636.1  171.94
#Mann= 10 ,-1 , 0
    4179     .07       0    4541    .035       0  4654.3     .12       0
  4755.2      .1       0  4991.2     .05       0  4995.4      .1       0
  5109.8     .12       0  5292.5     .07       0  5414.9    .035       0
  5584.6     .07       0
Bank Sta=4991.2,4995.4
XS Rating Curve= 0 ,0
Exp/Cntr=0.3,0.1

Type RM Length L Ch R = 1 ,5053    ,461,461,461
BEGIN DESCRIPTION:
TRIB 3 TO ROCKY CREEK 8.0
END DESCRIPTION:
XS GIS Cut Line= 3
      2544874.99     13518225.01        2545075.       13517925.
      2545374.98     13517225.04
#Sta/Elev= 30
  4644.2  162.98  4657.7  162.98  4713.1  160.92    4717  160.96  4723.8  160.06
  4759.9  158.43  4788.4  158.09    4832  156.22  4919.1  153.84  4946.1  152.14
  4961.2  150.37    4980  147.02  4980.3  146.52  4984.1  146.52  4984.4  147.02
  4997.3  149.44  5001.8  152.51  5013.8  151.91  5026.5  152.64  5057.3  150.57
  5119.5  150.96  5142.6  151.99  5242.5  152.21  5309.4   153.6  5481.2   159.1
  5505.2  159.37  5646.7  164.45  5704.7  165.47  5744.6  167.43  5766.3  167.47
#Mann= 10 ,-1 , 0
  4644.2     .12       0  4713.1     .07       0    4717     .05       0
  4946.1     .07       0    4980     .05       0  4984.4     .07       0
  5057.3     .12       0  5119.5     .07       0  5242.5     .05       0
  5481.2     .12       0
Bank Sta=4980,4984.4
XS Rating Curve= 0 ,0
Exp/Cntr=0.3,0.1

Type RM Length L Ch R = 1 ,4592    ,447,447,447
BEGIN DESCRIPTION:
TRIB 3 TO ROCKY CREEK 7.0
END DESCRIPTION:
XS GIS Cut Line= 3
      2544724.98     13518675.02        2545425.       13517875.
        2545425.     13517425.05
#Sta/Elev= 30
    3941  186.52    3967  186.05  3976.6  186.36  4082.9  178.73    4175   174.5
  4267.1  168.41  4309.8  167.49  4401.8  162.33  4465.4  160.75  4479.7  159.65
    4586  155.94  4657.1  155.25  4763.1  152.63    4862  149.66  4947.6  148.53
  4961.8  149.05    4976  148.01  4982.7  148.62  4990.3  146.46  4996.9   147.1
  4998.5  145.43  4998.8  144.93  5002.9  145.43    5024  147.17    5044  150.15
    5124  150.85  5387.4  159.48    5414  161.11    5424  162.54    5454  162.25
#Mann= 7 ,-1 , 0
    3941     .12       0    3967     .05       0  4763.1     .12       0
    4862     .05       0  4998.5     .05       0  5002.9     .05       0
  5387.4     .12       0
Bank Sta=4998.5,5002.9
XS Rating Curve= 0 ,0
Exp/Cntr=0.3,0.1

Type RM Length L Ch R = 1 ,4145    ,424,424,424
BEGIN DESCRIPTION:
TRIB 3 TO ROCKY CREEK 6.0
END DESCRIPTION:
XS GIS Cut Line= 3
        2545575.     13518375.02        2545675.       13517975.
        2545625.       13517425.
#Sta/Elev= 30
  4592.7     159    4634  157.32  4693.2  155.72  4698.4   156.1  4734.5  154.31
  4757.6  154.05  4881.3  148.53  4932.9  147.74  4940.6  146.77  4945.8   147.7
  4974.1  145.57  4981.8  144.15    4987  144.64  4992.5  143.25  4992.8  142.75
  4996.7  142.75    4997  143.25  5002.5  144.36  5007.5  144.36  5015.1  146.75
  5025.1  147.79  5095.4  147.97  5115.5  148.89  5175.7  148.94  5185.8  149.72
  5266.1  150.57  5376.6  155.12  5456.9  157.47  5537.2  161.34  5557.3  161.67
#Mann= 3 ,-1 , 0
  4592.7     .05       0  4992.5     .05       0    4997     .05       0
Bank Sta=4992.5,4997
XS Rating Curve= 0 ,0
Exp/Cntr=0.3,0.1

Type RM Length L Ch R = 1 ,3721    ,456,456,456
BEGIN DESCRIPTION:
TRIB 3 TO ROCKY CREEK 5.0
END DESCRIPTION:
XS GIS Cut Line= 3
        2545825.       13518625.        2546025.       13517825.
        2546075.     13517574.98
#Sta/Elev= 30
  4180.7  164.97    4240  163.36  4345.6  159.09  4355.9  159.53  4376.6   157.6
  4410.1  156.55  4446.1   156.9    4459  155.05  4492.5  153.76  4520.9  154.75
  4551.8  152.31  4587.9  151.64  4611.1  151.85  4623.9  150.54  4644.6  149.64
  4685.8  148.69  4813.8  147.13  4912.1  145.07  4933.2  144.11  4974.4  144.84
  5000.4  141.34  5000.7  140.84    5005  141.34  5007.9  141.34  5026.4  145.97
  5097.1  151.06  5158.3  153.31  5178.7  155.12  5219.5  155.88  5260.3  157.82
#Mann= 7 ,-1 , 0
  4180.7     .05       0  4587.9    .035       0  4813.8     .05       0
  4912.1    .035       0  5000.4    .035       0    5005    .035       0
  5026.4     .12       0
Bank Sta=5000.4,5005
XS Rating Curve= 0 ,0
Exp/Cntr=0.3,0.1

Type RM Length L Ch R = 1 ,3265    ,449,449,449
BEGIN DESCRIPTION:
TRIB 3 TO ROCKY CREEK 4.0
END DESCRIPTION:
XS GIS Cut Line= 3
      2546025.02     13518374.98        2546375.       13517975.
        2546425.       13517575.
#Sta/Elev= 30
  4457.3  154.16  4485.3  155.14  4507.1  153.03  4535.6  152.03  4577.3  152.29
  4599.2  150.62  4656.1  148.95  4691.2  148.94  4776.2  146.63  4789.9  142.99
  4797.5  138.27  4801.8     138  4802.2   137.5  4806.5     138  4811.8     140
  4818.4  139.16  4837.3  140.44  4881.1  141.63  4918.1  142.72    4939  141.49
  4946.5  142.52    4975  141.01  4981.7   142.1  5026.6   138.8  5039.2  139.25
  5089.6   145.5  5107.2  144.96  5220.6  149.97  5321.4  158.15  5391.9  162.43
#Mann= 5 ,-1 , 0
  4457.3     .05       0  4801.8     .05       0  4806.5     .05       0
  4837.3     .12       0  4881.1     .05       0
Bank Sta=4801.8,4806.5
XS Rating Curve= 0 ,0
Exp/Cntr=0.3,0.1

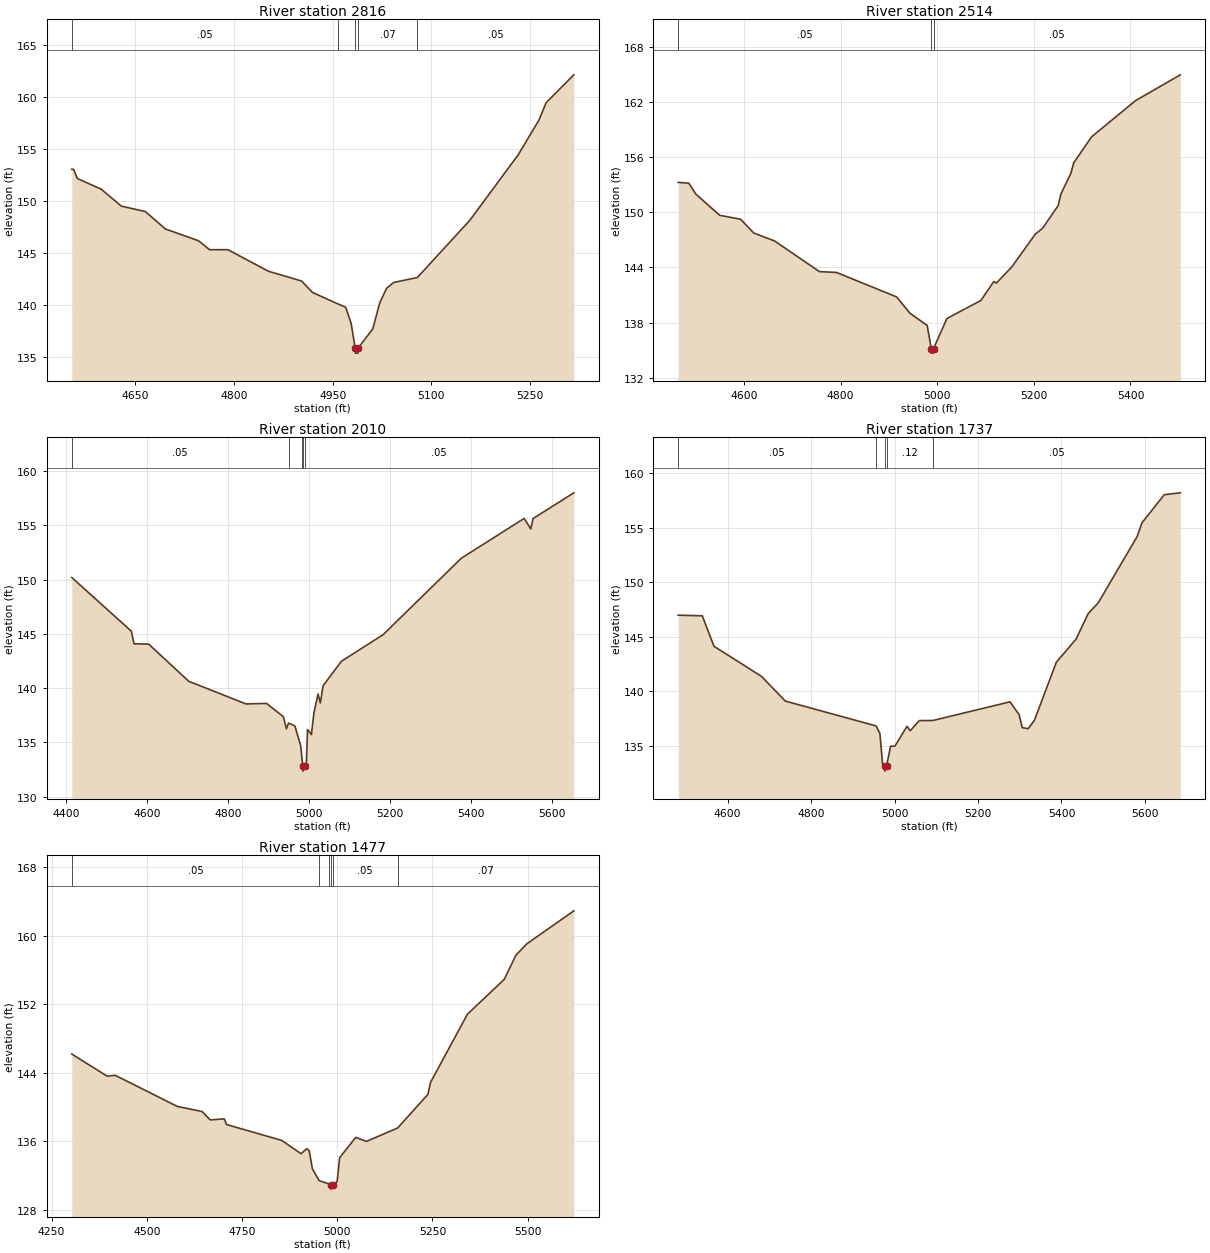
Type RM Length L Ch R = 1 ,2816    ,302,302,302
BEGIN DESCRIPTION:
TRIB 3 TO ROCKY CREEK 3.0
END DESCRIPTION:
XS GIS Cut Line= 3
      2546525.02     13518424.97        2546725.       13518025.
        2546825.     13517725.01
#Sta/Elev= 30
  4553.3  153.01  4556.1  153.01  4561.7  152.13    4598   151.1  4628.7  149.47
  4665.1  148.95  4695.8  147.27  4746.1  146.14  4762.9  145.28  4790.8  145.28
  4852.3  143.21  4902.7  142.27  4919.4  141.17  4958.7  140.05  4969.7  139.76
  4978.1   138.2  4984.2  135.84  4984.5  135.34  4988.5  135.34  4988.9  135.84
    5011  137.67  5021.6  140.18  5032.1  141.58  5042.6  142.13  5078.8  142.61
  5158.6  148.11  5232.4  154.43    5264  157.78  5274.5  159.41  5316.7  162.09
#Mann= 5 ,-1 , 0
  4553.3     .05       0  4958.7     .07       0  4984.2     .05       0
  4988.9     .07       0  5078.8     .05       0
Bank Sta=4984.2,4988.9
XS Rating Curve= 0 ,0
Exp/Cntr=0.3,0.1

Type RM Length L Ch R = 1 ,2514    ,504,504,504
BEGIN DESCRIPTION:
Mapping XS 0c6a4939
END DESCRIPTION:
XS GIS Cut Line= 4
      2546695.12     13518505.63      2546978.11      13518153.2
      2547042.34     13518002.16      2546912.23     13517599.68
#Sta/Elev= 30
  4464.1  153.28    4486  153.19  4500.4  152.01    4550  149.69  4593.2  149.26
  4620.4  147.76  4663.6  146.89  4756.4  143.55  4791.6  143.46  4916.1  140.79
  4943.9     139  4979.3  137.69  4987.8  135.16  4988.1  134.66  4992.2  134.66
  4992.5  135.16  5020.2  138.44  5090.4   140.4  5117.2  142.47  5122.4  142.29
  5154.4  144.06  5203.3  147.65  5217.9  148.26  5250.5  150.75  5255.9  151.99
  5276.9  154.29  5282.5  155.41  5319.8  158.26  5410.6   162.2  5503.2  165.01
#Mann= 3 ,-1 , 0
  4464.1     .05       0  4987.8     .05       0  4992.5     .05       0
Bank Sta=4987.8,4992.5
XS Rating Curve= 0 ,0
Exp/Cntr=0.3,0.1

Type RM Length L Ch R = 1 ,2010    ,273,273,273
BEGIN DESCRIPTION:
Mapping XS edee0bf3
END DESCRIPTION:
XS GIS Cut Line= 3
      2547033.31     13518570.97      2547413.49      13518128.3
      2547111.42     13517544.99
#Sta/Elev= 30
  4413.9  150.19  4561.2  145.24  4567.8  144.08    4604  144.05  4702.8  140.63
  4844.4  138.54  4894.8  138.59  4936.6  137.37  4944.2  136.25  4949.5  136.78
  4965.1  136.52  4979.4   134.7  4983.8  133.13  4984.6  132.85    4985  132.35
  4989.4  132.85  4993.6   133.2  4996.3  136.18  5005.9  135.72  5012.4  137.78
  5022.4  139.46    5028  138.63  5034.9  140.22    5080  142.47    5183  144.92
  5376.5  151.97  5531.5  155.63    5548  154.67  5553.6  155.62  5654.3  157.99
#Mann= 5 ,-1 , 0
  4413.9     .05       0  4949.5     .12       0  4983.8     .05       0
  4984.6     .05       0  4989.4     .05       0
Bank Sta=4984.6,4989.4
XS Rating Curve= 0 ,0
Exp/Cntr=0.3,0.1

Type RM Length L Ch R = 1 ,1737    ,260,260,260
BEGIN DESCRIPTION:
Mapping XS e7675540
END DESCRIPTION:
XS GIS Cut Line= 3
      2547241.62     13518623.09      2547627.03     13518284.55
      2547897.67      13517649.6
#Sta/Elev= 30
  4481.6  146.99  4539.3  146.93  4567.3  144.14  4681.2  141.38  4738.1  139.12
  4955.8  136.84  4964.9  136.15  4971.5  133.28  4976.2   133.2  4976.5   132.7
    4981   133.2  4990.5  134.98  5000.8  134.99  5029.9  136.81  5037.6   136.4
  5059.3  137.33  5091.9  137.34  5276.7  139.05  5298.5  137.87    5306  136.69
  5320.2  136.59  5335.1  137.35  5387.8  142.69    5435  144.79  5464.1  147.14
  5487.7   148.1  5581.1  154.17  5593.1  155.46  5646.3  158.03  5684.8   158.2
#Mann= 5 ,-1 , 0
  4481.6     .05       0  4955.8     .12       0  4976.2     .05       0
    4981     .12       0  5091.9     .05       0
Bank Sta=4976.2,4981
XS Rating Curve= 0 ,0
Exp/Cntr=0.3,0.1

Type RM Length L Ch R = 1 ,1477    ,0,0,0
BEGIN DESCRIPTION:
TRIB 3 TO ROCKY CREEK 1.0
END DESCRIPTION:
XS GIS Cut Line= 4
      2547317.15     13518695.92      2547737.62     13518444.72
       2547929.6     13518169.36      2548022.86     13517685.64
#Sta/Elev= 30
  4303.1  146.18  4396.1  143.59  4417.5  143.69  4580.2  140.06  4645.2  139.47
  4666.6  138.49  4703.5  138.61  4709.4  137.95  4854.6  136.09  4905.2  134.54
    4920  135.14  4926.6  134.87  4934.8  132.79  4952.5   131.4  4979.7     131
  4982.6  130.91  4983.1  130.41  4988.2  130.91  4999.8   131.3  5006.4  134.08
  5048.6  136.45  5076.8  135.98  5158.8  137.55  5238.1  141.47    5245  142.87
  5341.9  150.83  5438.5  154.89  5469.1  157.71  5497.5  159.03  5621.2  162.89
#Mann= 6 ,-1 , 0
  4303.1     .05       0  4952.5     .12       0  4979.7     .05       0
  4982.6     .05       0  4988.2     .05       0  5158.8     .07       0
Bank Sta=4982.6,4988.2
XS Rating Curve= 0 ,0
Exp/Cntr=0.3,0.1

Chan Stop Cuts=-1
Use User Specified Reach Order=0
Composite Channel Slope=5