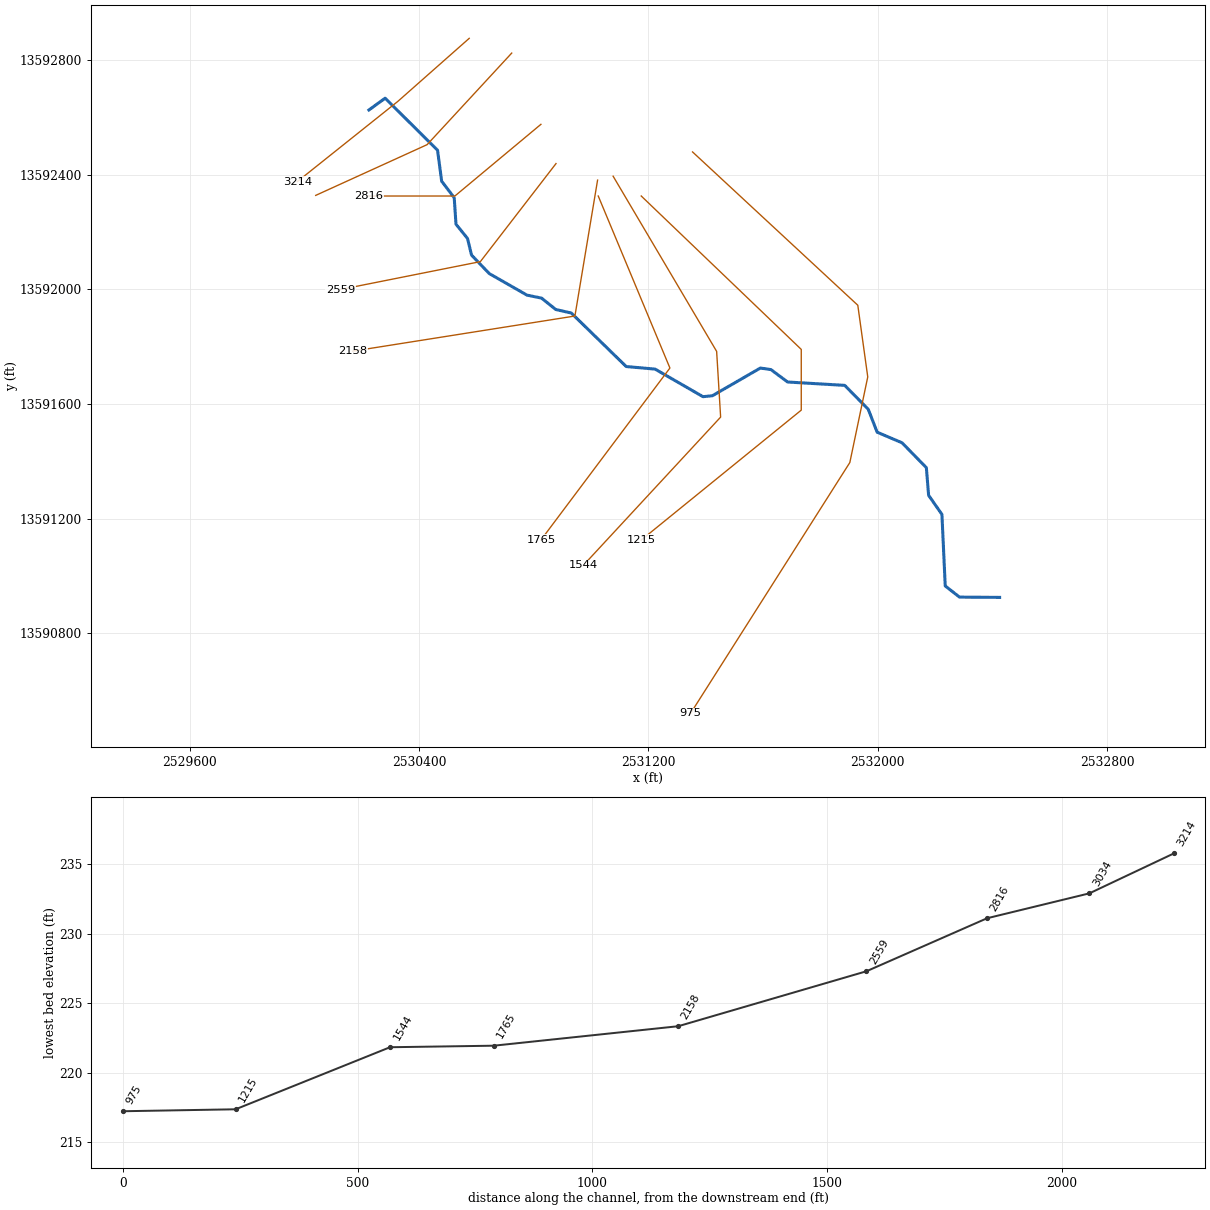
--- TRIB 3 TO SANDY FORK.prj (project) ---

Proj Title=TRIB 3 TO SANDY FORK Base Level Engineering
Current Plan=p01
Default Exp/Contr=0.3,0.1
English Units
Geom File=g01
Flow File=f01
Plan File=p01
Y Axis Title=Elevation
X Axis Title(PF)=Main Channel Distance
X Axis Title(XS)=Station
BEGIN DESCRIPTION:
TRIB 3 TO SANDY FORK
END DESCRIPTION:
DSS Export Rating Curves= 0
DSS Export Rating Curve Sorted= 0
DSS Export Volume Flow Curves= 0
DXF OffsetX= 0
DXF OffsetY= 0
DXF ScaleX= 1
DXF ScaleY= 10

--- TRIB 3 TO SANDY FORK.p01 (plan) ---

Plan Title=Multiple Run
Short Identifier=Multiple
Geom File=g01
Flow File=f01
Subcritical Flow
K Sum by GR= 0
Std Step Tol= 0.01
Critical Tol= 0.01
Num of Std Step Trials= 20
Max Error Tol= 0.3
Flow Tol Ratio= 0.001
Split Flow NTrial= 30
Split Flow Tol= 0.02
Split Flow Ratio= 0.02
Log Output Level= 0
Friction Slope Method= 1
Unsteady Friction Slope Method= 2
Unsteady Bridges Friction Slope Method= 1
Parabolic Critical Depth
Global Vel Dist=  1 , 1 , 1
Global Log Level= 0
CheckData=True
Encroach Param= -1, 0, 0, 0
BEGIN DESCRIPTION:
Multiple Run
END DESCRIPTION:

--- TRIB 3 TO SANDY FORK.f01 (steady flow) ---

Flow Title=Multiple
Number of Profiles=7
Profile Names=10-year,25-year,50-year,1pct_min,100-year,1pct_plu,500-year
River Rch & RM= TRIB 3 TO SANDY ,Reach-1,3214
     290     448     585     372     742    1481    1179
River Rch & RM= TRIB 3 TO SANDY ,Reach-1,1765
     540     868    1164     759    1514    3021    2531
Boundary for River Rch & Prof#=TRIB 3 TO SANDY ,Reach-1,1
Up Type=0
Dn Type=3
Dn Slope=0.005
Boundary for River Rch & Prof#=TRIB 3 TO SANDY ,Reach-1,2
Up Type=0
Dn Type=3
Dn Slope=0.005
Boundary for River Rch & Prof#=TRIB 3 TO SANDY ,Reach-1,3
Up Type=0
Dn Type=3
Dn Slope=0.005
Boundary for River Rch & Prof#=TRIB 3 TO SANDY ,Reach-1,4
Up Type=0
Dn Type=3
Dn Slope=0.005
Boundary for River Rch & Prof#=TRIB 3 TO SANDY ,Reach-1,5
Up Type=0
Dn Type=3
Dn Slope=0.005
Boundary for River Rch & Prof#=TRIB 3 TO SANDY ,Reach-1,6
Up Type=0
Dn Type=3
Dn Slope=0.005
Boundary for River Rch & Prof#=TRIB 3 TO SANDY ,Reach-1,7
Up Type=0
Dn Type=3
Dn Slope=0.005

--- TRIB 3 TO SANDY FORK.g01 (geometry) ---

Geom Title=Existing Conditions
Program Version=4.10

River Reach=TRIB 3 TO SANDY ,Reach-1
Reach XY= 30
        2530225.       13592625.      2530281.67     13592666.23
      2530464.48     13592484.79      2530478.86      13592376.6
      2530522.65     13592319.03      2530528.82     13592226.58
      2530568.86     13592177.17      2530583.13     13592118.93
      2530644.76     13592054.58      2530776.72     13591979.16
       2530827.2     13591968.92      2530876.74     13591929.19
      2530931.06     13591916.86      2531122.45     13591730.22
      2531223.43      13591721.2      2531390.39     13591625.07
      2531423.28     13591628.34      2531590.39     13591724.92
      2531627.18     13591719.63       2531685.5     13591676.24
      2531884.82     13591664.53      2531966.84     13591581.05
      2531997.86     13591501.16      2532084.69     13591464.22
      2532169.48     13591377.44      2532177.36     13591280.98
      2532223.78      13591214.5      2532235.32     13590964.82
      2532285.23     13590925.91        2532425.       13590925.

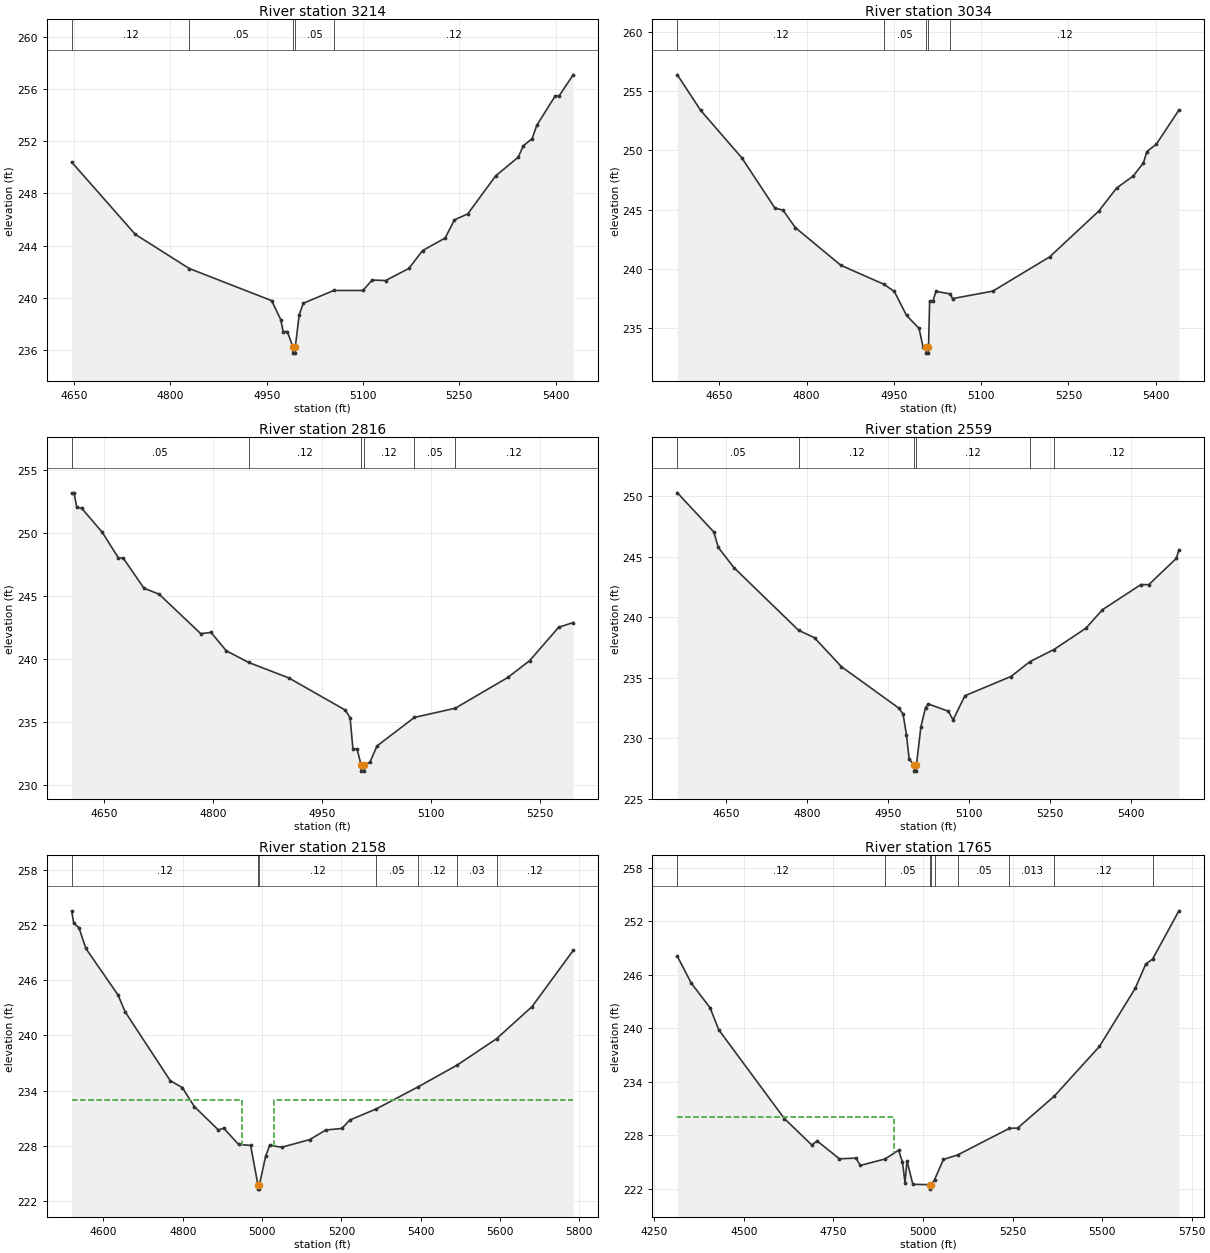
Type RM Length L Ch R = 1 ,3214    ,180,180,180
BEGIN DESCRIPTION:
TRIB 3_1 TO SANDY FORK 3.0
END DESCRIPTION:
XS GIS Cut Line= 3
      2530574.98     13592874.98      2530326.08     13592655.13
      2529975.03     13592375.02
#Sta/Elev= 30
  4646.2   250.4  4745.3  244.86  4829.5  242.24  4957.8  239.78    4972  238.32
  4975.7  237.41  4982.2  237.41  4990.7  236.26  4990.9  235.76  4994.4  235.76
  4994.7  236.26  5000.7  238.71  5007.1  239.58  5054.4  240.56    5100  240.56
  5114.4  241.36  5135.2  241.32  5171.6  242.25  5192.9  243.62  5228.1  244.58
  5242.5  245.97  5263.3  246.43  5306.5  249.33  5341.8  250.77  5349.8  251.65
  5363.5  252.19  5370.6   253.2  5399.4  255.46  5405.8  255.49  5427.4  257.08
#Mann= 5 ,-1 , 0
  4646.2     .12       0  4829.5     .05       0  4990.7     .05       0
  4994.7     .05       0  5054.4     .12       0
Bank Sta=4990.7,4994.7
XS Rating Curve= 0 ,0
Exp/Cntr=0.3,0.1

Type RM Length L Ch R = 1 ,3034    ,218,218,218
BEGIN DESCRIPTION:
Mapping XS da1c67cc
END DESCRIPTION:
XS GIS Cut Line= 3
       2530723.2     13592823.55      2530428.07     13592504.12
      2530039.56      13592327.2
#Sta/Elev= 30
  4578.1  256.37    4618  253.38  4688.9  249.36  4745.6  245.14  4759.8  244.94
  4780.8  243.48    4859   240.3    4933   238.7  4950.9  238.09  4971.9  236.07
  4993.4  234.97  5000.2  233.41  5005.6  233.39  5005.8  232.89  5009.3  232.89
  5009.6  233.39  5011.6   237.3  5017.4   237.3  5022.4   238.1  5046.8  237.89
  5050.9  237.49  5120.1  238.12  5217.8  241.01  5302.1  244.87  5333.1  246.83
  5361.6  247.84    5379  248.95  5384.7  249.89    5401  250.51  5439.9   253.4
#Mann= 5 ,-1 , 0
  4578.1     .12       0    4933     .05       0  5005.6     .05       0
  5009.6     .05       0  5046.8     .12       0
Bank Sta=5005.6,5009.6
XS Rating Curve= 0 ,0
Exp/Cntr=0.3,0.1

Type RM Length L Ch R = 1 ,2816    ,257,257,257
BEGIN DESCRIPTION:
TRIB 3_1 TO SANDY FORK 2.0
END DESCRIPTION:
XS GIS Cut Line= 3
      2530825.03     13592575.02        2530525.       13592325.
      2530225.05       13592325.
#Sta/Elev= 30
  4604.8  253.18  4608.1  253.18    4612  252.02  4618.5  251.97  4647.1  250.04
  4669.3  248.01  4675.8  248.01  4704.4  245.61  4725.2  245.14  4782.5  242.01
  4796.8   242.1  4817.7  240.65  4848.6  239.72  4903.6   238.5  4981.7  235.94
  4988.2  235.33  4992.1  232.86  4997.8  232.86  5003.3   231.6  5003.6   231.1
  5007.1   231.1  5007.3   231.6  5015.3  231.79  5025.3   233.1  5076.7  235.36
    5133  236.09  5205.3  238.53  5235.3  239.86  5275.3  242.51  5295.3  242.89
#Mann= 6 ,-1 , 0
  4604.8     .05       0  4848.6     .12       0  5003.3     .05       0
  5007.3     .12       0  5076.7     .05       0    5133     .12       0
Bank Sta=5003.3,5007.3
XS Rating Curve= 0 ,0
Exp/Cntr=0.3,0.1

Type RM Length L Ch R = 1 ,2559    ,401,401,401
BEGIN DESCRIPTION:
Mapping XS 8bbdbedf
END DESCRIPTION:
XS GIS Cut Line= 3
      2530877.72     13592438.14      2530613.84     13592096.13
      2530126.01     13591998.91
#Sta/Elev= 30
    4559  250.29  4626.6  247.05  4634.8  245.78  4663.8  244.11  4783.6  238.93
  4813.2  238.31    4863  235.92    4969  232.51  4977.2  232.02  4983.5   230.3
  4988.5  228.28    4998  227.79  4998.2  227.29  5001.7  227.29    5002  227.79
  5010.2  230.93  5018.8  232.54  5023.9  232.84  5061.2  232.24  5069.9  231.52
  5091.8  233.52  5177.1  235.11  5212.4  236.34  5256.8  237.34  5316.1   239.1
  5346.7  240.63  5418.1  242.71  5432.5   242.7  5483.6  244.87  5488.4  245.59
#Mann= 6 ,-1 , 0
    4559     .05       0  4783.6     .12       0    4998     .05       0
    5002     .12       0  5212.4     .05       0  5256.8     .12       0
Bank Sta=4998,5002
XS Rating Curve= 0 ,0
Exp/Cntr=0.3,0.1

Type RM Length L Ch R = 1 ,2158    ,393,393,393
BEGIN DESCRIPTION:
TRIB 3_1 TO SANDY FORK 1.0
END DESCRIPTION:
XS GIS Cut Line= 3
      2531022.68     13592380.38      2530943.67     13591906.42
      2530168.81     13591783.81
#Sta/Elev= 30
  4519.6  253.52  4525.1  252.16  4538.1  251.69  4555.5  249.44  4636.6   244.4
  4654.7  242.56  4768.4   235.1  4798.8  234.35  4829.2  232.29    4890  229.75
    4903  229.96  4940.7  228.19  4971.1  228.08  4989.4  223.84  4989.6  223.34
  4993.1  223.34  4993.4  223.84  5008.9  226.89    5019   228.1  5049.4  227.88
  5120.2  228.71  5160.7  229.75  5201.2  229.92  5221.5  230.84  5288.1  232.04
  5393.1  234.42  5492.3   236.8  5591.4  239.65    5681  243.14  5784.6  249.22
#Mann= 7 ,-1 , 0
  4519.6     .12       0  4989.4     .05       0  4993.4     .12       0
  5288.1     .05       0  5393.1     .12       0  5492.3     .03       0
  5591.4     .12       0
#XS Ineff= 2 , 0
       0    4950     233    5030       0     233
Permanent Ineff=
       F       F
Bank Sta=4989.4,4993.4
XS Rating Curve= 0 ,0
Exp/Cntr=0.3,0.1

Type RM Length L Ch R = 1 ,1765    ,221,221,221
BEGIN DESCRIPTION:
TRIB 3 TO SANDY FORK 2.0
END DESCRIPTION:
XS GIS Cut Line= 3
        2531025.     13592325.01        2531275.       13591725.
        2530825.       13591125.
#Sta/Elev= 30
  4314.5  248.08    4353  245.09    4406  242.29  4429.9  239.84    4613  229.87
  4689.9  226.89  4704.5  227.35  4766.8  225.35  4812.8  225.42  4825.3   224.6
  4894.4  225.33    4932  226.31  4942.8  224.99  4949.9  222.68  4955.3  225.13
  4971.8  222.48  5019.8  222.44    5020  221.94  5023.8  222.44  5032.3  222.99
  5057.2  225.27  5097.5  225.79  5241.3  228.77  5264.5   228.8  5367.1   232.4
  5492.6  237.96  5592.6  244.49  5621.8   247.2  5640.9  247.77  5714.5  253.19
#Mann= 9 ,-1 , 0
  4314.5     .12       0  4894.4     .05       0  5019.8     .05       0
  5023.8     .05       0  5032.3     .12       0  5097.5     .05       0
  5241.3    .013       0  5367.1     .12       0  5640.9     .05       0
#XS Ineff= 2 , 0
       0    4920     230               0
Permanent Ineff=
       F       F
Bank Sta=5019.8,5023.8
XS Rating Curve= 0 ,0
Exp/Cntr=0.3,0.1

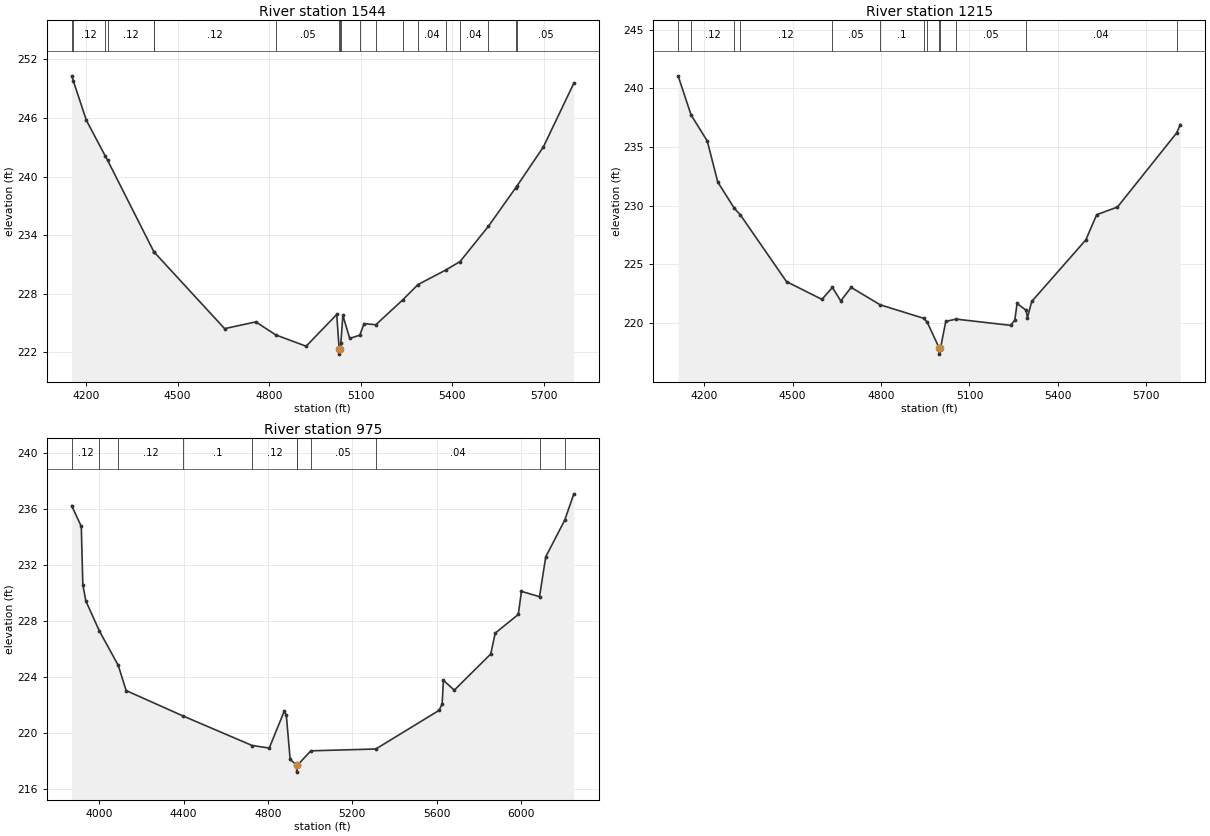
Type RM Length L Ch R = 1 ,1544    ,329,329,329
BEGIN DESCRIPTION:
Mapping XS 6eee277e
END DESCRIPTION:
XS GIS Cut Line= 4
       2531076.9     13592394.12        2531438.     13591783.03
      2531451.89     13591553.87      2530972.69     13591036.47
#Sta/Elev= 30
  4153.1  250.32  4158.3  249.83  4201.4  245.76  4263.2  242.11  4270.9  241.67
    4422  232.33  4422.5   232.3    4654  224.44  4756.1  225.13    4822  223.79
    4921  222.64  5021.2  225.89  5029.2  222.33  5029.5  221.83  5033.2  222.33
  5034.6  222.93  5041.3   225.8  5063.8  223.44  5096.7  223.77  5110.7  224.95
  5149.3  224.84  5237.2  227.38  5287.2  228.95  5377.7  230.43  5425.1  231.31
  5518.2  234.93  5607.3  238.86  5611.9  239.06  5698.1  243.05  5797.7  249.57
#Mann= 19 ,-1 , 0
  4153.1     .05       0  4158.3     .12       0  4263.2     .05       0
  4270.9     .12       0    4422     .05       0  4422.5     .12       0
    4822     .05       0  5029.2     .05       0  5033.2     .05       0
  5034.6    .013       0  5096.7     .05       0  5149.3     .04       0
  5237.2    .013       0  5287.2     .04       0  5377.7     .12       0
  5425.1     .04       0  5518.2     .05       0  5607.3     .12       0
  5611.9     .05       0
Bank Sta=5029.2,5033.2
XS Rating Curve= 0 ,0
Exp/Cntr=0.3,0.1

Type RM Length L Ch R = 1 ,1215    ,240,240,240
BEGIN DESCRIPTION:
TRIB 3 TO SANDY FORK 1.0
END DESCRIPTION:
XS GIS Cut Line= 4
      2531174.97     13592325.03      2531733.14     13591789.98
      2531733.14     13591578.17      2531175.04     13591125.03
#Sta/Elev= 30
  4111.5  241.06  4155.4  237.73  4210.5  235.51    4246  232.02  4301.8   229.8
  4322.5  229.23  4479.3  223.54  4599.5  222.03    4635  223.05  4663.3   221.9
  4698.5  223.05    4797  221.57  4944.5  220.42  4956.5   220.1  4997.7  217.87
  4997.9  217.37  5001.7  217.87  5019.7  220.16    5055  220.35  5239.3  219.82
  5253.7  220.25  5261.6  221.68    5292  221.11  5296.8  220.47  5311.2  221.85
    5495   227.1  5531.7  229.24  5602.1  229.89  5802.7  236.19  5815.4  236.91
#Mann= 13 ,-1 , 0
  4111.5     .05       0  4155.4     .12       0  4301.8     .05       0
  4322.5     .12       0    4635     .05       0    4797      .1       0
  4944.5     .05       0  4956.5    .013       0  4997.7     .03       0
  5001.7    .013       0    5055     .05       0    5292     .04       0
  5802.7     .12       0
Bank Sta=4997.7,5001.7
XS Rating Curve= 0 ,0
Exp/Cntr=0.3,0.1

Type RM Length L Ch R = 1 ,975     ,0,0,0
BEGIN DESCRIPTION:
LGII3949
END DESCRIPTION:
XS GIS Cut Line= 5
      2531353.98      13592478.7      2531930.35     13591943.99
      2531965.07     13591693.99      2531902.57     13591395.38
      2531347.04     13590520.42
#Sta/Elev= 30
  3869.8  236.25  3915.5  234.76  3922.8  230.61    3937  229.45    4001  227.31
  4090.9  224.84    4128  223.05  4397.4  221.24  4725.3  219.13  4806.4  218.95
  4877.1  221.57  4887.2   221.3  4905.4  218.14  4936.1  217.73  4936.4  217.23
  4940.1  217.73  5003.4  218.75  5311.2  218.88  5610.4  221.63  5625.7  222.08
  5631.6  223.78  5683.3  223.08    5856  225.66  5877.3  227.15  5986.5  228.48
  6001.7  230.13  6087.2  229.75  6116.9   232.6  6206.7  235.21  6249.9  237.09
#Mann= 11 ,-1 , 0
  3869.8     .12       0    4001     .05       0  4090.9     .12       0
  4397.4      .1       0  4725.3     .12       0  4936.1     .05       0
  4940.1     .12       0  5003.4     .05       0  5311.2     .04       0
  6087.2     .05       0  6206.7     .12       0
Bank Sta=4936.1,4940.1
XS Rating Curve= 0 ,0
Exp/Cntr=0.3,0.1

Chan Stop Cuts=-1
Use User Specified Reach Order=0
Composite Channel Slope=5