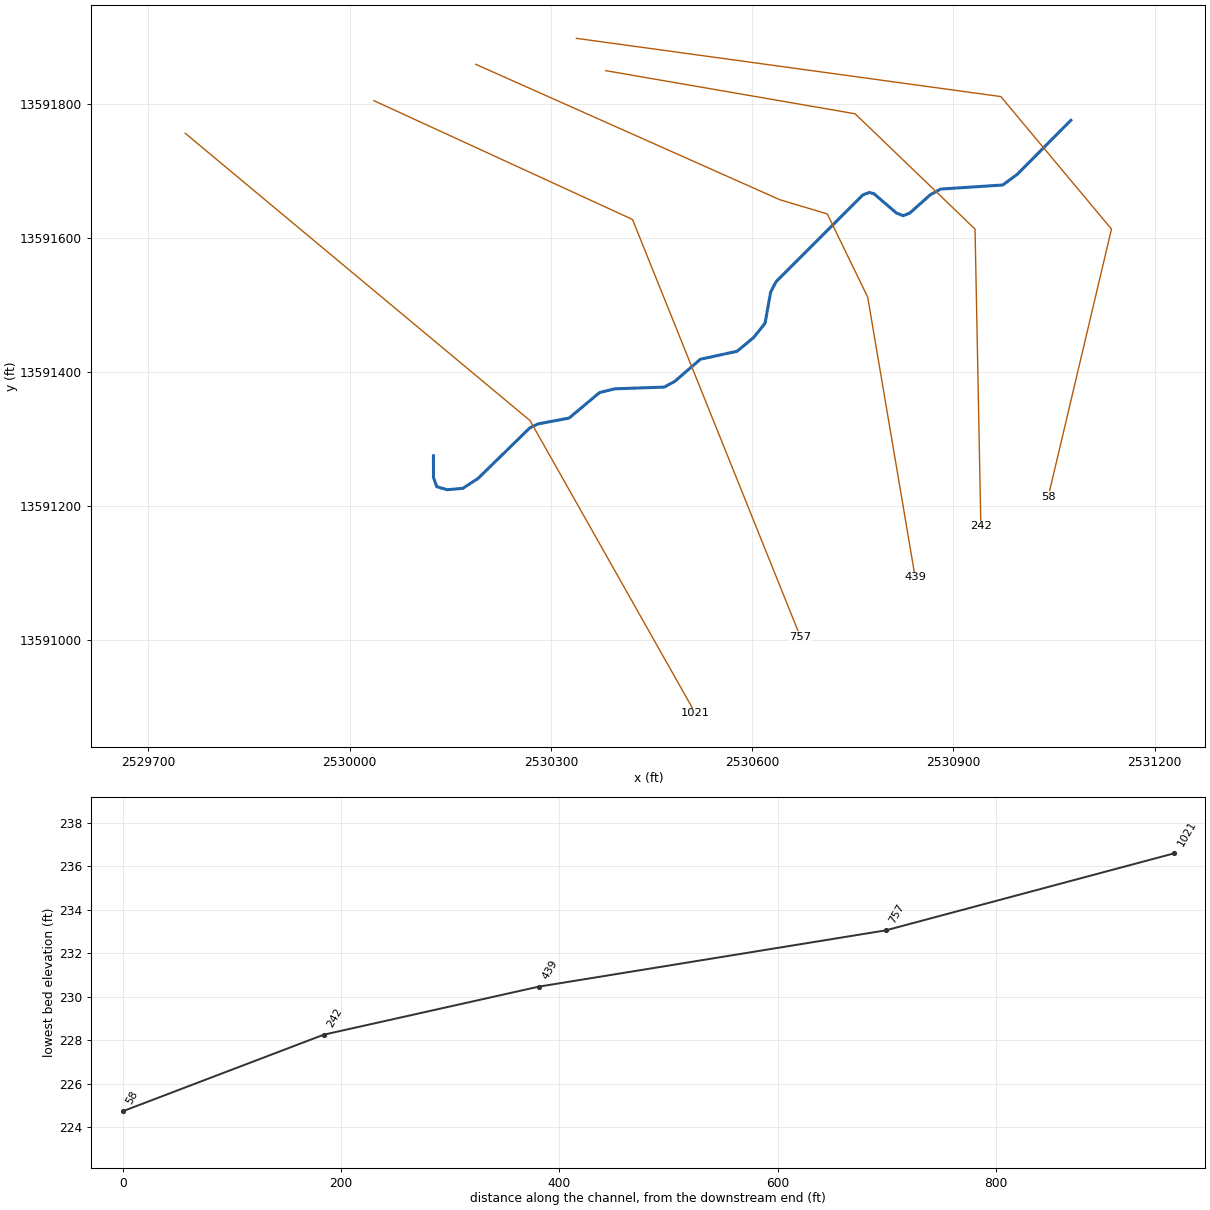
--- TRIB 3_1 TO SANDY FORK.prj (project) ---

Proj Title=TRIB 3_1 TO SANDY FORK Base Level Engineering
Current Plan=p01
Default Exp/Contr=0.3,0.1
English Units
Geom File=g01
Flow File=f01
Plan File=p01
BEGIN DESCRIPTION:
TRIB 3_1 TO SANDY FORK
END DESCRIPTION:

--- TRIB 3_1 TO SANDY FORK.p01 (plan) ---

Plan Title=Multiple Run
Short Identifier=Multiple
Geom File=g01
Flow File=f01
Subcritical Flow
K Sum by GR= 0
Std Step Tol= 0.01
Critical Tol= 0.01
Num of Std Step Trials= 20
Max Error Tol= 0.3
Flow Tol Ratio= 0.001
Split Flow NTrial= 30
Split Flow Tol= 0.02
Split Flow Ratio= 0.02
Log Output Level= 0
Friction Slope Method= 1
Unsteady Friction Slope Method= 2
Unsteady Bridges Friction Slope Method= 1
Parabolic Critical Depth
Global Vel Dist=  1 , 1 , 1
Global Log Level= 0
CheckData=True
Encroach Param= -1, 0, 0, 0
BEGIN DESCRIPTION:
Multiple Run
END DESCRIPTION:

--- TRIB 3_1 TO SANDY FORK.f01 (steady flow) ---

Flow Title=Multiple
Number of Profiles=7
Profile Names=10-year,25-year,50-year,1pct_min,100-year,1pct_plu,500-year
River Rch & RM= TRIB 3_1 TO SAND,Reach-1,1021
     253     386     500     316     631    1258     988
Boundary for River Rch & Prof#=TRIB 3_1 TO SAND,Reach-1,1
Up Type=0
Dn Type=3
Dn Slope=0.005
Boundary for River Rch & Prof#=TRIB 3_1 TO SAND,Reach-1,2
Up Type=0
Dn Type=3
Dn Slope=0.005
Boundary for River Rch & Prof#=TRIB 3_1 TO SAND,Reach-1,3
Up Type=0
Dn Type=3
Dn Slope=0.005
Boundary for River Rch & Prof#=TRIB 3_1 TO SAND,Reach-1,4
Up Type=0
Dn Type=3
Dn Slope=0.005
Boundary for River Rch & Prof#=TRIB 3_1 TO SAND,Reach-1,5
Up Type=0
Dn Type=3
Dn Slope=0.005
Boundary for River Rch & Prof#=TRIB 3_1 TO SAND,Reach-1,6
Up Type=0
Dn Type=3
Dn Slope=0.005
Boundary for River Rch & Prof#=TRIB 3_1 TO SAND,Reach-1,7
Up Type=0
Dn Type=3
Dn Slope=0.005

--- TRIB 3_1 TO SANDY FORK.g01 (geometry) ---

Geom Title=Existing Conditions

River Reach=TRIB 3_1 TO SAND,Reach-1
Reach XY= 30
      2530125.00     13591275.00      2530125.07     13591242.63
      2530129.92     13591228.93      2530145.41     13591224.37
      2530168.79     13591226.43      2530191.54     13591241.26
      2530268.95     13591316.84      2530281.04     13591322.50
      2530327.17     13591331.14      2530372.68     13591369.23
      2530395.09     13591374.77      2530469.04     13591377.33
      2530484.66     13591385.83      2530522.85     13591418.85
      2530577.55     13591430.73      2530602.14     13591451.16
      2530619.25     13591472.46      2530627.55     13591518.91
      2530635.79     13591534.66      2530765.00     13591663.76
      2530774.99     13591667.45      2530781.66     13591665.40
      2530814.94     13591636.85      2530824.90     13591632.80
      2530834.85     13591636.62      2530865.21     13591663.77
      2530880.89     13591672.46      2530973.52     13591678.56
      2530995.20     13591694.52      2531075.00     13591775.00

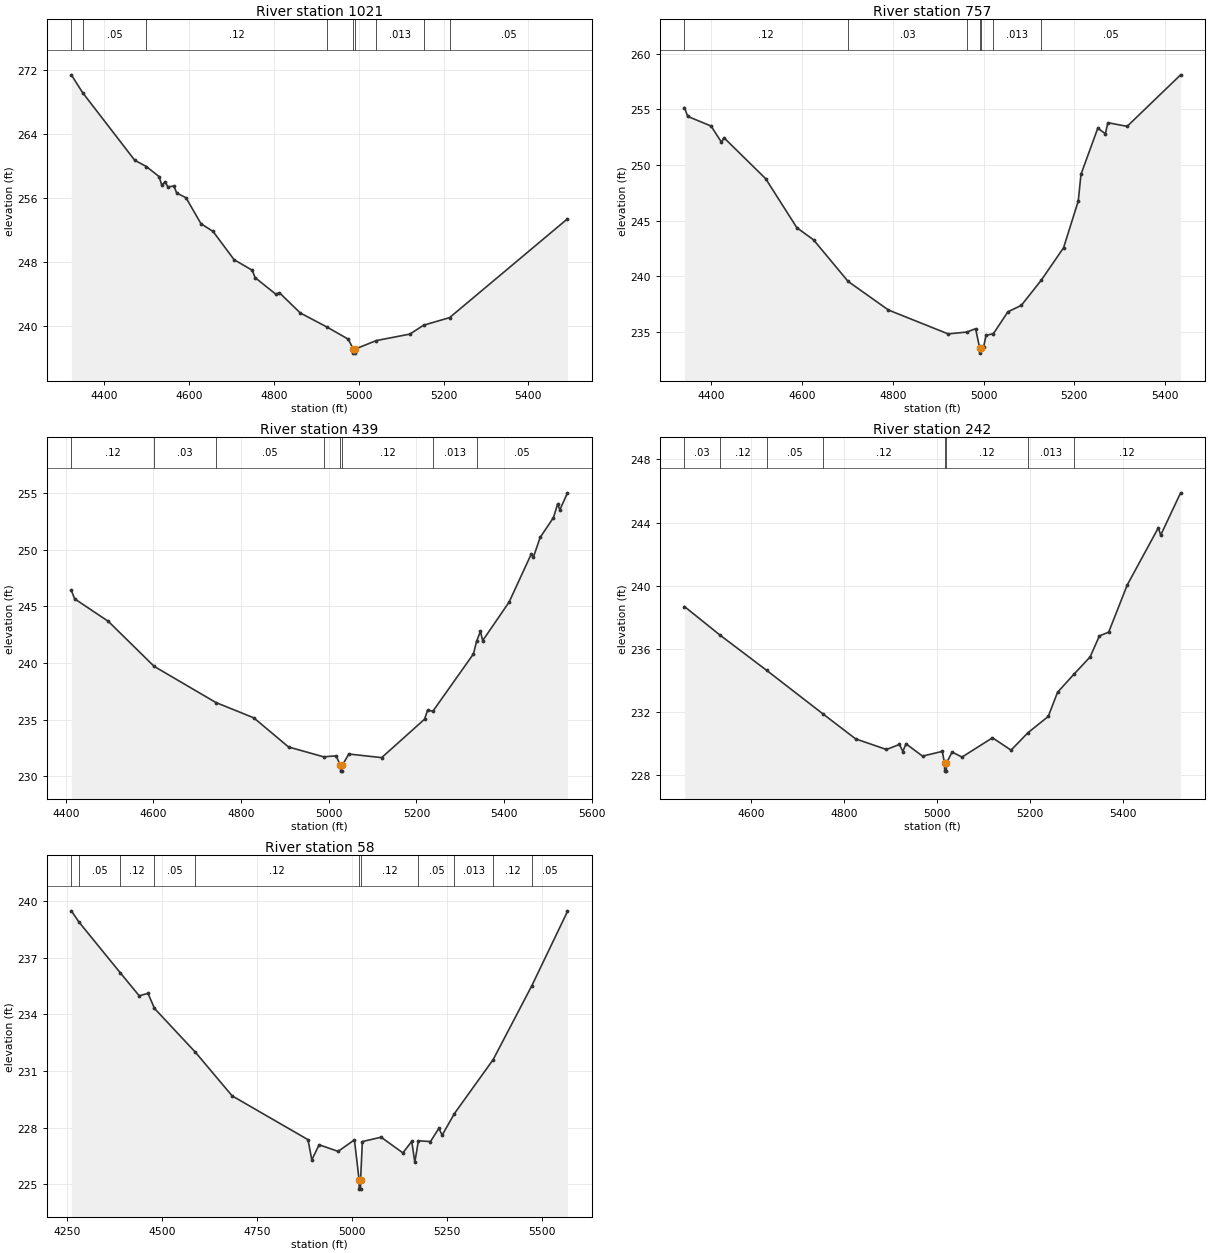
Type RM Length L Ch R = 1,1021,264,264,264
BEGIN DESCRIPTION:
TRIB 3 TO SANDY FORK 4.0
END DESCRIPTION:
XS GIS Cut Line= 3
      2529755.06     13591755.61      2530269.05     13591327.30
      2530515.46     13590891.03
#Sta/Elev= 30
  4322.0  271.39  4348.6  269.16  4471.5  260.71  4498.8  259.93  4528.8  258.68
  4535.3  257.59  4543.1  258.03  4549.6  257.38  4563.9  257.49  4570.4  256.62
  4592.5  256.02  4627.7  252.78  4656.3  251.81  4705.8  248.28  4748.7  246.96
  4755.3  246.04  4804.7  243.95  4812.5  244.16  4862.0  241.62  4926.0  239.83
  4975.2  238.34  4986.9  237.10  4987.2  236.60  4990.7  236.60  4990.9  237.10
  5041.3  238.17  5120.4  238.98  5152.7  240.09  5214.1  241.04  5492.1  253.39
#Mann=9,-1,0
  4322.0    0.12       0  4348.6    0.05       0  4498.8    0.12       0
  4926.0    0.03       0  4986.9    0.03       0  4990.9    0.03       0
  5041.3   0.013       0  5152.7    0.12       0  5214.1    0.05       0
Bank Sta=4986.9,4990.9
Exp/Cntr=0.3,0.1

Type RM Length L Ch R = 1,757,318,318,318
BEGIN DESCRIPTION:
Mapping XS 8520583c
END DESCRIPTION:
XS GIS Cut Line= 3
      2530036.30     13591804.23      2530421.70     13591627.15
      2530671.72     13591005.58
#Sta/Elev= 30
  4340.5  255.17  4347.6  254.38  4399.1  253.51  4422.0  252.06  4427.5  252.46
  4519.5  248.77  4588.4  244.35  4625.2  243.26  4701.3  239.52  4790.4  236.94
  4922.0  234.79  4963.3  234.96  4982.5  235.26  4991.3  233.56  4991.6  233.06
  4995.3  233.56  5000.0  233.58  5005.4  234.65  5021.9  234.82  5053.7  236.78
  5083.3  237.36  5127.0  239.61  5176.5  242.55  5208.9  246.76  5214.9  249.16
  5252.0  253.32  5268.7  252.81  5274.1  253.81  5316.7  253.48  5434.6  258.12
#Mann=7,-1,0
  4340.5    0.12       0  4701.3    0.03       0  4963.3    0.12       0
  4991.3    0.05       0  4995.3    0.12       0  5021.9   0.013       0
  5127.0    0.05       0
Bank Sta=4991.3,4995.3
Exp/Cntr=0.3,0.1

Type RM Length L Ch R = 1,439,197,197,197
BEGIN DESCRIPTION:
LGII3948
END DESCRIPTION:
XS GIS Cut Line= 5
      2530188.03     13591858.43      2530641.21     13591656.62
      2530712.03     13591635.38      2530772.22     13591511.45
      2530843.04     13591093.60
#Sta/Elev= 30
  4412.8  246.40  4420.4  245.66  4497.1  243.68  4601.6  239.71  4742.5  236.52
  4828.9  235.17  4908.2  232.60  4988.4  231.73  5016.6  231.82  5026.6  230.97
  5026.9  230.47  5030.4  230.47  5030.6  230.97  5045.6  231.98  5120.6  231.66
  5218.4  235.05  5225.2  235.83  5237.5  235.76  5330.0  240.81  5337.0  241.91
  5345.9  242.80  5351.0  241.98  5411.3  245.38  5461.6  249.60  5466.6  249.33
  5482.1  251.08  5512.5  252.83  5521.9  254.03  5527.0  253.51  5544.4  255.01
#Mann=8,-1,0
  4412.8    0.12       0  4601.6    0.03       0  4742.5    0.05       0
  4988.4    0.12       0  5026.6    0.05       0  5030.6    0.12       0
  5237.5   0.013       0  5337.0    0.05       0
Bank Sta=5026.6,5030.6
Exp/Cntr=0.3,0.1

Type RM Length L Ch R = 1,242,184,184,184
BEGIN DESCRIPTION:
Mapping XS 5da32435
END DESCRIPTION:
XS GIS Cut Line= 4
      2530381.89     13591848.96      2530753.40     13591784.73
      2530932.22     13591612.85      2530940.90     13591170.19
#Sta/Elev= 30
  4456.5  238.68  4533.1  236.87  4633.4  234.64  4755.6  231.86  4825.0  230.30
  4891.2  229.63  4919.2  229.95  4926.4  229.50  4933.3  229.99  4968.9  229.21
  5011.3  229.51  5016.3  228.76  5016.5  228.26  5020.0  228.26  5020.3  228.76
  5032.4  229.47  5053.8  229.15  5119.4  230.37  5159.4  229.59  5195.7  230.69
  5239.4  231.72  5259.4  233.25  5294.2  234.38  5329.5  235.49  5349.5  236.82
  5369.5  237.06  5409.5  240.05  5476.4  243.67  5481.4  243.20  5524.3  245.88
#Mann=8,-1,0
  4456.5    0.03       0  4533.1    0.12       0  4633.4    0.05       0
  4755.6    0.12       0  5016.3    0.05       0  5020.3    0.12       0
  5195.7   0.013       0  5294.2    0.12       0
Bank Sta=5016.3,5020.3
Exp/Cntr=0.3,0.1

Type RM Length L Ch R = 1,58,0,0,0
BEGIN DESCRIPTION:
LGII3947
END DESCRIPTION:
XS GIS Cut Line= 4
      2530338.07     13591897.14      2530970.63     13591810.34
      2531135.56     13591612.85      2531041.32     13591214.02
#Sta/Elev= 30
  4262.1  239.48  4281.6  238.90  4390.8  236.20  4440.7  234.98  4463.8  235.11
  4480.9  234.31  4588.6  231.99  4685.2  229.68  4884.8  227.36  4894.9  226.29
  4914.1  227.09  4964.1  226.74  5007.0  227.35  5019.3  225.24  5019.6  224.74
  5023.1  224.74  5023.3  225.24  5027.9  227.26  5077.3  227.49  5134.6  226.66
  5157.9  227.27  5166.0  226.16  5175.3  227.30  5207.1  227.26  5229.2  227.96
  5237.9  227.60  5270.1  228.74  5372.1  231.60  5474.0  235.52  5567.7  239.45
#Mann=11,-1,0
  4262.1    0.12       0  4281.6    0.05       0  4390.8    0.12       0
  4480.9    0.05       0  4588.6    0.12       0  5019.3    0.05       0
  5023.3    0.12       0  5175.3    0.05       0  5270.1   0.013       0
  5372.1    0.12       0  5474.0    0.05       0
Bank Sta=5019.3,5023.3
Exp/Cntr=0.3,0.1

Chan Stop Cuts=-1