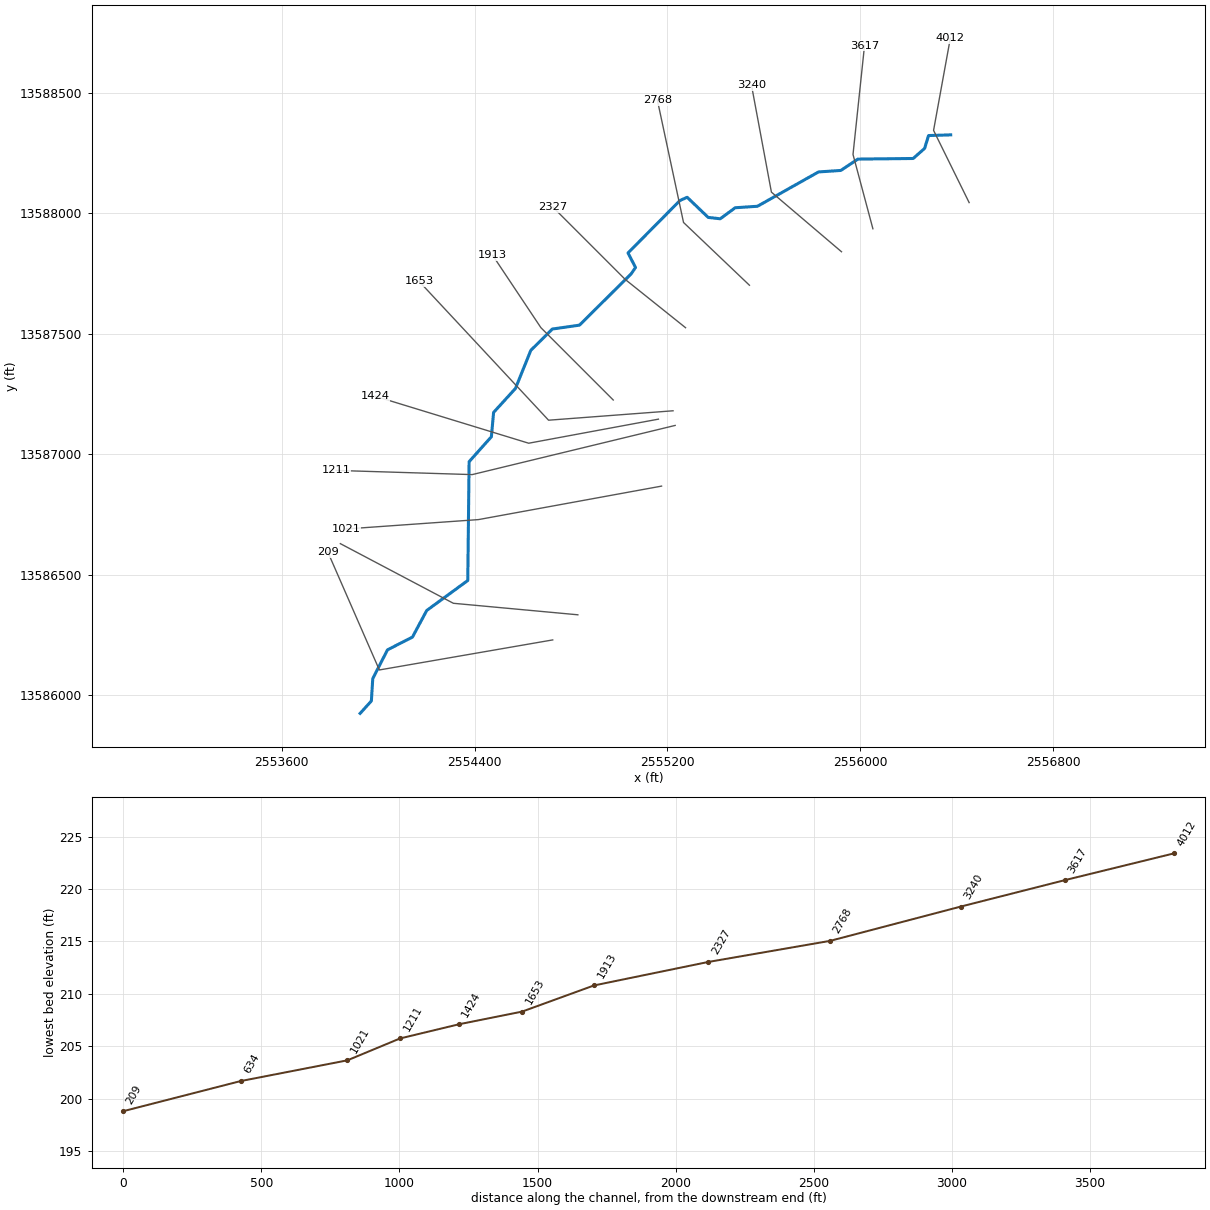
--- TRIB 4 TO CRITTENOON HOLLOW.prj (project) ---

Proj Title=TRIB 4 TO CRITTENOON HOLLOW Base Level Engineering
Current Plan=p01
Default Exp/Contr=0.3,0.1
English Units
Geom File=g01
Flow File=f01
Plan File=p01
BEGIN DESCRIPTION:
TRIB 4 TO CRITTENOON HOLLOW
END DESCRIPTION:

--- TRIB 4 TO CRITTENOON HOLLOW.p01 (plan) ---

Plan Title=Multiple Run
Short Identifier=Multiple
Geom File=g01
Flow File=f01
Subcritical Flow
K Sum by GR= 0
Std Step Tol= 0.01
Critical Tol= 0.01
Num of Std Step Trials= 20
Max Error Tol= 0.3
Flow Tol Ratio= 0.001
Split Flow NTrial= 30
Split Flow Tol= 0.02
Split Flow Ratio= 0.02
Log Output Level= 0
Friction Slope Method= 1
Unsteady Friction Slope Method= 2
Unsteady Bridges Friction Slope Method= 1
Parabolic Critical Depth
Global Vel Dist=  1 , 1 , 1
Global Log Level= 0
CheckData=True
Encroach Param= -1, 0, 0, 0
BEGIN DESCRIPTION:
Multiple Run
END DESCRIPTION:

--- TRIB 4 TO CRITTENOON HOLLOW.f01 (steady flow) ---

Flow Title=Multiple
Number of Profiles=7
Profile Names=10-year,25-year,50-year,1pct_min,100-year,1pct_plu,500-year
River Rch & RM= TRIB 4 TO CRITTE,Reach-1,4012
     495     782    1036     667    1330    2654    2166
River Rch & RM= TRIB 4 TO CRITTE,Reach-1,1913
     564     900    1200     776    1549    3091    2553
Boundary for River Rch & Prof#=TRIB 4 TO CRITTE,Reach-1,1
Up Type=0
Dn Type=3
Dn Slope=0.005
Boundary for River Rch & Prof#=TRIB 4 TO CRITTE,Reach-1,2
Up Type=0
Dn Type=3
Dn Slope=0.005
Boundary for River Rch & Prof#=TRIB 4 TO CRITTE,Reach-1,3
Up Type=0
Dn Type=3
Dn Slope=0.005
Boundary for River Rch & Prof#=TRIB 4 TO CRITTE,Reach-1,4
Up Type=0
Dn Type=3
Dn Slope=0.005
Boundary for River Rch & Prof#=TRIB 4 TO CRITTE,Reach-1,5
Up Type=0
Dn Type=3
Dn Slope=0.005
Boundary for River Rch & Prof#=TRIB 4 TO CRITTE,Reach-1,6
Up Type=0
Dn Type=3
Dn Slope=0.005
Boundary for River Rch & Prof#=TRIB 4 TO CRITTE,Reach-1,7
Up Type=0
Dn Type=3
Dn Slope=0.005

--- TRIB 4 TO CRITTENOON HOLLOW.g01 (geometry) ---

Geom Title=Existing Conditions

River Reach=TRIB 4 TO CRITTE,Reach-1
Reach XY= 30
      2556375.00     13588325.00      2556283.12     13588322.14
      2556266.88     13588268.93      2556219.32     13588227.00
      2555990.22     13588224.48      2555919.02     13588177.36
      2555826.58     13588171.17      2555573.42     13588028.83
      2555480.97     13588022.62      2555418.87     13587976.78
      2555368.94     13587982.52      2555281.66     13588066.03
      2555251.67     13588052.61      2555036.24     13587835.00
      2555067.44     13587775.00      2555049.23     13587748.33
      2554834.79     13587535.52      2554722.56     13587519.48
      2554633.13     13587431.07      2554569.15     13587272.71
      2554478.63     13587173.50      2554469.46     13587072.58
      2554377.07     13586969.14      2554371.55     13586476.25
      2554201.27     13586351.88      2554142.04     13586241.50
      2554038.48     13586188.56      2553977.30     13586069.05
      2553971.61     13585976.40      2553925.00     13585925.00

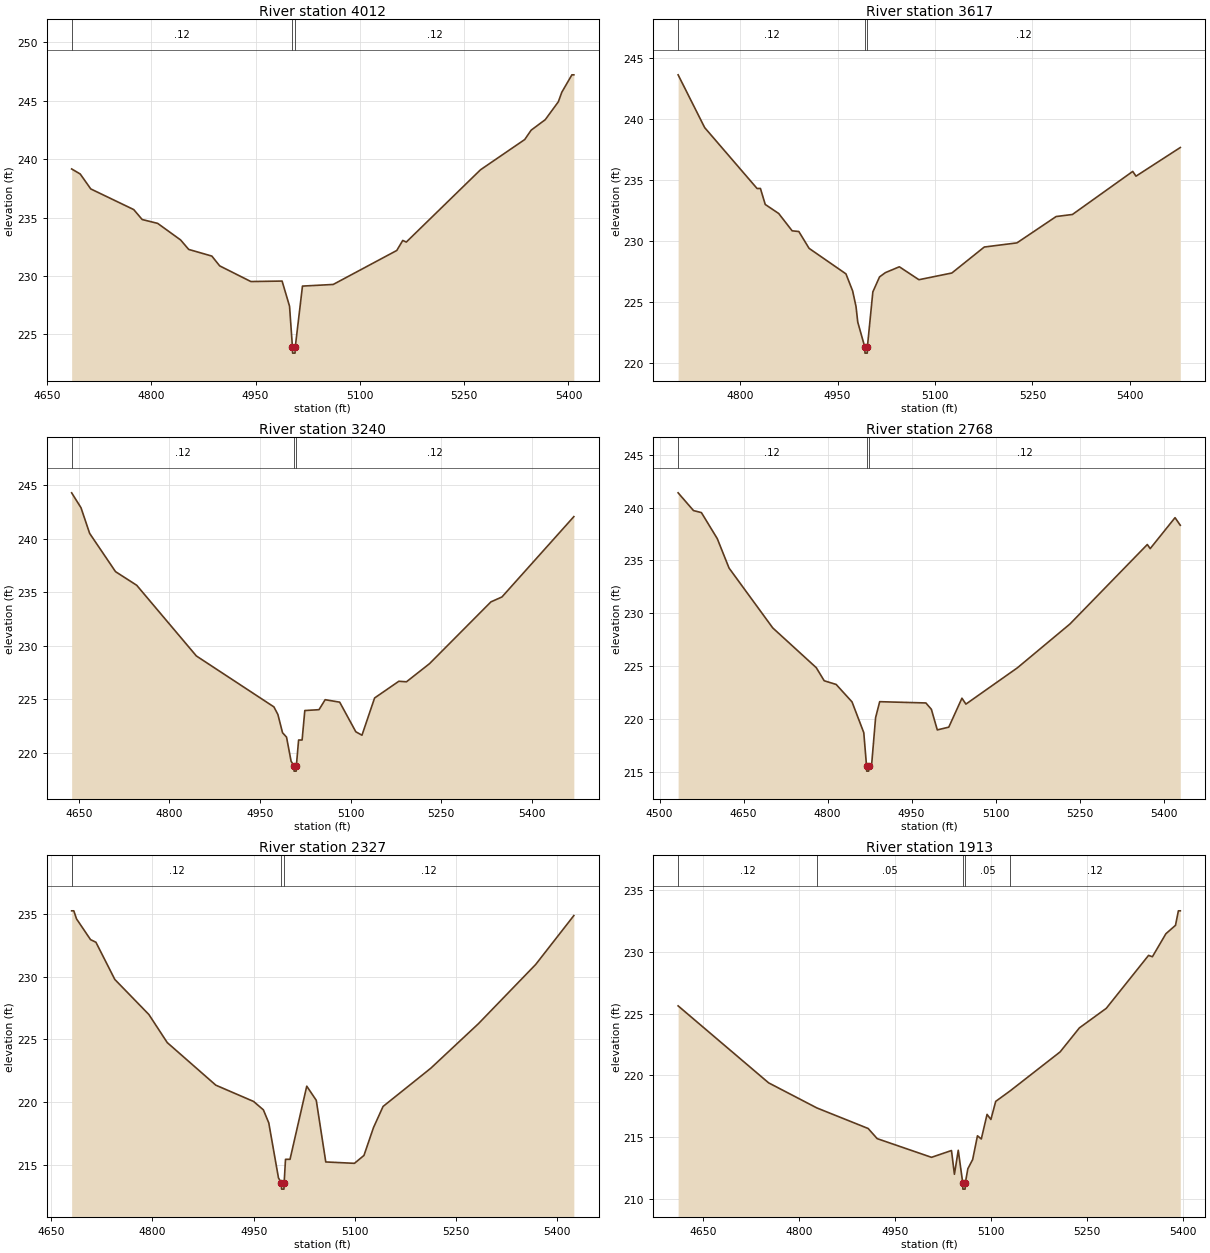
Type RM Length L Ch R = 1,4012,395,395,395
BEGIN DESCRIPTION:
Mapping XS 0b453df0
END DESCRIPTION:
XS GIS Cut Line= 3
      2556451.51     13588044.00      2556303.92     13588343.51
      2556373.37     13588725.45
#Sta/Elev= 30
  4685.6  239.16  4697.9  238.73  4713.1  237.45  4774.9  235.68  4787.0  234.83
  4809.3  234.50  4842.3  233.08  4853.9  232.27  4887.2  231.70  4898.5  230.86
  4943.3  229.52  4988.2  229.56  4998.9  227.41  5003.1  223.89  5003.3  223.39
  5006.8  223.39  5007.1  223.89  5017.5  229.13  5061.7  229.27  5153.1  232.18
  5161.7  233.04  5166.8  232.90  5273.5  239.09  5337.1  241.68  5346.3  242.48
  5366.6  243.38  5385.4  244.91  5390.4  245.73  5404.9  247.22  5407.7  247.22
#Mann=3,-1,0
  4685.6    0.12       0  5003.1    0.05       0  5007.1    0.12       0
Bank Sta=5003.1,5007.1
Exp/Cntr=0.3,0.1

Type RM Length L Ch R = 1,3617,377,377,377
BEGIN DESCRIPTION:
Mapping XS b68653ef
END DESCRIPTION:
XS GIS Cut Line= 3
      2556052.20     13587935.49      2555969.72     13588243.69
      2556017.46     13588695.03
#Sta/Elev= 30
  4704.6  243.66  4745.5  239.33  4826.1  234.34  4831.3  234.34  4838.7  233.03
  4859.4  232.29  4880.1  230.87  4890.4  230.81  4906.2  229.43  4962.9  227.34
  4973.2  225.94  4978.4  224.66  4981.1  223.38  4991.9  221.34  4992.2  220.84
  4995.7  220.84  4995.9  221.34  5004.3  225.86  5014.6  227.09  5023.6  227.44
  5045.1  227.92  5075.2  226.86  5125.9  227.41  5175.8  229.54  5226.1  229.88
  5286.4  232.04  5311.5  232.21  5404.3  235.74  5409.3  235.35  5477.5  237.70
#Mann=3,-1,0
  4704.6    0.12       0  4991.9    0.05       0  4995.9    0.12       0
Bank Sta=4991.9,4995.9
Exp/Cntr=0.3,0.1

Type RM Length L Ch R = 1,3240,472,472,472
BEGIN DESCRIPTION:
Mapping XS 03a11527
END DESCRIPTION:
XS GIS Cut Line= 3
      2555921.97     13587840.05      2555631.18     13588087.44
      2555548.73     13588530.04
#Sta/Elev= 30
  4638.0  244.27  4653.5  242.88  4667.8  240.49  4710.7  236.92  4745.8  235.65
  4844.6  229.06  4973.1  224.31  4979.7  223.60  4987.4  221.90  4994.0  221.49
  5001.6  219.24  5006.3  218.82  5006.5  218.32  5010.0  218.32  5010.3  218.82
  5014.0  221.22  5019.8  221.22  5024.3  223.97  5047.8  224.05  5058.0  224.98
  5082.1  224.75  5108.8  221.99  5119.0  221.67  5139.9  225.14  5180.1  226.70
  5192.7  226.65  5230.9  228.34  5332.6  234.10  5350.9  234.56  5470.0  242.05
#Mann=3,-1,0
  4638.0    0.12       0  5006.3    0.05       0  5010.3    0.12       0
Bank Sta=5006.3,5010.3
Exp/Cntr=0.3,0.1

Type RM Length L Ch R = 1,2768,441,441,441
BEGIN DESCRIPTION:
Mapping XS 3bbb88e8
END DESCRIPTION:
XS GIS Cut Line= 3
      2555540.03     13587701.16      2555266.60     13587961.57
      2555158.08     13588469.41
#Sta/Elev= 30
  4533.1  241.39  4560.6  239.71  4574.7  239.52  4603.1  237.05  4624.1  234.27
  4702.1  228.61  4779.8  224.85  4794.0  223.61  4815.4  223.26  4843.7  221.61
  4864.7  218.70  4869.6  215.56  4869.9  215.06  4873.4  215.06  4873.6  215.56
  4878.9  215.78  4885.8  220.12  4893.1  221.63  4975.6  221.51  4985.4  220.91
  4996.0  218.96  5016.5  219.22  5040.0  221.96  5047.1  221.40  5139.2  224.84
  5232.9  228.98  5371.1  236.50  5376.2  236.11  5420.6  239.04  5430.0  238.32
#Mann=3,-1,0
  4533.1    0.12       0  4869.6    0.05       0  4873.6    0.12       0
Bank Sta=4869.6,4873.6
Exp/Cntr=0.3,0.1

Type RM Length L Ch R = 1,2327,414,414,414
BEGIN DESCRIPTION:
TRIB 4 TO CRITTENOON HOLLOW 5.0
END DESCRIPTION:
XS GIS Cut Line= 3
      2555275.01     13587524.99      2555025.00     13587725.00
      2554725.02     13588024.98
#Sta/Elev= 30
  4680.2  235.27  4683.4  235.27  4687.4  234.63  4708.2  232.97  4716.2  232.76
  4744.2  229.79  4794.7  226.99  4821.9  224.75  4893.9  221.35  4949.9  220.05
  4964.4  219.38  4972.4  218.34  4986.8  213.94  4991.2  213.55  4991.4  213.05
  4994.9  213.05  4995.2  213.55  4997.2  215.43  5003.9  215.43  5028.7  221.27
  5042.8  220.14  5056.9  215.22  5099.4  215.11  5113.5  215.74  5127.6  217.96
  5141.8  219.65  5212.5  222.70  5283.2  226.26  5368.1  230.99  5424.6  234.89
#Mann=3,-1,0
  4680.2    0.12       0  4991.2    0.05       0  4995.2    0.12       0
Bank Sta=4991.2,4995.2
Exp/Cntr=0.3,0.1

Type RM Length L Ch R = 1,1913,260,260,260
BEGIN DESCRIPTION:
TRIB 4 TO CRITTENOON HOLLOW 4.0
END DESCRIPTION:
XS GIS Cut Line= 3
      2554974.98     13587225.02      2554675.00     13587525.00
      2554475.00     13587825.00
#Sta/Elev= 30
  4610.6  225.62  4752.0  219.40  4827.5  217.37  4907.6  215.71  4921.7  214.89
  5006.6  213.38  5037.8  213.93  5042.4  212.01  5048.4  213.95  5055.4  211.31
  5055.6  210.81  5059.1  210.81  5059.4  211.31  5063.4  212.46  5070.9  213.20
  5078.4  215.12  5084.4  214.86  5093.4  216.85  5099.4  216.44  5106.9  217.90
  5129.5  218.75  5207.6  221.90  5237.7  223.84  5279.7  225.42  5345.8  229.70
  5351.8  229.59  5372.9  231.45  5387.9  232.13  5392.4  233.30  5395.4  233.30
#Mann=5,-1,0
  4610.6    0.12       0  4827.5    0.05       0  5055.4    0.05       0
  5059.4    0.05       0  5129.5    0.12       0
Bank Sta=5055.4,5059.4
Exp/Cntr=0.3,0.1

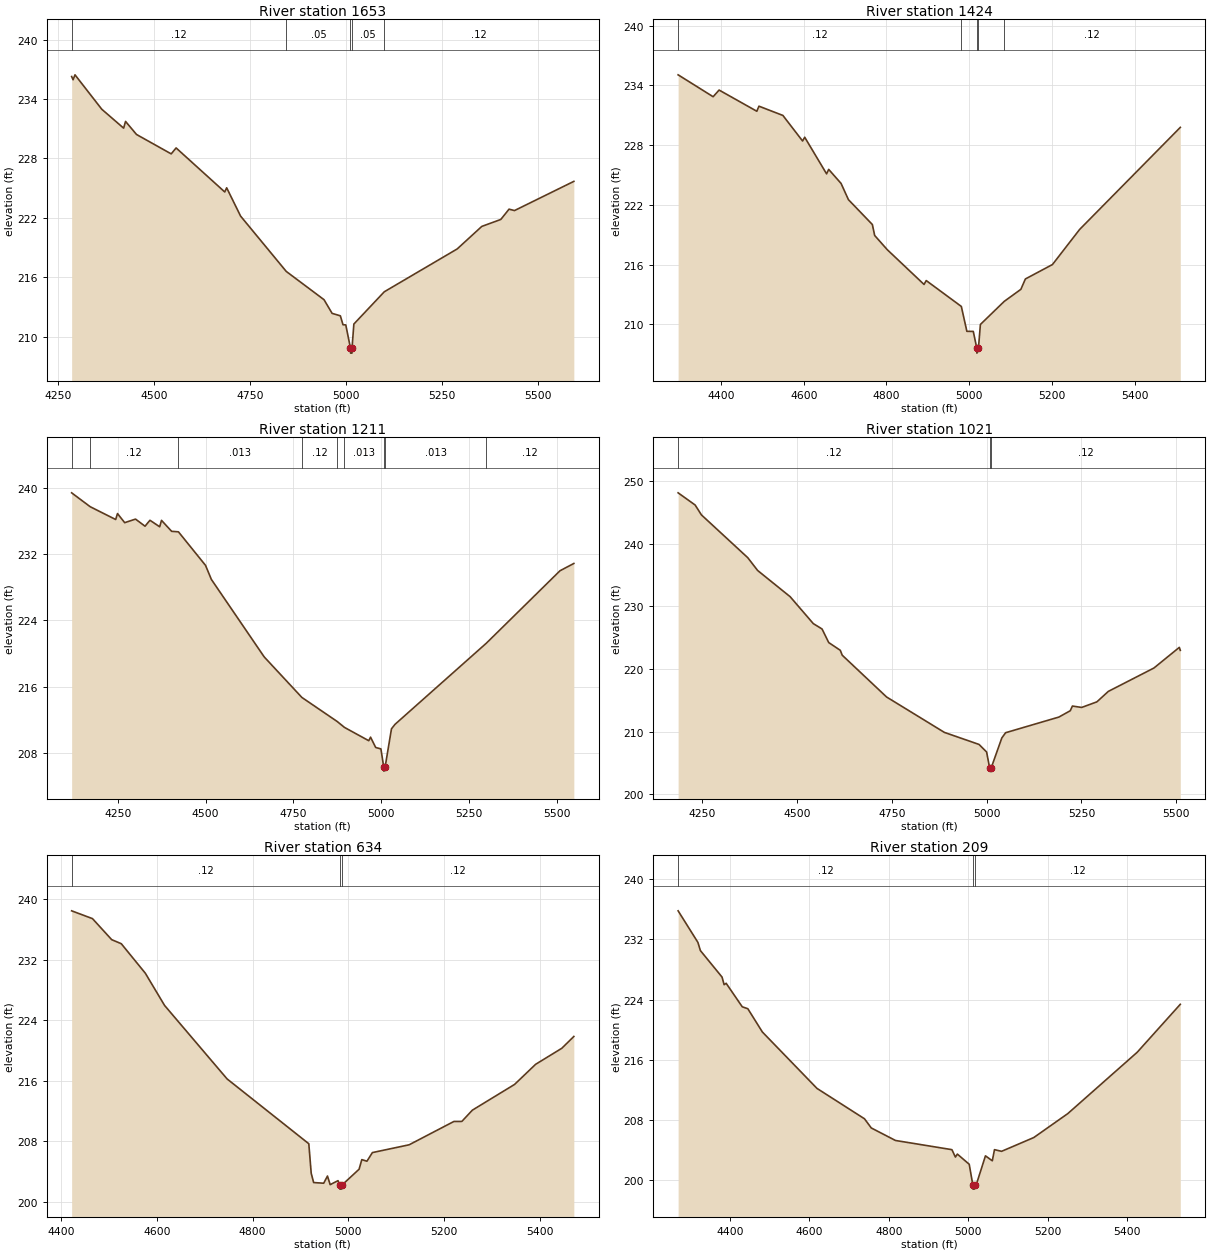
Type RM Length L Ch R = 1,1653,229,229,229
BEGIN DESCRIPTION:
Mapping XS 415995e2
END DESCRIPTION:
XS GIS Cut Line= 3
      2555223.19     13587180.32      2554706.70     13587141.25
      2554169.25     13587717.71
#Sta/Elev= 30
  4286.3  236.28  4290.0  235.95  4295.0  236.45  4364.7  232.97  4421.5  231.06
  4426.5  231.74  4455.0  230.42  4545.2  228.46  4558.0  229.06  4684.5  224.61
  4689.5  225.03  4725.7  222.17  4844.4  216.58  4942.7  213.72  4963.7  212.34
  4985.2  212.09  4992.0  211.19  4999.3  211.17  5011.5  208.82  5011.8  208.32
  5015.3  208.32  5015.5  208.82  5020.3  211.26  5099.4  214.52  5289.0  218.85
  5353.1  221.13  5402.4  221.83  5423.9  222.87  5438.1  222.73  5592.4  225.68
#Mann=5,-1,0
  4286.3    0.12       0  4844.4    0.05       0  5011.5    0.05       0
  5015.5    0.05       0  5099.4    0.12       0
Bank Sta=5011.5,5015.5
Exp/Cntr=0.3,0.1

Type RM Length L Ch R = 1,1424,213,213,213
BEGIN DESCRIPTION:
Mapping XS 8c772763
END DESCRIPTION:
XS GIS Cut Line= 3
      2555162.44     13587145.60      2554624.24     13587045.77
      2553986.25     13587241.07
#Sta/Elev= 30
  4296.1  235.07  4380.8  232.87  4395.2  233.54  4486.5  231.41  4491.6  231.92
  4549.5  230.99  4597.2  228.42  4602.3  228.80  4655.2  225.12  4660.3  225.57
  4690.2  224.16  4708.0  222.53  4765.9  220.03  4771.5  218.93  4802.0  217.50
  4890.9  214.01  4896.2  214.40  4981.1  211.80  4994.5  209.30  5010.0  209.29
  5018.5  207.61  5018.7  207.11  5022.5  207.61  5027.2  209.99  5084.9  212.31
  5125.1  213.52  5136.0  214.56  5201.5  216.01  5267.1  219.53  5510.7  229.79
#Mann=5,-1,0
  4296.1    0.12       0  4981.1    0.05       0  5018.5    0.05       0
  5022.5    0.05       0  5084.9    0.12       0
Bank Sta=5018.5,5022.5
Exp/Cntr=0.3,0.1

Type RM Length L Ch R = 1,1211,190,190,190
BEGIN DESCRIPTION:
Mapping XS 211ff445
END DESCRIPTION:
XS GIS Cut Line= 3
      2555231.87     13587119.55      2554389.86     13586915.56
      2553825.60     13586932.92
#Sta/Elev= 30
  4118.4  239.44  4171.2  237.76  4243.9  236.21  4249.0  236.93  4269.5  235.83
  4300.4  236.26  4327.5  235.40  4341.5  236.12  4369.3  235.33  4374.4  236.11
  4403.3  234.78  4422.7  234.72  4499.9  230.66  4516.5  228.96  4667.1  219.58
  4774.3  214.68  4874.9  211.77  4895.8  211.05  4965.0  209.44  4970.1  209.87
  4984.7  208.62  4999.6  208.45  5007.6  206.26  5007.9  205.76  5011.6  206.26
  5029.7  210.88  5039.7  211.42  5300.2  221.25  5509.9  230.01  5549.3  230.89
#Mann=9,-1,0
  4118.4   0.013       0  4171.2    0.12       0  4422.7   0.013       0
  4774.3    0.12       0  4874.9    0.05       0  4895.8   0.013       0
  5007.6    0.03       0  5011.6   0.013       0  5300.2    0.12       0
Bank Sta=5007.6,5011.6
Exp/Cntr=0.3,0.1

Type RM Length L Ch R = 1,1021,387,387,387
BEGIN DESCRIPTION:
Mapping XS f571b130
END DESCRIPTION:
XS GIS Cut Line= 3
      2555175.49     13586867.83      2554415.90     13586728.93
      2553865.67     13586689.94
#Sta/Elev= 30
  4186.8  248.16  4231.7  246.21  4248.3  244.63  4370.3  237.80  4396.4  235.75
  4482.1  231.56  4543.1  227.26  4566.2  226.40  4583.8  224.23  4614.3  222.99
  4619.4  222.21  4736.3  215.53  4888.7  209.87  4979.9  207.95  5000.0  206.74
  5008.0  204.18  5008.3  203.68  5011.8  203.68  5012.0  204.18  5040.1  208.98
  5050.1  209.82  5190.5  212.32  5220.5  213.33  5226.2  214.08  5250.6  213.86
  5290.7  214.75  5320.8  216.42  5441.1  220.16  5508.0  223.46  5510.6  222.98
#Mann=3,-1,0
  4186.8    0.12       0  5008.0    0.05       0  5012.0    0.12       0
Bank Sta=5008,5012
Exp/Cntr=0.3,0.1

Type RM Length L Ch R = 1,634,425,425,425
BEGIN DESCRIPTION:
Mapping XS 3f956c8b
END DESCRIPTION:
XS GIS Cut Line= 3
      2554828.27     13586333.96      2554311.74     13586381.71
      2553842.96     13586629.12
#Sta/Elev= 30
  4422.1  238.49  4465.6  237.46  4505.7  234.68  4525.8  234.14  4576.0  230.24
  4616.2  225.98  4746.7  216.27  4917.4  207.70  4922.4  203.80  4927.5  202.57
  4948.5  202.48  4956.4  203.43  4962.0  202.29  4978.4  202.82  4982.0  202.20
  4982.3  201.70  4985.8  201.70  4986.0  202.20  5022.4  204.33  5028.1  205.60
  5038.8  205.39  5050.2  206.53  5126.9  207.56  5220.6  210.65  5237.0  210.65
  5259.0  212.14  5347.1  215.54  5391.1  218.20  5445.8  220.32  5470.9  221.88
#Mann=3,-1,0
  4422.1    0.12       0  4982.0    0.05       0  4986.0    0.12       0
Bank Sta=4982,4986
Exp/Cntr=0.3,0.1

Type RM Length L Ch R = 1,209,0,0,0
BEGIN DESCRIPTION:
TRIB 4 TO CRITTENOON HOLLOW 1.0
END DESCRIPTION:
XS GIS Cut Line= 3
      2554724.02     13586229.79      2554004.69     13586105.13
      2553790.89     13586594.40
#Sta/Elev= 30
  4270.0  235.78  4319.8  231.59  4326.1  230.50  4380.6  226.98  4385.8  225.97
  4390.9  226.16  4431.4  223.04  4445.5  222.78  4482.1  219.69  4619.6  212.20
  4739.1  208.17  4756.2  206.95  4817.1  205.29  4959.1  204.07  4967.9  203.09
  4972.9  203.48  5002.7  202.13  5012.0  199.33  5012.3  198.83  5015.8  198.83
  5016.0  199.33  5021.7  199.63  5043.6  203.25  5060.8  202.59  5066.3  204.07
  5084.2  203.85  5165.3  205.68  5250.9  208.86  5425.5  217.00  5534.0  223.37
#Mann=3,-1,0
  4270.0    0.12       0  5012.0    0.05       0  5016.0    0.12       0
Bank Sta=5012,5016
Exp/Cntr=0.3,0.1

Chan Stop Cuts=-1