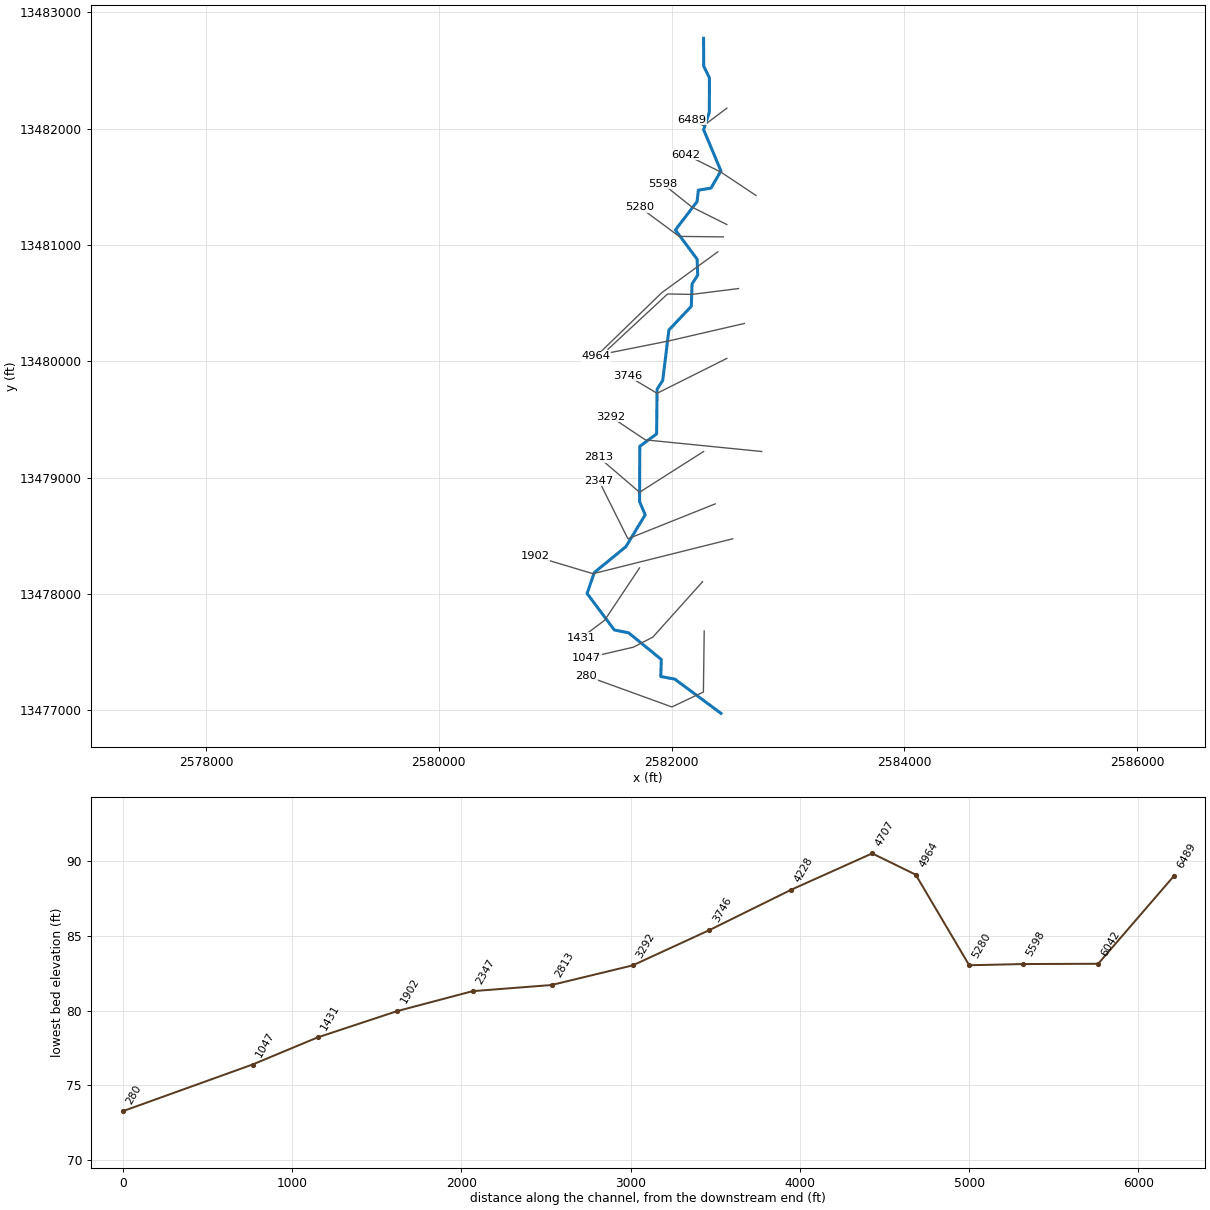
--- TRIB 4 TO DRY CREEK.prj (project) ---

Proj Title=TRIB 4 TO DRY CREEK Base Level Engineering
Current Plan=p01
Default Exp/Contr=0.3,0.1
English Units
Geom File=g01
Flow File=f01
Plan File=p01
Y Axis Title=Elevation
X Axis Title(PF)=Main Channel Distance
X Axis Title(XS)=Station
BEGIN DESCRIPTION:
TRIB 4 TO DRY CREEK
END DESCRIPTION:
DSS Export Rating Curves= 0
DSS Export Rating Curve Sorted= 0
DSS Export Volume Flow Curves= 0
DXF OffsetX= 0
DXF OffsetY= 0
DXF ScaleX= 1
DXF ScaleY= 10

--- TRIB 4 TO DRY CREEK.p01 (plan) ---

Plan Title=Multiple Run
Program Version=4.10
Short Identifier=Multiple
Geom File=g01
Flow File=f01
Subcritical Flow
K Sum by GR= 0
Std Step Tol= 0.01
Critical Tol= 0.01
Num of Std Step Trials= 20
Max Error Tol= 0.3
Flow Tol Ratio= 0.001
Split Flow NTrial= 30
Split Flow Tol= 0.02
Split Flow Ratio= 0.02
Log Output Level= 0
Friction Slope Method= 1
Unsteady Friction Slope Method= 2
Unsteady Bridges Friction Slope Method= 1
Parabolic Critical Depth
Global Vel Dist= 1 , 1 , 1
Global Log Level= 0
CheckData=True
Persistent XS Scale= 4600 , 5400 , 110 , 80 , 100 , 5
Encroach Param=-1 ,0,0, 0
BEGIN DESCRIPTION:
Multiple Run
END DESCRIPTION:
Computation Interval=1HOUR
Output Interval=1HOUR
Run HTab= 0
Run UNet= 0
Run PostProcess= 0
Run WQNet= 0
UNET Theta= 1
UNET Theta Warmup= 1
UNET ZTol= 0.02
UNET ZSATol= 0.05
UNET MxIter= 20
UNET MaxInSteps= 0
UNET DtIC= 0
UNET DtMin= 0
UNET MaxCRTS= 20
UNET WFStab= 2
UNET SFStab= 1
UNET WFX= 1
UNET SFX= 1
UNET DSS MLevel= 4
UNET DZMax Abort= 100
UNET Convert EG Bridges= 0
UNET Use Existing IB Tables=-1
UNET Froude Reduction=False
UNET Froude Limit= 1
UNET Froude Power= 10
UNET Time Slicing=0,0, 5
UNET Junction Losses=0
Instantaneous Interval=1HOUR
Write IC File= 0
Write IC File at Sim End=0
Echo Input=False
Echo Parameters=False
Echo Output=False
Write Detailed= 0
WQ AD Non Conservative
WQ ULTIMATE=-1
WQ Max Comp Step=1HOUR
WQ Output Interval=15MIN
WQ Output Selected Increments= 0
WQ Output face flow=0
WQ Output face velocity=0
WQ Output face area=0
WQ Output face dispersion=0
WQ Output cell volume=0
WQ Output cell surface area=0
WQ Output cell continuity=0
WQ Output cumulative cell continuity=0
WQ Output face conc=0
WQ Output face dconc_dx=0
WQ Output face courant=0
WQ Output face peclet=0
WQ Output face adv mass=0
WQ Output face disp mass=0
WQ Output cell mass=0
WQ Output cell source sink temp=0
WQ Output cell source sink nsm=0
WQ Output MaxMinRange=-1
WQ Daily Max Min Mean=-1
WQ Daily Range=0
WQ Daily Time=0
WQ Create Restart=0
WQ Fixed Restart=0
WQ System Summary=0
WQ Use Fixed Temperature=0
Sorting and Armoring Iterations= 10
XS Update Threshold= 0.02
Hydraulics Update Threshold= 0.02
Energy Slope Method= 1
Volume Change Method= 0
XS Weighting Method= 0
Number of US Weighted Cross Sections= 1
Number of DS Weighted Cross Sections= 1
Upstream XS Weight=0.25
Main XS Weight=0.5
Downstream XS Weight=0.25
Number of DS XS's Weighted with US Boundary= 1
Upstream Boundary Weight= 1
Weight of XSs Associated with US Boundary= 0
Number of US XS's Weighted with DS Boundary= 1
Downstream Boundary Weight= 0.5
Weight of XSs Associated with DS Boundary= 0.5
Sediment Output Level= 4
Mass or Volume Output= 0
Output Increment Type= 1
Profile and TS Output Increment= 10
XS Output Flag= 0
XS Output Increment= 10
Disregard all LS=0
Disregard all Conn=0
Disregard all Breaches=0
Disregard all Pumps=0

--- TRIB 4 TO DRY CREEK.f01 (steady flow) ---

Flow Title=Multiple
Number of Profiles=7
Profile Names=10-year,25-year,50-year,1pct_min,100-year,1pct_plu,500-year
River Rch & RM= TRIB 4 TO DRY CR,Reach-1,6489
     897    1432    1910    1231    2455    4899    4011
River Rch & RM= TRIB 4 TO DRY CR,Reach-1,4228
    1017    1632    2183    1411    2815    5617    4624
Boundary for River Rch & Prof#=TRIB 4 TO DRY CR,Reach-1,1
Up Type=0
Dn Type=3
Dn Slope=0.005
Boundary for River Rch & Prof#=TRIB 4 TO DRY CR,Reach-1,2
Up Type=0
Dn Type=3
Dn Slope=0.005
Boundary for River Rch & Prof#=TRIB 4 TO DRY CR,Reach-1,3
Up Type=0
Dn Type=3
Dn Slope=0.005
Boundary for River Rch & Prof#=TRIB 4 TO DRY CR,Reach-1,4
Up Type=0
Dn Type=3
Dn Slope=0.005
Boundary for River Rch & Prof#=TRIB 4 TO DRY CR,Reach-1,5
Up Type=0
Dn Type=3
Dn Slope=0.005
Boundary for River Rch & Prof#=TRIB 4 TO DRY CR,Reach-1,6
Up Type=0
Dn Type=3
Dn Slope=0.005
Boundary for River Rch & Prof#=TRIB 4 TO DRY CR,Reach-1,7
Up Type=0
Dn Type=3
Dn Slope=0.005

--- TRIB 4 TO DRY CREEK.g01 (geometry) ---

Geom Title=Existing Conditions
Program Version=4.10

River Reach=TRIB 4 TO DRY CR,Reach-1
Reach XY= 30
        2582275.       13482775.      2582276.22      13482535.5
      2582325.45     13482435.19      2582324.48     13482140.22
      2582275.37     13481990.27      2582424.25     13481635.68
      2582338.62     13481488.27      2582230.11     13481469.89
      2582219.44     13481372.64      2582032.78      13481128.4
      2582219.55     13480877.45      2582224.49     13480740.22
      2582176.22     13480664.49      2582169.54     13480472.55
      2581977.07     13480269.14      2581923.78      13479835.5
      2581875.52     13479759.78      2581871.55     13479376.25
      2581726.98     13479269.33      2581725.09     13478795.03
      2581773.37     13478681.04      2581608.36     13478408.32
      2581335.75     13478184.71      2581274.33     13478004.92
      2581508.21     13477691.44      2581631.17     13477667.14
      2581911.88     13477438.24      2581907.36     13477291.44
      2582027.42     13477269.48        2582425.       13476975.

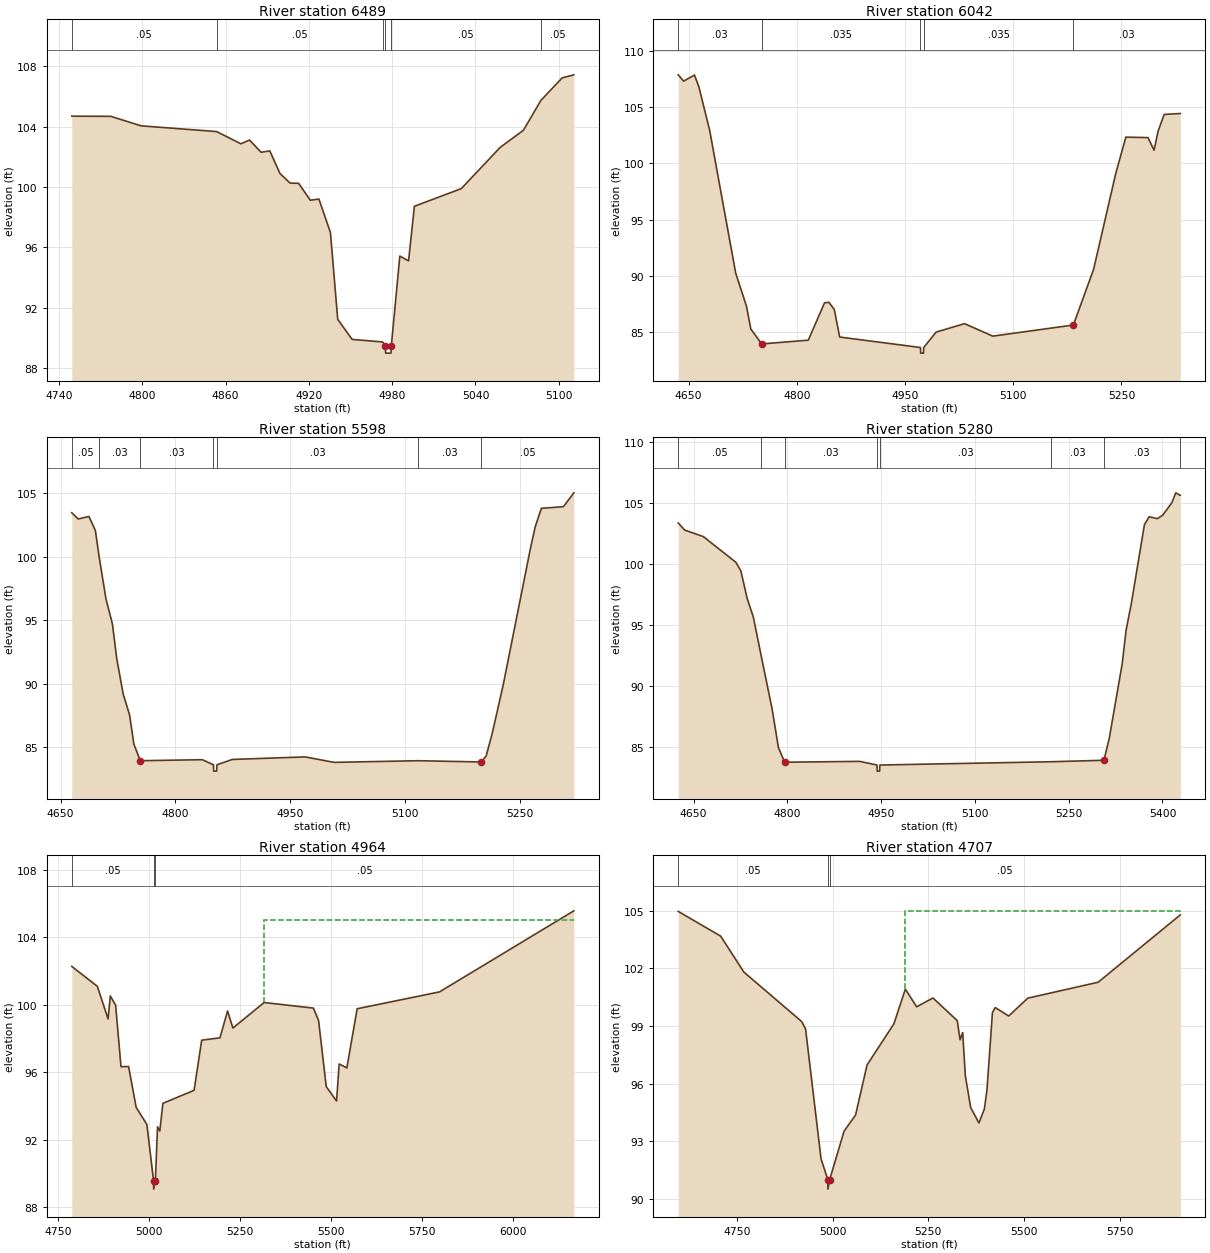
Type RM Length L Ch R = 1 ,6489    ,447,447,447
BEGIN DESCRIPTION:
TRIB 4 TO DRY CREEK 14.0
END DESCRIPTION:
XS GIS Cut Line= 3
      2582474.99     13482174.99        2582275.       13482025.
      2582174.99       13482075.
#Sta/Elev= 30
  4749.1  104.69  4777.2  104.68  4799.1  104.05  4853.5  103.67    4871  102.86
  4877.2  103.11  4885.5   102.3  4891.8  102.39  4899.1   100.9  4906.4  100.26
  4912.6  100.24    4921   99.12  4927.2    99.2  4935.5   96.98 4940.75   91.23
  4951.1    89.9  4973.1   89.73    4975   89.49  4975.3   88.99  4979.1   88.99
  4979.4   89.49  4985.5   95.42  4991.8    95.1    4996   98.72  5029.8   99.89
  5057.8  102.62  5074.6  103.76  5087.2  105.74  5102.5  107.23  5110.9  107.43
#Mann= 6 ,-1 , 0
  4749.1     .05       0  4853.5     .05       0  4973.1     .05       0
    4975     .05       0  4979.4     .05       0  5087.2     .05       0
Bank Sta=4975,4979.4
XS Rating Curve= 0 ,0
Exp/Cntr=0.3,0.1

Type RM Length L Ch R = 1 ,6042    ,444,444,444
BEGIN DESCRIPTION:
TRIB 4 TO DRY CREEK 13.0
END DESCRIPTION:
XS GIS Cut Line= 3
      2582724.99     13481425.01        2582425.       13481625.
      2582124.96     13481775.02
#Sta/Elev= 30
  4635.7  107.87  4643.2  107.31  4658.2  107.85  4664.2  106.83  4679.3  102.93
  4715.3   90.26  4730.3    87.3  4736.3   85.28  4751.4   83.95    4816   84.28
  4838.5    87.6  4844.5   87.65    4852   87.02  4859.5   84.56  4971.5   83.63
  4971.8   83.13  4975.7   83.13    4976   83.63  4993.2      85  5032.6   85.75
  5071.7   84.64  5183.5   85.63  5211.5   90.58  5242.2    99.1  5256.2  102.33
  5286.9  102.29  5295.3  101.17  5300.9  102.85  5309.3  104.35  5331.7  104.43
#Mann= 5 ,-1 , 0
  4635.7     .03       0  4751.4    .035       0  4971.5    .035       0
    4976    .035       0  5183.5     .03       0
Bank Sta=4751.4,5183.5
XS Rating Curve= 0 ,0
Exp/Cntr=0.3,0.1

Type RM Length L Ch R = 1 ,5598    ,318,318,318
BEGIN DESCRIPTION:
TRIB 4 TO DRY CREEK 12.0
END DESCRIPTION:
XS GIS Cut Line= 3
      2582475.01       13481175.        2582175.       13481325.
      2581924.98     13481525.01
#Sta/Elev= 30
  4664.6  103.45    4673  102.96    4687  103.16  4695.4  102.06  4700.7   99.85
  4709.3   96.66  4717.7   94.69  4723.3   91.98  4731.7   89.19  4740.1   87.53
  4745.7   85.23  4754.1   83.93  4835.1   84.01  4849.6   83.61  4849.9   83.11
  4853.8   83.11  4854.2   83.61  4874.2   84.03  4969.3   84.23  5007.2    83.8
  5117.3   83.93  5199.3   83.83  5205.7    84.3  5213.7    86.1  5228.1   89.94
  5263.3  100.58  5269.8  102.35  5277.8   103.8  5306.6  103.93  5320.2  105.02
#Mann= 7 ,-1 , 0
  4664.6     .05       0  4700.7     .03       0  4754.1     .03       0
  4849.6     .03       0  4854.2     .03       0  5117.3     .03       0
  5199.3     .05       0
Bank Sta=4754.1,5199.3
XS Rating Curve= 0 ,0
Exp/Cntr=0.3,0.1

Type RM Length L Ch R = 1 ,5280    ,316,316,316
BEGIN DESCRIPTION:
TRIB 4 TO DRY CREEK 11.0
END DESCRIPTION:
XS GIS Cut Line= 3
      2582445.24     13481068.98      2582065.52     13481073.32
      2581724.98     13481325.01
#Sta/Elev= 30
  4625.3  103.38  4635.5   102.8  4665.5  102.26  4717.4  100.16  4725.5   99.45
  4735.5   97.21  4745.5   95.65  4758.3   92.41  4775.5   88.12  4785.6   84.96
  4795.6   83.76  4915.6   83.83  4943.3   83.53  4943.6   83.03  4947.5   83.03
  4947.9   83.53  5221.9    83.8  5306.3   83.92  5314.7   85.68  5335.6   91.85
  5341.8    94.6  5350.2   96.79  5371.1  103.24  5378.7  103.89  5391.9  103.73
  5400.3  104.02  5414.9  105.03  5421.2  105.85  5428.2  105.65  5428.5  105.65
#Mann= 8 ,-1 , 0
  4625.3     .05       0  4758.3     .03       0  4795.6     .03       0
  4943.3     .03       0  4947.9     .03       0  5221.9     .03       0
  5306.3     .03       0  5428.2     .07       0
Bank Sta=4795.6,5306.3
XS Rating Curve= 0 ,0
Exp/Cntr=0.3,0.1

Type RM Length L Ch R = 1 ,4964    ,257,257,257
BEGIN DESCRIPTION:
Mapping XS 4e1b7dbc
END DESCRIPTION:
XS GIS Cut Line= 3
      2582397.53     13480940.93      2581915.78     13480589.38
       2581353.7     13480044.67
#Sta/Elev= 30
    4787  102.27  4857.3  101.09  4886.7   99.16  4892.9  100.52  4907.5   99.97
  4922.2   96.33  4943.1   96.34  4963.9   93.92  4993.3   92.91  5011.7   89.58
    5012   89.08  5016.6   89.58  5022.6   92.77  5028.8   92.52  5037.3   94.16
    5123   94.93  5143.9    97.9  5194.1   98.04    5215   99.63  5229.6   98.62
  5315.4  100.13  5450.7    99.8  5464.9   99.07    5486   95.15  5514.3    94.3
  5521.5   96.49  5542.6   96.26  5570.9   99.76  5797.2  100.76  6166.1  105.56
#Mann= 3 ,-1 , 0
    4787     .05       0  5011.7     .05       0  5016.6     .05       0
#XS Ineff= 2 , 0
       0                  5315.4       0     105
Permanent Ineff=
       F       F
Bank Sta=5011.7,5016.6
XS Rating Curve= 0 ,0
Exp/Cntr=0.3,0.1

Type RM Length L Ch R = 1 ,4707    ,479,479,479
BEGIN DESCRIPTION:
TRIB 4 TO DRY CREEK 10.0
END DESCRIPTION:
XS GIS Cut Line= 4
        2582575.       13480625.        2582175.       13480575.
      2581965.69     13480578.53      2581453.57      13480103.3
#Sta/Elev= 30
  4596.9  104.97  4707.8  103.68  4768.2  101.81  4919.4   99.23  4929.5   98.84
  4969.8   92.08  4987.5      91  4987.8    90.5  4992.4      91    5030   93.52
    5060   94.36    5090   96.97    5160   99.11    5190  100.92  5219.5     100
    5262  100.46  5325.5   99.28  5332.9   98.28  5339.7   98.66  5346.7    96.4
  5360.7   94.74  5382.2   93.95  5396.4   94.68  5403.2   95.69  5417.4    99.7
  5424.7   99.96  5459.9   99.52  5509.8  100.45  5693.5  101.28    5908  104.79
#Mann= 3 ,-1 , 0
  4596.9     .05       0  4987.5     .05       0  4992.4     .05       0
#XS Ineff= 2 , 0
       0                    5190       0     105
Permanent Ineff=
       F       F
Bank Sta=4987.5,4992.4
XS Rating Curve= 0 ,0
Exp/Cntr=0.3,0.1

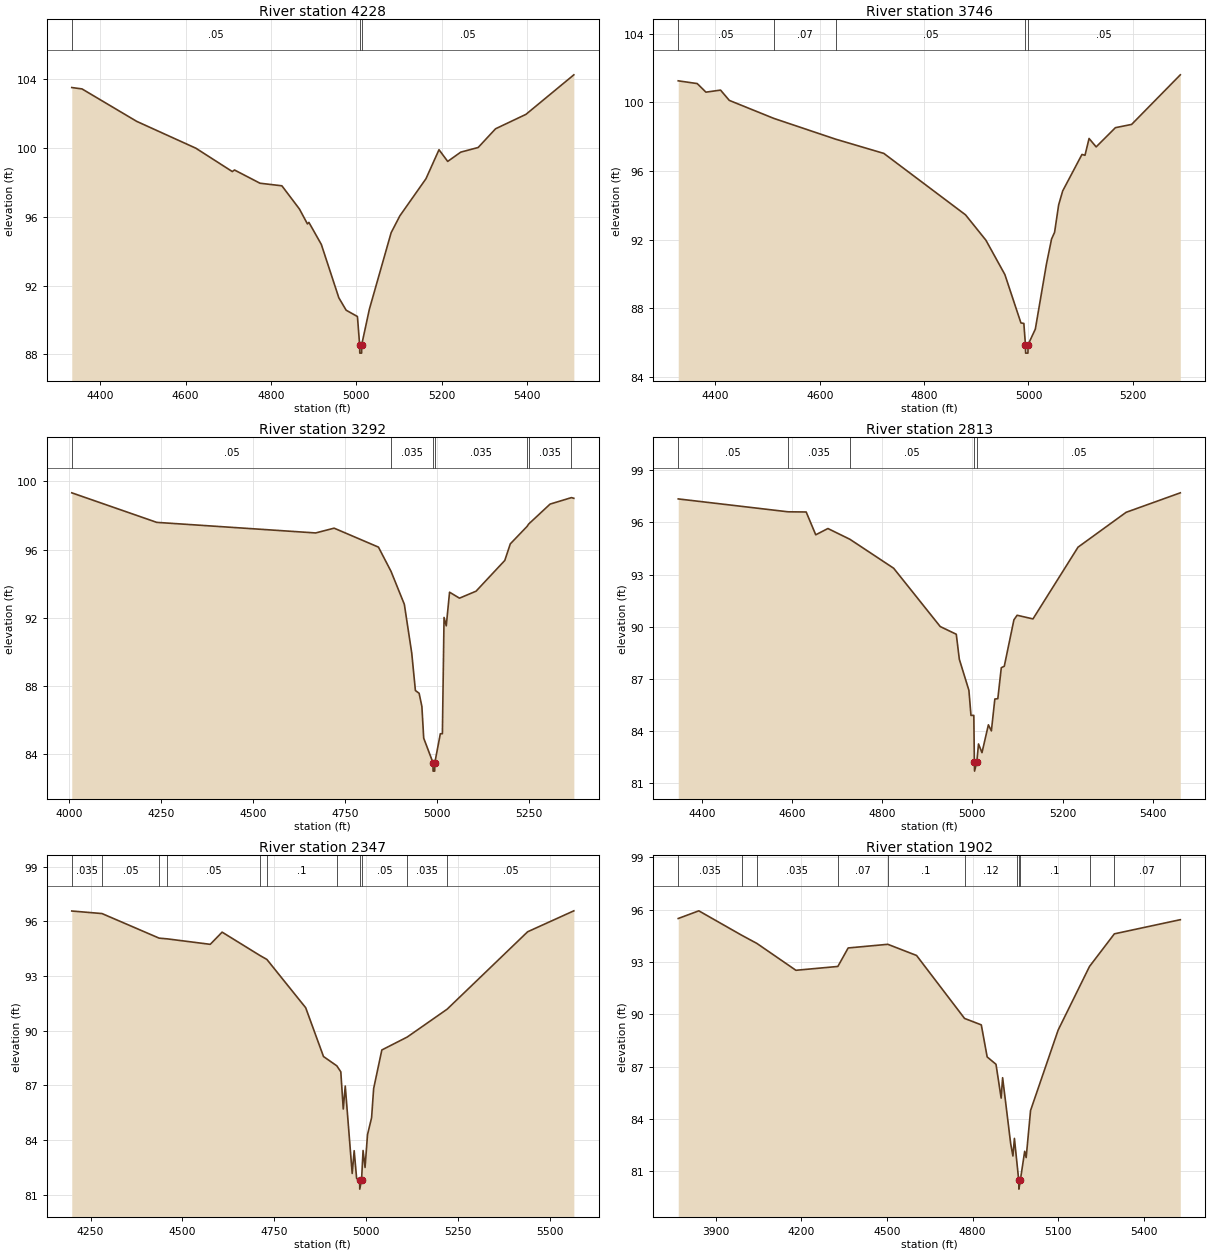
Type RM Length L Ch R = 1 ,4228    ,482,482,482
BEGIN DESCRIPTION:
TRIB 4 TO DRY CREEK 9.0
END DESCRIPTION:
XS GIS Cut Line= 3
      2582625.03     13480325.01        2581975.       13480175.
      2581475.02       13480075.
#Sta/Elev= 30
  4333.2  103.53  4357.2  103.45  4485.5  101.56    4624     100  4709.5   98.64
  4714.7   98.73  4774.5   97.96  4825.8   97.81  4866.9   96.46  4885.7   95.59
  4889.1   95.68  4918.2    94.4  4959.3   91.29  4976.4   90.57  5002.9    90.2
    5008   88.57  5008.4   88.07  5012.7   88.07    5013   88.57  5030.9   90.63
  5081.9   95.08  5102.3   96.06  5163.5   98.22  5194.1   99.91  5214.5   99.23
  5245.1   99.77  5285.9  100.04  5326.7  101.13    5398  101.97  5510.2  104.27
#Mann= 3 ,-1 , 0
  4333.2     .05       0    5008     .05       0    5013     .05       0
Bank Sta=5008,5013
XS Rating Curve= 0 ,0
Exp/Cntr=0.3,0.1

Type RM Length L Ch R = 1 ,3746    ,454,454,454
BEGIN DESCRIPTION:
TRIB 4 TO DRY CREEK 8.0
END DESCRIPTION:
XS GIS Cut Line= 3
      2582475.03     13480025.02        2581875.       13479725.
        2581625.       13479875.
#Sta/Elev= 30
  4328.7  101.25  4365.1  101.09  4381.8  100.59  4409.8  100.71  4426.6  100.11
    4512   99.06  4630.4   97.85  4722.8   97.02  4879.4   93.44  4918.5   91.96
  4954.8   89.96  4985.6   87.14  4991.2   87.11  4994.2   85.88  4994.6   85.38
    4999   85.38  4999.4   85.88  5013.2   86.78  5034.5   90.57  5044.3   92.03
  5050.1   92.42  5057.9   94.02  5065.6   94.83  5102.6   96.96  5108.4   96.91
  5116.2   97.89  5129.8    97.4  5166.7   98.52  5197.8   98.71  5291.1   101.6
#Mann= 5 ,-1 , 0
  4328.7     .05       0    4512     .07       0  4630.4     .05       0
  4994.2     .05       0  4999.4     .05       0
Bank Sta=4994.2,4999.4
XS Rating Curve= 0 ,0
Exp/Cntr=0.3,0.1

Type RM Length L Ch R = 1 ,3292    ,479,479,479
BEGIN DESCRIPTION:
TRIB 4 TO DRY CREEK 7.0
END DESCRIPTION:
XS GIS Cut Line= 3
      2582774.97       13479225.        2581775.       13479325.
      2581475.01       13479525.
#Sta/Elev= 30
  4007.5   99.32  4238.6   97.59  4670.8   96.97    4721   97.25  4841.6   96.14
  4875.8   94.72    4912   92.79  4932.1   89.94  4942.1   87.74  4952.2   87.58
  4959.7   86.81  4964.7   84.95  4989.8   83.52  4990.2   83.02  4994.6   83.02
    4995   83.52  5009.9   85.21  5015.5   85.21    5020   92.02    5026   91.53
    5035    93.5    5062   93.15  5107.1   93.56  5185.2   95.36  5200.2   96.33
  5246.1   97.36    5250   97.49  5308.4   98.66  5366.5   99.04    5373      99
#Mann= 7 ,-1 , 0
  4007.5     .05       0  4875.8    .035       0  4989.8    .035       0
    4995    .035       0  5246.1     .05       0    5250    .035       0
  5366.5     .05       0
Bank Sta=4989.8,4995
XS Rating Curve= 0 ,0
Exp/Cntr=0.3,0.1

Type RM Length L Ch R = 1 ,2813    ,466,466,466
BEGIN DESCRIPTION:
TRIB 4 TO DRY CREEK 6.0
END DESCRIPTION:
XS GIS Cut Line= 3
      2582274.96     13479224.98        2581725.       13478875.
      2581374.97     13479175.03
#Sta/Elev= 30
    4348   97.34  4591.5    96.6  4631.6   96.59  4652.8   95.28  4679.8   95.64
  4728.7   95.02  4825.5   93.36  4928.8   90.01  4964.3   89.57  4971.1   88.13
  4992.3   86.35  4996.9   84.91  5003.2   84.91  5004.4   82.21  5004.8   81.71
  5009.7   82.21  5013.6   83.27  5021.3   82.77  5035.5   84.37  5042.1   84.02
  5049.8   85.85  5056.4   85.87  5064.1   87.65  5070.7   87.73  5092.1    90.4
  5099.2   90.66  5134.3   90.45  5234.2   94.57  5340.7   96.57  5460.9   97.69
#Mann= 5 ,-1 , 0
    4348     .05       0  4591.5    .035       0  4728.7     .05       0
  5004.4     .05       0  5009.7     .05       0
Bank Sta=5004.4,5009.7
XS Rating Curve= 0 ,0
Exp/Cntr=0.3,0.1

Type RM Length L Ch R = 1 ,2347    ,445,445,445
BEGIN DESCRIPTION:
TRIB 4 TO DRY CREEK 5.0
END DESCRIPTION:
XS GIS Cut Line= 3
      2582375.03     13478775.01        2581625.       13478475.
      2581375.01     13478974.98
#Sta/Elev= 30
    4199   96.57  4281.3   96.43  4436.9   95.08  4459.1   95.04    4576   94.74
  4608.3   95.41  4711.1   94.13  4730.2   93.91  4835.8   91.26  4884.3   88.58
  4920.5   88.07  4931.4   87.74  4938.1    85.7  4943.5   86.96  4962.4   82.16
  4967.8   83.41  4974.5   81.88  4982.6    81.8    4983    81.3  4987.9    81.8
    4992   83.42  4997.4   82.49  5004.1   84.29  5015.2   85.22  5020.8   86.82
  5043.1   88.94  5112.2   89.65  5220.9   91.18    5440   95.43  5565.8   96.58
#Mann= 11 ,-1 , 0
    4199    .035       0  4281.3     .05       0  4436.9    .035       0
  4459.1     .05       0  4711.1    .035       0  4730.2      .1       0
  4920.5     .05       0  4982.6     .05       0  4987.9     .05       0
  5112.2    .035       0  5220.9     .05       0
Bank Sta=4982.6,4987.9
XS Rating Curve= 0 ,0
Exp/Cntr=0.3,0.1

Type RM Length L Ch R = 1 ,1902    ,471,471,471
BEGIN DESCRIPTION:
TRIB 4 TO DRY CREEK 4.0
END DESCRIPTION:
XS GIS Cut Line= 3
      2582524.99       13478475.        2581325.       13478175.
      2580825.04     13478324.99
#Sta/Elev= 30
  3768.6   95.49  3840.7   95.93  3990.9   94.53  4044.2   94.06  4180.9   92.52
  4327.8   92.74  4363.9    93.8  4502.8   94.01  4603.5   93.37  4771.6   89.76
  4830.3   89.39  4850.9   87.55  4881.8   87.13  4899.9   85.19    4905   86.36
  4933.4   82.56  4941.1   81.87  4946.3   82.88  4954.7   81.55  4961.5   80.47
    4962   79.97    4967   80.47  4982.3   82.14  4987.5   81.78  5002.9   84.48
  5099.5   89.09  5209.4   92.74  5296.5   94.61    5527   95.42  5527.5   95.42
#Mann= 12 ,-1 , 0
  3768.6    .035       0  3990.9     .05       0  4044.2    .035       0
  4327.8     .07       0  4502.8      .1       0  4771.6     .12       0
  4954.7      .1       0  4961.5     .05       0    4967      .1       0
  5209.4     .12       0  5296.5     .07       0    5527     .05       0
Bank Sta=4961.5,4967
XS Rating Curve= 0 ,0
Exp/Cntr=0.3,0.1

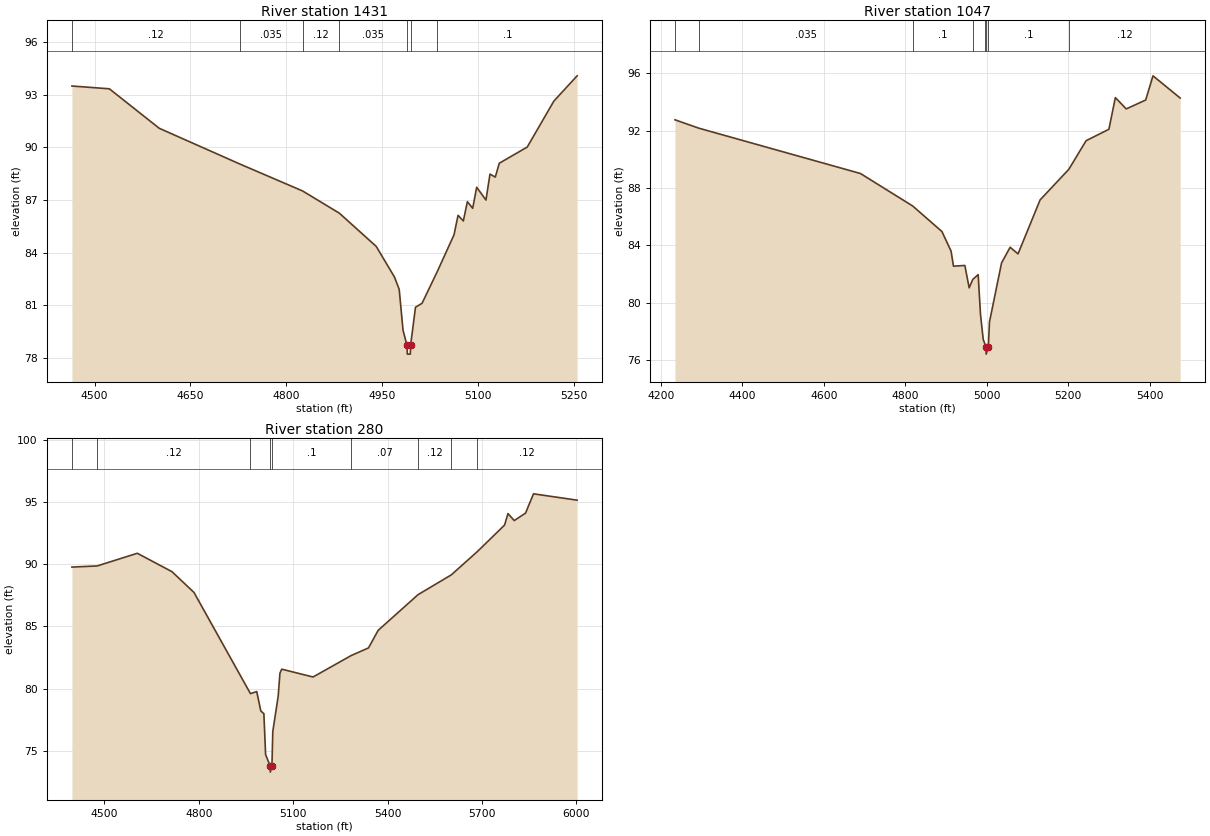
Type RM Length L Ch R = 1 ,1431    ,384,384,384
BEGIN DESCRIPTION:
TRIB 4 TO DRY CREEK 3.0
END DESCRIPTION:
XS GIS Cut Line= 3
      2581725.01     13478225.01        2581425.       13477775.
      2581225.04     13477625.03
#Sta/Elev= 30
  4464.6   93.49  4523.2   93.33  4601.3   91.08  4727.7   89.04  4825.6   87.51
  4883.3   86.24  4940.9   84.35  4969.4   82.61  4976.9    81.9  4982.9   79.57
  4989.1   78.71  4989.6   78.21  4994.3   78.21  4994.7   78.71  5002.4   80.88
  5012.7   81.11  5036.7   82.93  5062.7   85.01    5069   86.12  5077.3    85.8
  5083.6    86.9  5091.9   86.52  5098.2   87.72  5112.7   86.99    5119   88.47
  5127.3    88.3  5133.6   89.09  5177.3   90.01    5219   92.63  5255.4   94.07
#Mann= 7 ,-1 , 0
  4464.6     .12       0  4727.7    .035       0  4825.6     .12       0
  4883.3    .035       0  4989.1    .035       0  4994.7    .035       0
  5036.7      .1       0
Bank Sta=4989.1,4994.7
XS Rating Curve= 0 ,0
Exp/Cntr=0.3,0.1

Type RM Length L Ch R = 1 ,1047    ,767,767,767
BEGIN DESCRIPTION:
Mapping XS 302d7c8a
END DESCRIPTION:
XS GIS Cut Line= 4
      2582266.61     13478106.49      2581839.51     13477630.77
      2581672.84     13477543.97      2581270.04     13477450.21
#Sta/Elev= 30
  4234.2   92.76  4293.4   92.17  4689.8   89.01  4818.2   86.74  4889.9   84.96
  4912.4   83.59  4918.3   82.54  4946.2   82.59  4956.8   81.03  4965.8   81.62
  4978.9   81.95  4984.6   79.18  4991.3   77.43  4995.8   77.08  4998.2    76.9
  4998.6    76.4  5003.9    76.9  5006.7   78.65  5036.4   82.77  5057.4   83.86
  5076.8    83.4  5131.1   87.17  5201.5    89.3    5244    91.3    5300    92.1
  5315.9   94.31  5342.6   93.52  5390.3   94.14  5408.3   95.83    5475   94.28
#Mann= 8 ,-1 , 0
  4234.2     .05       0  4293.4    .035       0  4818.2      .1       0
  4965.8     .07       0  4995.8      .1       0  4998.2     .05       0
  5003.9      .1       0  5201.5     .12       0
Bank Sta=4998.2,5003.9
XS Rating Curve= 0 ,0
Exp/Cntr=0.3,0.1

Type RM Length L Ch R = 1 ,280     ,0,0,0
BEGIN DESCRIPTION:
TRIB 4 TO DRY CREEK 1.0
END DESCRIPTION:
XS GIS Cut Line= 4
      2582280.48     13477682.82      2582273.53     13477158.55
       2582002.7     13477030.08      2581268.32     13477296.81
#Sta/Elev= 30
  4396.9   89.77  4477.1   89.86  4604.7   90.88  4714.8    89.4  4784.8   87.73
  4964.3   79.59  4984.2   79.76  4997.1    78.2  5006.9   77.98  5012.4   74.69
  5026.8   73.78  5027.2   73.28  5032.5   73.78  5035.2   76.55  5052.4   79.39
  5057.9   81.23  5063.5   81.56  5163.1   80.93  5284.7   82.66  5339.4   83.27
    5370   84.68  5496.7   87.55  5602.3   89.14  5684.6      91  5771.8   93.15
  5782.5   94.07  5802.5   93.51  5838.4   94.11  5863.7   95.66  6002.3   95.15
#Mann= 9 ,-1 , 0
  4396.9     .05       0  4477.1     .12       0  4964.3      .1       0
  5026.8     .05       0  5032.5      .1       0  5284.7     .07       0
  5496.7     .12       0  5602.3     .07       0  5684.6     .12       0
Bank Sta=5026.8,5032.5
XS Rating Curve= 0 ,0
Exp/Cntr=0.3,0.1

Chan Stop Cuts=-1
Use User Specified Reach Order=0
Composite Channel Slope=5