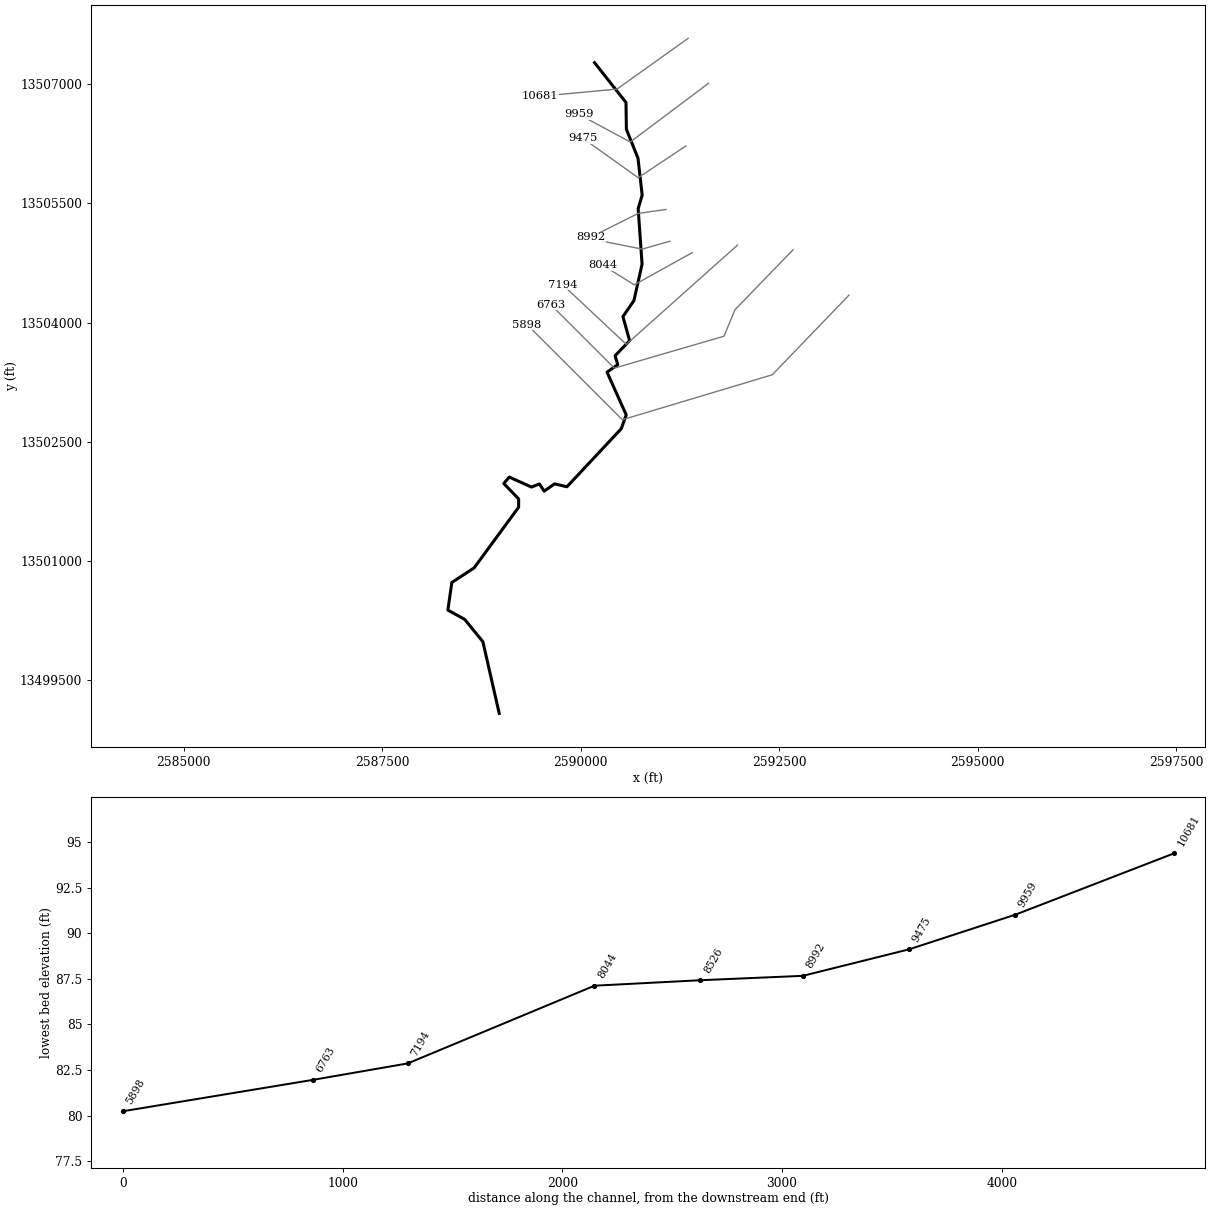
--- TRIB 4 TO GUADALUPE RIVER.prj (project) ---

Proj Title=TRIB 4 TO GUADALUPE RIVER Base Level Engineering
Current Plan=p01
Default Exp/Contr=0.3,0.1
English Units
Geom File=g01
Flow File=f01
Plan File=p01
Y Axis Title=Elevation
X Axis Title(PF)=Main Channel Distance
X Axis Title(XS)=Station
BEGIN DESCRIPTION:
TRIB 4 TO GUADALUPE RIVER
END DESCRIPTION:
DSS Export Rating Curves= 0
DSS Export Rating Curve Sorted= 0
DSS Export Volume Flow Curves= 0
DXF OffsetX= 0
DXF OffsetY= 0
DXF ScaleX= 1
DXF ScaleY= 10

--- TRIB 4 TO GUADALUPE RIVER.p01 (plan) ---

Plan Title=Multiple Run
Short Identifier=Multiple
Geom File=g01
Flow File=f01
Subcritical Flow
K Sum by GR= 0
Std Step Tol= 0.01
Critical Tol= 0.01
Num of Std Step Trials= 20
Max Error Tol= 0.3
Flow Tol Ratio= 0.001
Split Flow NTrial= 30
Split Flow Tol= 0.02
Split Flow Ratio= 0.02
Log Output Level= 0
Friction Slope Method= 1
Unsteady Friction Slope Method= 2
Unsteady Bridges Friction Slope Method= 1
Parabolic Critical Depth
Global Vel Dist=  1 , 1 , 1
Global Log Level= 0
CheckData=True
Encroach Param= -1, 0, 0, 0
BEGIN DESCRIPTION:
Multiple Run
END DESCRIPTION:

--- TRIB 4 TO GUADALUPE RIVER.f01 (steady flow) ---

Flow Title=Multiple
Number of Profiles=7
Profile Names=10-year,25-year,50-year,1pct_min,100-year,1pct_plu,500-year
River Rch & RM= TRIB 4 TO GUADAL,Reach-1,10681
     749    1168    1532     970    1936    3862    3054
Boundary for River Rch & Prof#=TRIB 4 TO GUADAL,Reach-1,1
Up Type=0
Dn Type=3
Dn Slope=0.005
Boundary for River Rch & Prof#=TRIB 4 TO GUADAL,Reach-1,2
Up Type=0
Dn Type=3
Dn Slope=0.005
Boundary for River Rch & Prof#=TRIB 4 TO GUADAL,Reach-1,3
Up Type=0
Dn Type=3
Dn Slope=0.005
Boundary for River Rch & Prof#=TRIB 4 TO GUADAL,Reach-1,4
Up Type=0
Dn Type=3
Dn Slope=0.005
Boundary for River Rch & Prof#=TRIB 4 TO GUADAL,Reach-1,5
Up Type=0
Dn Type=3
Dn Slope=0.005
Boundary for River Rch & Prof#=TRIB 4 TO GUADAL,Reach-1,6
Up Type=0
Dn Type=3
Dn Slope=0.005
Boundary for River Rch & Prof#=TRIB 4 TO GUADAL,Reach-1,7
Up Type=0
Dn Type=3
Dn Slope=0.005

--- TRIB 4 TO GUADALUPE RIVER.g01 (geometry) ---

Geom Title=Existing Conditions
Program Version=4.10

River Reach=TRIB 4 TO GUADAL,Reach-1
Reach XY= 30
        2590175.       13507275.      2590571.25     13506773.45
      2590576.22      13506435.5      2590722.74     13506069.06
      2590775.09      13505604.9      2590724.54     13505435.18
      2590773.78      13504735.5      2590671.25     13504276.55
      2590532.55       13504075.      2590616.96     13503771.68
      2590434.03     13503582.01      2590467.61     13503468.67
      2590332.45     13503375.21      2590574.24     13502835.69
       2590511.6      13502661.7      2589827.43      13501930.4
      2589671.59     13501967.19      2589541.04     13501875.21
        2589482.     13501965.92      2589381.13     13501926.84
      2589101.53     13502052.56      2589032.59     13501971.69
       2589219.6     13501777.43       2589219.6     13501672.57
       2588658.5     13500907.95      2588378.45     13500723.75
      2588328.44     13500376.25      2588541.68     13500258.36
      2588769.52     13499977.44        2588975.       13499075.

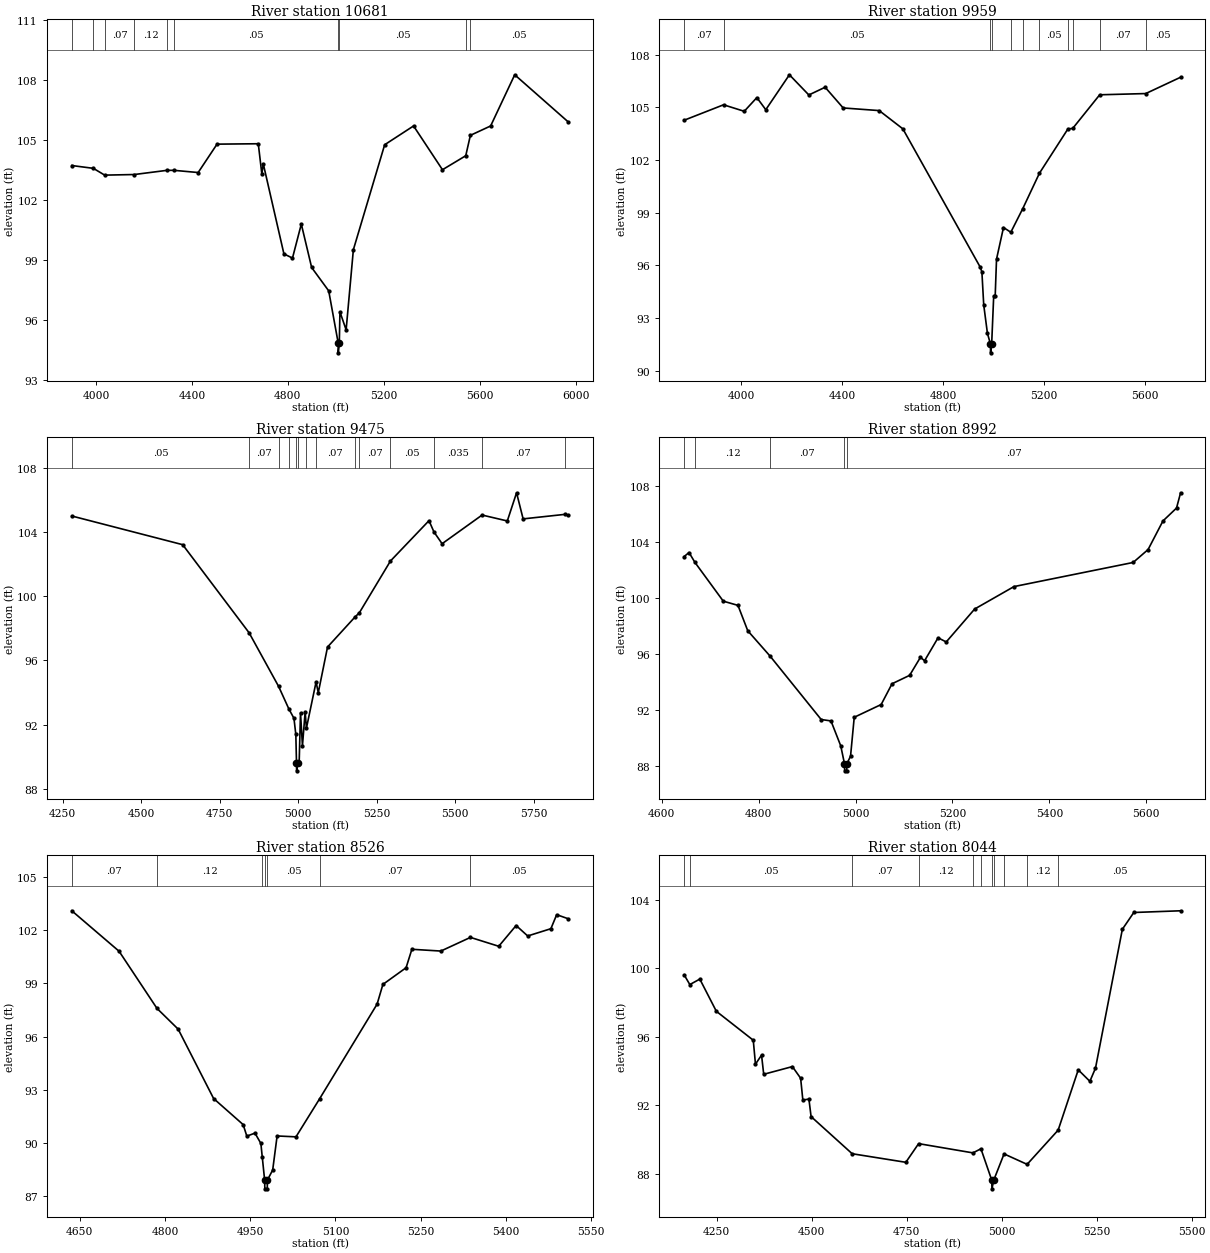
Type RM Length L Ch R = 1 ,10681   ,722,722,722
BEGIN DESCRIPTION:
TRIB 4 TO GUADALUPE RIVER 16.0
END DESCRIPTION:
XS GIS Cut Line= 3
      2591353.84     13507581.16      2590458.05     13506941.55
      2589492.69     13506851.99
#Sta/Elev= 30
  3899.3  103.74  3989.1   103.6  4036.4  103.26  4159.7  103.29  4296.6   103.5
  4325.2   103.5  4426.2  103.39  4504.9  104.81  4676.9  104.83  4691.7  103.32
  4697.8  103.82  4783.8   99.32  4819.5   99.11  4856.3  100.81  4899.4   98.64
  4970.6   97.47    5010   94.87  5010.4   94.37  5014.8   94.87  5017.4   96.42
  5043.2   95.52  5073.4   99.53  5203.9  104.78  5324.4  105.72  5444.9  103.53
    5542  104.23  5561.3  105.25  5645.8  105.72  5746.2  108.28  5969.5  105.92
#Mann= 10 ,-1 , 0
  3899.3     .07       0  3989.1     .12       0  4036.4     .07       0
  4159.7     .12       0  4296.6     .07       0  4325.2     .05       0
    5010     .05       0  5014.8     .05       0    5542     .07       0
  5561.3     .05       0
Bank Sta=5010,5014.8
XS Rating Curve= 0 ,0
Exp/Cntr=0.3,0.1

Type RM Length L Ch R = 1 ,9959    ,484,484,484
BEGIN DESCRIPTION:
TRIB 4 TO GUADALUPE RIVER 15.0
END DESCRIPTION:
XS GIS Cut Line= 3
       2591609.6       13507014.        2590625.       13506275.
      2589975.02     13506624.99
#Sta/Elev= 30
  3773.3  104.26  3929.6  105.14  4011.8  104.77  4061.8  105.55  4097.2  104.86
  4190.9  106.85    4268   105.7  4332.6  106.14  4404.2  104.96  4547.1  104.81
  4640.9  103.77  4947.1   95.91  4954.4   95.63  4961.7   93.74  4976.3   92.13
  4988.4   91.51  4988.8   91.01  4993.2   91.51  5001.3   94.26  5007.2   94.26
  5012.5   96.35  5040.1   98.15  5069.2   97.88  5116.7   99.23  5182.6  101.24
  5295.9  103.77  5314.4  103.79  5421.7  105.71  5604.4  105.78  5742.6  106.71
#Mann= 11 ,-1 , 0
  3773.3     .07       0  3929.6     .05       0  4988.4     .05       0
  4993.2     .05       0  5069.2    .035       0  5116.7     .07       0
  5182.6     .05       0  5295.9     .07       0  5314.4     .05       0
  5421.7     .07       0  5604.4     .05       0
Bank Sta=4988.4,4993.2
XS Rating Curve= 0 ,0
Exp/Cntr=0.3,0.1

Type RM Length L Ch R = 1 ,9475    ,483,483,483
BEGIN DESCRIPTION:
TRIB 4 TO GUADALUPE RIVER 14.0
END DESCRIPTION:
XS GIS Cut Line= 3
      2591325.04     13506225.03        2590725.       13505825.
      2590024.99     13506325.01
#Sta/Elev= 30
  4278.8  105.02  4631.9  103.23  4843.5   97.73  4937.6   94.38  4970.3   92.97
  4986.4   92.39  4992.4   91.38  4994.5   89.61  4994.9   89.11  4999.4   89.61
    5003   89.61  5007.3   92.73  5013.5   90.68  5022.1   92.79  5026.1   91.77
  5056.9   94.66  5063.9   93.99  5093.4   96.84  5180.2    98.7  5194.8   98.98
  5293.8  102.21  5416.6  104.73  5432.2  104.03  5458.3  103.29  5585.7  105.08
    5666  104.71  5695.5  106.47  5716.4  104.84  5848.5  105.12  5860.2  105.08
#Mann= 14 ,-1 , 0
  4278.8     .05       0  4843.5     .07       0  4937.6     .05       0
  4970.3     .07       0  4994.5     .05       0  4999.4     .07       0
  5026.1     .05       0  5056.9     .07       0  5180.2     .05       0
  5194.8     .07       0  5293.8     .05       0  5432.2    .035       0
  5585.7     .07       0  5848.5     .05       0
Bank Sta=4994.5,4999.4
XS Rating Curve= 0 ,0
Exp/Cntr=0.3,0.1

Type RM Length L Ch R = 1 ,8992    ,466,466,466
BEGIN DESCRIPTION:
TRIB 4 TO GUADALUPE RIVER 13.0
END DESCRIPTION:
XS GIS Cut Line= 3
      2591074.98       13505425.        2590725.       13505375.
      2590124.96     13505074.98
#Sta/Elev= 30
  4646.3  102.94  4656.4  103.23  4668.5  102.53  4727.1   99.76  4757.4   99.46
  4777.6   97.65  4823.7   95.84  4929.1   91.32  4949.3   91.22  4969.5   89.44
  4977.2   88.16  4977.5   87.66  4981.7   87.66  4982.1   88.16  4989.7   88.71
  4997.3   91.48  5052.9   92.39  5075.3   93.87  5111.6   94.47    5134   95.76
  5142.4   95.51  5170.3   97.15  5187.1   96.85  5245.8    99.2  5326.9   100.8
  5572.8  102.52  5603.6  103.44  5634.3  105.48  5662.3   106.4  5670.7  107.49
#Mann= 5 ,-1 , 0
  4646.3     .07       0  4668.5     .12       0  4823.7     .07       0
  4977.2     .05       0  4982.1     .07       0
Bank Sta=4977.2,4982.1
XS Rating Curve= 0 ,0
Exp/Cntr=0.3,0.1

Type RM Length L Ch R = 1 ,8526    ,482,482,482
BEGIN DESCRIPTION:
TRIB 4 TO GUADALUPE RIVER 12.0
END DESCRIPTION:
XS GIS Cut Line= 3
      2591125.01       13505025.        2590775.       13504925.
      2590275.02       13505025.
#Sta/Elev= 30
    4636  103.09  4719.2  100.81  4785.9   97.59  4823.2   96.42  4885.6   92.51
  4937.6   91.04  4944.1   90.39  4958.4   90.56  4968.8   89.98  4971.3    89.2
  4975.4   87.92  4975.8   87.42    4980   87.42  4980.4   87.92  4989.6   88.48
  4997.4    90.4  5030.6   90.35  5072.3    92.5  5173.4   97.83  5183.6   98.94
  5224.4   99.88  5234.6  100.92  5285.6  100.82  5337.7  101.59  5387.5  101.09
  5418.1  102.26  5438.5  101.67  5479.3  102.08  5489.5  102.87  5509.9  102.64
#Mann= 7 ,-1 , 0
    4636     .07       0  4785.9     .12       0  4971.3     .05       0
  4975.4     .05       0  4980.4     .05       0  5072.3     .07       0
  5337.7     .05       0
Bank Sta=4975.4,4980.4
XS Rating Curve= 0 ,0
Exp/Cntr=0.3,0.1

Type RM Length L Ch R = 1 ,8044    ,850,850,850
BEGIN DESCRIPTION:
TRIB 4 TO GUADALUPE RIVER 11.0
END DESCRIPTION:
XS GIS Cut Line= 3
      2591405.14     13504880.63        2590675.       13504475.
      2590275.04     13504724.97
#Sta/Elev= 30
  4164.3   99.62  4179.3   99.05  4205.6   99.37  4249.1   97.49  4346.3    95.8
  4352.1    94.4  4368.1   94.93  4373.8   93.81  4449.3   94.26    4471   93.58
  4476.8   92.31  4492.8   92.36  4498.5   91.34  4606.7   89.17  4747.9   88.67
  4781.6   89.76  4924.6   89.22  4945.6   89.46  4974.2   87.62  4974.6   87.12
  4979.2   87.62  5006.5   89.16  5067.2   88.55  5148.9   90.55  5201.8   94.07
  5232.4    93.4  5247.2   94.17  5317.9  102.28    5348  103.26  5471.2  103.36
#Mann= 11 ,-1 , 0
  4164.3     .07       0  4179.3     .05       0  4606.7     .07       0
  4781.6     .12       0  4924.6      .1       0  4945.6     .12       0
  4974.2     .05       0  4979.2     .12       0  5006.5      .1       0
  5067.2     .12       0  5148.9     .05       0
Bank Sta=4974.2,4979.2
XS Rating Curve= 0 ,0
Exp/Cntr=0.3,0.1

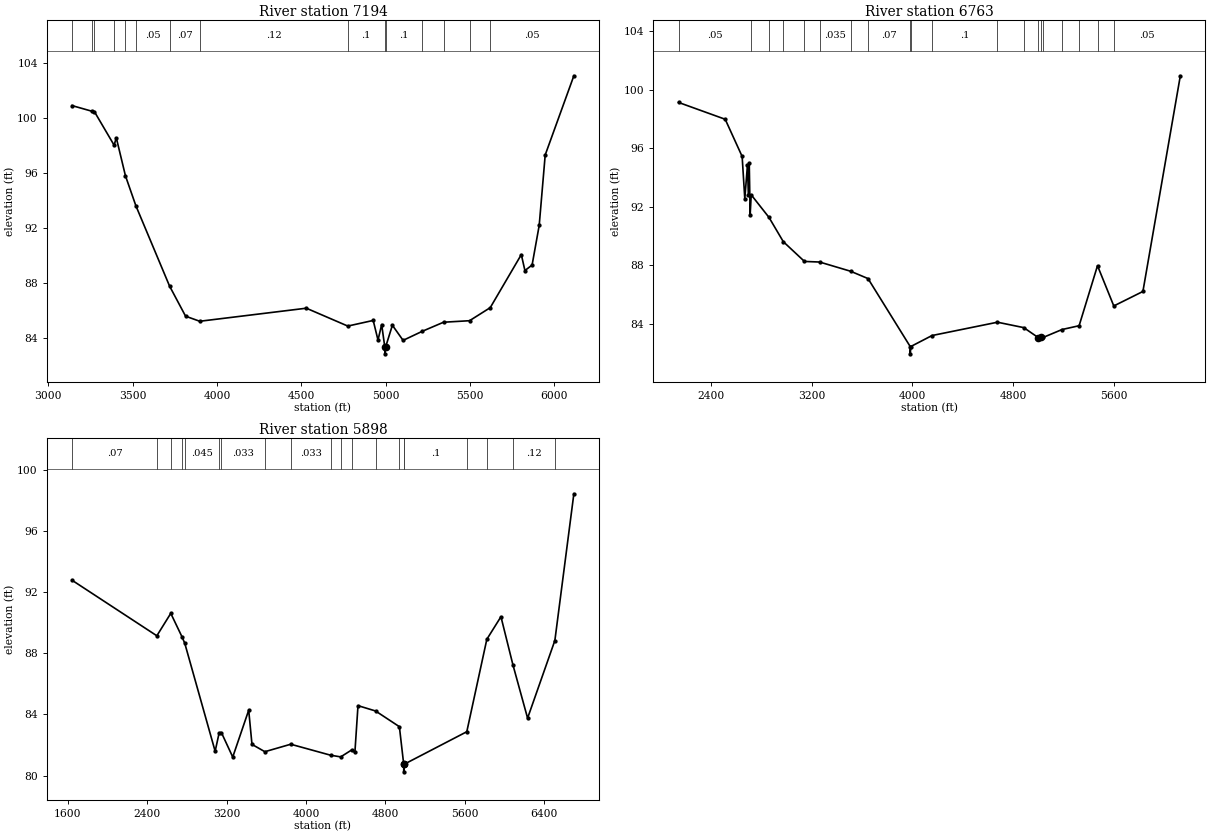
Type RM Length L Ch R = 1 ,7194    ,431,431,431
BEGIN DESCRIPTION:
TRIB 4 TO GUADALUPE RIVER 10.0
END DESCRIPTION:
XS GIS Cut Line= 3
      2591975.03     13504975.02        2590575.       13503725.
      2589774.97     13504475.03
#Sta/Elev= 30
  3141.3  100.92  3261.9   100.5  3273.7  100.48  3390.5   98.04  3403.4   98.58
  3457.7   95.81  3519.5   93.63    3719   87.79  3813.9    85.6  3897.8   85.23
  4529.5   86.18  4775.2   84.88  4925.8   85.29  4954.2   83.86  4975.9   84.99
  4994.4   83.36  4994.7   82.86  4999.4   83.36  5039.4   84.94  5102.9   83.84
  5216.6    84.5  5342.6   85.16  5496.6   85.27  5619.3   86.22  5803.4   90.08
  5824.8   88.92  5867.3   89.32  5909.4    92.2    5945   97.33  6114.8  103.09
#Mann= 15 ,-1 , 0
  3141.3     .07       0  3261.9     .05       0  3273.7     .12       0
  3390.5     .05       0  3457.7     .07       0  3519.5     .05       0
    3719     .07       0  3897.8     .12       0  4775.2      .1       0
  4994.4     .05       0  4999.4      .1       0  5216.6     .12       0
  5342.6      .1       0  5496.6     .12       0  5619.3     .05       0
Bank Sta=4994.4,4999.4
XS Rating Curve= 0 ,0
Exp/Cntr=0.3,0.1

Type RM Length L Ch R = 1 ,6763    ,865,865,865
BEGIN DESCRIPTION:
TRIB 4 TO GUADALUPE RIVER 9.0
END DESCRIPTION:
XS GIS Cut Line= 5
      2592675.79     13504918.05       2591944.6     13504162.26
      2591804.69     13503827.47        2590425.       13503425.
      2589625.01     13504224.99
#Sta/Elev= 30
  2143.7   99.13  2514.1   97.98  2648.6   95.44  2669.7   92.54  2690.9   94.87
    2698   92.81    2705   94.97  2712.2   91.45  2720.5   92.82  2861.5   91.28
  2975.3   89.62  3143.4   88.27  3263.6   88.23  3509.8    87.6  3647.7    87.1
  3982.4   82.46  3982.8   81.96  3987.4   82.46  4155.7   83.21  4675.3   84.12
  4883.9   83.75  4998.9   83.07  5023.6   83.11  5037.8   83.08  5187.7   83.62
  5323.3   83.88  5469.3   87.98  5598.6   85.23  5829.7   86.22  6126.7  100.95
#Mann= 20 ,-1 , 0
  2143.7     .05       0  2720.5    .035       0  2861.5    .035       0
  2975.3     .12       0  3143.4     .07       0  3263.6    .035       0
  3509.8     .07       0  3647.7     .07       0  3982.4     .07       0
  3987.4     .12       0  4155.7      .1       0  4675.3     .12       0
  4883.9      .1       0  4998.9     .05       0  5023.6     .07       0
  5037.8      .1       0  5187.7     .12       0  5323.3      .1       0
  5469.3      .1       0  5598.6     .05       0
Bank Sta=4998.9,5023.6
XS Rating Curve= 0 ,0
Exp/Cntr=0.3,0.1

Type RM Length L Ch R = 1 ,5898    ,0,0,0
BEGIN DESCRIPTION:
TRIB 4 TO GUADALUPE RIVER 8.0
END DESCRIPTION:
XS GIS Cut Line= 4
       2593378.9     13504345.11      2592413.31     13503341.49
        2590525.       13502775.      2589325.01     13503974.99
#Sta/Elev= 30
  1641.6    92.8  2496.7   89.16  2637.2   90.63  2749.8    89.1  2777.8   88.68
  3084.7   81.59  3125.3    82.8  3148.1   82.81  3262.2   81.21  3423.2   84.28
  3456.2   82.04  3586.3   81.56  3847.3   82.05  4249.3   81.33  4351.1   81.22
  4463.1   81.68  4494.2   81.51  4525.5   84.58  4702.6   84.23    4943    83.2
  4986.5   80.74    4987   80.24  4991.9   80.74  5622.9   82.87    5825   88.93
  5967.4   90.41    6088   87.26  6236.1   83.76  6511.2   88.85  6702.8   98.47
#Mann= 20 ,-1 , 0
  1641.6     .07       0  2496.7    .035       0  2637.2    .045       0
  2749.8    .035       0  2777.8    .045       0  3125.3     .05       0
  3148.1    .033       0  3586.3     .12       0  3847.3    .033       0
  4249.3    .035       0  4351.1    .033       0  4463.1    .045       0
  4702.6     .07       0    4943      .1       0  4986.5     .05       0
  4991.9      .1       0  5622.9     .12       0    5825     .07       0
    6088     .12       0  6511.2     .05       0
Bank Sta=4986.5,4991.9
XS Rating Curve= 0 ,0
Exp/Cntr=0.3,0.1

Chan Stop Cuts=-1
Use User Specified Reach Order=0
Composite Channel Slope=5