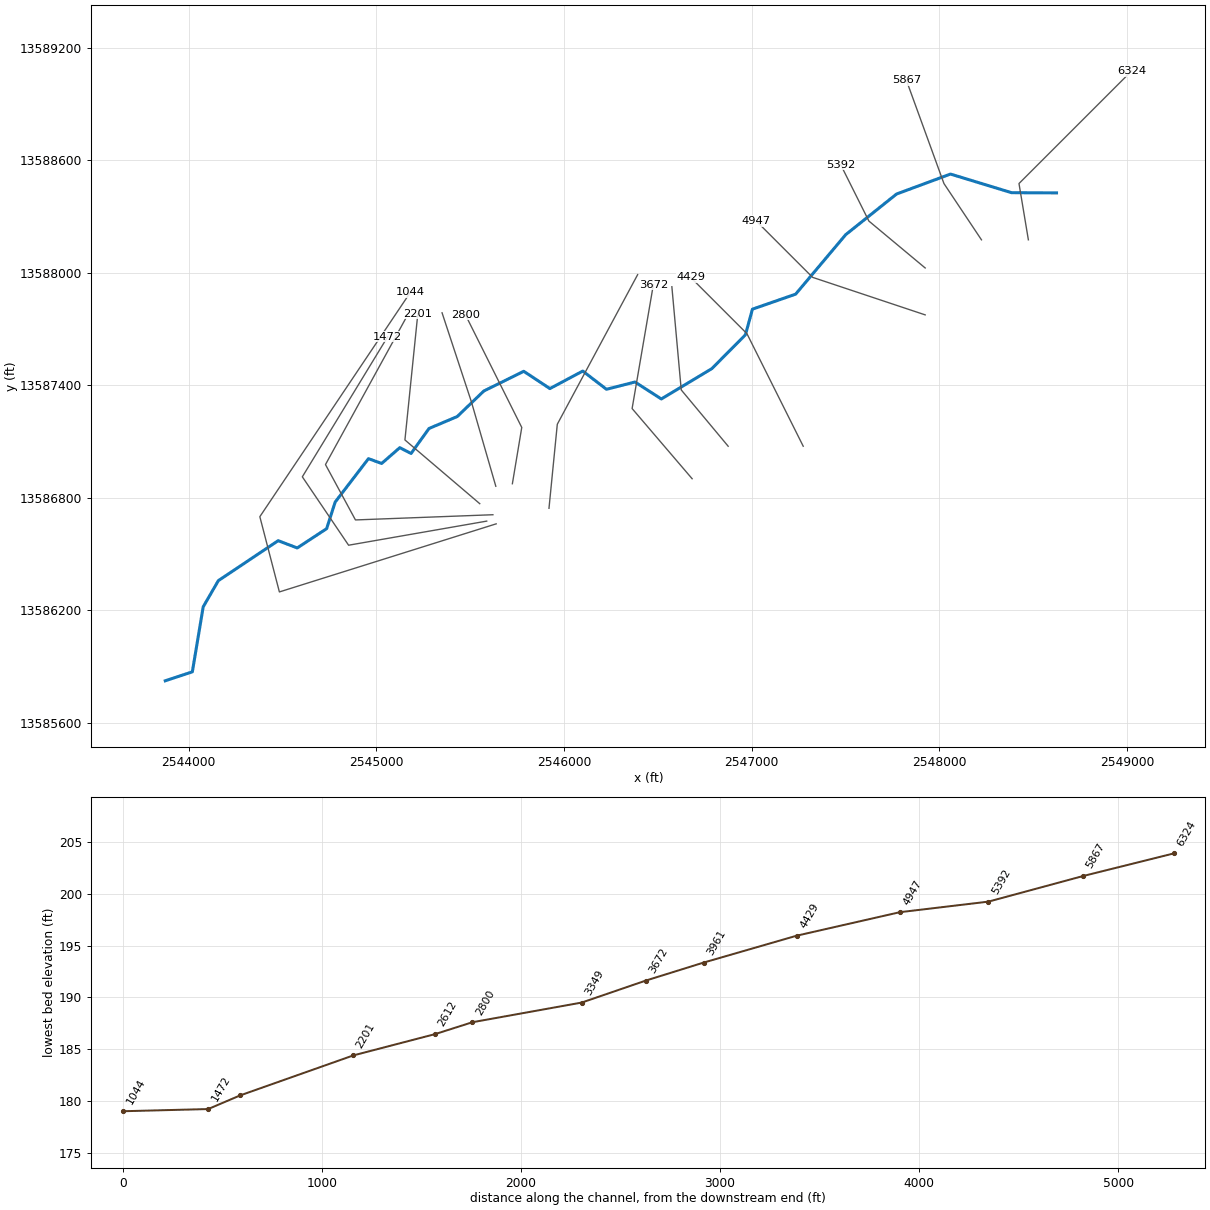
--- TRIB 4 TO IRISH CREEK.prj (project) ---

Proj Title=TRIB 4 TO IRISH CREEK Base Level Engineering
Current Plan=p01
Default Exp/Contr=0.3,0.1
English Units
Geom File=g01
Flow File=f01
Plan File=p01
BEGIN DESCRIPTION:
TRIB 4 TO IRISH CREEK
END DESCRIPTION:

--- TRIB 4 TO IRISH CREEK.p01 (plan) ---

Plan Title=Multiple Run
Short Identifier=Multiple
Geom File=g01
Flow File=f01
Subcritical Flow
K Sum by GR= 0
Std Step Tol= 0.01
Critical Tol= 0.01
Num of Std Step Trials= 20
Max Error Tol= 0.3
Flow Tol Ratio= 0.001
Split Flow NTrial= 30
Split Flow Tol= 0.02
Split Flow Ratio= 0.02
Log Output Level= 0
Friction Slope Method= 1
Unsteady Friction Slope Method= 2
Unsteady Bridges Friction Slope Method= 1
Parabolic Critical Depth
Global Vel Dist=  1 , 1 , 1
Global Log Level= 0
CheckData=True
Encroach Param= -1, 0, 0, 0
BEGIN DESCRIPTION:
Multiple Run
END DESCRIPTION:

--- TRIB 4 TO IRISH CREEK.f01 (steady flow) ---

Flow Title=Multiple
Number of Profiles=7
Profile Names=10-year,25-year,50-year,1pct_min,100-year,1pct_plu,500-year
River Rch & RM= TRIB 4 TO IRISH ,Reach-1,6324
     517     824    1100     713    1422    2837    2348
River Rch & RM= TRIB 4 TO IRISH ,Reach-1,5392
     731    1183    1594    1041    2077    4145    3490
Boundary for River Rch & Prof#=TRIB 4 TO IRISH ,Reach-1,1
Up Type=0
Dn Type=3
Dn Slope=0.005
Boundary for River Rch & Prof#=TRIB 4 TO IRISH ,Reach-1,2
Up Type=0
Dn Type=3
Dn Slope=0.005
Boundary for River Rch & Prof#=TRIB 4 TO IRISH ,Reach-1,3
Up Type=0
Dn Type=3
Dn Slope=0.005
Boundary for River Rch & Prof#=TRIB 4 TO IRISH ,Reach-1,4
Up Type=0
Dn Type=3
Dn Slope=0.005
Boundary for River Rch & Prof#=TRIB 4 TO IRISH ,Reach-1,5
Up Type=0
Dn Type=3
Dn Slope=0.005
Boundary for River Rch & Prof#=TRIB 4 TO IRISH ,Reach-1,6
Up Type=0
Dn Type=3
Dn Slope=0.005
Boundary for River Rch & Prof#=TRIB 4 TO IRISH ,Reach-1,7
Up Type=0
Dn Type=3
Dn Slope=0.005

--- TRIB 4 TO IRISH CREEK.g01 (geometry) ---

Geom Title=Existing Conditions

River Reach=TRIB 4 TO IRISH ,Reach-1
Reach XY= 30
      2548625.00     13588425.00      2548385.50     13588426.22
      2548059.84     13588525.47      2547772.70     13588419.17
      2547501.16     13588202.14      2547234.79     13587885.52
      2547004.43     13587805.42      2546967.14     13587668.83
      2546788.21     13587488.63      2546518.88     13587326.76
      2546378.41     13587417.19      2546226.50     13587378.47
      2546100.03     13587475.50      2545925.00     13587382.10
      2545785.70     13587474.30      2545572.70     13587369.17
      2545431.05     13587233.14      2545280.61     13587169.40
      2545185.02     13587036.24      2545125.00     13587067.41
      2545028.32     13586983.04      2544957.96     13587008.76
      2544780.53     13586777.42      2544735.05     13586635.62
      2544578.40     13586532.83      2544476.74     13586571.63
      2544157.95     13586358.51      2544077.25     13586219.07
      2544019.32     13585872.43      2543875.00     13585825.00

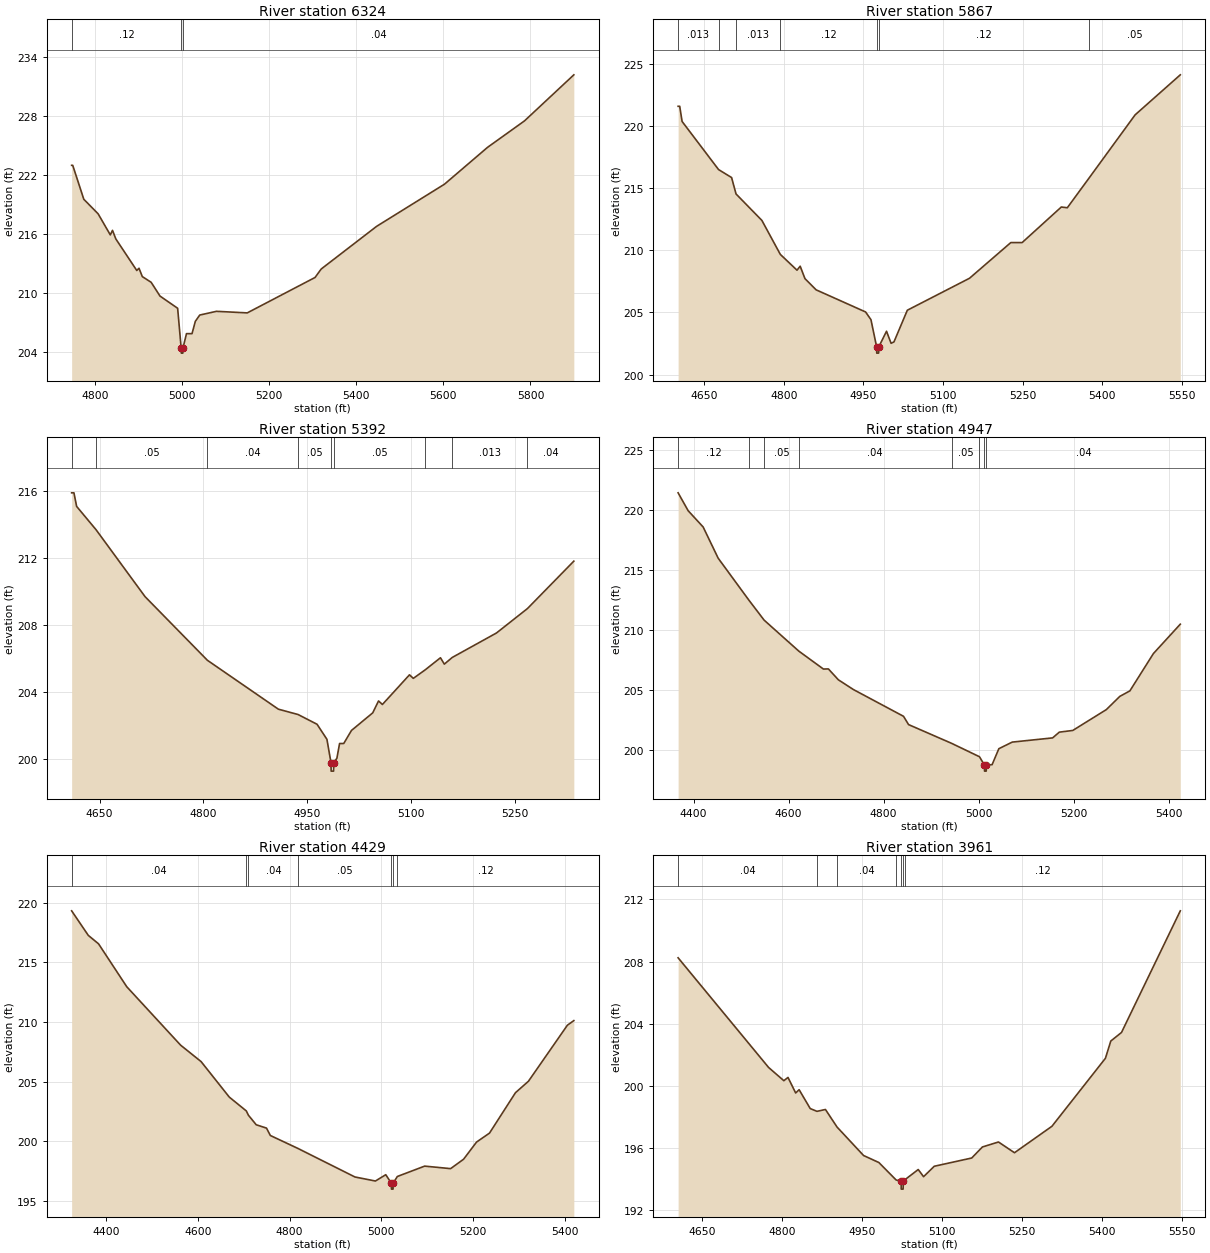
Type RM Length L Ch R = 1,6324,457,457,457
BEGIN DESCRIPTION:
TRIB 4 TO IRISH CREEK 10.0
END DESCRIPTION:
XS GIS Cut Line= 3
      2548475.00     13588175.01      2548425.00     13588475.00
      2549025.03     13589075.03
#Sta/Elev= 30
  4746.9  223.01  4749.4  223.01  4774.8  219.56  4807.7  218.08  4835.6  215.94
  4840.7  216.40  4848.3  215.53  4896.4  212.32  4901.5  212.55  4909.1  211.70
  4929.4  211.12  4949.7  209.72  4990.2  208.48  4998.3  204.42  4998.6  203.92
  5002.1  203.92  5002.3  204.42  5010.5  205.90  5023.2  205.90  5030.8  207.15
  5040.9  207.79  5079.3  208.17  5150.0  208.01  5305.6  211.61  5319.7  212.47
  5447.0  216.81  5602.6  221.09  5701.6  224.84  5786.4  227.53  5899.6  232.21
#Mann=3,-1,0
  4746.9    0.12       0  4998.3    0.04       0  5002.3    0.04       0
Bank Sta=4998.3,5002.3
Exp/Cntr=0.3,0.1

Type RM Length L Ch R = 1,5867,475,475,475
BEGIN DESCRIPTION:
TRIB 4 TO IRISH CREEK 9.0
END DESCRIPTION:
XS GIS Cut Line= 3
      2548225.01     13588174.98      2548025.00     13588475.00
      2547825.01     13589024.98
#Sta/Elev= 30
  4600.9  221.58  4603.9  221.58  4608.4  220.36  4677.1  216.49  4701.6  215.85
  4710.0  214.53  4758.7  212.40  4793.4  209.67  4824.8  208.40  4830.8  208.72
  4839.8  207.72  4860.8  206.82  4954.0  205.04  4964.1  204.42  4974.8  202.23
  4975.0  201.73  4978.5  201.73  4978.8  202.23  4993.4  203.49  5002.0  202.52
  5007.4  202.63  5032.6  205.18  5149.7  207.75  5227.5  210.62  5248.8  210.62
  5322.6  213.48  5333.9  213.42  5375.2  215.83  5461.6  220.89  5546.7  224.11
#Mann=7,-1,0
  4600.9   0.013       0  4677.1    0.12       0  4710.0   0.013       0
  4793.4    0.12       0  4974.8    0.05       0  4978.8    0.12       0
  5375.2    0.05       0
Bank Sta=4974.8,4978.8
Exp/Cntr=0.3,0.1

Type RM Length L Ch R = 1,5392,445,445,445
BEGIN DESCRIPTION:
TRIB 4 TO IRISH CREEK 8.0
END DESCRIPTION:
XS GIS Cut Line= 3
      2547925.01     13588024.99      2547625.00     13588275.00
      2547475.01     13588574.97
#Sta/Elev= 30
  4609.7  215.88  4613.0  215.88  4616.9  215.07  4645.1  213.67  4715.8  209.68
  4805.9  205.88  4908.5  202.96  4937.0  202.64  4964.4  202.06  4978.7  201.16
  4984.6  199.76  4984.8  199.26  4988.3  199.26  4988.6  199.76  4993.1  200.03
  4997.0  200.91  5003.0  200.91  5014.2  201.69  5044.9  202.74  5053.3  203.45
  5058.9  203.24  5098.0  205.01  5103.6  204.80  5120.8  205.31  5142.8  206.03
  5148.4  205.65  5159.9  206.05  5223.8  207.51  5268.6  208.97  5335.6  211.80
#Mann=9,-1,0
  4609.7    0.12       0  4645.1    0.05       0  4805.9    0.04       0
  4937.0    0.05       0  4984.6    0.05       0  4988.6    0.05       0
  5120.8    0.04       0  5159.9   0.013       0  5268.6    0.04       0
Bank Sta=4984.6,4988.6
Exp/Cntr=0.3,0.1

Type RM Length L Ch R = 1,4947,518,518,518
BEGIN DESCRIPTION:
TRIB 4 TO IRISH CREEK 7.0
END DESCRIPTION:
XS GIS Cut Line= 3
      2547924.97     13587775.01      2547325.00     13587975.00
      2547024.99     13588275.01
#Sta/Elev= 30
  4367.6  221.44  4388.7  219.95  4420.3  218.59  4451.9  215.99  4516.8  212.48
  4548.5  210.83  4621.4  208.25  4673.3  206.75  4683.8  206.76  4704.9  205.85
  4736.5  205.04  4841.9  202.81  4852.5  202.12  4942.9  200.56  5001.7  199.44
  5012.2  198.74  5012.4  198.24  5015.9  198.24  5016.2  198.74  5028.3  198.78
  5042.5  200.11  5070.7  200.66  5155.6  201.01  5169.7  201.49  5198.0  201.63
  5268.7  203.37  5297.0  204.47  5318.2  204.93  5367.7  208.04  5424.3  210.49
#Mann=8,-1,0
  4367.6    0.12       0  4516.8    0.04       0  4548.5    0.05       0
  4621.4    0.04       0  4942.9    0.05       0  5001.7    0.04       0
  5012.2    0.05       0  5016.2    0.04       0
Bank Sta=5012.2,5016.2
Exp/Cntr=0.3,0.1

Type RM Length L Ch R = 1,4429,468,468,468
BEGIN DESCRIPTION:
TRIB 4 TO IRISH CREEK 6.0
END DESCRIPTION:
XS GIS Cut Line= 3
      2547275.01     13587074.99      2546975.00     13587675.00
      2546675.00     13587975.00
#Sta/Elev= 30
  4324.8  219.32  4361.1  217.26  4383.5  216.55  4445.0  212.95  4562.4  208.05
  4607.1  206.67  4668.6  203.69  4705.7  202.53  4710.3  202.17  4727.3  201.37
  4749.7  201.09  4758.1  200.47  4819.0  199.37  4942.5  196.99  4987.2  196.65
  5009.8  197.18  5021.9  196.47  5022.2  195.97  5025.7  195.97  5025.9  196.47
  5035.0  197.03  5094.6  197.90  5151.2  197.69  5179.5  198.48  5207.8  199.92
  5236.0  200.67  5292.6  204.06  5320.9  205.02  5405.8  209.72  5419.9  210.11
#Mann=7,-1,0
  4324.8    0.04       0  4705.7    0.05       0  4710.3    0.04       0
  4819.0    0.05       0  5021.9    0.05       0  5025.9    0.05       0
  5035.0    0.12       0
Bank Sta=5021.9,5025.9
Exp/Cntr=0.3,0.1

Type RM Length L Ch R = 1,3961,289,289,289
BEGIN DESCRIPTION:
TRIB 4 TO IRISH CREEK 5.0
END DESCRIPTION:
XS GIS Cut Line= 3
      2546875.02     13587074.98      2546625.00     13587375.00
      2546575.00     13587924.99
#Sta/Elev= 30
  4604.9  208.24  4774.8  201.19  4803.4  200.34  4811.2  200.55  4825.6  199.55
  4832.1  199.76  4852.9  198.55  4865.6  198.37  4881.5  198.49  4903.3  197.36
  4953.1  195.53  4981.8  195.08  5014.1  193.96  5023.6  193.87  5023.8  193.37
  5027.3  193.37  5027.6  193.87  5030.5  193.97  5055.7  194.63  5065.7  194.17
  5085.8  194.84  5156.1  195.37  5176.2  196.08  5206.3  196.40  5236.4  195.71
  5306.7  197.41  5407.1  201.78  5417.2  202.89  5437.3  203.44  5547.7  211.26
#Mann=7,-1,0
  4604.9    0.04       0  4865.6    0.05       0  4903.3    0.04       0
  5014.1    0.05       0  5023.6    0.04       0  5027.6    0.05       0
  5030.5    0.12       0
Bank Sta=5023.6,5027.6
Exp/Cntr=0.3,0.1

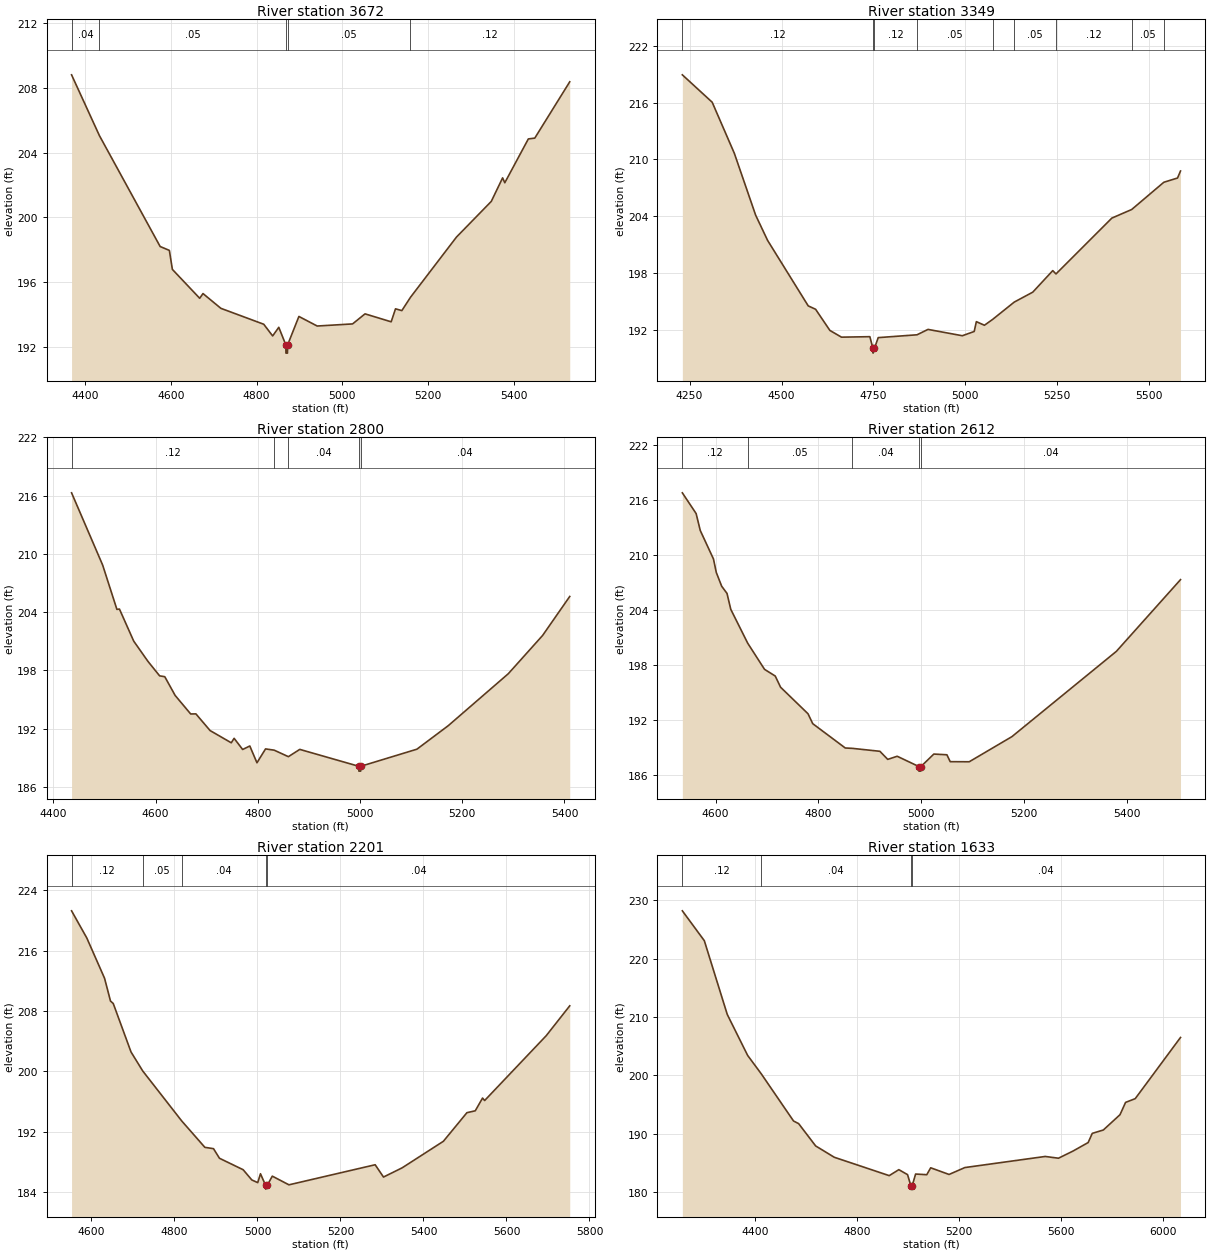
Type RM Length L Ch R = 1,3672,323,323,323
BEGIN DESCRIPTION:
Mapping XS 0e0c8f17
END DESCRIPTION:
XS GIS Cut Line= 3
      2546683.02     13586901.70      2546363.09     13587275.78
      2546476.29     13587935.30
#Sta/Elev= 30
  4368.8  208.79  4433.6  205.05  4575.3  198.21  4596.8  197.97  4603.8  196.80
  4667.5  195.02  4675.2  195.31  4716.9  194.40  4816.8  193.42  4837.6  192.70
  4851.9  193.23  4868.4  192.14  4868.6  191.64  4872.1  191.64  4872.4  192.14
  4898.8  193.90  4941.4  193.31  5023.9  193.44  5053.0  194.06  5113.9  193.57
  5124.0  194.37  5138.8  194.26  5158.9  195.08  5266.1  198.79  5347.3  200.99
  5373.7  202.44  5378.8  202.14  5433.7  204.84  5448.7  204.89  5530.2  208.36
#Mann=5,-1,0
  4368.8    0.04       0  4433.6    0.05       0  4868.4    0.05       0
  4872.4    0.05       0  5158.9    0.12       0
Bank Sta=4868.4,4872.4
Exp/Cntr=0.3,0.1

Type RM Length L Ch R = 1,3349,549,549,549
BEGIN DESCRIPTION:
Mapping XS 6a35f368
END DESCRIPTION:
XS GIS Cut Line= 3
      2545920.12     13586744.23      2545964.42     13587192.11
      2546392.62     13587989.44
#Sta/Elev= 30
  4230.2  218.96  4311.4  216.06  4371.7  210.65  4429.5  204.12  4462.1  201.44
  4572.6  194.51  4592.7  194.15  4631.6  191.91  4663.1  191.20  4740.3  191.25
  4748.7  190.01  4749.0  189.51  4752.7  190.01  4763.0  191.15  4868.6  191.45
  4898.5  192.02  4991.8  191.35  5024.1  191.80  5030.0  192.84  5051.9  192.46
  5074.0  193.07  5133.0  194.91  5183.4  195.96  5237.8  198.24  5246.6  197.89
  5398.6  203.80  5452.6  204.71  5539.9  207.59  5577.2  208.04  5585.3  208.78
#Mann=9,-1,0
  4230.2    0.12       0  4748.7    0.05       0  4752.7    0.12       0
  4868.6    0.05       0  5074.0    0.12       0  5133.0    0.05       0
  5246.6    0.12       0  5452.6    0.05       0  5539.9    0.12       0
Bank Sta=4748.7,4752.7
Exp/Cntr=0.3,0.1

Type RM Length L Ch R = 1,2800,188,188,188
BEGIN DESCRIPTION:
TRIB 4 TO IRISH CREEK 3.0
END DESCRIPTION:
XS GIS Cut Line= 3
      2545725.01     13586875.04      2545775.00     13587175.00
      2545475.01     13587774.99
#Sta/Elev= 30
  4435.4  216.29  4496.2  208.85  4524.1  204.28  4529.1  204.31  4557.0  201.01
  4584.9  198.92  4607.7  197.43  4617.8  197.34  4638.1  195.41  4668.5  193.50
  4678.7  193.51  4706.5  191.79  4747.9  190.53  4753.5  190.99  4770.2  189.84
  4784.2  190.20  4798.2  188.47  4815.0  189.90  4831.9  189.77  4859.7  189.10
  4882.0  189.85  4997.4  188.11  4997.7  187.61  5001.2  187.61  5001.4  188.11
  5111.2  189.87  5172.7  192.30  5290.1  197.65  5357.2  201.59  5410.3  205.61
#Mann=5,-1,0
  4435.4    0.12       0  4831.9    0.05       0  4859.7    0.04       0
  4997.4    0.04       0  5001.4    0.04       0
Bank Sta=4997.4,5001.4
Exp/Cntr=0.3,0.1

Type RM Length L Ch R = 1,2612,411,411,411
BEGIN DESCRIPTION:
Mapping XS 65630946
END DESCRIPTION:
XS GIS Cut Line= 3
      2545636.69     13586861.58      2545506.47     13587312.12
      2545350.23     13587786.05
#Sta/Elev= 30
  4535.5  216.78  4562.3  214.52  4570.3  212.68  4596.0  209.57  4601.5  208.10
  4611.9  206.61  4622.3  205.82  4629.6  204.09  4662.5  200.40  4695.2  197.55
  4716.0  196.82  4726.4  195.60  4779.7  192.71  4788.9  191.63  4852.1  188.98
  4866.0  188.94  4919.4  188.62  4934.6  187.74  4953.0  188.08  4995.1  186.96
  4995.3  186.46  4998.8  186.46  4999.1  186.96  5024.2  188.32  5049.6  188.24
  5056.0  187.49  5093.0  187.48  5176.0  190.22  5378.9  199.51  5503.5  207.32
#Mann=5,-1,0
  4535.5    0.12       0  4662.5    0.05       0  4866.0    0.04       0
  4995.1    0.04       0  4999.1    0.04       0
Bank Sta=4995.1,4999.1
Exp/Cntr=0.3,0.1

Type RM Length L Ch R = 1,2201,568,568,568
BEGIN DESCRIPTION:
Mapping XS e9dca3f2
END DESCRIPTION:
XS GIS Cut Line= 3
      2545551.02     13586768.81      2545152.32     13587108.44
      2545221.09     13587781.39
#Sta/Elev= 30
  4552.2  221.28  4588.9  217.68  4631.7  212.34  4646.0  209.32  4652.6  209.00
  4695.4  202.58  4723.6  200.06  4817.5  193.44  4873.3  189.94  4894.2  189.76
  4908.5  188.49  4965.6  186.97  4986.4  185.62  5000.7  185.26  5007.3  186.44
  5019.6  184.90  5019.8  184.40  5023.6  184.90  5035.8  186.12  5075.9  184.97
  5283.6  187.63  5303.7  186.00  5348.6  187.22  5448.0  190.74  5504.7  194.53
  5524.8  194.78  5542.4  196.47  5547.4  196.14  5695.7  204.73  5752.4  208.69
#Mann=5,-1,0
  4552.2    0.12       0  4723.6    0.05       0  4817.5    0.04       0
  5019.6    0.04       0  5023.6    0.04       0
Bank Sta=5019.6,5023.6
Exp/Cntr=0.3,0.1

Type RM Length L Ch R = 1,1633,161,161,161
BEGIN DESCRIPTION:
Mapping XS 64916816
END DESCRIPTION:
XS GIS Cut Line= 4
      2545621.28     13586709.90      2544888.64     13586682.12
      2544728.91     13586977.26      2545156.01     13587755.06
#Sta/Elev= 30
  4114.1  228.16  4200.4  223.05  4290.5  210.43  4370.5  203.42  4423.5  200.30
  4550.7  192.20  4570.7  191.75  4637.6  187.93  4710.8  185.99  4926.4  182.85
  4964.2  183.87  4998.4  183.02  5012.0  181.04  5012.2  180.54  5016.0  181.04
  5030.1  183.12  5073.9  183.01  5089.3  184.19  5161.4  183.05  5223.4  184.23
  5539.0  186.13  5591.0  185.83  5648.0  187.05  5707.6  188.51  5723.7  190.08
  5767.3  190.66  5832.7  193.28  5854.5  195.38  5892.4  196.02  6070.2  206.49
#Mann=4,-1,0
  4114.1    0.12       0  4423.5    0.04       0  5012.0    0.04       0
  5016.0    0.04       0
Bank Sta=5012,5016
Exp/Cntr=0.3,0.1

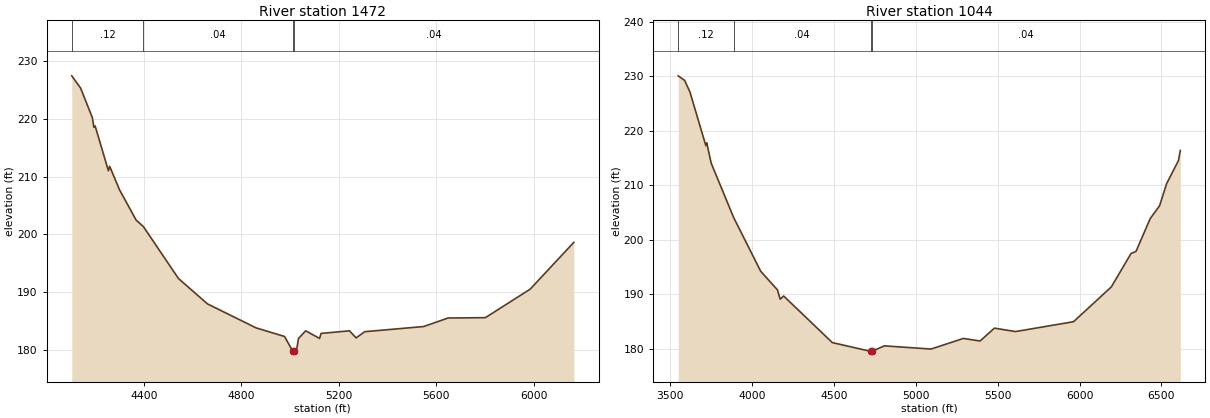
Type RM Length L Ch R = 1,1472,428,428,428
BEGIN DESCRIPTION:
Mapping XS f485125b
END DESCRIPTION:
XS GIS Cut Line= 4
      2545588.19     13586675.87      2544852.08     13586547.40
      2544605.56     13586911.98      2545060.20     13587658.14
#Sta/Elev= 30
  4103.8  227.46  4140.2  225.33  4188.2  220.22  4194.7  218.54  4199.8  218.76
  4254.2  211.01  4259.3  211.78  4299.9  207.70  4368.2  202.44  4397.6  201.34
  4541.8  192.33  4660.8  187.93  4860.5  183.77  4977.3  182.28  5011.3  179.72
  5011.5  179.22  5015.3  179.72  5028.2  180.29  5034.3  181.92  5064.2  183.26
  5121.1  181.94  5127.2  182.81  5244.0  183.26  5271.0  182.03  5306.4  183.11
  5548.0  184.00  5648.7  185.48  5801.7  185.54  5985.6  190.48  6164.9  198.60
#Mann=4,-1,0
  4103.8    0.12       0  4397.6    0.04       0  5011.3    0.04       0
  5015.3    0.04       0
Bank Sta=5011.3,5015.3
Exp/Cntr=0.3,0.1

Type RM Length L Ch R = 1,1044,0,0,0
BEGIN DESCRIPTION:
Mapping XS 3a83d5f0
END DESCRIPTION:
XS GIS Cut Line= 4
      2545638.63     13586661.29      2544483.25     13586298.44
      2544379.09     13586699.49      2545180.92     13587894.54
#Sta/Elev= 30
  3550.5  230.09  3589.6  229.25  3622.0  227.12  3719.2  217.27  3724.5  217.80
  3751.6  214.06  3889.3  204.05  4053.8  194.22  4156.3  190.80  4172.7  189.09
  4193.9  189.68  4490.9  181.13  4726.2  179.51  4726.5  179.01  4730.2  179.51
  4809.3  180.53  5093.2  179.94  5291.1  181.89  5393.1  181.42  5480.1  183.78
  5609.1  183.15  5963.2  184.96  6194.1  191.35  6314.5  197.49  6344.4  197.86
  6431.4  203.89  6488.4  206.24  6531.3  210.29  6603.5  214.53  6615.0  216.39
#Mann=4,-1,0
  3550.5    0.12       0  3889.3    0.04       0  4726.2    0.04       0
  4730.2    0.04       0
Bank Sta=4726.2,4730.2
Exp/Cntr=0.3,0.1

Chan Stop Cuts=-1