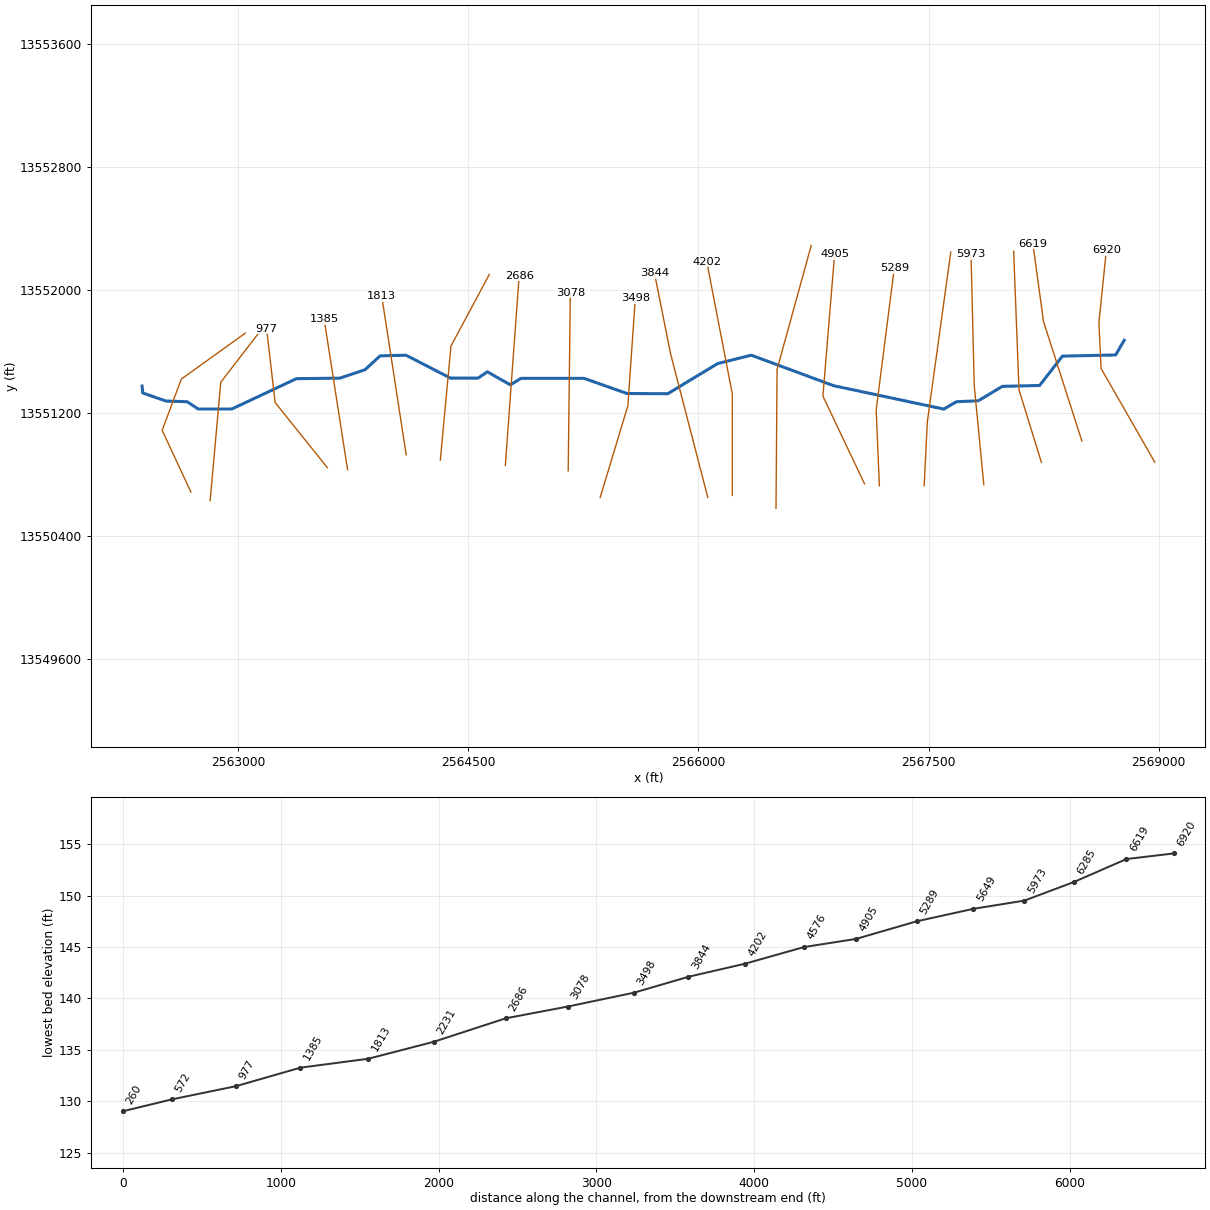
--- TRIB 4 TO PRICE CREEK.prj (project) ---

Proj Title=TRIB 4 TO PRICE CREEK Base Level Engineering
Current Plan=p01
Default Exp/Contr=0.3,0.1
English Units
Geom File=g01
Flow File=f01
Plan File=p01
Y Axis Title=Elevation
X Axis Title(PF)=Main Channel Distance
X Axis Title(XS)=Station
BEGIN DESCRIPTION:
TRIB 4 TO PRICE CREEK
END DESCRIPTION:
DSS Export Rating Curves= 0
DSS Export Rating Curve Sorted= 0
DSS Export Volume Flow Curves= 0
DXF OffsetX= 0
DXF OffsetY= 0
DXF ScaleX= 1
DXF ScaleY= 10

--- TRIB 4 TO PRICE CREEK.p01 (plan) ---

Plan Title=Multiple Run
Short Identifier=Multiple
Geom File=g01
Flow File=f01
Subcritical Flow
K Sum by GR= 0
Std Step Tol= 0.01
Critical Tol= 0.01
Num of Std Step Trials= 20
Max Error Tol= 0.3
Flow Tol Ratio= 0.001
Split Flow NTrial= 30
Split Flow Tol= 0.02
Split Flow Ratio= 0.02
Log Output Level= 0
Friction Slope Method= 1
Unsteady Friction Slope Method= 2
Unsteady Bridges Friction Slope Method= 1
Parabolic Critical Depth
Global Vel Dist=  1 , 1 , 1
Global Log Level= 0
CheckData=True
Encroach Param= -1, 0, 0, 0
BEGIN DESCRIPTION:
Multiple Run
END DESCRIPTION:

--- TRIB 4 TO PRICE CREEK.f01 (steady flow) ---

Flow Title=Multiple
Number of Profiles=7
Profile Names=10-year,25-year,50-year,1pct_min,100-year,1pct_plu,500-year
River Rch & RM= TRIB 4 TO PRICE ,Reach-1,6920
     690    1103    1473     953    1902    3795    3136
River Rch & RM= TRIB 4 TO PRICE ,Reach-1,6619
    1020    1660    2243    1466    2924    5835    4913
River Rch & RM= TRIB 4 TO PRICE ,Reach-1,4202
    1189    1947    2643    1733    3457    6898    5849
Boundary for River Rch & Prof#=TRIB 4 TO PRICE ,Reach-1,1
Up Type=0
Dn Type=3
Dn Slope=0.005
Boundary for River Rch & Prof#=TRIB 4 TO PRICE ,Reach-1,2
Up Type=0
Dn Type=3
Dn Slope=0.005
Boundary for River Rch & Prof#=TRIB 4 TO PRICE ,Reach-1,3
Up Type=0
Dn Type=3
Dn Slope=0.005
Boundary for River Rch & Prof#=TRIB 4 TO PRICE ,Reach-1,4
Up Type=0
Dn Type=3
Dn Slope=0.005
Boundary for River Rch & Prof#=TRIB 4 TO PRICE ,Reach-1,5
Up Type=0
Dn Type=3
Dn Slope=0.005
Boundary for River Rch & Prof#=TRIB 4 TO PRICE ,Reach-1,6
Up Type=0
Dn Type=3
Dn Slope=0.005
Boundary for River Rch & Prof#=TRIB 4 TO PRICE ,Reach-1,7
Up Type=0
Dn Type=3
Dn Slope=0.005

--- TRIB 4 TO PRICE CREEK.g01 (geometry) ---

Geom Title=Existing Conditions

River Reach=TRIB 4 TO PRICE ,Reach-1
Reach XY= 30
      2568775.00     13551672.68      2568719.31     13551576.93
      2568372.53     13551569.55      2568223.75     13551378.45
      2567980.93     13551372.76      2567823.44     13551278.76
      2567680.94     13551272.73      2567600.00     13551224.60
      2566880.94     13551377.27      2566345.05     13551575.60
      2566126.58     13551521.17      2565800.12     13551324.71
      2565535.50     13551326.22      2565254.97     13551424.93
      2564844.98     13551424.82      2564774.99     13551382.53
      2564625.01     13551467.47      2564564.56     13551426.38
      2564385.50     13551426.20      2564095.15     13551575.37
      2563926.47     13551571.45      2563827.42     13551480.54
      2563664.50     13551426.22      2563380.94     13551422.74
      2562959.79     13551225.51      2562740.22     13551225.52
      2562669.06     13551272.73      2562530.94     13551277.27
      2562379.68     13551329.74      2562375.00     13551375.00

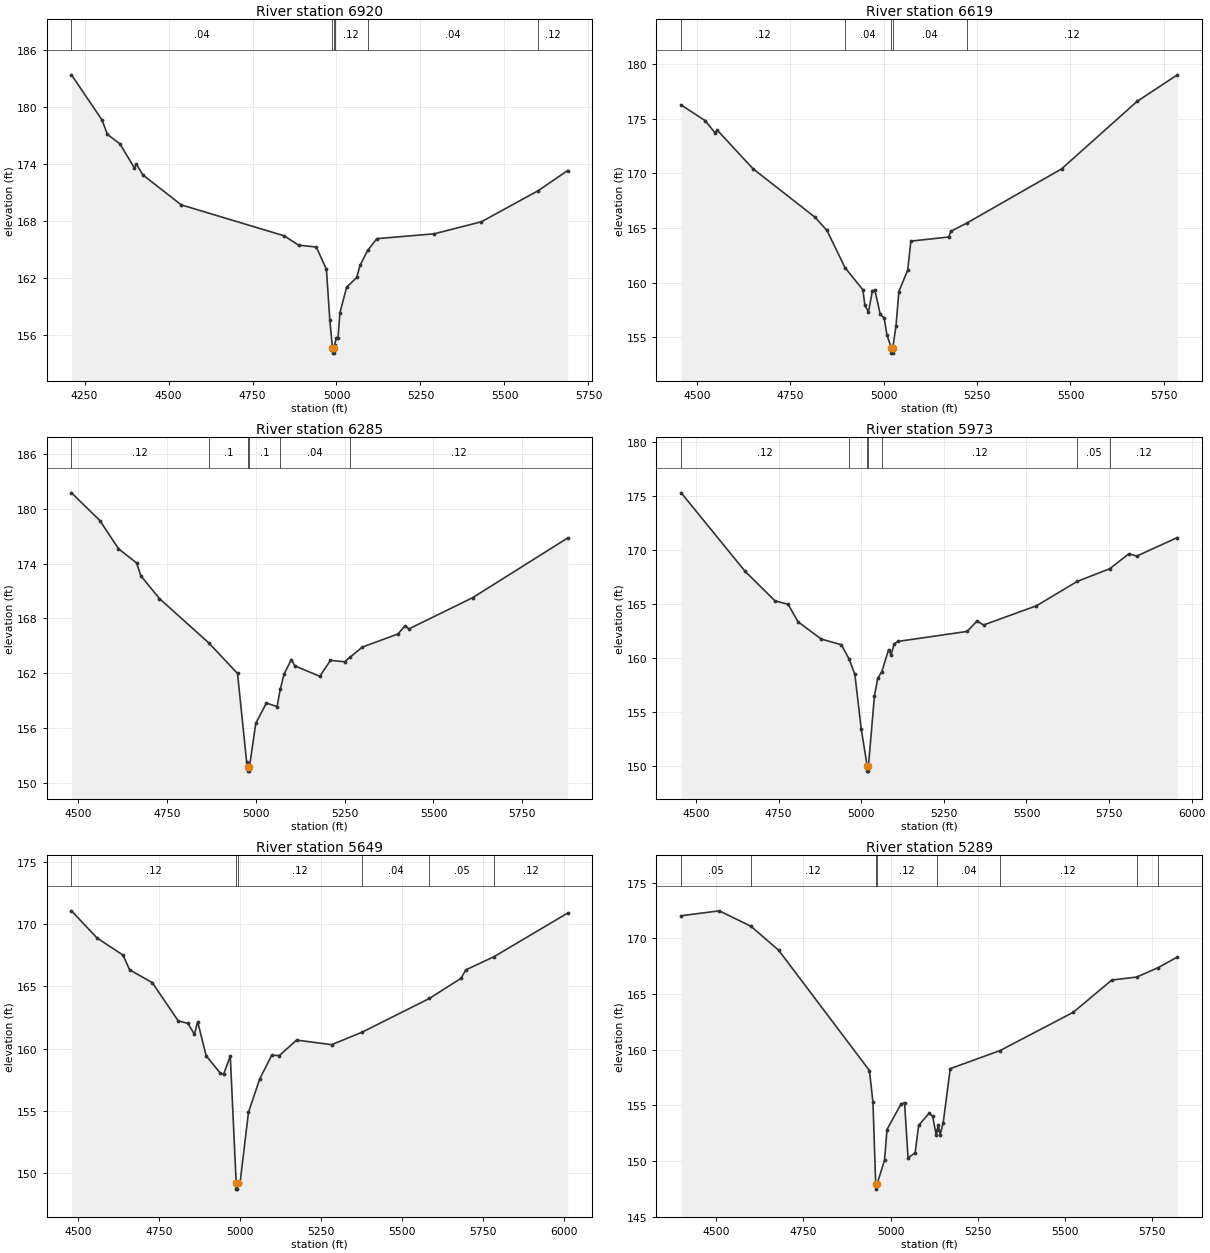
Type RM Length L Ch R = 1,6920,301,301,301
BEGIN DESCRIPTION:
LGII3061
END DESCRIPTION:
XS GIS Cut Line= 5
      2568974.32     13550879.44      2568867.21     13551066.12
      2568624.15     13551489.73      2568610.26     13551788.34
      2568658.84     13552260.30
#Sta/Elev= 30
  4211.1  183.42  4302.1  178.66  4317.9  177.15  4355.3  176.15  4398.4  173.61
  4404.2  174.02  4423.5  172.88  4537.9  169.72  4844.3  166.46  4887.4  165.47
  4940.0  165.28  4970.0  162.93  4980.1  157.62  4988.1  154.60  4988.3  154.10
  4991.8  154.10  4992.1  154.60  4994.2  154.92  4999.6  155.73  5004.6  155.68
  5010.1  158.33  5030.1  161.03  5060.1  162.07  5070.1  163.34  5092.7  164.92
  5120.2  166.16  5290.7  166.67  5431.4  167.94  5600.7  171.22  5688.1  173.34
#Mann=6,-1,0
  4211.1    0.04       0  4988.1    0.05       0  4992.1    0.04       0
  4994.2    0.12       0  5092.7    0.04       0  5600.7    0.12       0
Bank Sta=4988.1,4992.1
Exp/Cntr=0.3,0.1

Type RM Length L Ch R = 1,6619,334,334,334
BEGIN DESCRIPTION:
LGII3060
END DESCRIPTION:
XS GIS Cut Line= 3
      2568499.14     13551017.53      2568249.15     13551795.29
      2568179.71     13552302.21
#Sta/Elev= 30
  4457.6  176.26  4521.7  174.83  4548.5  173.70  4553.8  173.97  4650.1  170.42
  4815.8  165.99  4847.9  164.78  4896.2  161.38  4944.2  159.34  4949.4  157.95
  4959.1  157.32  4969.6  159.27  4976.3  159.30  4990.6  157.10  5001.1  156.78
  5008.4  155.24  5020.1  154.05  5020.4  153.55  5023.9  153.55  5024.1  154.05
  5032.7  156.00  5040.5  159.19  5064.2  161.16  5072.6  163.80  5174.1  164.18
  5179.7  164.70  5222.2  165.45  5476.1  170.41  5678.0  176.58  5786.2  179.02
#Mann=5,-1,0
  4457.6    0.12       0  4896.2    0.04       0  5020.1    0.04       0
  5024.1    0.04       0  5222.2    0.12       0
Bank Sta=5020.1,5024.1
Exp/Cntr=0.3,0.1

Type RM Length L Ch R = 1,6285,312,312,312
BEGIN DESCRIPTION:
LGII3059
END DESCRIPTION:
XS GIS Cut Line= 3
      2568235.25     13550878.65      2568089.43     13551350.84
      2568054.78     13552251.78
#Sta/Elev= 30
  4481.6  181.74  4561.5  178.71  4613.8  175.63  4664.9  174.07  4676.6  172.68
  4729.0  170.18  4867.9  165.33  4948.7  161.99  4974.4  152.31  4978.4  151.81
  4978.6  151.31  4982.1  151.31  4982.4  151.81  5000.0  156.53  5030.0  158.76
  5060.0  158.36  5068.9  160.25  5080.0  161.95  5100.0  163.51  5110.1  162.82
  5180.1  161.68  5210.1  163.42  5250.2  163.27  5265.9  163.79  5300.2  164.88
  5400.3  166.31  5420.3  167.22  5430.3  166.85  5610.4  170.28  5877.4  176.80
#Mann=6,-1,0
  4481.6    0.12       0  4867.9     0.1       0  4978.4    0.05       0
  4982.4     0.1       0  5068.9    0.04       0  5265.9    0.12       0
Bank Sta=4978.4,4982.4
Exp/Cntr=0.3,0.1

Type RM Length L Ch R = 1,5973,324,324,324
BEGIN DESCRIPTION:
LGII3058
END DESCRIPTION:
XS GIS Cut Line= 3
      2567860.26     13550732.77      2567797.76     13551378.62
      2567776.96     13552231.40
#Sta/Elev= 30
  4454.9  175.33  4648.0  168.06  4738.4  165.32  4778.6  164.98  4808.8  163.36
  4879.1  161.76  4939.4  161.24  4963.6  159.89  4980.6  158.49  4999.7  153.46
  5017.7  150.01  5018.0  149.51  5021.6  149.51  5021.8  150.01  5039.8  156.48
  5049.9  158.13  5062.3  158.74  5082.8  160.79  5090.1  160.29  5099.4  161.30
  5110.1  161.54  5320.2  162.47  5350.2  163.43  5370.2  163.07  5530.3  164.85
  5653.6  167.11  5752.1  168.29  5810.4  169.68  5833.8  169.46  5956.8  171.18
#Mann=7,-1,0
  4454.9    0.12       0  4963.6     0.1       0  5017.7    0.05       0
  5021.8     0.1       0  5062.3    0.12       0  5653.6    0.05       0
  5752.1    0.12       0
Bank Sta=5017.7,5021.8
Exp/Cntr=0.3,0.1

Type RM Length L Ch R = 1,5649,360,360,360
BEGIN DESCRIPTION:
LGII3057
END DESCRIPTION:
XS GIS Cut Line= 3
      2567471.37     13550725.86      2567492.21     13551142.51
      2567644.99     13552246.72
#Sta/Elev= 30
  4480.4  171.08  4559.6  168.89  4639.7  167.52  4659.8  166.34  4729.8  165.31
  4809.9  162.24  4840.0  162.03  4860.0  161.15  4870.0  162.17  4896.3  159.43
  4940.5  158.01  4950.0  157.94  4970.7  159.40  4988.9  149.21  4989.1  148.71
  4992.7  148.71  4993.0  149.21  5001.0  149.24  5026.8  154.88  5061.6  157.57
  5098.6  159.47  5122.2  159.45  5175.5  160.69  5283.7  160.32  5378.8  161.34
  5585.7  164.04  5683.3  165.66  5697.6  166.33  5785.5  167.40  6012.3  170.90
#Mann=6,-1,0
  4480.4    0.12       0  4988.9    0.05       0  4993.0    0.12       0
  5378.8    0.04       0  5585.7    0.05       0  5785.5    0.12       0
Bank Sta=4988.9,4993
Exp/Cntr=0.3,0.1

Type RM Length L Ch R = 1,5289,384,384,384
BEGIN DESCRIPTION:
LGII3056
END DESCRIPTION:
XS GIS Cut Line= 3
      2567179.71     13550725.80      2567158.87     13551218.90
      2567276.77     13552141.26
#Sta/Elev= 30
  4399.2  172.04  4508.5  172.48  4599.1  171.10  4678.6  168.95  4939.2  158.14
  4949.3  155.30  4957.2  147.99  4957.5  147.49  4961.6  147.99  4982.5  150.09
  4989.6  152.84  5029.9  155.14  5040.0  155.24  5050.1  150.28  5070.3  150.76
  5080.4  153.22  5110.6  154.31  5120.7  154.02  5130.8  152.32  5134.1  152.82
  5137.0  153.26  5142.1  152.37  5150.9  153.47  5171.1  158.31  5313.8  159.93
  5523.9  163.37  5634.8  166.27  5705.8  166.53  5766.8  167.37  5822.6  168.33
#Mann=8,-1,0
  4399.2    0.05       0  4599.1    0.12       0  4957.2    0.05       0
  4961.6    0.12       0  5134.1    0.04       0  5313.8    0.12       0
  5705.8    0.05       0  5766.8    0.12       0
Bank Sta=4957.2,4961.6
Exp/Cntr=0.3,0.1

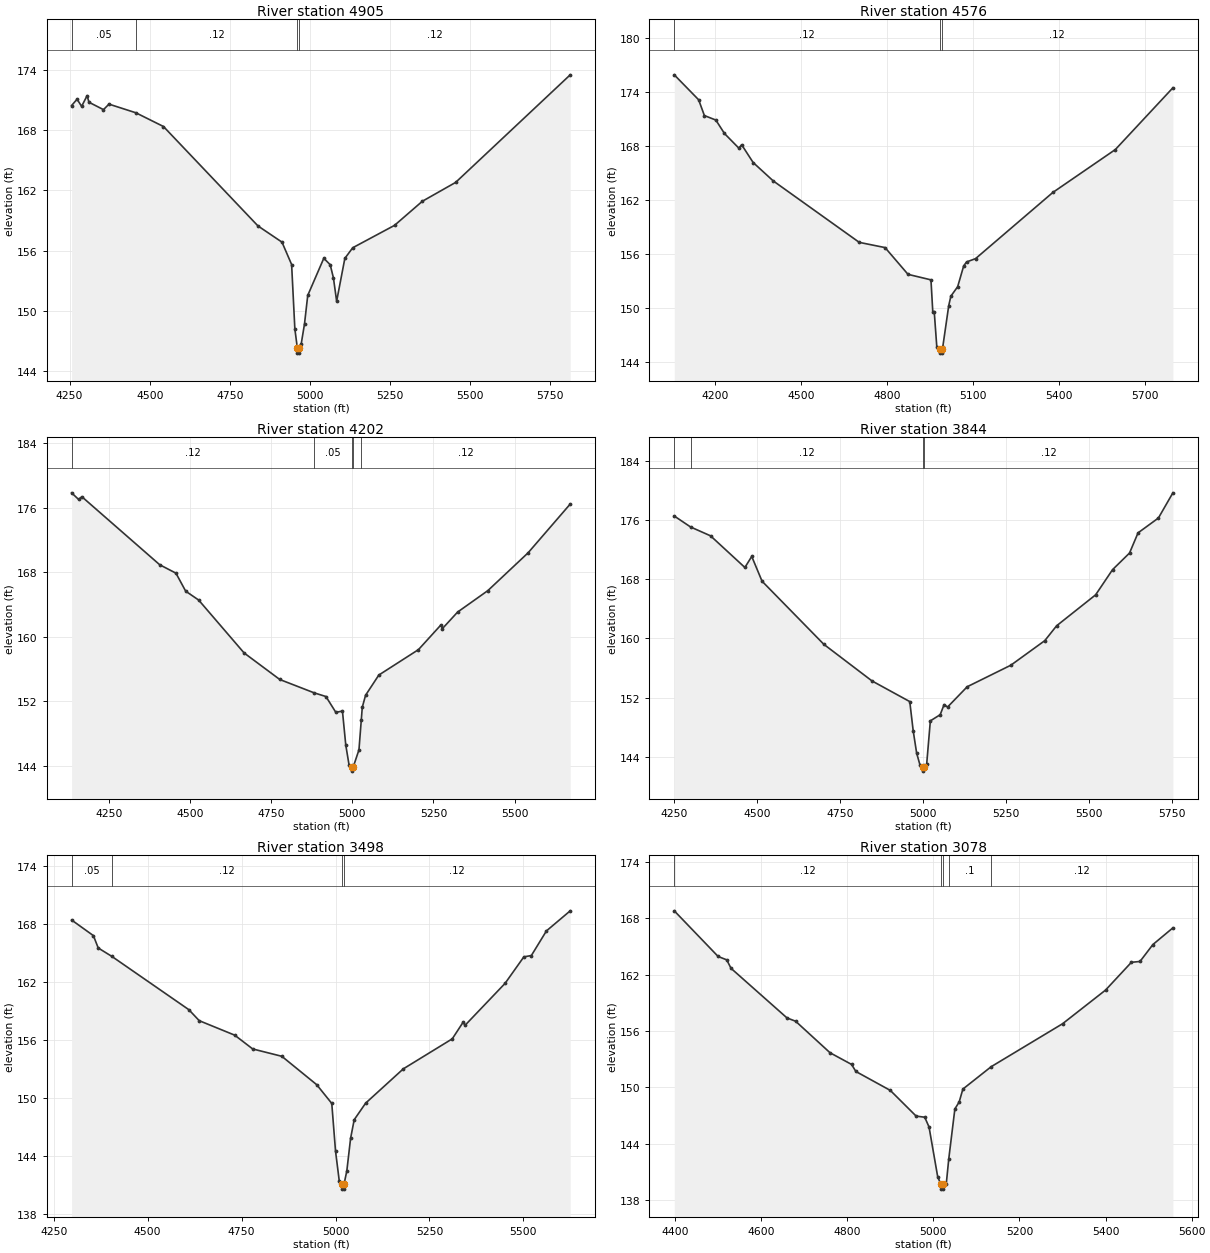
Type RM Length L Ch R = 1,4905,329,329,329
BEGIN DESCRIPTION:
LGII3055
END DESCRIPTION:
XS GIS Cut Line= 3
      2567082.50     13550739.69      2566811.65     13551309.18
      2566887.92     13552231.41
#Sta/Elev= 30
  4256.2  170.45  4273.2  171.08  4287.5  170.37  4304.7  171.44  4310.3  170.78
  4355.7  170.04  4372.8  170.59  4456.6  169.73  4542.9  168.36  4837.9  158.45
  4912.7  156.84  4942.8  154.61  4952.9  148.19  4960.7  146.28  4961.0  145.78
  4964.8  145.78  4965.1  146.28  4972.9  146.73  4983.0  148.69  4993.1  151.53
  5043.2  155.23  5063.2  154.59  5073.3  153.27  5083.3  150.95  5108.9  155.22
  5133.5  156.28  5263.9  158.51  5350.7  160.91  5454.6  162.79  5812.2  173.51
#Mann=4,-1,0
  4256.2    0.05       0  4456.6    0.12       0  4960.7    0.05       0
  4965.1    0.12       0
Bank Sta=4960.7,4965.1
Exp/Cntr=0.3,0.1

Type RM Length L Ch R = 1,4576,374,374,374
BEGIN DESCRIPTION:
LGII3054
END DESCRIPTION:
XS GIS Cut Line= 3
      2566506.09     13550580.01      2566513.04     13551482.79
      2566735.27     13552288.39
#Sta/Elev= 30
  4057.5  175.87  4142.5  173.10  4162.5  171.35  4202.5  170.85  4232.5  169.36
  4282.5  167.74  4292.5  168.11  4332.5  166.14  4402.5  164.10  4702.5  157.28
  4792.5  156.70  4872.5  153.73  4952.5  153.12  4958.9  149.55  4964.0  149.55
  4973.0  145.62  4985.1  145.49  4985.4  144.99  4989.6  144.99  4990.0  145.49
  4993.7  145.68  5014.5  150.27  5021.9  151.31  5045.6  152.36  5066.6  154.67
  5076.7  155.11  5107.8  155.47  5377.5  162.82  5595.4  167.58  5796.0  174.43
#Mann=3,-1,0
  4057.5    0.12       0  4985.1    0.05       0  4990.0    0.12       0
Bank Sta=4985.1,4990
Exp/Cntr=0.3,0.1

Type RM Length L Ch R = 1,4202,358,358,358
BEGIN DESCRIPTION:
LGII3053
END DESCRIPTION:
XS GIS Cut Line= 3
      2566221.37     13550663.38      2566221.37     13551323.07
      2566054.70     13552184.20
#Sta/Elev= 30
  4134.7  177.84  4156.3  177.02  4166.3  177.36  4406.3  168.93  4456.3  167.89
  4486.3  165.66  4526.3  164.56  4666.3  158.01  4776.3  154.72  4882.7  153.06
  4918.6  152.61  4949.1  150.65  4969.5  150.81  4979.7  146.61  4989.9  144.12
  4997.6  143.87  4998.0  143.37  5002.6  143.87  5020.4  146.01  5027.5  149.68
  5030.6  151.28  5040.8  152.77  5081.6  155.27  5203.8  158.42  5272.6  161.46
  5277.7  161.03  5324.4  163.07  5417.7  165.73  5541.7  170.41  5671.5  176.45
#Mann=5,-1,0
  4134.7    0.12       0  4882.7    0.05       0  4997.6    0.05       0
  5002.6    0.05       0  5027.5    0.12       0
Bank Sta=4997.6,5002.6
Exp/Cntr=0.3,0.1

Type RM Length L Ch R = 1,3844,346,346,346
BEGIN DESCRIPTION:
LGII3052
END DESCRIPTION:
XS GIS Cut Line= 3
      2566061.66     13550649.41      2565818.59     13551586.95
      2565714.42     13552107.80
#Sta/Elev= 30
  4251.7  176.51  4300.9  175.03  4360.8  173.84  4464.1  169.57  4484.7  171.06
  4515.7  167.72  4701.7  159.20  4846.3  154.27  4960.0  151.48  4970.3  147.55
  4980.7  144.53  4990.9  142.90  4998.8  142.60  4999.1  142.10  5003.8  142.60
  5010.9  143.06  5021.9  148.88  5051.5  149.71  5063.3  151.08  5073.6  150.74
  5132.7  153.48  5264.1  156.39  5366.1  159.70  5401.8  161.71  5519.0  165.88
  5570.0  169.28  5621.0  171.52  5646.6  174.24  5707.8  176.24  5751.4  179.64
#Mann=4,-1,0
  4251.7    0.05       0  4300.9    0.12       0  4998.8    0.05       0
  5003.8    0.12       0
Bank Sta=4998.8,5003.8
Exp/Cntr=0.3,0.1

Type RM Length L Ch R = 1,3498,420,420,420
BEGIN DESCRIPTION:
LGII3051
END DESCRIPTION:
XS GIS Cut Line= 3
      2565360.27     13550649.49      2565540.82     13551246.68
      2565589.43     13551948.11
#Sta/Elev= 30
  4297.6  168.43  4355.6  166.81  4368.5  165.53  4404.7  164.66  4609.6  159.14
  4637.3  158.00  4731.7  156.50  4779.6  155.07  4857.1  154.31  4949.9  151.37
  4990.0  149.43  5000.0  144.49  5010.0  141.38  5017.4  141.05  5017.8  140.55
  5022.2  140.55  5022.6  141.05  5030.1  142.45  5040.1  145.81  5049.7  147.74
  5080.2  149.46  5180.4  153.01  5310.7  156.12  5339.7  157.85  5344.7  157.52
  5451.1  161.86  5501.2  164.61  5521.2  164.75  5561.3  167.30  5624.6  169.38
#Mann=4,-1,0
  4297.6    0.05       0  4404.7    0.12       0  5017.4    0.05       0
  5022.6    0.12       0
Bank Sta=5017.4,5022.6
Exp/Cntr=0.3,0.1

Type RM Length L Ch R = 1,3078,392,392,392
BEGIN DESCRIPTION:
LGII3050
END DESCRIPTION:
XS GIS Cut Line= 2
      2565151.93     13550823.10      2565165.80     13551981.42
#Sta/Elev= 30
  4398.0  168.77  4499.9  163.92  4519.9  163.56  4529.9  162.66  4659.9  157.39
  4679.9  157.04  4759.9  153.69  4809.9  152.45  4819.9  151.70  4899.9  149.69
  4959.9  146.96  4979.9  146.84  4989.9  145.80  5009.9  140.54  5017.3  139.70
  5017.7  139.20  5022.2  139.20  5022.6  139.70  5029.9  139.75  5035.7  142.41
  5049.9  147.72  5059.9  148.46  5068.5  149.83  5134.3  152.21  5300.0  156.77
  5400.0  160.35  5460.0  163.30  5480.0  163.39  5510.0  165.19  5556.4  166.96
#Mann=5,-1,0
  4398.0    0.12       0  5017.3    0.05       0  5022.6    0.12       0
  5035.7     0.1       0  5134.3    0.12       0
Bank Sta=5017.3,5022.6
Exp/Cntr=0.3,0.1

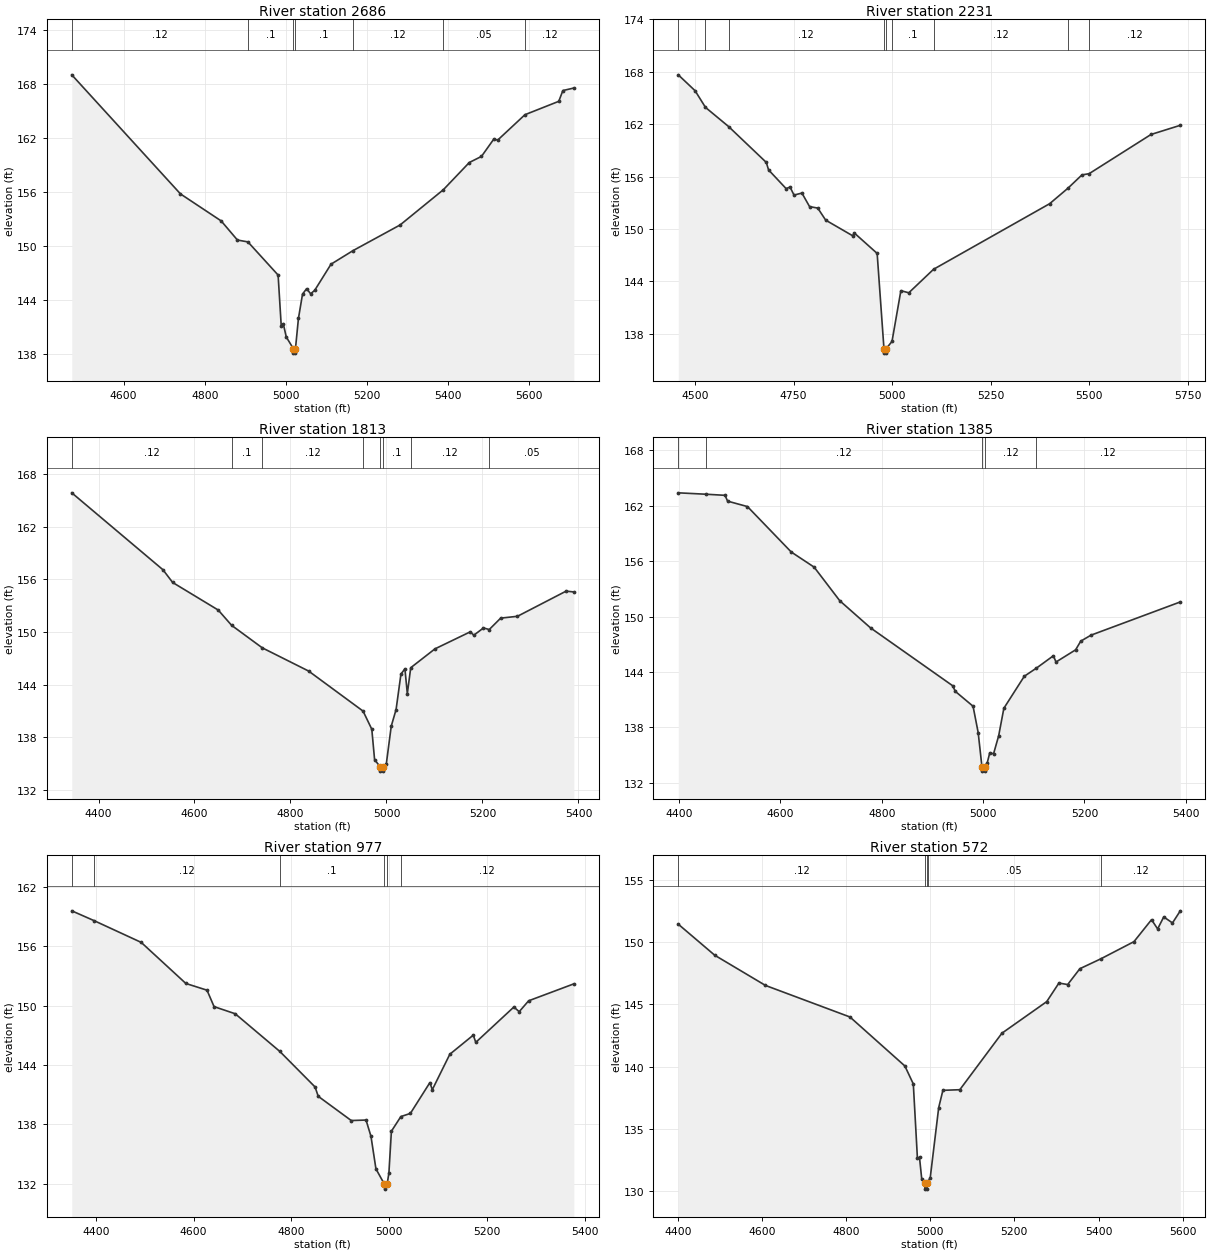
Type RM Length L Ch R = 1,2686,455,455,455
BEGIN DESCRIPTION:
LGII3049
END DESCRIPTION:
XS GIS Cut Line= 2
      2564742.20     13550857.74      2564832.34     13552091.96
#Sta/Elev= 30
  4472.3  169.04  4740.3  155.78  4840.5  152.78  4880.6  150.65  4906.5  150.44
  4980.9  146.75  4988.6  141.09  4993.6  141.34  5001.0  139.86  5018.4  138.56
  5018.8  138.06  5023.3  138.06  5023.7  138.56  5031.0  141.92  5041.1  144.63
  5051.1  145.23  5061.1  144.67  5071.1  145.05  5111.3  147.96  5165.5  149.47
  5281.7  152.33  5388.2  156.25  5452.2  159.28  5482.2  159.96  5512.3  161.87
  5522.3  161.78  5589.3  164.60  5672.7  166.09  5682.8  167.29  5709.8  167.57
#Mann=7,-1,0
  4472.3    0.12       0  4906.5     0.1       0  5018.4    0.05       0
  5023.7     0.1       0  5165.5    0.12       0  5388.2    0.05       0
  5589.3    0.12       0
Bank Sta=5018.4,5023.7
Exp/Cntr=0.3,0.1

Type RM Length L Ch R = 1,2231,418,418,418
BEGIN DESCRIPTION:
LGII3048
END DESCRIPTION:
XS GIS Cut Line= 3
      2564318.60     13550892.53      2564388.04     13551635.57
      2564637.82     13552100.44
#Sta/Elev= 30
  4457.2  167.65  4499.9  165.83  4526.3  163.92  4584.9  161.73  4680.6  157.62
  4686.4  156.76  4730.9  154.62  4740.9  154.80  4750.9  153.88  4771.0  154.11
  4790.4  152.56  4811.2  152.39  4831.3  151.01  4899.4  149.23  4904.4  149.52
  4961.9  147.20  4979.2  136.28  4979.7  135.78  4984.2  135.78  4984.6  136.28
  4999.6  137.12  5022.1  142.93  5042.2  142.69  5105.0  145.38  5399.6  152.89
  5445.9  154.66  5481.6  156.19  5499.8  156.33  5656.9  160.82  5731.2  161.87
#Mann=9,-1,0
  4457.2    0.12       0  4526.3     0.1       0  4584.9    0.12       0
  4979.2    0.05       0  4984.6    0.12       0  4999.6     0.1       0
  5105.0    0.12       0  5445.9    0.05       0  5499.8    0.12       0
Bank Sta=4979.2,4984.6
Exp/Cntr=0.3,0.1

Type RM Length L Ch R = 1,1813,428,428,428
BEGIN DESCRIPTION:
LGII3047
END DESCRIPTION:
XS GIS Cut Line= 2
      2564096.37     13550927.24      2563936.80     13551960.99
#Sta/Elev= 30
  4344.3  165.88  4534.3  157.10  4554.5  155.65  4649.5  152.50  4677.3  150.76
  4741.2  148.19  4837.8  145.54  4951.2  140.97  4969.4  138.90  4975.2  135.43
  4986.8  134.62  4987.3  134.12  4992.0  134.12  4992.4  134.62  4999.7  134.97
  5009.9  139.25  5020.0  141.15  5030.1  145.19  5038.4  145.80  5043.4  142.96
  5050.5  145.92  5100.9  148.07  5174.7  150.02  5181.9  149.63  5202.1  150.46
  5214.1  150.28  5237.9  151.58  5272.9  151.79  5374.2  154.66  5390.3  154.57
#Mann=8,-1,0
  4344.3    0.12       0  4677.3     0.1       0  4741.2    0.12       0
  4951.2     0.1       0  4986.8    0.05       0  4992.4     0.1       0
  5050.5    0.12       0  5214.1    0.05       0
Bank Sta=4986.8,4992.4
Exp/Cntr=0.3,0.1

Type RM Length L Ch R = 1,1385,408,408,408
BEGIN DESCRIPTION:
LGII3046
END DESCRIPTION:
XS GIS Cut Line= 2
      2563714.42     13550830.03      2563561.65     13551809.18
#Sta/Elev= 30
  4398.2  163.41  4452.3  163.26  4490.5  163.14  4495.6  162.51  4534.8  161.92
  4621.2  157.00  4666.4  155.36  4717.0  151.72  4777.7  148.78  4939.6  142.52
  4945.3  141.89  4980.1  140.29  4990.2  137.44  4997.6  133.76  4998.0  133.26
  5002.7  133.26  5003.2  133.76  5008.1  134.16  5013.1  135.25  5020.6  135.14
  5030.7  137.10  5040.9  140.07  5081.3  143.54  5105.2  144.42  5138.7  145.76
  5143.8  145.08  5182.5  146.40  5192.7  147.34  5212.9  147.99  5389.2  151.59
#Mann=5,-1,0
  4398.2    0.05       0  4452.3    0.12       0  4997.6    0.05       0
  5003.2    0.12       0  5105.2    0.12       0
Bank Sta=4997.6,5003.2
Exp/Cntr=0.3,0.1

Type RM Length L Ch R = 1,977,405,405,405
BEGIN DESCRIPTION:
LGII3045
END DESCRIPTION:
XS GIS Cut Line= 3
      2563582.48     13550843.90      2563242.21     13551267.51
      2563186.65     13551746.65
#Sta/Elev= 30
  4351.1  159.58  4396.6  158.59  4493.0  156.39  4584.2  152.24  4627.4  151.56
  4641.8  149.90  4685.0  149.18  4776.0  145.38  4848.2  141.78  4854.6  140.84
  4922.1  138.39  4952.3  138.44  4962.4  136.79  4972.5  133.51  4989.8  131.96
  4990.2  131.46  4995.4  131.96  4999.0  133.09  5004.1  137.31  5023.4  138.79
  5042.9  139.11  5082.7  142.22  5087.7  141.51  5123.5  145.09  5171.4  147.02
  5176.5  146.29  5254.3  149.86  5265.2  149.39  5284.5  150.49  5376.8  152.20
#Mann=6,-1,0
  4351.1    0.05       0  4396.6    0.12       0  4776.0     0.1       0
  4989.8    0.05       0  4995.4     0.1       0  5023.4    0.12       0
Bank Sta=4989.8,4995.4
Exp/Cntr=0.3,0.1

Type RM Length L Ch R = 1,572,312,312,312
BEGIN DESCRIPTION:
LGII3044
END DESCRIPTION:
XS GIS Cut Line= 3
      2562818.59     13550628.62      2562888.04     13551399.45
      2563143.93     13551731.42
#Sta/Elev= 30
  4401.3  151.42  4488.0  148.93  4608.5  146.51  4809.3  143.98  4939.9  140.05
  4959.9  138.61  4969.6  132.69  4974.6  132.72  4980.0  130.96  4987.2  130.68
  4987.6  130.18  4992.5  130.18  4993.0  130.68  4994.3  130.76  5000.1  131.09
  5020.2  136.71  5030.2  138.10  5070.4  138.15  5170.5  142.68  5276.9  145.21
  5305.9  146.70  5326.7  146.58  5355.7  147.85  5405.4  148.64  5484.3  150.02
  5526.0  151.78  5540.5  151.04  5555.0  152.00  5575.8  151.52  5594.4  152.49
#Mann=5,-1,0
  4401.3    0.12       0  4987.2    0.05       0  4993.0    0.12       0
  4994.3    0.05       0  5405.4    0.12       0
Bank Sta=4987.2,4993
Exp/Cntr=0.3,0.1

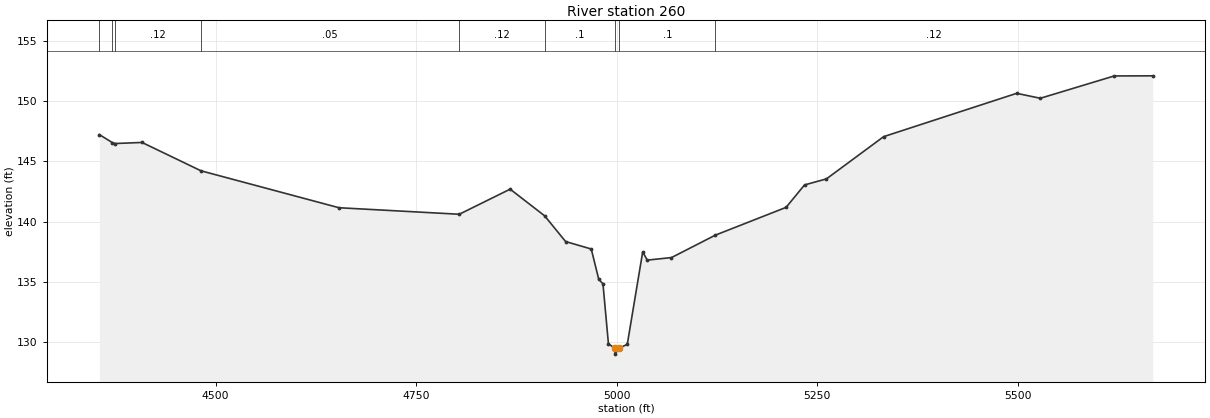
Type RM Length L Ch R = 1,260,0,0,0
BEGIN DESCRIPTION:
LGII3043
END DESCRIPTION:
XS GIS Cut Line= 4
      2562693.60     13550684.16      2562506.09     13551086.95
      2562631.09     13551420.29      2563047.74     13551718.89
#Sta/Elev= 30
  4355.2  147.21  4371.6  146.54  4374.6  146.47  4408.4  146.56  4481.9  144.21
  4653.9  141.15  4803.8  140.61  4867.2  142.69  4910.2  140.48  4936.3  138.35
  4968.3  137.73  4977.6  135.23  4982.9  134.84  4989.7  129.88  4997.4  129.52
  4997.9  129.02  5003.2  129.52  5013.2  129.83  5032.4  137.49  5038.1  136.81
  5068.3  137.02  5123.0  138.88  5211.1  141.18  5234.1  143.04  5261.4  143.54
  5332.7  147.04  5498.5  150.63  5528.0  150.22  5620.1  152.07  5668.1  152.08
#Mann=9,-1,0
  4355.2    0.12       0  4371.6    0.05       0  4374.6    0.12       0
  4481.9    0.05       0  4803.8    0.12       0  4910.2     0.1       0
  4997.4    0.05       0  5003.2     0.1       0  5123.0    0.12       0
Bank Sta=4997.4,5003.2
Exp/Cntr=0.3,0.1

Chan Stop Cuts=-1