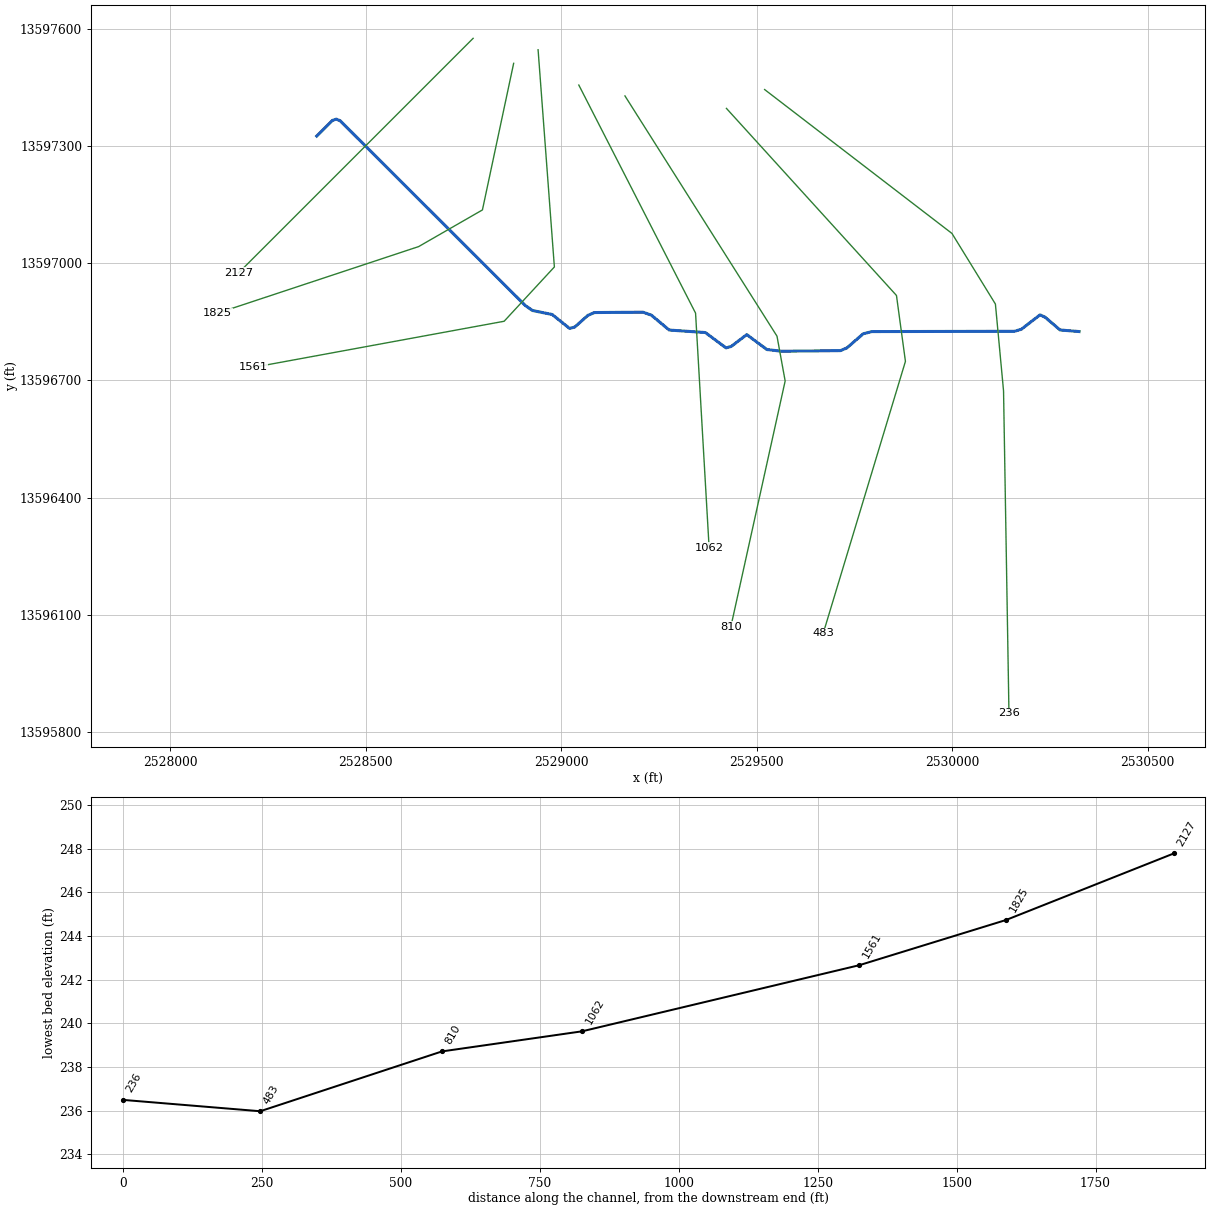
--- TRIB 4 TO SANDY FORK.prj (project) ---

Proj Title=TRIB 4 TO SANDY FORK Base Level Engineering
Current Plan=p01
Default Exp/Contr=0.3,0.1
English Units
Geom File=g01
Flow File=f01
Plan File=p01
BEGIN DESCRIPTION:
TRIB 4 TO SANDY FORK
END DESCRIPTION:

--- TRIB 4 TO SANDY FORK.p01 (plan) ---

Plan Title=Multiple Run
Short Identifier=Multiple
Geom File=g01
Flow File=f01
Subcritical Flow
K Sum by GR= 0
Std Step Tol= 0.01
Critical Tol= 0.01
Num of Std Step Trials= 20
Max Error Tol= 0.3
Flow Tol Ratio= 0.001
Split Flow NTrial= 30
Split Flow Tol= 0.02
Split Flow Ratio= 0.02
Log Output Level= 0
Friction Slope Method= 1
Unsteady Friction Slope Method= 2
Unsteady Bridges Friction Slope Method= 1
Parabolic Critical Depth
Global Vel Dist=  1 , 1 , 1
Global Log Level= 0
CheckData=True
Encroach Param= -1, 0, 0, 0
BEGIN DESCRIPTION:
Multiple Run
END DESCRIPTION:

--- TRIB 4 TO SANDY FORK.f01 (steady flow) ---

Flow Title=Multiple
Number of Profiles=7
Profile Names=10-year,25-year,50-year,1pct_min,100-year,1pct_plu,500-year
River Rch & RM= TRIB 4 TO SANDY ,Reach-1,2127
     472     750     997     644    1285    2563    2109
Boundary for River Rch & Prof#=TRIB 4 TO SANDY ,Reach-1,1
Up Type=0
Dn Type=3
Dn Slope=0.005
Boundary for River Rch & Prof#=TRIB 4 TO SANDY ,Reach-1,2
Up Type=0
Dn Type=3
Dn Slope=0.005
Boundary for River Rch & Prof#=TRIB 4 TO SANDY ,Reach-1,3
Up Type=0
Dn Type=3
Dn Slope=0.005
Boundary for River Rch & Prof#=TRIB 4 TO SANDY ,Reach-1,4
Up Type=0
Dn Type=3
Dn Slope=0.005
Boundary for River Rch & Prof#=TRIB 4 TO SANDY ,Reach-1,5
Up Type=0
Dn Type=3
Dn Slope=0.005
Boundary for River Rch & Prof#=TRIB 4 TO SANDY ,Reach-1,6
Up Type=0
Dn Type=3
Dn Slope=0.005
Boundary for River Rch & Prof#=TRIB 4 TO SANDY ,Reach-1,7
Up Type=0
Dn Type=3
Dn Slope=0.005

--- TRIB 4 TO SANDY FORK.g01 (geometry) ---

Geom Title=Existing Conditions

River Reach=TRIB 4 TO SANDY ,Reach-1
Reach XY= 30
      2528375.00     13597325.00      2528415.00     13597364.90
      2528425.00     13597368.43      2528435.00     13597364.11
      2528908.33     13596891.63      2528926.65     13596878.91
      2528977.28     13596868.59      2529021.68     13596833.04
      2529034.90     13596836.46      2529068.82     13596866.55
      2529085.44     13596873.63      2529209.78     13596874.49
      2529231.06     13596866.87      2529276.60     13596828.85
      2529369.11     13596822.46      2529421.78     13596783.28
      2529435.05     13596786.83      2529474.90     13596817.21
      2529526.46     13596779.00      2529564.79     13596774.59
      2529714.49     13596776.22      2529731.06     13596783.14
      2529772.67     13596819.25      2529795.03     13596824.93
      2530159.84     13596825.65      2530177.45     13596831.00
      2530225.04     13596867.69      2530238.28     13596861.52
      2530276.36     13596829.00      2530325.00     13596825.00

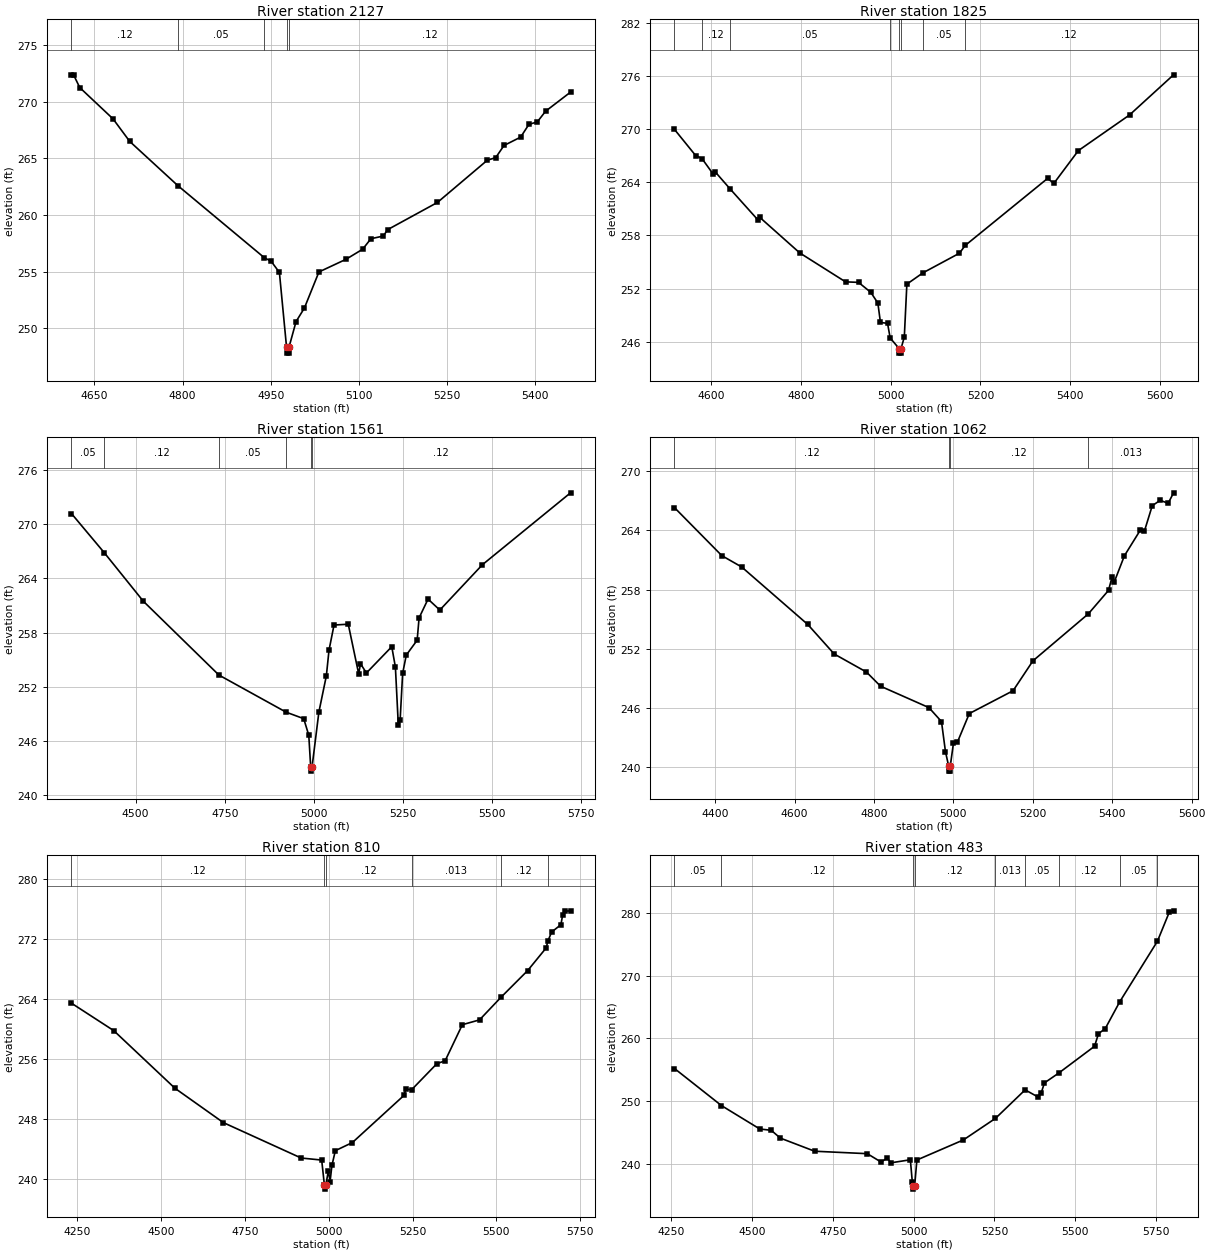
Type RM Length L Ch R = 1,2127,302,302,302
BEGIN DESCRIPTION:
TRIB 4 TO SANDY FORK 4.0
END DESCRIPTION:
XS GIS Cut Line= 3
      2528774.99     13597574.99      2528475.00     13597275.00
      2528175.01     13596975.01
#Sta/Elev= 30
  4611.2  272.40  4614.7  272.40  4625.3  271.27  4681.9  268.50  4710.2  266.51
  4792.2  262.59  4939.1  256.22  4950.6  255.91  4964.7  254.92  4976.9  248.28
  4977.1  247.78  4980.6  247.78  4980.9  248.28  4993.0  250.57  5007.2  251.77
  5031.9  254.96  5077.9  256.08  5106.2  256.97  5120.3  257.90  5141.5  258.14
  5148.6  258.70  5233.4  261.11  5318.3  264.85  5332.4  265.07  5346.6  266.15
  5374.9  266.89  5389.0  268.02  5403.1  268.23  5417.3  269.18  5459.7  270.87
#Mann=5,-1,0
  4611.2    0.12       0  4792.2    0.05       0  4939.1    0.12       0
  4976.9    0.05       0  4980.9    0.12       0
Bank Sta=4976.9,4980.9
Exp/Cntr=0.3,0.1

Type RM Length L Ch R = 1,1825,264,264,264
BEGIN DESCRIPTION:
Mapping XS 0eb41199
END DESCRIPTION:
XS GIS Cut Line= 4
      2528878.68     13597511.05      2528798.82     13597136.07
      2528635.63     13597042.32      2528121.76     13596872.19
#Sta/Elev= 30
  4517.8  269.96  4564.9  267.02  4579.0  266.68  4604.1  264.92  4609.2  265.14
  4641.3  263.28  4703.2  259.79  4708.3  260.03  4797.2  256.03  4899.2  252.77
  4928.2  252.71  4955.5  251.59  4971.3  250.38  4977.1  248.19  4992.9  248.09
  4998.8  246.44  5018.9  245.23  5019.2  244.73  5022.7  244.73  5022.9  245.23
  5030.3  246.54  5036.0  252.51  5072.0  253.79  5153.3  256.00  5166.0  256.87
  5349.7  264.43  5363.9  263.88  5418.4  267.57  5532.5  271.59  5630.7  276.12
#Mann=8,-1,0
  4517.8    0.05       0  4579.0    0.12       0  4641.3    0.05       0
  4998.8    0.12       0  5018.9    0.05       0  5022.9    0.12       0
  5072.0    0.05       0  5166.0    0.12       0
Bank Sta=5018.9,5022.9
Exp/Cntr=0.3,0.1

Type RM Length L Ch R = 1,1561,499,499,499
BEGIN DESCRIPTION:
Mapping XS 4406a67c
END DESCRIPTION:
XS GIS Cut Line= 4
      2528941.19     13597545.75      2528982.85     13596990.24
      2528854.38     13596851.35      2528212.00     13596733.29
#Sta/Elev= 30
  4320.1  271.18  4412.6  266.82  4521.4  261.48  4733.5  253.30  4921.9  249.19
  4971.3  248.47  4985.5  246.63  4990.8  243.16  4991.1  242.66  4994.8  243.16
  5013.8  249.20  5034.8  253.22  5042.2  256.05  5056.3  258.84  5096.2  258.93
  5125.4  253.44  5130.5  254.56  5147.1  253.53  5218.2  256.44  5228.4  254.18
  5236.6  247.74  5241.7  248.35  5248.7  253.48  5258.9  255.51  5289.4  257.16
  5294.8  259.63  5319.9  261.71  5353.0  260.50  5472.4  265.52  5719.5  273.48
#Mann=6,-1,0
  4320.1    0.05       0  4412.6    0.12       0  4733.5    0.05       0
  4921.9    0.12       0  4990.8    0.05       0  4994.8    0.12       0
Bank Sta=4990.8,4994.8
Exp/Cntr=0.3,0.1

Type RM Length L Ch R = 1,1062,252,252,252
BEGIN DESCRIPTION:
Mapping XS ef379640
END DESCRIPTION:
XS GIS Cut Line= 3
      2529045.35     13597455.51      2529343.96     13596872.18
      2529378.68     13596271.50
#Sta/Elev= 30
  4297.4  266.31  4416.6  261.45  4466.7  260.30  4633.1  254.48  4699.7  251.49
  4781.0  249.66  4816.4  248.23  4938.3  246.06  4969.9  244.65  4979.9  241.61
  4988.0  240.13  4988.2  239.63  4991.7  239.63  4992.0  240.13  5000.0  242.45
  5010.0  242.56  5040.0  245.46  5150.2  247.77  5200.3  250.80  5339.9  255.56
  5390.6  257.93  5399.8  259.32  5404.8  258.75  5430.7  261.44  5470.8  264.04
  5480.8  263.90  5500.8  266.51  5520.8  267.05  5540.9  266.75  5554.4  267.81
#Mann=4,-1,0
  4297.4    0.12       0  4988.0    0.05       0  4992.0    0.12       0
  5339.9   0.013       0
Bank Sta=4988,4992
Exp/Cntr=0.3,0.1

Type RM Length L Ch R = 1,810,327,327,327
BEGIN DESCRIPTION:
Mapping XS ff026192
END DESCRIPTION:
XS GIS Cut Line= 4
      2529163.41     13597427.72      2529552.29     13596813.15
      2529573.13     13596698.57      2529434.23     13596070.07
#Sta/Elev= 30
  4233.6  263.46  4359.6  259.81  4541.9  252.14  4686.5  247.56  4918.2  242.85
  4979.3  242.58  4987.5  239.21  4987.7  238.71  4991.5  239.21  4999.3  241.17
  5004.3  239.72  5009.8  241.86  5020.0  243.83  5070.8  244.91  5224.4  251.18
  5230.2  252.02  5247.3  251.94  5322.6  255.41  5347.3  255.80  5398.5  260.60
  5449.7  261.24  5513.7  264.25  5593.1  267.80  5648.7  270.84  5653.0  271.68
  5664.7  272.94  5692.3  273.91  5697.4  275.19  5705.7  275.72  5721.0  275.76
#Mann=6,-1,0
  4233.6    0.12       0  4987.5    0.05       0  4991.5    0.12       0
  5247.3   0.013       0  5513.7    0.12       0  5653.0    0.05       0
Bank Sta=4987.5,4991.5
Exp/Cntr=0.3,0.1

Type RM Length L Ch R = 1,483,247,247,247
BEGIN DESCRIPTION:
TRIB 4 TO SANDY FORK 1.0
END DESCRIPTION:
XS GIS Cut Line= 4
      2529422.91     13597395.84      2529857.85     13596917.32
      2529880.77     13596748.69      2529670.35     13596052.74
#Sta/Elev= 30
  4260.3  255.19  4405.7  249.28  4524.3  245.55  4559.4  245.35  4587.8  244.10
  4693.9  242.01  4856.7  241.62  4899.3  240.29  4918.6  240.92  4929.5  240.16
  4990.0  240.65  4996.1  237.07  4999.2  236.47  4999.4  235.97  5003.2  236.47
  5010.2  240.61  5154.1  243.81  5253.4  247.25  5345.1  251.79  5384.0  250.68
  5395.2  251.36  5404.8  252.90  5448.9  254.46  5559.9  258.74  5572.0  260.74
  5592.9  261.55  5637.7  265.82  5754.4  275.48  5791.4  280.15  5804.2  280.32
#Mann=9,-1,0
  4260.3    0.05       0  4405.7    0.12       0  4999.2    0.05       0
  5003.2    0.12       0  5253.4   0.013       0  5345.1    0.05       0
  5448.9    0.12       0  5637.7    0.05       0  5754.4    0.12       0
Bank Sta=4999.2,5003.2
Exp/Cntr=0.3,0.1

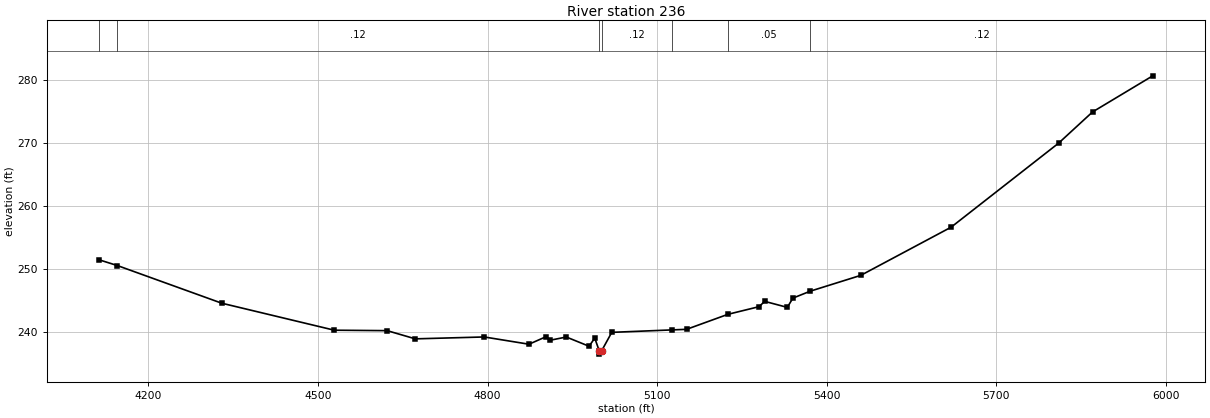
Type RM Length L Ch R = 1,236,0,0,0
BEGIN DESCRIPTION:
LGII3945
END DESCRIPTION:
XS GIS Cut Line= 5
      2529520.62     13597443.99      2529999.79     13597075.94
      2530110.90     13596895.38      2530131.73     13596673.16
      2530145.60     13595848.38
#Sta/Elev= 30
  4112.8  251.43  4144.8  250.53  4329.6  244.56  4528.9  240.28  4622.3  240.21
  4672.2  238.91  4794.1  239.21  4873.3  238.06  4904.2  239.28  4910.0  238.68
  4939.4  239.20  4979.6  237.74  4989.7  239.03  4997.7  236.99  4998.0  236.49
  5001.7  236.99  5019.8  239.94  5126.8  240.33  5152.2  240.42  5225.4  242.80
  5280.4  244.01  5290.4  244.85  5330.4  243.90  5340.4  245.37  5371.2  246.47
  5460.4  248.97  5620.4  256.61  5810.5  269.92  5870.5  274.86  5977.1  280.59
#Mann=7,-1,0
  4112.8    0.05       0  4144.8    0.12       0  4997.7    0.05       0
  5001.7    0.12       0  5126.8   0.013       0  5225.4    0.05       0
  5371.2    0.12       0
Bank Sta=4997.7,5001.7
Exp/Cntr=0.3,0.1

Chan Stop Cuts=-1