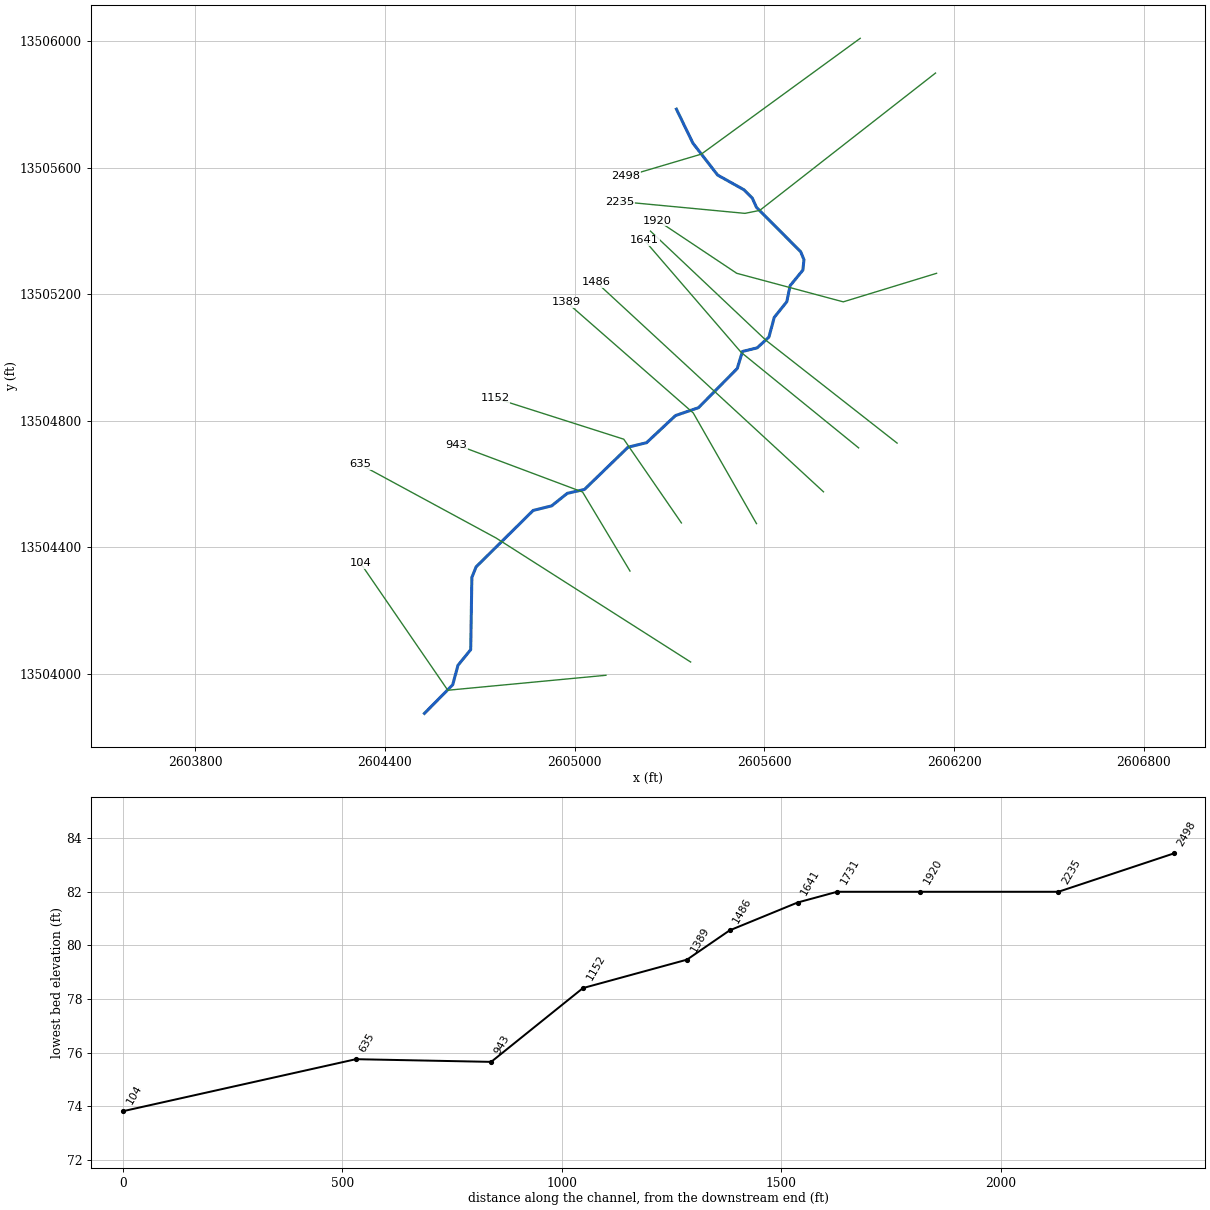
--- TRIB 4 TO SPRING CREEK.prj (project) ---

Proj Title=TRIB 4 TO SPRING CREEK Base Level Engineering
Current Plan=p01
Default Exp/Contr=0.3,0.1
English Units
Geom File=g01
Flow File=f01
Plan File=p01
Y Axis Title=Elevation
X Axis Title(PF)=Main Channel Distance
X Axis Title(XS)=Station
BEGIN DESCRIPTION:
TRIB 4 TO SPRING CREEK
END DESCRIPTION:
DSS Export Rating Curves= 0
DSS Export Rating Curve Sorted= 0
DSS Export Volume Flow Curves= 0
DXF OffsetX= 0
DXF OffsetY= 0
DXF ScaleX= 1
DXF ScaleY= 10

--- TRIB 4 TO SPRING CREEK.p01 (plan) ---

Plan Title=Multiple Run
Short Identifier=Multiple
Geom File=g01
Flow File=f01
Subcritical Flow
K Sum by GR= 0
Std Step Tol= 0.01
Critical Tol= 0.01
Num of Std Step Trials= 20
Max Error Tol= 0.3
Flow Tol Ratio= 0.001
Split Flow NTrial= 30
Split Flow Tol= 0.02
Split Flow Ratio= 0.02
Log Output Level= 0
Friction Slope Method= 1
Unsteady Friction Slope Method= 2
Unsteady Bridges Friction Slope Method= 1
Parabolic Critical Depth
Global Vel Dist=  1 , 1 , 1
Global Log Level= 0
CheckData=True
Encroach Param= -1, 0, 0, 0
BEGIN DESCRIPTION:
Multiple Run
END DESCRIPTION:

--- TRIB 4 TO SPRING CREEK.f01 (steady flow) ---

Flow Title=Multiple
Number of Profiles=7
Profile Names=10-year,25-year,50-year,1pct_min,100-year,1pct_plu,500-year
River Rch & RM= TRIB 4 TO SPRING,Reach-1,2498
     638     993    1301     825    1646    3285    2600
River Rch & RM= TRIB 4 TO SPRING,Reach-1,2235
     889    1412    1875    1204    2402    4793    3893
Boundary for River Rch & Prof#=TRIB 4 TO SPRING,Reach-1,1
Up Type=0
Dn Type=3
Dn Slope=0.005
Boundary for River Rch & Prof#=TRIB 4 TO SPRING,Reach-1,2
Up Type=0
Dn Type=3
Dn Slope=0.005
Boundary for River Rch & Prof#=TRIB 4 TO SPRING,Reach-1,3
Up Type=0
Dn Type=3
Dn Slope=0.005
Boundary for River Rch & Prof#=TRIB 4 TO SPRING,Reach-1,4
Up Type=0
Dn Type=3
Dn Slope=0.005
Boundary for River Rch & Prof#=TRIB 4 TO SPRING,Reach-1,5
Up Type=0
Dn Type=3
Dn Slope=0.005
Boundary for River Rch & Prof#=TRIB 4 TO SPRING,Reach-1,6
Up Type=0
Dn Type=3
Dn Slope=0.005
Boundary for River Rch & Prof#=TRIB 4 TO SPRING,Reach-1,7
Up Type=0
Dn Type=3
Dn Slope=0.005

--- TRIB 4 TO SPRING CREEK.g01 (geometry) ---

Geom Title=Existing Conditions
Program Version=4.10

River Reach=TRIB 4 TO SPRING,Reach-1
Reach XY= 30
      2605321.81     13505785.59      2605373.89     13505678.17
      2605452.02     13505577.26      2605535.57      13505530.6
      2605561.61     13505504.56        2605575.       13505475.
      2605714.82     13505334.69      2605725.06     13505309.66
      2605721.69     13505276.74      2605681.16      13505227.2
      2605670.85     13505176.72      2605631.11     13505127.16
      2605614.31     13505065.02      2605577.21     13505030.89
      2605530.65     13505019.37      2605514.11     13504965.58
      2605391.67     13504841.65      2605318.96     13504816.82
      2605227.28     13504730.87      2605168.95     13504716.84
      2605031.06     13504583.14      2604976.74     13504570.81
      2604927.19      13504531.1      2604868.94     13504516.86
      2604688.37     13504338.32      2604674.96     13504305.02
      2604671.25     13504076.55      2604631.13     13504027.17
       2604614.3     13503965.29        2604525.       13503875.

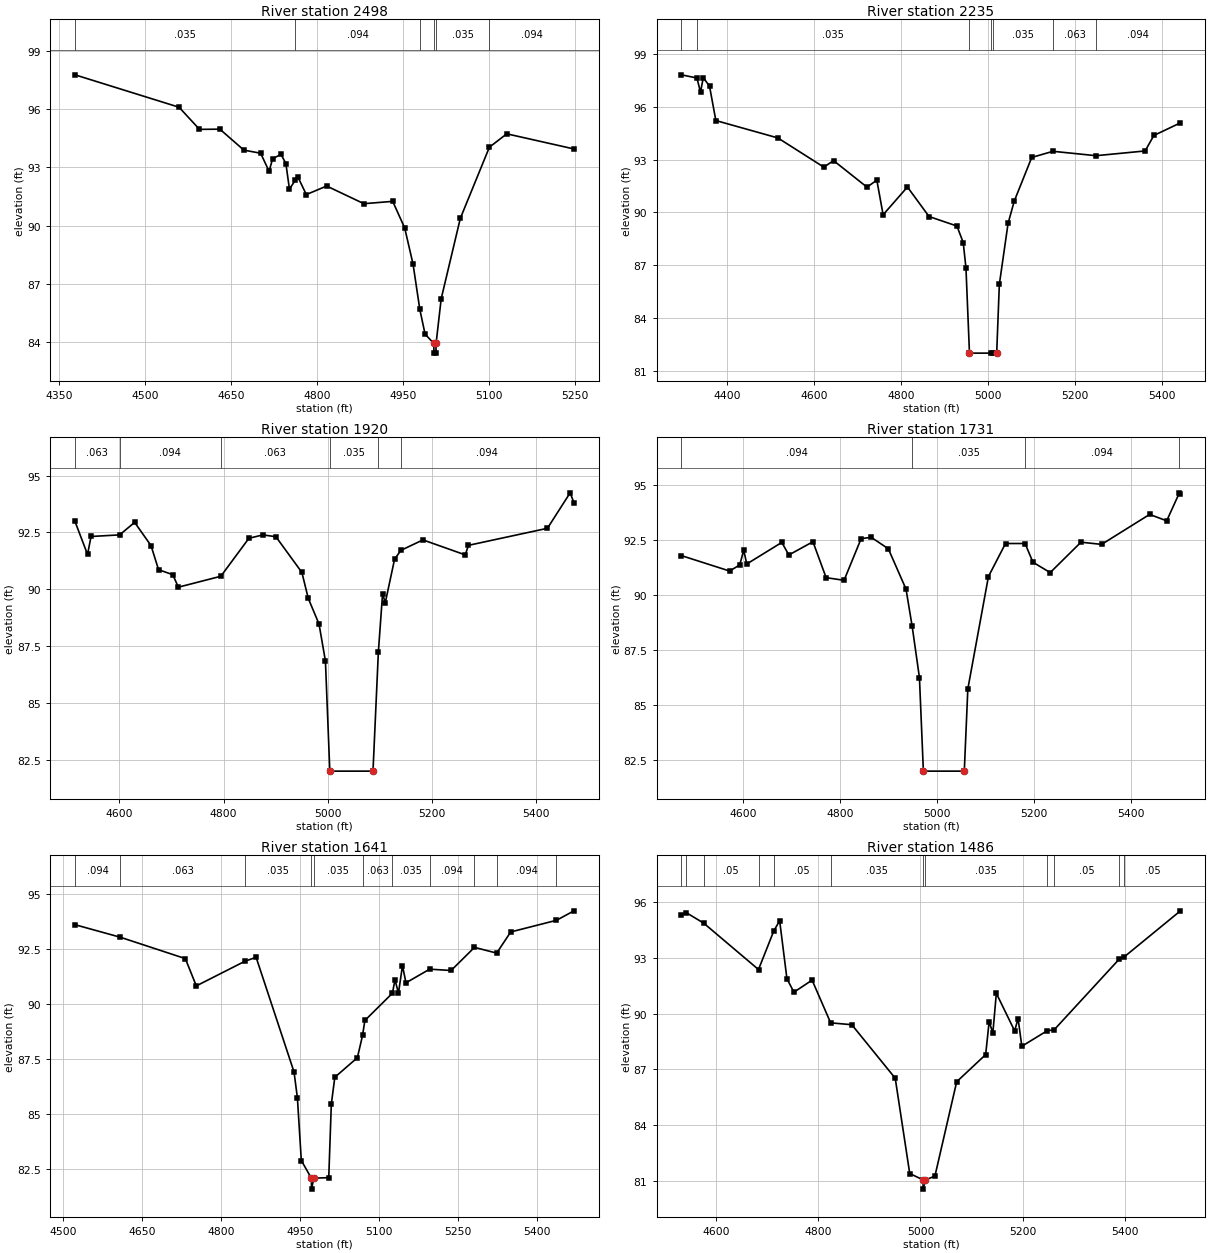
Type RM Length L Ch R = 1 ,2498    ,263,263,263
BEGIN DESCRIPTION:
TRIB 4 TO SPRING CREEK 4.0
END DESCRIPTION:
XS GIS Cut Line= 3
       2605902.9     13506009.58      2605400.49     13505643.38
      2605162.62     13505572.88
#Sta/Elev= 30
  4378.3   97.77  4559.7    96.1  4595.3   94.96  4630.8   94.97  4672.7   93.89
  4701.9   93.73  4716.6    92.8  4722.8   93.45  4737.4   93.67  4745.9    93.2
  4752.1   91.88  4762.5   92.35  4766.8   92.51  4781.5    91.6    4817   92.04
  4881.9   91.13  4932.1   91.25    4953   89.88  4967.6   88.01  4979.3   85.69
  4988.5   84.41  5003.7   83.93    5004   83.43  5007.5   83.43  5007.7   83.93
  5016.6   86.23  5049.9   90.37  5100.6   94.04  5130.9   94.73  5248.1   93.95
#Mann= 6 ,-1 , 0
  4378.3    .035       0  4762.5    .094       0  4979.3    .035       0
  5003.7    .035       0  5007.7    .035       0  5100.6    .094       0
Bank Sta=5003.7,5007.7
XS Rating Curve= 0 ,0
Exp/Cntr=0.3,0.1

Type RM Length L Ch R = 1 ,2235    ,315,315,315
BEGIN DESCRIPTION:
Mapping XS 68eb4592
END DESCRIPTION:
XS GIS Cut Line= 4
      2606141.07     13505899.82      2605585.28     13505465.46
      2605538.58     13505456.12      2605143.95     13505493.48
#Sta/Elev= 30
    4294   97.83  4329.6   97.65  4337.9   96.85  4344.3   97.67  4358.7   97.18
  4373.2   95.23  4516.1   94.24  4621.9   92.58  4644.4   92.95  4721.4   91.44
    4744   91.84  4758.5   89.87  4814.5   91.45  4864.3   89.77  4928.5   89.23
    4943   88.29  4949.3   86.85  4957.4      82  5007.9      82  5011.9      82
  5020.1      82  5026.2   85.91  5046.3   89.38  5060.6   90.65  5100.8   93.13
  5149.8   93.48  5248.9   93.23    5362    93.5  5382.1   94.38  5443.4    95.1
#Mann= 7 ,-1 , 0
    4294    .063       0  4329.6    .035       0  4957.4    .035       0
  5007.9    .035       0  5011.9    .035       0  5149.8    .063       0
  5248.9    .094       0
Bank Sta=4957.4,5020.1
XS Rating Curve= 0 ,0
Exp/Cntr=0.3,0.1

Type RM Length L Ch R = 1 ,1920    ,189,189,189
BEGIN DESCRIPTION:
Mapping XS 46badd28
END DESCRIPTION:
XS GIS Cut Line= 4
      2606144.48     13505266.59      2605849.35     13505176.32
      2605512.55     13505266.59      2605262.53     13505433.27
#Sta/Elev= 30
  4514.8   92.98  4538.9   91.53  4545.6   92.32  4600.4   92.39  4629.3   92.94
  4660.7   91.92  4675.2   90.86  4702.5   90.64  4713.2   90.09  4794.7   90.57
  4848.6   92.24  4875.4   92.39  4900.4   92.31  4950.3   90.74  4962.5    89.6
  4983.2   88.47  4995.5   86.84  5003.9      82  5086.8      82  5097.1   87.24
  5105.2   89.81  5110.3    89.4  5128.2   91.32  5140.3   91.71  5182.7   92.17
  5263.9   91.51  5269.9   91.93  5421.6   92.68  5465.2   94.24  5472.6    93.8
#Mann= 6 ,-1 , 0
  4514.8    .063       0  4600.4    .094       0  4794.7    .063       0
  5003.9    .035       0  5097.1    .063       0  5140.3    .094       0
Bank Sta=5003.9,5086.8
XS Rating Curve= 0 ,0
Exp/Cntr=0.3,0.1

Type RM Length L Ch R = 1 ,1731    ,90,90,90
BEGIN DESCRIPTION:
Mapping XS ed733c23
END DESCRIPTION:
XS GIS Cut Line= 3
      2606019.58     13504729.68      2605605.95     13505053.88
      2605239.83      13505399.9
#Sta/Elev= 30
  4473.5   91.78  4572.9   91.08  4593.8   91.36  4601.9   92.03  4608.2    91.4
  4680.5   92.38    4695   91.81  4744.7   92.41  4771.9   90.78  4808.9   90.66
  4844.1   92.55    4865   92.61  4900.2   92.09  4936.7   90.26  4949.4   88.57
  4964.4   86.24  4972.5      82  5056.9      82  5064.2   85.73  5106.7   90.83
  5141.9   92.33  5182.3   92.33  5198.5   91.48  5234.1   91.01  5297.6   92.39
  5340.1   92.29  5439.2   93.65  5474.4   93.36  5500.6   94.63  5502.8   94.56
#Mann= 4 ,-1 , 0
  4473.5    .094       0  4949.4    .035       0  5182.3    .094       0
  5500.6    .063       0
Bank Sta=4972.5,5056.9
XS Rating Curve= 0 ,0
Exp/Cntr=0.3,0.1

Type RM Length L Ch R = 1 ,1641    ,155,155,155
BEGIN DESCRIPTION:
Mapping XS cb3a1be4
END DESCRIPTION:
XS GIS Cut Line= 3
      2605897.94     13504714.53      2605526.44     13505016.59
      2605221.19     13505370.41
#Sta/Elev= 30
  4523.3   93.61  4609.3   93.04  4732.5   92.07  4753.3   90.83  4845.5   91.95
  4866.7   92.13  4938.6   86.92    4945   85.74  4952.4    82.9  4971.4    82.1
  4971.8    81.6  4976.1    82.1  5004.4   82.12  5009.3   85.46  5015.9   86.68
  5058.7   87.57  5068.5   88.58  5072.9   89.26  5125.2    90.5    5130   91.11
  5136.6    90.5  5144.2   91.75  5150.8   90.97  5195.7   91.59  5236.4   91.53
  5280.7   92.58  5322.8   92.32  5349.4   93.28  5436.2   93.81  5469.4   94.24
#Mann= 11 ,-1 , 0
  4523.3    .094       0  4609.3    .063       0  4845.5    .035       0
  4971.4    .035       0  4976.1    .035       0  5068.5    .063       0
  5125.2    .035       0  5195.7    .094       0  5280.7    .035       0
  5322.8    .094       0  5436.2    .063       0
Bank Sta=4971.4,4976.1
XS Rating Curve= 0 ,0
Exp/Cntr=0.3,0.1

Type RM Length L Ch R = 1 ,1486    ,97,97,97
BEGIN DESCRIPTION:
Mapping XS ed5b6a63
END DESCRIPTION:
XS GIS Cut Line= 3
      2605786.84     13504575.63      2605432.69     13504902.01
      2605069.03     13505237.96
#Sta/Elev= 30
  4532.2   95.34  4541.7   95.44  4575.6   94.88    4683   92.38  4712.8   94.45
  4724.4   95.01  4738.6   91.89  4752.3   91.16  4787.9   91.81  4824.2   89.51
  4865.6   89.41  4950.6   86.53    4979    81.4    5005   81.06  5005.3   80.56
  5009.8   81.06  5028.3   81.26  5070.9   86.34  5127.6    87.8  5134.4   89.57
  5141.7   88.97  5148.5    91.1  5184.3   89.08  5191.1   89.74  5198.4   88.25
  5247.7   89.08  5261.8   89.14  5388.7   92.93  5399.2   93.07  5508.9   95.54
#Mann= 12 ,-1 , 0
  4532.2     .05       0  4541.7    .035       0  4575.6     .05       0
    4683    .035       0  4712.8     .05       0  4824.2    .035       0
    5005    .035       0  5009.8    .035       0  5247.7    .094       0
  5261.8     .05       0  5388.7    .035       0  5399.2     .05       0
Bank Sta=5005,5009.8
XS Rating Curve= 0 ,0
Exp/Cntr=0.3,0.1

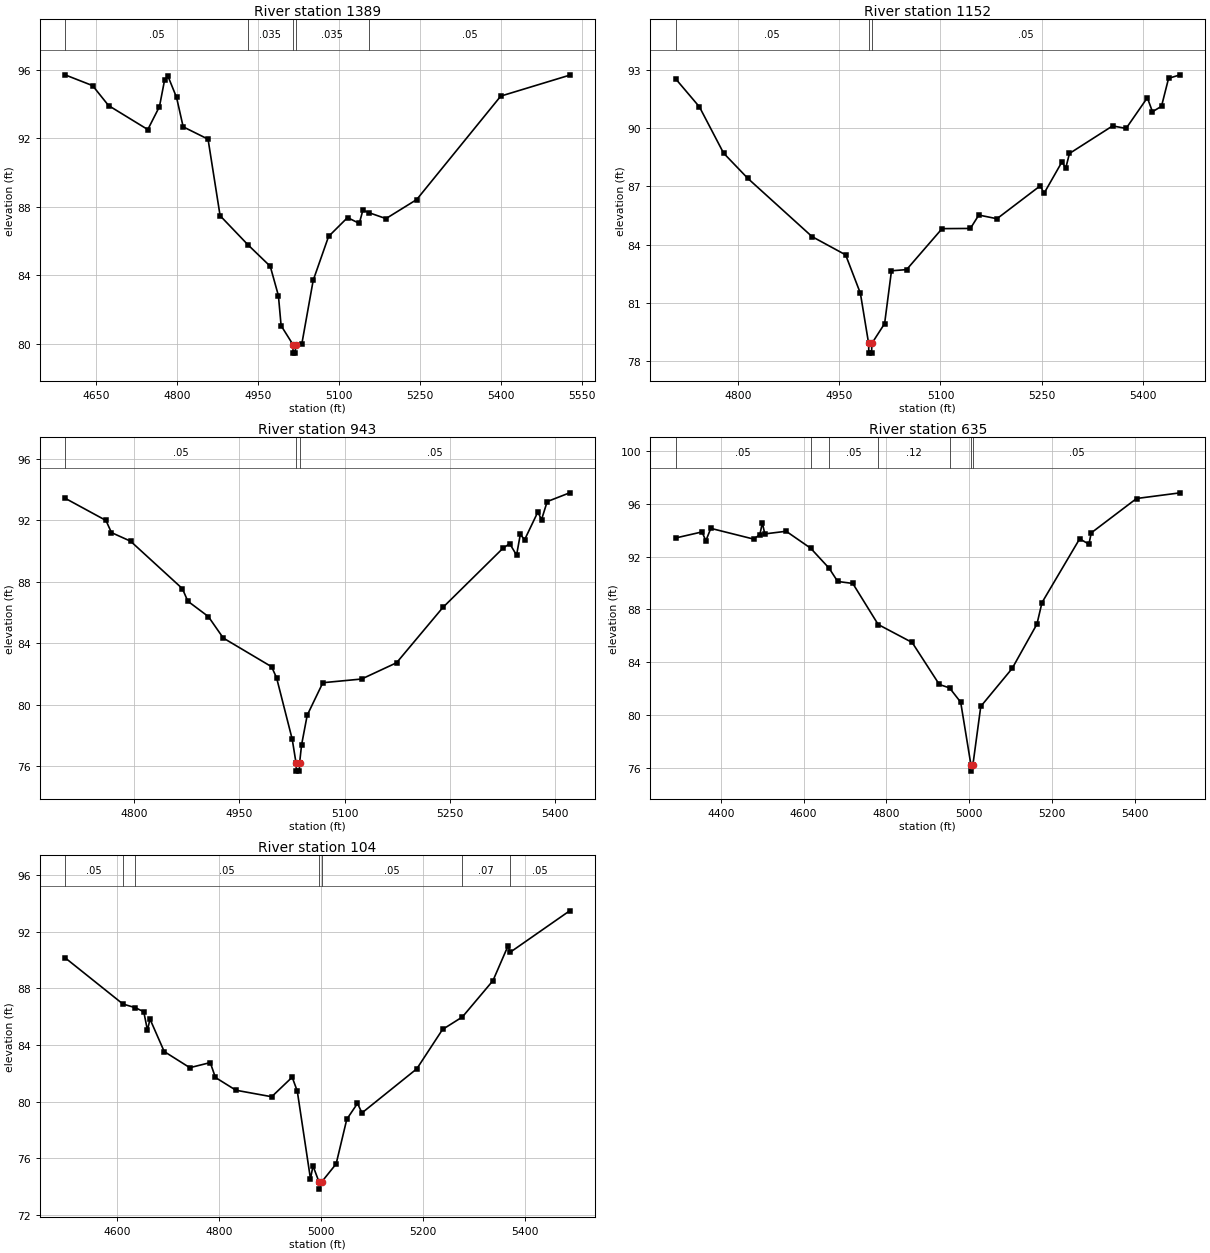
Type RM Length L Ch R = 1 ,1389    ,237,237,237
BEGIN DESCRIPTION:
TRIB 4 TO SPRING CREEK 3.0
END DESCRIPTION:
XS GIS Cut Line= 3
        2605575.       13504475.        2605375.       13504825.
      2604975.01     13505174.99
#Sta/Elev= 30
  4591.9   95.69    4643   95.06  4672.5    93.9  4745.2    92.5  4766.8   93.84
  4776.2   95.37  4782.7    95.6  4798.5   94.37  4810.7   92.66  4856.8   91.94
  4879.1   87.48  4930.5   85.79    4972   84.53  4987.1   82.82  4992.1   81.07
    5014   79.97  5014.3   79.47  5018.4   79.47  5018.8   79.97  5030.6   80.03
  5051.5   83.71    5080   86.27  5115.1   87.37  5136.9   87.03  5143.5    87.8
  5155.3   87.65  5186.3   87.31  5243.2   88.42  5398.9   94.45  5526.5   95.67
#Mann= 5 ,-1 , 0
  4591.9     .05       0  4930.5    .035       0    5014    .035       0
  5018.8    .035       0  5155.3     .05       0
Bank Sta=5014,5018.8
XS Rating Curve= 0 ,0
Exp/Cntr=0.3,0.1

Type RM Length L Ch R = 1 ,1152    ,209,209,209
BEGIN DESCRIPTION:
Mapping XS 32abe26b
END DESCRIPTION:
XS GIS Cut Line= 3
      2605337.55     13504477.24      2605155.28     13504741.98
       2604748.6     13504871.77
#Sta/Elev= 30
  4707.2   92.54  4742.6   91.09  4778.4   88.71  4814.3   87.41  4909.6   84.41
  4959.4   83.47  4981.3   81.49  4993.5   78.91  4993.8   78.41  4997.9   78.41
  4998.3   78.91  5017.2   79.93  5027.4   82.65  5049.8   82.71  5102.4   84.82
  5144.4   84.83  5156.9   85.52  5183.8   85.33  5248.2   87.03  5253.5   86.63
  5280.4   88.27  5285.7   87.92  5291.3   88.69  5355.3   90.11  5375.3   89.98
  5406.8   91.56  5414.4   90.84  5427.8   91.12  5438.3   92.56  5455.5   92.74
#Mann= 3 ,-1 , 0
  4707.2     .05       0  4993.5     .05       0  4998.3     .05       0
Bank Sta=4993.5,4998.3
XS Rating Curve= 0 ,0
Exp/Cntr=0.3,0.1

Type RM Length L Ch R = 1 ,943     ,308,308,308
BEGIN DESCRIPTION:
TRIB 4 TO SPRING CREEK 2.0
END DESCRIPTION:
XS GIS Cut Line= 3
      2605174.99     13504325.02        2605025.       13504575.
      2604625.03     13504724.99
#Sta/Elev= 30
  4701.6   93.44  4759.9   91.99  4767.7    91.2  4794.9   90.64  4868.7   87.55
  4876.5   86.73  4905.7   85.73    4927   84.33  4995.8   82.46  5002.9   81.74
  5025.2   77.73  5030.7   76.16  5031.1   75.66  5035.3   75.66  5035.6   76.16
  5038.5   77.37  5046.5    79.3  5068.8   81.42    5124   81.66  5173.8   82.72
  5239.7   86.32  5325.1   90.17  5334.9   90.48  5344.7   89.73    5350   91.08
  5356.2   90.74  5374.9   92.53  5380.3   92.05  5388.3   93.22  5420.3   93.79
#Mann= 3 ,-1 , 0
  4701.6     .05       0  5030.7     .05       0  5035.6     .05       0
Bank Sta=5030.7,5035.6
XS Rating Curve= 0 ,0
Exp/Cntr=0.3,0.1

Type RM Length L Ch R = 1 ,635     ,531,531,531
BEGIN DESCRIPTION:
Mapping XS 7531d3eb
END DESCRIPTION:
XS GIS Cut Line= 3
      2605366.72     13504037.42      2604751.63     13504429.48
      2604321.58     13504662.43
#Sta/Elev= 30
  4290.7   93.41  4354.6   93.87  4363.9    93.2  4375.8   94.14    4479   93.33
  4494.3   93.66  4500.2   94.56  4506.2   93.72  4557.8   93.92  4616.8   92.64
  4661.3   91.13  4682.2   90.12  4718.6   89.97    4780   86.86    4862    85.5
  4927.6   82.32  4952.3   82.06  4979.2   80.98  5003.8   76.26  5004.2   75.76
  5008.8   76.26  5027.7   80.66  5103.4   83.53  5163.3   86.89  5175.5   88.52
  5266.5   93.35  5288.8   92.94  5294.5    93.8  5403.9    96.4  5509.2   96.83
#Mann= 7 ,-1 , 0
  4290.7     .05       0  4616.8     .12       0  4661.3     .05       0
    4780     .12       0  4952.3     .05       0  5003.8     .05       0
  5008.8     .05       0
Bank Sta=5003.8,5008.8
XS Rating Curve= 0 ,0
Exp/Cntr=0.3,0.1

Type RM Length L Ch R = 1 ,104     ,0,0,0
BEGIN DESCRIPTION:
TRIB 4 TO SPRING CREEK 1.0
END DESCRIPTION:
XS GIS Cut Line= 3
      2605098.87     13503995.45       2604598.8     13503948.14
       2604322.4     13504350.68
#Sta/Elev= 30
  4497.7   90.15  4611.5   86.88  4635.2   86.63  4652.3   86.34  4659.5   85.03
  4664.5   85.82  4692.4   83.53  4742.7   82.39  4782.8   82.75  4792.9    81.7
  4833.1    80.8  4903.4   80.34  4943.6   81.72  4953.6   80.74  4979.5   74.55
  4984.5   75.46  4996.3   74.32  4996.7   73.82  5001.3   74.32  5029.9    75.6
  5050.8   78.75  5071.8   79.87  5080.6    79.2  5188.2   82.31  5238.8   85.09
  5277.7   85.97  5337.7   88.53  5367.5      91  5371.3   90.53  5488.3   93.46
#Mann= 7 ,-1 , 0
  4497.7     .05       0  4611.5     .12       0  4635.2     .05       0
  4996.3     .05       0  5001.3     .05       0  5277.7     .07       0
  5371.3     .05       0
Bank Sta=4996.3,5001.3
XS Rating Curve= 0 ,0
Exp/Cntr=0.3,0.1

Chan Stop Cuts=-1
Use User Specified Reach Order=0
Composite Channel Slope=5