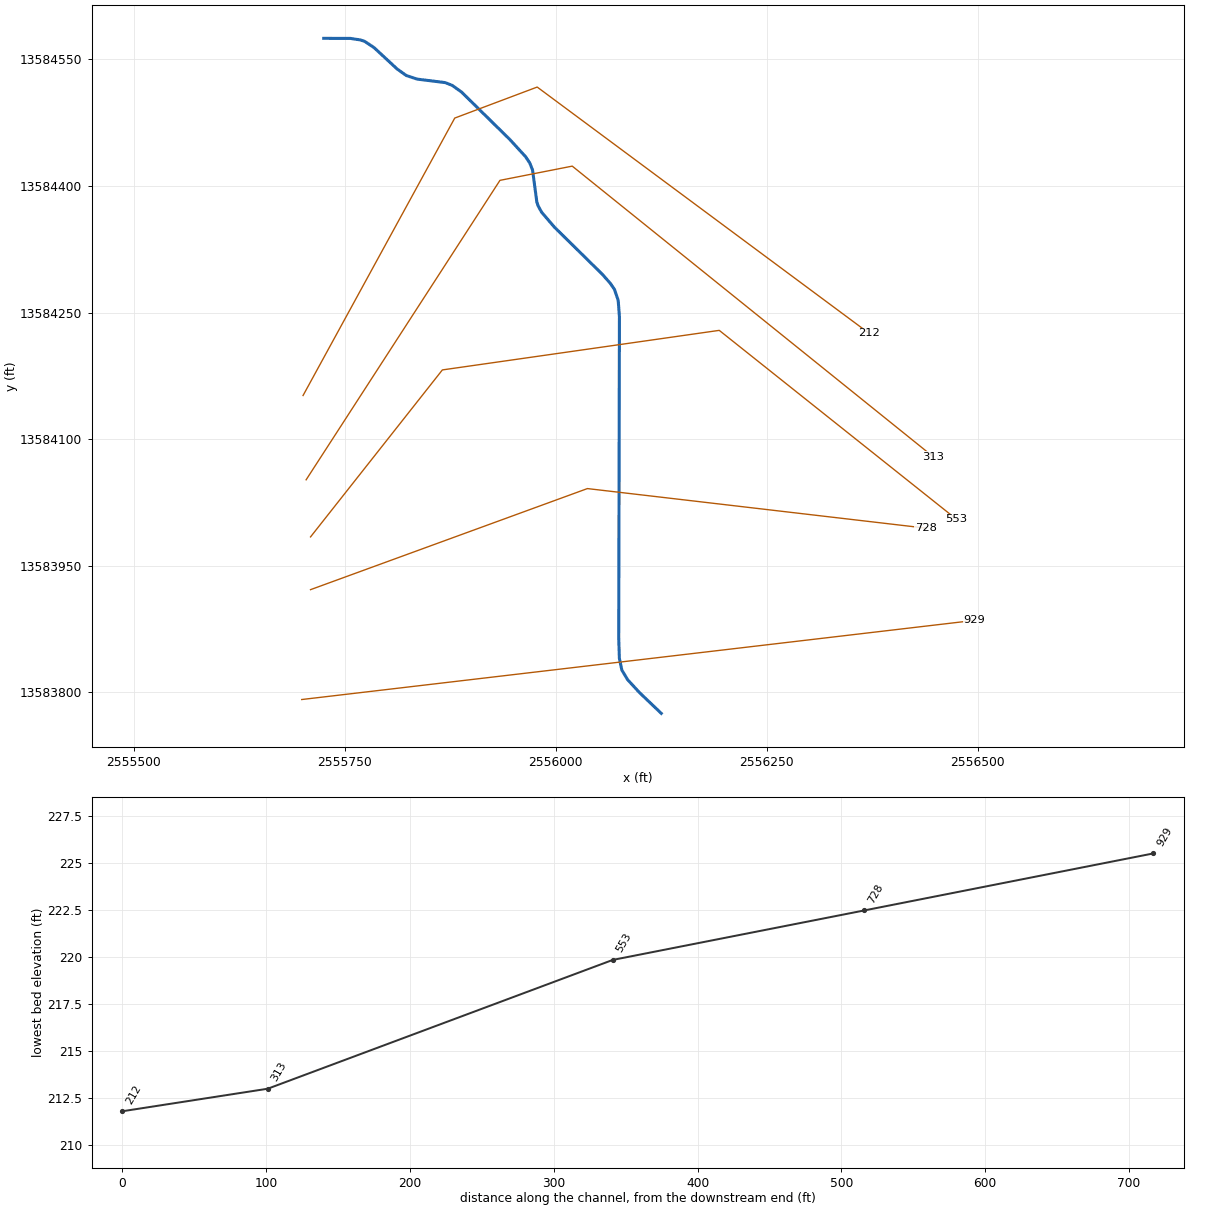
--- TRIB 5 TO CRITTENOON HOLLOW.prj (project) ---

Proj Title=TRIB 5 TO CRITTENOON HOLLOW Base Level Engineering
Current Plan=p01
Default Exp/Contr=0.3,0.1
English Units
Geom File=g01
Flow File=f01
Plan File=p01
Y Axis Title=Elevation
X Axis Title(PF)=Main Channel Distance
X Axis Title(XS)=Station
BEGIN DESCRIPTION:
TRIB 5 TO CRITTENOON HOLLOW
END DESCRIPTION:
DSS Export Rating Curves= 0
DSS Export Rating Curve Sorted= 0
DSS Export Volume Flow Curves= 0
DXF OffsetX= 0
DXF OffsetY= 0
DXF ScaleX= 1
DXF ScaleY= 10

--- TRIB 5 TO CRITTENOON HOLLOW.p01 (plan) ---

Plan Title=Multiple Run
Short Identifier=Multiple
Geom File=g01
Flow File=f01
Subcritical Flow
K Sum by GR= 0
Std Step Tol= 0.01
Critical Tol= 0.01
Num of Std Step Trials= 20
Max Error Tol= 0.3
Flow Tol Ratio= 0.001
Split Flow NTrial= 30
Split Flow Tol= 0.02
Split Flow Ratio= 0.02
Log Output Level= 0
Friction Slope Method= 1
Unsteady Friction Slope Method= 2
Unsteady Bridges Friction Slope Method= 1
Parabolic Critical Depth
Global Vel Dist=  1 , 1 , 1
Global Log Level= 0
CheckData=True
Encroach Param= -1, 0, 0, 0
BEGIN DESCRIPTION:
Multiple Run
END DESCRIPTION:

--- TRIB 5 TO CRITTENOON HOLLOW.f01 (steady flow) ---

Flow Title=Multiple
Number of Profiles=7
Profile Names=10-year,25-year,50-year,1pct_min,100-year,1pct_plu,500-year
River Rch & RM= TRIB 5 TO CRITTE,Reach-1,929
     158     231     291     180     358     715     532
Boundary for River Rch & Prof#=TRIB 5 TO CRITTE,Reach-1,1
Up Type=0
Dn Type=3
Dn Slope=0.005
Boundary for River Rch & Prof#=TRIB 5 TO CRITTE,Reach-1,2
Up Type=0
Dn Type=3
Dn Slope=0.005
Boundary for River Rch & Prof#=TRIB 5 TO CRITTE,Reach-1,3
Up Type=0
Dn Type=3
Dn Slope=0.005
Boundary for River Rch & Prof#=TRIB 5 TO CRITTE,Reach-1,4
Up Type=0
Dn Type=3
Dn Slope=0.005
Boundary for River Rch & Prof#=TRIB 5 TO CRITTE,Reach-1,5
Up Type=0
Dn Type=3
Dn Slope=0.005
Boundary for River Rch & Prof#=TRIB 5 TO CRITTE,Reach-1,6
Up Type=0
Dn Type=3
Dn Slope=0.005
Boundary for River Rch & Prof#=TRIB 5 TO CRITTE,Reach-1,7
Up Type=0
Dn Type=3
Dn Slope=0.005

--- TRIB 5 TO CRITTENOON HOLLOW.g01 (geometry) ---

Geom Title=Existing Conditions
Program Version=4.10

River Reach=TRIB 5 TO CRITTE,Reach-1
Reach XY= 30
        2556125.       13583775.      2556099.11     13583799.71
      2556085.05     13583815.02      2556078.29     13583826.36
      2556075.36     13583840.15      2556074.58     13583864.83
      2556075.43     13584245.18      2556073.95     13584264.56
      2556069.53     13584277.45       2556064.5     13584284.79
      2556055.36     13584295.15      2555998.07     13584351.56
      2555983.18     13584368.96      2555978.99     13584376.65
      2555977.54     13584381.06      2555972.47     13584418.96
      2555969.15      13584427.3      2555964.23      13584434.7
      2555945.42     13584455.23      2555888.24      13584511.4
      2555877.32     13584519.19      2555868.98     13584522.53
      2555835.69     13584526.66      2555822.76     13584530.98
      2555811.85     13584538.78       2555784.6     13584564.02
      2555773.51      13584571.4      2555768.74     13584573.05
      2555756.81      13584574.9        2555725.       13584575.

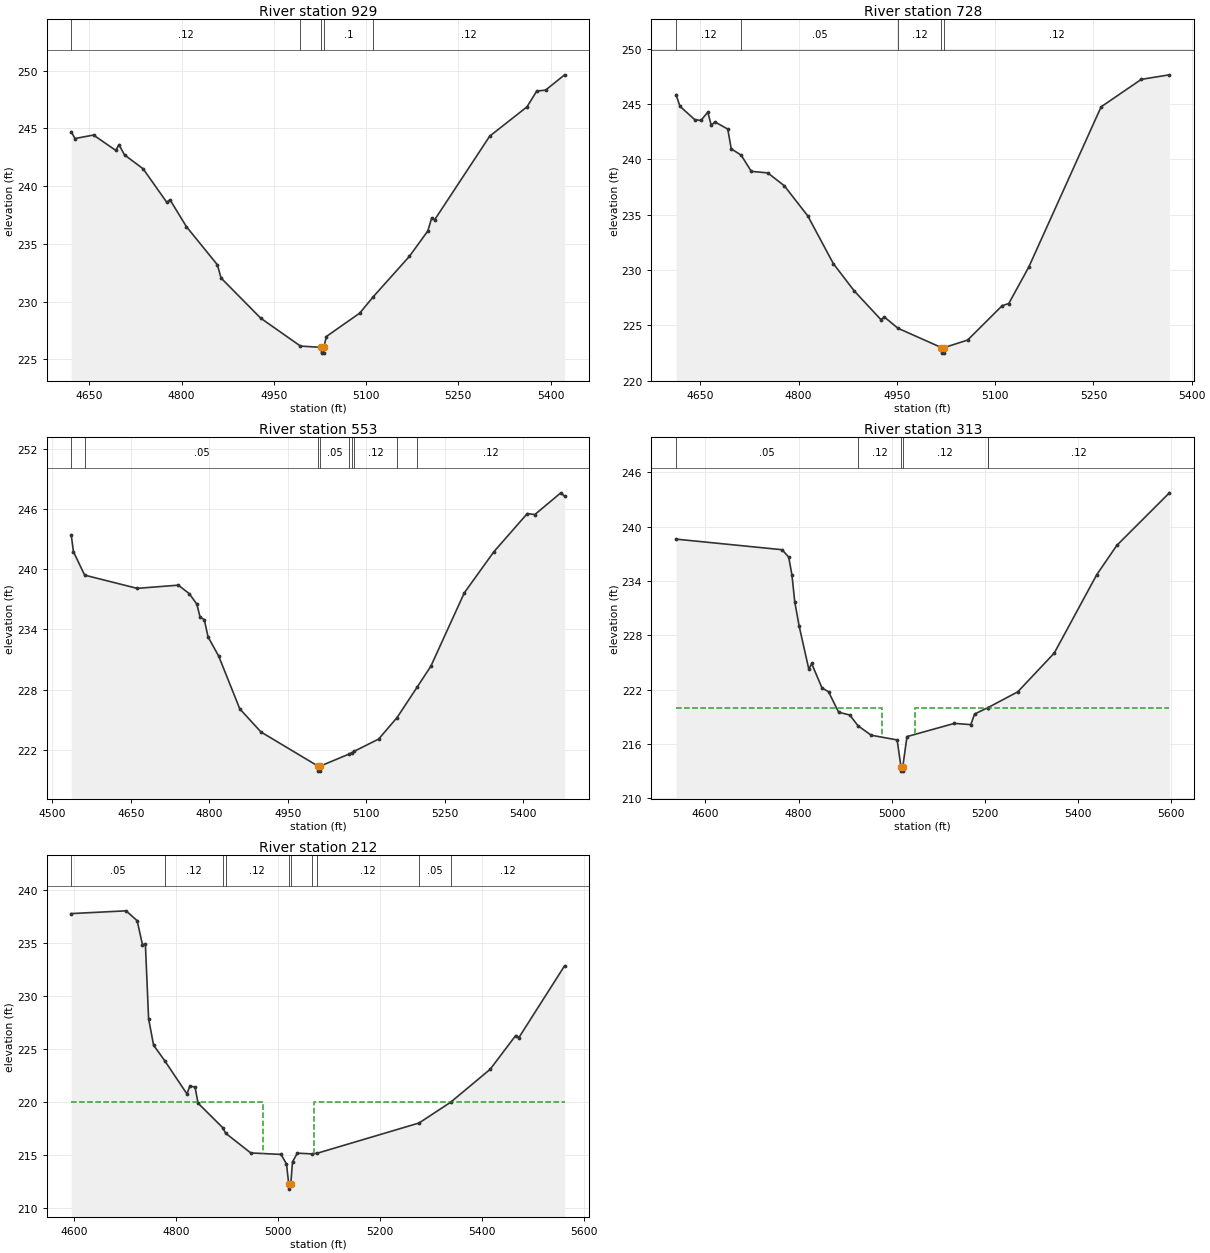
Type RM Length L Ch R = 1 ,929     ,201,201,201
BEGIN DESCRIPTION:
LGII3822
END DESCRIPTION:
XS GIS Cut Line= 2
      2555698.92     13583791.41      2556495.82     13583885.16
#Sta/Elev= 30
  4620.4  244.72  4626.5  244.13  4656.7  244.43  4692.9   243.1    4698   243.6
  4707.1  242.71  4737.3  241.51    4776  238.59    4781  238.83  4807.8  236.49
  4858.1  233.19  4864.1  232.04  4928.6  228.56  4993.3  226.14  5027.3  226.03
  5027.5  225.53    5031  225.53  5031.3  226.03  5035.3  226.97  5089.7     229
  5111.5  230.41  5170.3  233.91  5200.5  236.13  5206.5  237.22  5211.5  237.09
  5301.1  244.34  5361.6  246.87  5377.6  248.25  5391.8  248.32  5422.8  249.65
#Mann= 5 ,-1 , 0
  4620.4     .12       0  4993.3      .1       0  5027.3     .05       0
  5031.3      .1       0  5111.5     .12       0
Bank Sta=5027.3,5031.3
XS Rating Curve= 0 ,0
Exp/Cntr=0.3,0.1

Type RM Length L Ch R = 1 ,728     ,175,175,175
BEGIN DESCRIPTION:
LGII3821
END DESCRIPTION:
XS GIS Cut Line= 3
      2555709.33     13583921.61      2556037.47     13584041.41
      2556438.51     13583994.54
#Sta/Elev= 30
  4612.9  245.84  4618.9  244.79  4641.5  243.58  4650.9  243.51  4661.4  244.26
  4666.7  243.07  4672.2  243.38  4691.9  242.73  4697.2  240.94  4712.3  240.38
  4727.8  238.91    4753  238.77  4778.2  237.61  4814.1  234.88  4853.1  230.57
  4885.1   228.1  4925.6  225.52    4931  225.75  4951.6  224.74  5018.1  222.99
  5018.4  222.49  5021.9  222.49  5022.1  222.99    5058  223.67  5110.8  226.78
  5120.8  226.97  5151.4  230.27  5261.8  244.74  5323.1  247.22    5366  247.63
#Mann= 5 ,-1 , 0
  4612.9     .12       0  4712.3     .05       0  4951.6     .12       0
  5018.1     .05       0  5022.1     .12       0
Bank Sta=5018.1,5022.1
XS Rating Curve= 0 ,0
Exp/Cntr=0.3,0.1

Type RM Length L Ch R = 1 ,553     ,240,240,240
BEGIN DESCRIPTION:
LGII3820
END DESCRIPTION:
XS GIS Cut Line= 4
      2555709.36     13583984.14      2555865.59     13584182.04
      2556193.72     13584228.91      2556474.95     13584004.97
#Sta/Elev= 30
    4536  243.45  4540.3  241.76  4561.7  239.42  4662.1   238.1  4740.7  238.42
  4761.5  237.58    4776  236.54  4782.3  235.25  4790.4  234.97  4797.6  233.25
  4817.8  231.35  4858.2  226.07  4898.7  223.76  5007.8  220.35    5008  219.85
  5011.5  219.85  5011.8  220.35  5067.4  221.56  5072.3   221.7  5076.6  221.82
  5123.6  223.05  5158.9   225.2  5197.4  228.25  5223.5  230.33  5287.4  237.65
  5343.8  241.75  5407.8  245.57  5422.2  245.47  5471.9  247.64  5479.1   247.3
#Mann= 9 ,-1 , 0
    4536     .12       0  4561.7     .05       0  5007.8     .05       0
  5011.8     .05       0  5067.4     .12       0  5072.3     .05       0
  5076.6     .12       0  5158.9     .05       0  5197.4     .12       0
Bank Sta=5007.8,5011.8
XS Rating Curve= 0 ,0
Exp/Cntr=0.3,0.1

Type RM Length L Ch R = 1 ,313     ,101,101,101
BEGIN DESCRIPTION:
LGII3819
END DESCRIPTION:
XS GIS Cut Line= 4
      2555704.12     13584051.81      2555933.84      13584406.7
      2556019.51     13584423.55      2556447.58     13584078.96
#Sta/Elev= 30
  4536.9  238.63  4764.8  237.46  4778.9  236.64  4785.9  234.66  4791.9  231.72
  4801.1  229.07  4822.2  224.24  4828.2  224.88  4850.4  222.18  4864.4  221.76
  4886.2  219.49  4909.9  219.19  4927.9  217.99  4956.1  216.95  5011.8  216.43
    5020  213.48  5020.2  212.98  5023.7  212.98    5024  213.48  5032.9   216.8
  5134.9  218.26  5170.1  218.12  5178.1  219.29  5206.2  219.99  5207.2  220.01
  5270.9  221.75  5349.2  226.03  5440.5   234.7  5483.6  237.94  5596.5  243.75
#Mann= 6 ,-1 , 0
  4536.9     .05       0  4927.9     .12       0    5020     .05       0
    5024     .12       0  5206.2     .05       0  5207.2     .12       0
#XS Ineff= 2 , 0
       0    4980     220    5050       0     220
Permanent Ineff=
       F       F
Bank Sta=5020,5024
XS Rating Curve= 0 ,0
Exp/Cntr=0.3,0.1

Type RM Length L Ch R = 1 ,212     ,0,0,0
BEGIN DESCRIPTION:
4828
END DESCRIPTION:
XS GIS Cut Line= 4
      2555700.48     13584151.69      2555880.25      13584480.5
      2555977.97     13584517.26      2556370.97     13584225.68
#Sta/Elev= 30
  4594.3  237.74  4701.9     238  4723.8  237.07  4734.2   234.8  4739.9   234.9
  4746.2  227.85    4756  225.34  4777.7  223.89  4821.5  220.75  4827.2  221.49
  4837.4   221.4  4843.3  219.88  4891.7  217.57  4897.4  217.05  4946.7  215.19
  5006.2  215.05  5016.9  214.15  5021.3  212.28  5021.6  211.78  5025.3  212.28
  5028.7  214.35  5038.2  215.17  5066.5   215.1  5077.1  215.16  5277.1  218.01
  5339.2  219.97  5416.7  223.07  5466.8  226.25    5473  226.05  5562.8  232.82
#Mann= 10 ,-1 , 0
  4594.3     .05       0  4777.7     .12       0  4891.7     .05       0
  4897.4     .12       0  5021.3     .05       0  5025.3     .12       0
  5066.5     .05       0  5077.1     .12       0  5277.1     .05       0
  5339.2     .12       0
#XS Ineff= 2 , 0
       0    4970     220    5070       0     220
Permanent Ineff=
       F       F
Bank Sta=5021.3,5025.3
XS Rating Curve= 0 ,0
Exp/Cntr=0.3,0.1

Chan Stop Cuts=-1
Use User Specified Reach Order=0
Composite Channel Slope=5