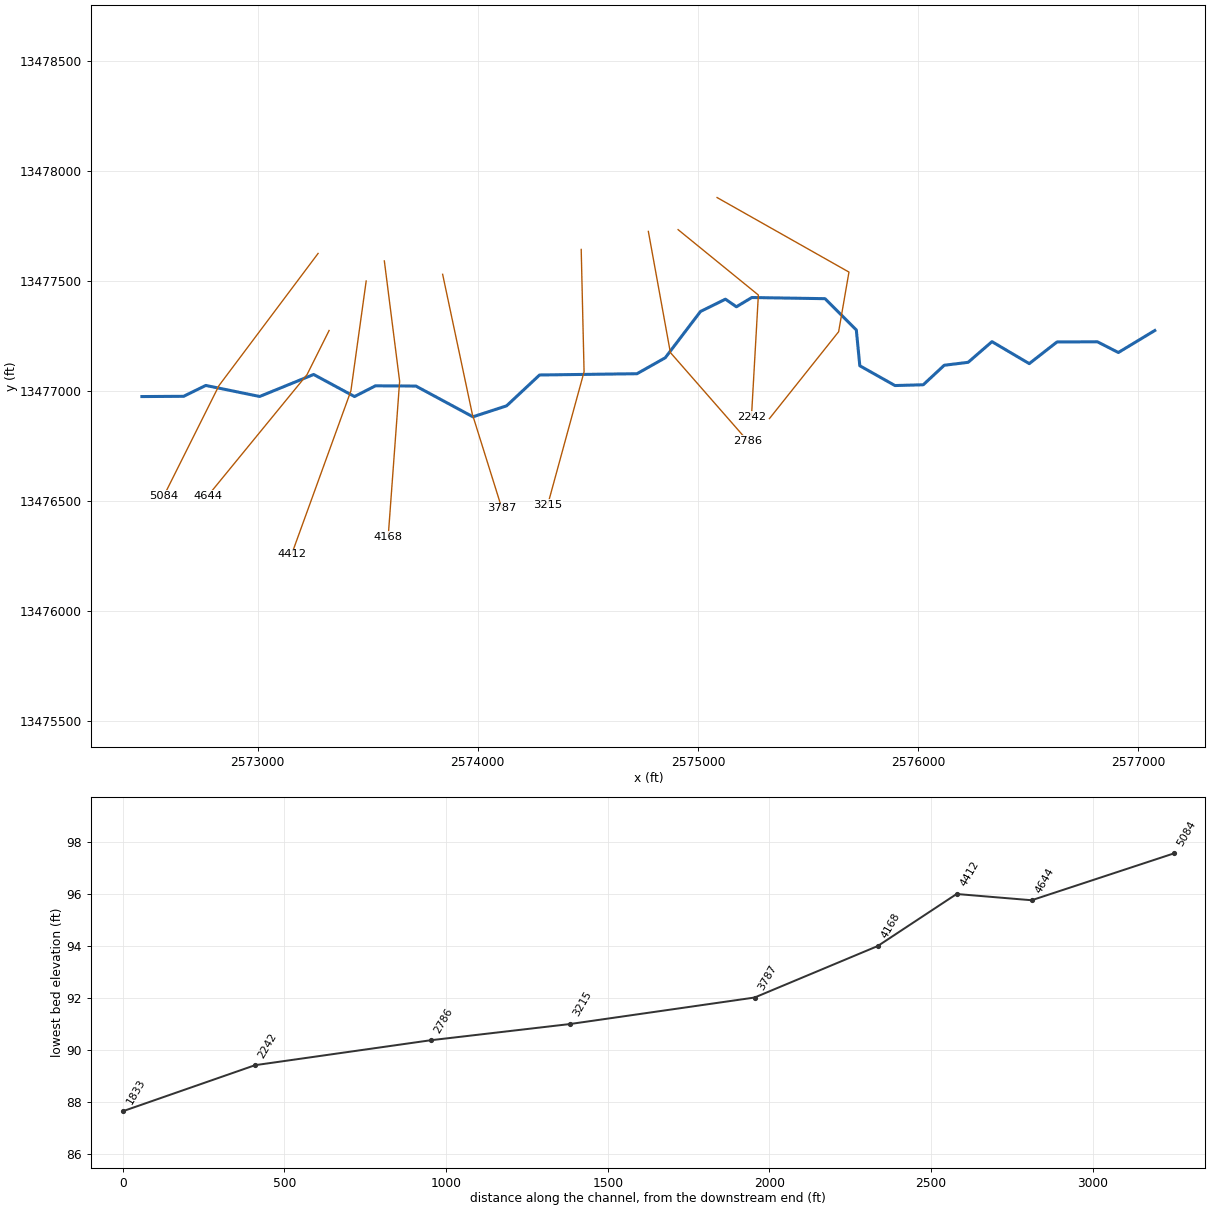
--- TRIB 5 TO DRY CREEK.prj (project) ---

Proj Title=TRIB 5 TO DRY CREEK Base Level Engineering
Current Plan=p01
Default Exp/Contr=0.3,0.1
English Units
Geom File=g01
Flow File=f01
Plan File=p01
Y Axis Title=Elevation
X Axis Title(PF)=Main Channel Distance
X Axis Title(XS)=Station
BEGIN DESCRIPTION:
TRIB 5 TO DRY CREEK
END DESCRIPTION:
DSS Export Rating Curves= 0
DSS Export Rating Curve Sorted= 0
DSS Export Volume Flow Curves= 0
DXF OffsetX= 0
DXF OffsetY= 0
DXF ScaleX= 1
DXF ScaleY= 10

--- TRIB 5 TO DRY CREEK.p01 (plan) ---

Plan Title=Multiple Run
Short Identifier=Multiple
Geom File=g01
Flow File=f01
Subcritical Flow
K Sum by GR= 0
Std Step Tol= 0.01
Critical Tol= 0.01
Num of Std Step Trials= 20
Max Error Tol= 0.3
Flow Tol Ratio= 0.001
Split Flow NTrial= 30
Split Flow Tol= 0.02
Split Flow Ratio= 0.02
Log Output Level= 0
Friction Slope Method= 1
Unsteady Friction Slope Method= 2
Unsteady Bridges Friction Slope Method= 1
Parabolic Critical Depth
Global Vel Dist=  1 , 1 , 1
Global Log Level= 0
CheckData=True
Encroach Param= -1, 0, 0, 0
BEGIN DESCRIPTION:
Multiple Run
END DESCRIPTION:

--- TRIB 5 TO DRY CREEK.f01 (steady flow) ---

Flow Title=Multiple
Number of Profiles=7
Profile Names=10-year,25-year,50-year,1pct_min,100-year,1pct_plu,500-year
River Rch & RM= TRIB 5 TO DRY CR,Reach-1,5084
     933    1485    1975    1268    2529    5047    4103
Boundary for River Rch & Prof#=TRIB 5 TO DRY CR,Reach-1,1
Up Type=0
Dn Type=3
Dn Slope=0.005
Boundary for River Rch & Prof#=TRIB 5 TO DRY CR,Reach-1,2
Up Type=0
Dn Type=3
Dn Slope=0.005
Boundary for River Rch & Prof#=TRIB 5 TO DRY CR,Reach-1,3
Up Type=0
Dn Type=3
Dn Slope=0.005
Boundary for River Rch & Prof#=TRIB 5 TO DRY CR,Reach-1,4
Up Type=0
Dn Type=3
Dn Slope=0.005
Boundary for River Rch & Prof#=TRIB 5 TO DRY CR,Reach-1,5
Up Type=0
Dn Type=3
Dn Slope=0.005
Boundary for River Rch & Prof#=TRIB 5 TO DRY CR,Reach-1,6
Up Type=0
Dn Type=3
Dn Slope=0.005
Boundary for River Rch & Prof#=TRIB 5 TO DRY CR,Reach-1,7
Up Type=0
Dn Type=3
Dn Slope=0.005

--- TRIB 5 TO DRY CREEK.g01 (geometry) ---

Geom Title=Existing Conditions
Program Version=4.10

River Reach=TRIB 5 TO DRY CR,Reach-1
Reach XY= 30
        2572475.       13476975.       2572664.5     13476976.21
      2572764.83      13477025.5      2573009.73     13476975.38
      2573254.83      13477075.3      2573440.39     13476975.08
       2573535.5     13477023.76      2573719.07     13477022.76
      2573978.29     13476883.05      2574131.17     13476932.86
      2574280.85     13477072.94      2574723.45     13477078.75
      2574851.88     13477151.27      2575011.76     13477361.41
      2575125.08     13477417.24       2575174.9      13477382.8
      2575244.98     13477424.82      2575577.45     13477419.54
      2575719.53     13477277.45      2575735.35     13477114.88
      2575895.03     13477025.04      2576023.53     13477028.54
      2576118.84     13477117.12      2576227.42     13477130.54
      2576335.64     13477224.44      2576504.84     13477124.53
      2576630.86     13477222.93       2576814.5     13477223.76
      2576909.61     13477175.07        2577075.       13477275.

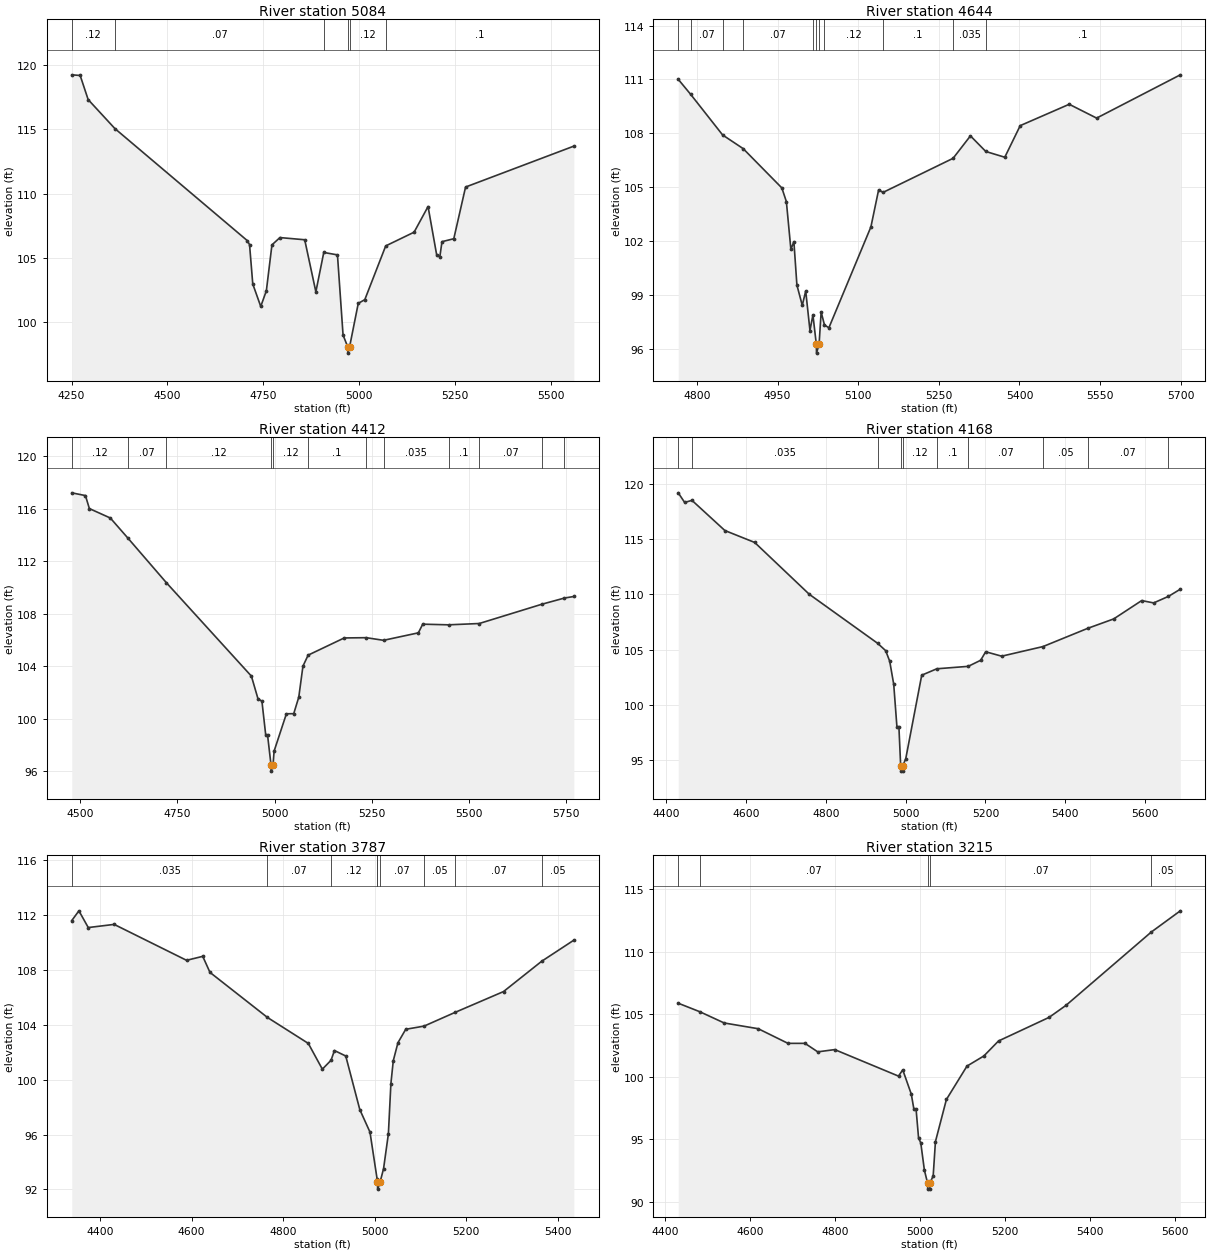
Type RM Length L Ch R = 1 ,5084    ,440,440,440
BEGIN DESCRIPTION:
TRIB 5 TO DRY CREEK 7.0
END DESCRIPTION:
XS GIS Cut Line= 3
      2573274.99     13477624.99        2572825.       13477025.
        2572575.     13476525.01
#Sta/Elev= 30
  4250.6  119.26  4272.5  119.21  4293.3  117.33    4363  115.07  4707.9  106.34
  4714.1  106.02  4722.5  102.95  4743.3   101.2  4757.9  102.42  4772.5     106
  4793.3  106.57  4857.9   106.4    4887  102.34  4907.6  105.41  4943.3  105.22
  4957.9   98.97  4969.9   98.06  4970.3   97.56    4975   98.06  4997.5  101.44
  5014.6  101.73  5069.1  105.92  5143.1  106.99  5179.5  108.99  5201.8  105.25
  5210.2  105.06  5215.8  106.25  5246.6  106.48  5277.3  110.51  5559.6   113.7
#Mann= 6 ,-1 , 0
  4250.6     .12       0    4363     .07       0  4907.6     .12       0
  4969.9     .05       0    4975     .12       0  5069.1      .1       0
Bank Sta=4969.9,4975
XS Rating Curve= 0 ,0
Exp/Cntr=0.3,0.1

Type RM Length L Ch R = 1 ,4644    ,232,232,232
BEGIN DESCRIPTION:
TRIB 5 TO DRY CREEK 6.0
END DESCRIPTION:
XS GIS Cut Line= 3
      2573324.99     13477274.99        2573225.       13477075.
      2572775.02     13476525.02
#Sta/Elev= 30
  4765.1  111.01  4788.3  110.17  4847.7  107.91  4885.9  107.15  4957.9  104.96
  4966.3   104.2  4974.7  101.54  4980.3  101.97  4985.9   99.55  4995.9   98.42
  5002.3   99.22  5010.2   97.02  5015.7   97.89    5022   96.26  5022.4   95.76
  5027.2   96.26    5031   98.05  5037.2   97.33  5045.4   97.17  5123.6  102.79
    5138  104.86  5146.1  104.71  5276.5  106.61  5308.8  107.86  5337.4  106.99
  5372.7  106.67  5401.4  108.43  5492.6  109.62  5543.6  108.85  5699.3  111.26
#Mann= 11 ,-1 , 0
  4765.1     .12       0  4788.3     .07       0  4847.7     .12       0
  4885.9     .07       0  5015.7      .1       0    5022     .05       0
  5027.2      .1       0  5037.2     .12       0  5146.1      .1       0
  5276.5    .035       0  5337.4      .1       0
Bank Sta=5022,5027.2
XS Rating Curve= 0 ,0
Exp/Cntr=0.3,0.1

Type RM Length L Ch R = 1 ,4412    ,244,244,244
BEGIN DESCRIPTION:
Mapping XS 4c24fa3a
END DESCRIPTION:
XS GIS Cut Line= 3
      2573493.48     13477499.89      2573424.03     13477000.71
      2573155.19     13476259.23
#Sta/Elev= 30
  4477.9  117.21  4513.1     117  4523.2  116.01  4577.2  115.29  4621.8  113.78
  4721.8  110.35  4940.4  103.24  4957.4  101.51  4967.5  101.33  4977.2   98.77
  4981.9   98.77  4990.8    96.5  4991.2      96  4996.2    96.5  4998.8   97.52
  5030.5  100.37  5049.4  100.38  5062.4  101.64  5073.1     104  5086.5  104.84
  5179.4  106.15    5236  106.17  5280.7  105.97  5370.3  106.54  5381.5   107.2
  5447.9  107.15    5527  107.25  5688.3  108.72  5746.2  109.19  5770.6  109.31
#Mann= 12 ,-1 , 0
  4477.9     .12       0  4621.8     .07       0  4721.8     .12       0
  4990.8     .05       0  4996.2     .12       0  5086.5      .1       0
    5236     .12       0  5280.7    .035       0  5447.9      .1       0
    5527     .07       0  5688.3     .12       0  5746.2     .07       0
Bank Sta=4990.8,4996.2
XS Rating Curve= 0 ,0
Exp/Cntr=0.3,0.1

Type RM Length L Ch R = 1 ,4168    ,381,381,381
BEGIN DESCRIPTION:
Mapping XS 50ac9562
END DESCRIPTION:
XS GIS Cut Line= 3
      2573575.94     13477590.96      2573645.38     13477044.11
      2573593.42     13476338.36
#Sta/Elev= 30
  4429.8  119.18  4445.9  118.31  4464.2   118.5  4546.7  115.77  4621.5  114.69
  4758.4     110  4929.6  105.57  4949.9   104.9    4960  103.95  4970.1  101.86
  4978.1   98.02  4983.1   98.02  4987.5    94.5  4987.9      94  4992.4      94
  4992.9    94.5  5000.2   95.11  5040.3  102.68  5078.2  103.26  5156.9  103.48
  5188.1  104.03  5200.7   104.8  5240.8   104.4  5344.4  105.27  5456.6  106.92
  5521.6  107.77  5591.8  109.43  5621.9  109.22  5658.9  109.81  5688.7  110.46
#Mann= 10 ,-1 , 0
  4429.8     .07       0  4464.2    .035       0  4929.6     .12       0
  4987.5     .05       0  4992.9     .12       0  5078.2      .1       0
  5156.9     .07       0  5344.4     .05       0  5456.6     .07       0
  5658.9     .05       0
Bank Sta=4987.5,4992.9
XS Rating Curve= 0 ,0
Exp/Cntr=0.3,0.1

Type RM Length L Ch R = 1 ,3787    ,572,572,572
BEGIN DESCRIPTION:
Mapping XS 14f717b2
END DESCRIPTION:
XS GIS Cut Line= 3
      2573840.69     13477530.24      2573975.24     13476896.54
      2574109.29     13476468.46
#Sta/Elev= 30
  4338.5  111.61  4354.1  112.32  4374.5   111.1  4431.1  111.33  4589.2  108.71
  4624.5     109  4640.3  107.83  4765.9  104.54    4855  102.65  4885.7  100.77
  4904.7  101.42  4912.1  102.13  4936.8  101.73  4967.5   97.82  4989.7   96.18
  5005.3   92.75    5006   92.52  5006.5   92.02  5011.7   92.52  5019.4   93.52
  5029.9   96.05  5035.4   99.72  5040.6  101.39  5050.8   102.7  5067.8  103.68
  5107.8  103.91  5176.1  104.92  5281.3  106.43  5364.6  108.64  5434.9  110.18
#Mann= 9 ,-1 , 0
  4338.5    .035       0  4765.9     .07       0  4904.7     .12       0
  5005.3     .07       0    5006     .05       0  5011.7     .07       0
  5107.8     .05       0  5176.1     .07       0  5364.6     .05       0
Bank Sta=5006,5011.7
XS Rating Curve= 0 ,0
Exp/Cntr=0.3,0.1

Type RM Length L Ch R = 1 ,3215    ,429,429,429
BEGIN DESCRIPTION:
Mapping XS d16250a8
END DESCRIPTION:
XS GIS Cut Line= 3
      2574470.03      13477643.1      2574483.06     13477087.51
      2574318.12     13476484.19
#Sta/Elev= 30
  4431.3  105.87    4482  105.19  4539.4  104.29  4619.5  103.83  4689.5  102.66
  4729.5  102.66  4759.5  101.98  4799.5  102.16  4949.5  100.04  4959.5  100.54
  4979.6    98.6  4985.8   97.38  4990.9   97.38  4996.7   95.09  5001.9    94.7
  5010.4   92.52  5017.8    91.5  5018.3      91  5023.1      91  5023.6    91.5
  5031.1   92.06  5036.4    94.8  5062.2   98.17  5110.6  100.84  5150.3  101.65
  5184.8  102.85  5303.9  104.74  5343.6   105.7  5544.1  111.56  5612.5  113.26
#Mann= 5 ,-1 , 0
  4431.3      .1       0    4482     .07       0  5017.8     .05       0
  5023.6     .07       0  5544.1     .05       0
Bank Sta=5017.8,5023.6
XS Rating Curve= 0 ,0
Exp/Cntr=0.3,0.1

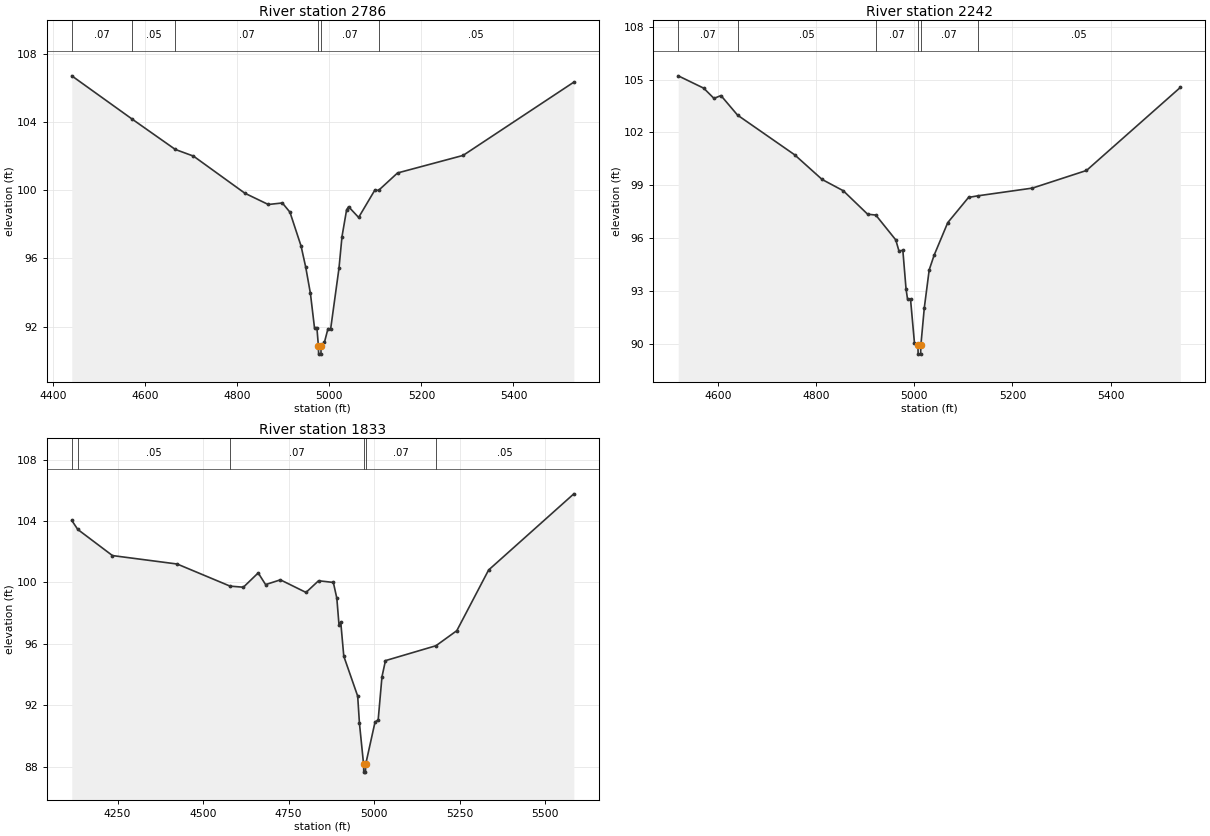
Type RM Length L Ch R = 1 ,2786    ,544,544,544
BEGIN DESCRIPTION:
TRIB 5 TO DRY CREEK 2.0
END DESCRIPTION:
XS GIS Cut Line= 3
      2574774.99     13477725.03        2574875.       13477175.
      2575225.03     13476774.96
#Sta/Elev= 30
  4440.5  106.71  4572.2  104.16  4665.4  102.39  4704.8     102  4816.6   99.82
  4867.4   99.16  4897.9   99.25  4914.4   98.71  4938.6   96.72  4948.7   95.48
  4958.9   93.94  4967.8   91.91  4972.9   91.94  4976.2   90.88  4976.7   90.38
  4981.7   90.38  4982.2   90.88  4989.4   91.08    4997   91.87  5002.9   91.87
  5020.9   95.41  5027.5   97.28  5037.5   98.85  5041.8   99.03  5063.6    98.4
  5098.7     100    5107   99.99  5148.1  101.01  5290.5  102.04  5531.1  106.34
#Mann= 6 ,-1 , 0
  4440.5     .07       0  4572.2     .05       0  4665.4     .07       0
  4976.2     .05       0  4982.2     .07       0    5107     .05       0
Bank Sta=4976.2,4982.2
XS Rating Curve= 0 ,0
Exp/Cntr=0.3,0.1

Type RM Length L Ch R = 1 ,2242    ,409,409,409
BEGIN DESCRIPTION:
Mapping XS 09381639
END DESCRIPTION:
XS GIS Cut Line= 3
      2574910.04     13477733.05      2575274.62     13477436.17
      2575243.37     13476884.12
#Sta/Elev= 30
    4519  105.21  4570.9  104.51  4591.8  103.93  4606.1  104.09  4639.9  102.98
  4756.2  100.73  4812.2   99.33  4855.3   98.69  4904.9   97.36  4921.6   97.31
  4962.3    95.9  4968.8   95.27  4976.7   95.31  4983.2   93.12  4986.2   92.55
  4992.3   92.55  5000.4   90.04  5007.4   89.92  5007.9   89.42  5012.9   89.42
  5013.4   89.92  5020.4   92.04  5030.4    94.2  5040.4   95.03  5068.2   96.88
  5110.5   98.31    5129    98.4  5240.7   98.84  5350.9   99.84  5542.1  104.55
#Mann= 6 ,-1 , 0
    4519     .07       0  4639.9     .05       0  4921.6     .07       0
  5007.4     .05       0  5013.4     .07       0    5129     .05       0
Bank Sta=5007.4,5013.4
XS Rating Curve= 0 ,0
Exp/Cntr=0.3,0.1

Type RM Length L Ch R = 1 ,1833    ,0,0,0
BEGIN DESCRIPTION:
TRIB 5 TO DRY CREEK 1.0
END DESCRIPTION:
XS GIS Cut Line= 4
      2575087.16     13477878.86      2575686.08     13477540.34
       2575639.2     13477269.51      2575324.98     13476874.98
#Sta/Elev= 30
  4116.3  104.04  4133.9  103.45  4235.2  101.75  4424.3   101.2  4578.9   99.76
  4617.8   99.69  4661.1  100.62  4682.7   99.86    4726  100.17  4800.8   99.35
  4837.5  100.11  4880.7     100  4890.9   98.97  4897.3   97.21  4902.3   97.42
  4911.2    95.2  4951.8    92.6    4957   90.82  4969.1   88.15  4969.6   87.65
  4974.6   87.65  4975.1   88.15  5002.5   90.91  5011.7   91.05  5022.8   93.86
    5033   94.91  5180.6   95.88  5241.5   96.86  5334.4  100.81  5583.5  105.77
#Mann= 6 ,-1 , 0
  4116.3     .07       0  4133.9     .05       0  4578.9     .07       0
  4969.1     .05       0  4975.1     .07       0  5180.6     .05       0
Bank Sta=4969.1,4975.1
XS Rating Curve= 0 ,0
Exp/Cntr=0.3,0.1

Chan Stop Cuts=-1
Use User Specified Reach Order=0
Composite Channel Slope=5