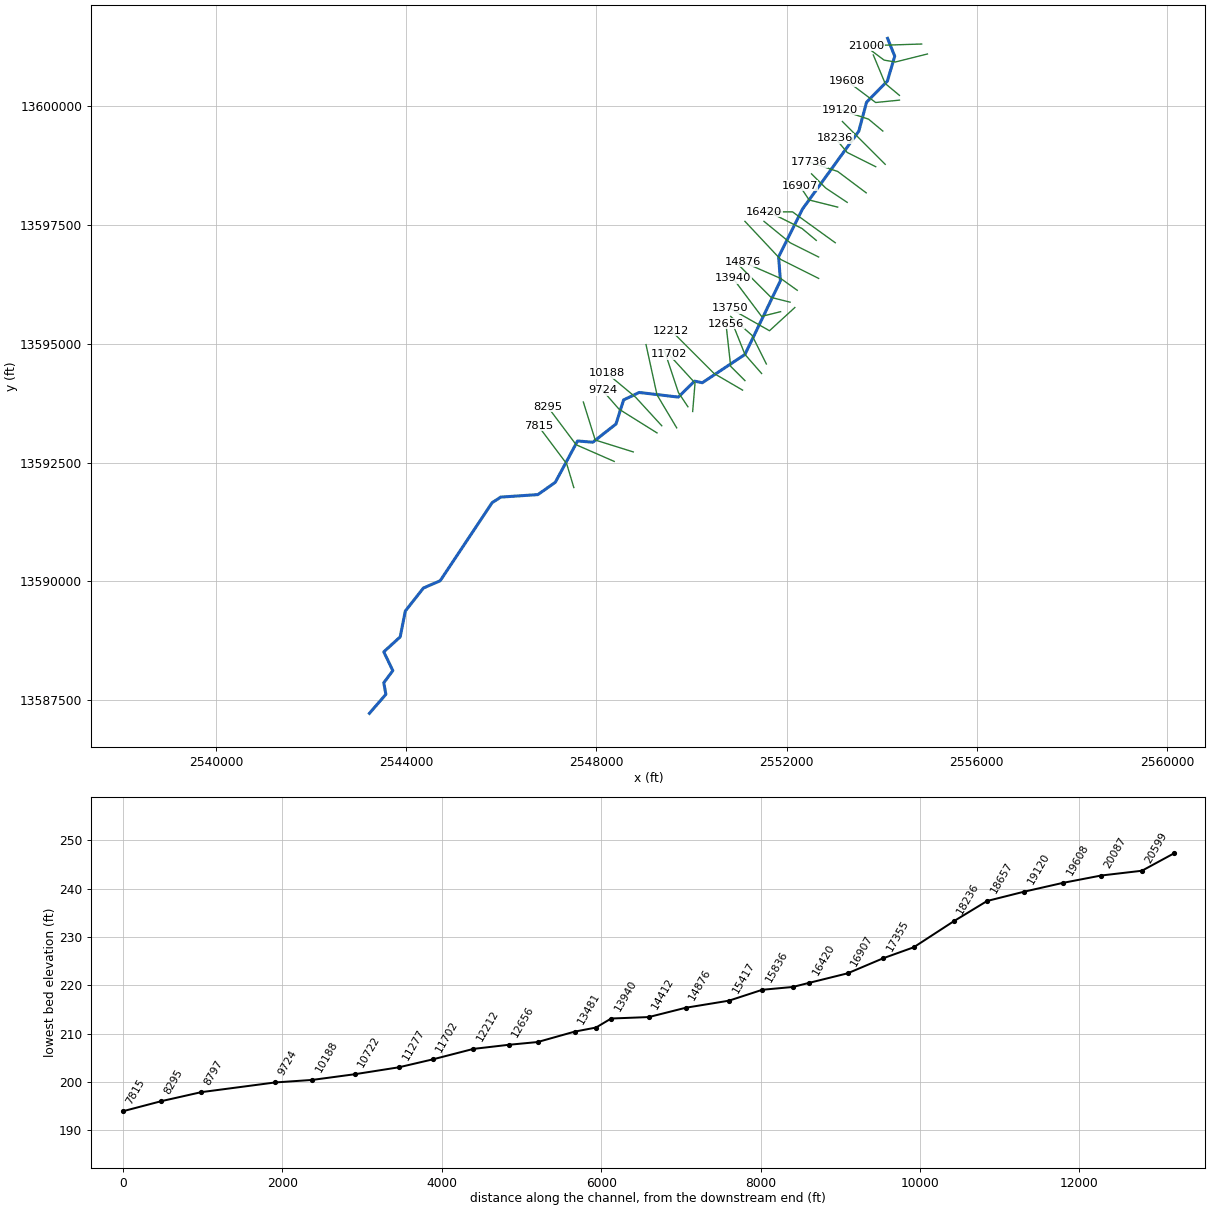
--- TRIB 5 TO IRISH CREEK.prj (project) ---

Proj Title=TRIB 5 TO IRISH CREEK Base Level Engineering
Current Plan=p01
Default Exp/Contr=0.3,0.1
English Units
Geom File=g01
Flow File=f01
Plan File=p01
BEGIN DESCRIPTION:
TRIB 5 TO IRISH CREEK
END DESCRIPTION:

--- TRIB 5 TO IRISH CREEK.p01 (plan) ---

Plan Title=Multiple Run
Short Identifier=Multiple
Geom File=g01
Flow File=f01
Subcritical Flow
K Sum by GR= 0
Std Step Tol= 0.01
Critical Tol= 0.01
Num of Std Step Trials= 20
Max Error Tol= 0.3
Flow Tol Ratio= 0.001
Split Flow NTrial= 30
Split Flow Tol= 0.02
Split Flow Ratio= 0.02
Log Output Level= 0
Friction Slope Method= 1
Unsteady Friction Slope Method= 2
Unsteady Bridges Friction Slope Method= 1
Parabolic Critical Depth
Global Vel Dist=  1 , 1 , 1
Global Log Level= 0
CheckData=True
Encroach Param= -1, 0, 0, 0
BEGIN DESCRIPTION:
Multiple Run
END DESCRIPTION:

--- TRIB 5 TO IRISH CREEK.f01 (steady flow) ---

Flow Title=Multiple
Number of Profiles=7
Profile Names=10-year,25-year,50-year,1pct_min,100-year,1pct_plu,500-year
River Rch & RM= TRIB 5 TO IRISH ,Reach-1,21000
     482     756     999     640    1278    2549    2064
River Rch & RM= TRIB 5 TO IRISH ,Reach-1,20087
     712    1143    1531     994    1983    3957    3290
River Rch & RM= TRIB 5 TO IRISH ,Reach-1,16218
     899    1464    1980    1295    2584    5156    4359
River Rch & RM= TRIB 5 TO IRISH ,Reach-1,13018
    1407    2345    3219    2135    4260    8500    7391
River Rch & RM= TRIB 5 TO IRISH ,Reach-1,10188
    1772    2980    4115    2743    5473   10919    9591
River Rch & RM= TRIB 5 TO IRISH ,Reach-1,5922
    2088    3526    4885    3264    6512   12994   11468
Boundary for River Rch & Prof#=TRIB 5 TO IRISH ,Reach-1,1
Up Type=0
Dn Type=3
Dn Slope=0.005
Boundary for River Rch & Prof#=TRIB 5 TO IRISH ,Reach-1,2
Up Type=0
Dn Type=3
Dn Slope=0.005
Boundary for River Rch & Prof#=TRIB 5 TO IRISH ,Reach-1,3
Up Type=0
Dn Type=3
Dn Slope=0.005
Boundary for River Rch & Prof#=TRIB 5 TO IRISH ,Reach-1,4
Up Type=0
Dn Type=3
Dn Slope=0.005
Boundary for River Rch & Prof#=TRIB 5 TO IRISH ,Reach-1,5
Up Type=0
Dn Type=3
Dn Slope=0.005
Boundary for River Rch & Prof#=TRIB 5 TO IRISH ,Reach-1,6
Up Type=0
Dn Type=3
Dn Slope=0.005
Boundary for River Rch & Prof#=TRIB 5 TO IRISH ,Reach-1,7
Up Type=0
Dn Type=3
Dn Slope=0.005

--- TRIB 5 TO IRISH CREEK.g01 (geometry) ---

Geom Title=Existing Conditions

River Reach=TRIB 5 TO IRISH ,Reach-1
Reach XY= 30
      2554125.00     13601425.00      2554275.50     13601050.03
      2554121.25     13600526.55      2553682.48     13600081.06
      2553519.89     13599472.71      2552334.19     13597831.95
      2551832.99     13596828.34      2551871.18     13596326.59
      2551125.00     13594775.00      2550227.43     13594180.40
      2550064.94     13594213.90      2549723.28     13593878.34
      2548899.80     13593975.48      2548572.69     13593819.17
      2548411.38     13593311.79      2547923.53     13592928.55
      2547604.43     13592955.77      2547135.11     13592085.39
      2546769.14     13591827.07      2545985.34     13591774.18
      2545804.91     13591655.21      2544714.48     13590015.21
      2544361.35     13589861.74      2543980.37     13589377.70
      2543872.03     13588833.32      2543527.14     13588519.03
      2543717.91     13588125.00      2543526.97     13587869.11
      2543571.54     13587626.50      2543225.00     13587225.00

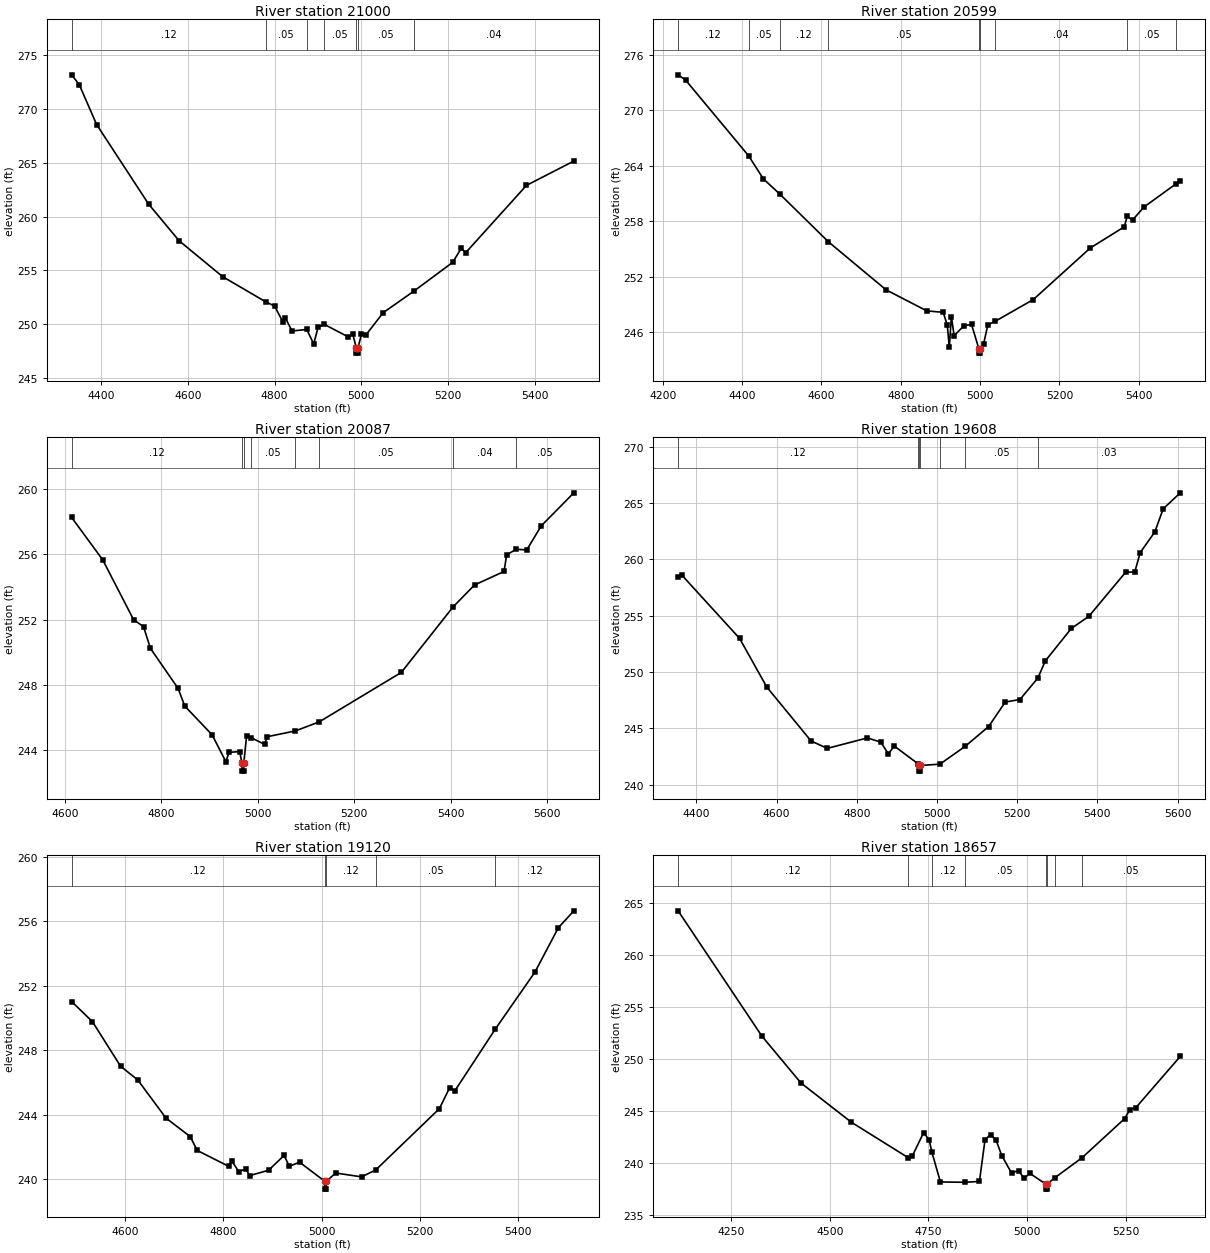
Type RM Length L Ch R = 1,21000,401,401,401
BEGIN DESCRIPTION:
LGII4035
END DESCRIPTION:
XS GIS Cut Line= 2
      2554842.45     13601305.40      2553685.91     13601269.14
#Sta/Elev= 30
  4332.6  273.18  4350.1  272.27  4390.1  268.56  4510.1  261.15  4580.2  257.75
  4680.2  254.42  4779.3  252.08  4800.3  251.67  4819.7  250.17  4824.7  250.60
  4840.3  249.36  4874.4  249.50  4890.3  248.15  4900.3  249.69  4914.5  249.98
  4970.4  248.80  4980.4  249.05  4988.4  247.80  4988.6  247.30  4992.1  247.30
  4992.4  247.80  5000.4  249.05  5010.4  248.98  5050.4  251.06  5121.7  253.08
  5210.5  255.74  5230.5  257.06  5240.5  256.64  5380.6  262.90  5489.7  265.16
#Mann=7,-1,0
  4332.6    0.12       0  4779.3    0.05       0  4874.4    0.12       0
  4914.5    0.05       0  4988.4    0.05       0  4992.4    0.05       0
  5121.7    0.04       0
Bank Sta=4988.4,4992.4
Exp/Cntr=0.3,0.1

Type RM Length L Ch R = 1,20599,512,512,512
BEGIN DESCRIPTION:
LGII4034
END DESCRIPTION:
XS GIS Cut Line= 4
      2554963.34     13601095.88      2554286.36     13600926.63
      2554052.64     13600966.93      2553786.71     13601164.36
#Sta/Elev= 30
  4238.5  273.84  4257.4  273.27  4416.1  265.08  4453.3  262.58  4494.4  260.95
  4617.5  255.76  4762.6  250.57  4865.6  248.28  4906.8  248.13  4917.1  246.76
  4922.3  244.34  4927.5  247.67  4934.4  245.61  4959.6  246.68  4978.3  246.82
  4996.6  244.21  4996.8  243.71  5000.3  243.71  5000.6  244.21  5008.7  244.71
  5019.5  246.78  5037.7  247.15  5134.1  249.51  5277.9  255.10  5363.4  257.38
  5370.8  258.52  5384.2  258.12  5413.5  259.54  5493.9  262.04  5504.7  262.32
#Mann=9,-1,0
  4238.5    0.12       0  4416.1    0.05       0  4494.4    0.12       0
  4617.5    0.05       0  4996.6    0.05       0  5000.6    0.05       0
  5037.7    0.04       0  5370.8    0.05       0  5493.9    0.04       0
Bank Sta=4996.6,5000.6
Exp/Cntr=0.3,0.1

Type RM Length L Ch R = 1,20087,479,479,479
BEGIN DESCRIPTION:
TRIB 5 TO IRISH CREEK 40.0
END DESCRIPTION:
XS GIS Cut Line= 3
      2554374.98     13600225.02      2554075.00     13600475.00
      2553824.99     13601075.01
#Sta/Elev= 30
  4614.4  258.27  4678.8  255.67  4742.6  252.01  4763.4  251.57  4777.7  250.24
  4835.0  247.79  4848.7  246.71  4905.3  244.95  4933.9  243.30  4940.5  243.87
  4962.6  243.92  4967.1  243.22  4967.3  242.72  4970.8  242.72  4971.1  243.22
  4976.9  244.88  4986.9  244.76  5014.1  244.36  5019.5  244.83  5077.5  245.18
  5127.4  245.74  5297.4  248.77  5404.5  252.78  5449.1  254.13  5510.3  254.96
  5515.7  255.98  5535.5  256.32  5557.4  256.28  5587.2  257.75  5654.9  259.78
#Mann=8,-1,0
  4614.4    0.12       0  4967.1    0.05       0  4971.1    0.12       0
  4986.9    0.05       0  5077.5    0.12       0  5127.4    0.05       0
  5404.5    0.04       0  5535.5    0.05       0
Bank Sta=4967.1,4971.1
Exp/Cntr=0.3,0.1

Type RM Length L Ch R = 1,19608,488,488,488
BEGIN DESCRIPTION:
TRIB 5 TO IRISH CREEK 39.0
END DESCRIPTION:
XS GIS Cut Line= 3
      2554375.00     13600125.00      2553875.00     13600075.00
      2553275.00     13600525.00
#Sta/Elev= 30
  4354.5  258.43  4364.6  258.58  4507.8  252.99  4575.6  248.67  4686.1  243.88
  4726.3  243.22  4826.8  244.15  4860.1  243.77  4878.9  242.73  4893.5  243.43
  4952.2  241.87  4955.0  241.70  4955.2  241.20  4958.7  241.20  4959.0  241.70
  5007.5  241.82  5070.4  243.40  5128.9  245.16  5170.5  247.34  5207.0  247.56
  5251.6  249.46  5270.5  251.00  5335.1  253.87  5378.9  254.95  5470.5  258.86
  5493.5  258.90  5507.0  260.61  5543.5  262.45  5564.3  264.50  5607.0  265.92
#Mann=7,-1,0
  4354.5    0.12       0  4952.2    0.05       0  4955.0    0.05       0
  4959.0    0.05       0  5007.5    0.12       0  5070.4    0.05       0
  5251.6    0.03       0
Bank Sta=4955,4959
Exp/Cntr=0.3,0.1

Type RM Length L Ch R = 1,19120,463,463,463
BEGIN DESCRIPTION:
TRIB 5 TO IRISH CREEK 38.0
END DESCRIPTION:
XS GIS Cut Line= 3
      2554025.04     13599474.97      2553725.00     13599725.00
      2553125.02     13599924.99
#Sta/Elev= 30
  4491.0  251.01  4533.4  249.76  4590.6  247.00  4625.8  246.14  4683.1  243.78
  4732.5  242.63  4746.8  241.77  4810.6  240.79  4817.1  241.13  4831.4  240.45
  4845.8  240.63  4853.6  240.21  4892.1  240.54  4923.7  241.46  4934.3  240.79
  4955.3  241.04  5006.1  239.87  5006.3  239.37  5009.8  239.37  5010.1  239.87
  5029.1  240.37  5081.8  240.13  5110.8  240.57  5240.0  244.36  5261.0  245.66
  5271.6  245.47  5354.2  249.31  5435.0  252.85  5482.4  255.59  5514.0  256.64
#Mann=5,-1,0
  4491.0    0.12       0  5006.1    0.05       0  5010.1    0.12       0
  5110.8    0.05       0  5354.2    0.12       0
Bank Sta=5006.1,5010.1
Exp/Cntr=0.3,0.1

Type RM Length L Ch R = 1,18657,421,421,421
BEGIN DESCRIPTION:
TRIB 5 TO IRISH CREEK 37.0
END DESCRIPTION:
XS GIS Cut Line= 3
      2554075.03     13598774.97      2553475.00     13599375.00
      2553175.03     13599674.97
#Sta/Elev= 30
  4115.8  264.26  4328.0  252.20  4427.0  247.68  4554.3  243.91  4698.9  240.48
  4709.8  240.67  4738.1  242.90  4752.2  242.17  4758.8  241.04  4780.5  238.14
  4842.0  238.11  4879.5  238.19  4893.7  242.22  4907.8  242.71  4921.9  242.14
  4936.1  240.68  4960.8  239.01  4978.5  239.24  4992.7  238.48  5006.8  238.98
  5047.2  237.95  5047.5  237.45  5051.0  237.45  5051.2  237.95  5071.1  238.56
  5139.8  240.48  5247.2  244.23  5261.4  245.12  5275.5  245.28  5388.6  250.24
#Mann=8,-1,0
  4115.8    0.12       0  4698.9    0.05       0  4758.8    0.12       0
  4842.0    0.05       0  5047.2    0.05       0  5051.2    0.05       0
  5071.1    0.12       0  5139.8    0.05       0
Bank Sta=5047.2,5051.2
Exp/Cntr=0.3,0.1

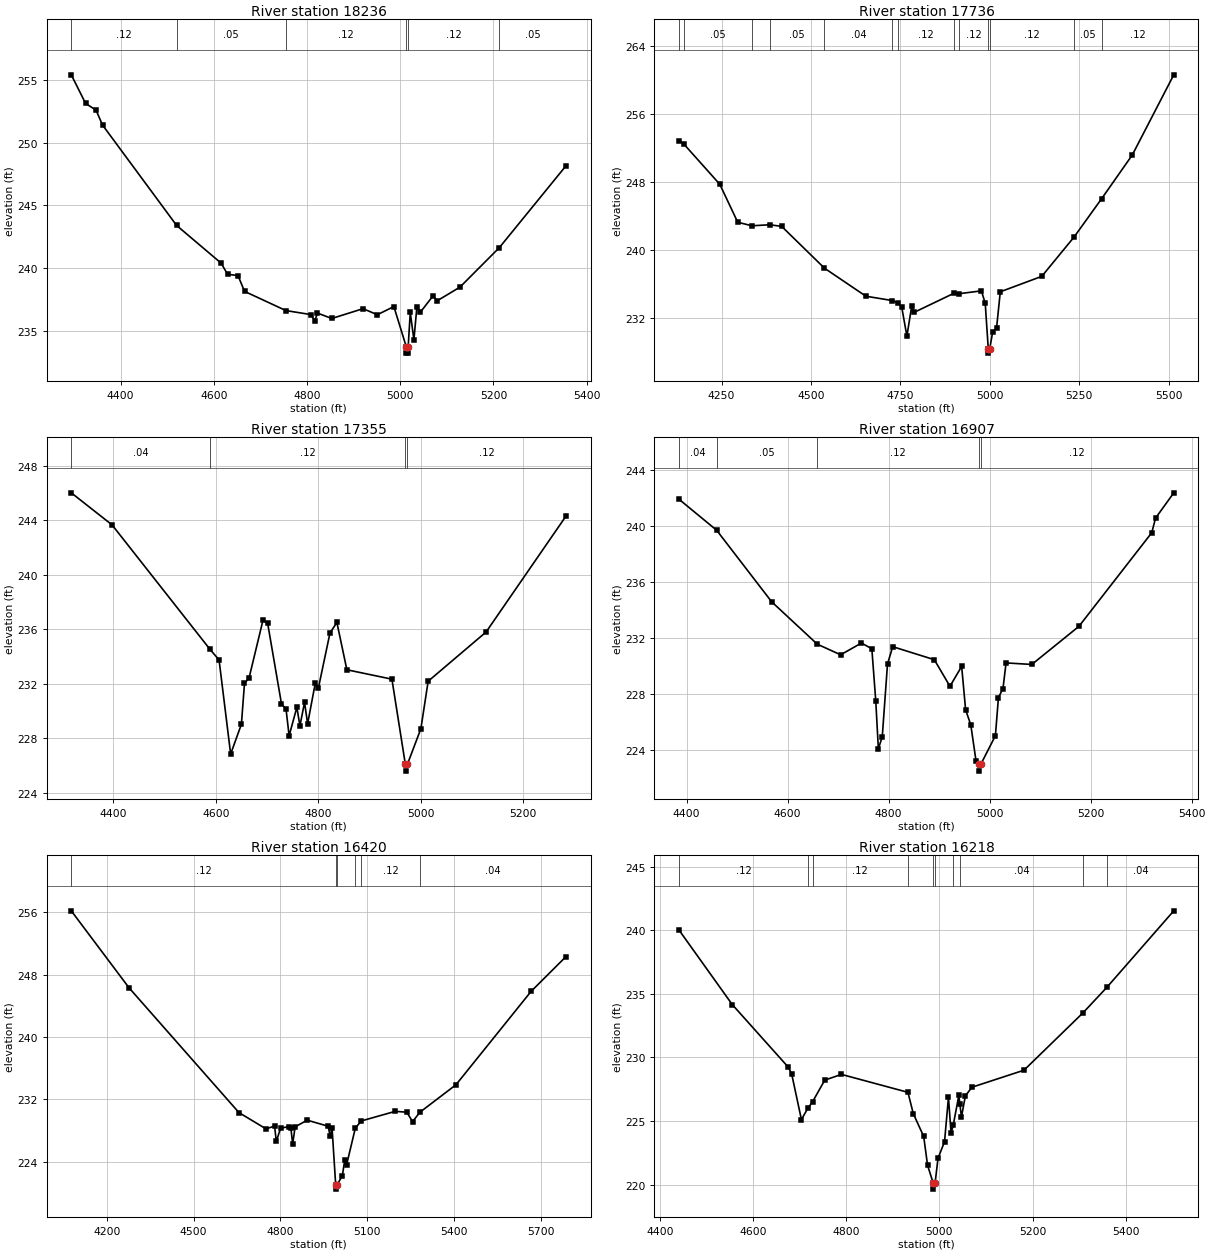
Type RM Length L Ch R = 1,18236,500,500,500
BEGIN DESCRIPTION:
TRIB 5 TO IRISH CREEK 36.0
END DESCRIPTION:
XS GIS Cut Line= 3
      2553875.03     13598724.98      2553275.00     13599025.00
      2553024.98     13599325.03
#Sta/Elev= 30
  4294.0  255.40  4324.8  253.12  4347.1  252.59  4361.1  251.40  4520.1  243.40
  4615.5  240.40  4629.4  239.51  4651.8  239.41  4665.8  238.15  4754.6  236.62
  4808.3  236.30  4816.7  235.80  4822.3  236.42  4853.1  235.99  4920.1  236.77
  4950.9  236.29  4986.3  236.94  5013.0  233.73  5013.2  233.23  5016.7  233.23
  5017.0  233.73  5021.5  236.47  5029.3  234.29  5035.8  236.94  5043.0  236.48
  5070.9  237.82  5078.8  237.39  5128.2  238.49  5212.8  241.64  5355.4  248.14
#Mann=6,-1,0
  4294.0    0.12       0  4520.1    0.05       0  4754.6    0.12       0
  5013.0    0.05       0  5017.0    0.12       0  5212.8    0.05       0
Bank Sta=5013,5017
Exp/Cntr=0.3,0.1

Type RM Length L Ch R = 1,17736,381,381,381
BEGIN DESCRIPTION:
TRIB 5 TO IRISH CREEK 35.0
END DESCRIPTION:
XS GIS Cut Line= 3
      2553675.04     13598174.97      2553075.00     13598625.00
      2552475.00     13598825.00
#Sta/Elev= 30
  4131.4  252.88  4145.1  252.44  4245.0  247.73  4295.0  243.27  4334.4  242.85
  4384.7  242.97  4417.9  242.78  4537.5  237.86  4653.3  234.56  4726.9  234.05
  4742.5  233.77  4753.3  233.32  4767.9  229.86  4781.4  233.39  4788.7  232.67
  4899.1  234.90  4912.8  234.85  4976.3  235.19  4986.9  233.71  4995.4  228.36
  4995.6  227.86  4999.4  228.36  5007.9  230.40  5018.5  230.80  5029.0  235.08
  5145.0  236.90  5235.1  241.52  5312.1  246.03  5398.0  251.19  5513.9  260.62
#Mann=13,-1,0
  4131.4    0.04       0  4145.1    0.05       0  4334.4    0.04       0
  4384.7    0.05       0  4537.5    0.04       0  4726.9    0.05       0
  4742.5    0.12       0  4899.1    0.05       0  4912.8    0.12       0
  4995.4    0.05       0  4999.4    0.12       0  5235.1    0.05       0
  5312.1    0.12       0
Bank Sta=4995.4,4999.4
Exp/Cntr=0.3,0.1

Type RM Length L Ch R = 1,17355,448,448,448
BEGIN DESCRIPTION:
TRIB 5 TO IRISH CREEK 34.0
END DESCRIPTION:
XS GIS Cut Line= 3
      2553274.98     13597975.01      2552825.00     13598275.00
      2552524.98     13598575.02
#Sta/Elev= 30
  4318.0  246.00  4397.6  243.65  4588.4  234.54  4606.4  233.75  4629.0  226.85
  4650.0  229.04  4656.0  232.03  4665.0  232.44  4692.0  236.65  4701.1  236.46
  4728.1  230.55  4737.1  230.14  4743.1  228.19  4758.2  230.28  4764.2  228.92
  4773.2  230.64  4779.2  229.07  4794.2  232.06  4800.2  231.69  4822.8  235.72
  4836.3  236.50  4855.8  233.03  4943.7  232.34  4969.9  226.10  4970.2  225.60
  4973.9  226.10  5000.2  228.71  5014.4  232.19  5127.5  235.80  5283.1  244.28
#Mann=4,-1,0
  4318.0    0.04       0  4588.4    0.12       0  4969.9    0.05       0
  4973.9    0.12       0
Bank Sta=4969.9,4973.9
Exp/Cntr=0.3,0.1

Type RM Length L Ch R = 1,16907,487,487,487
BEGIN DESCRIPTION:
TRIB 5 TO IRISH CREEK 33.0
END DESCRIPTION:
XS GIS Cut Line= 3
      2553075.04     13597874.99      2552475.00     13598025.00
      2552274.98     13598325.03
#Sta/Elev= 30
  4385.5  241.88  4459.6  239.68  4568.5  234.57  4658.8  231.54  4705.1  230.78
  4746.3  231.62  4766.9  231.21  4774.7  227.46  4779.8  224.07  4787.5  224.92
  4797.9  230.12  4808.2  231.36  4890.6  230.43  4921.5  228.53  4944.7  229.95
  4952.5  226.86  4962.8  225.77  4973.1  223.21  4978.8  222.97  4979.1  222.47
  4982.8  222.97  5011.5  225.00  5017.5  227.72  5026.5  228.37  5032.6  230.20
  5083.6  230.09  5176.8  232.81  5321.0  239.50  5328.5  240.54  5364.6  242.35
#Mann=5,-1,0
  4385.5    0.04       0  4459.6    0.05       0  4658.8    0.12       0
  4978.8    0.05       0  4982.8    0.12       0
Bank Sta=4978.8,4982.8
Exp/Cntr=0.3,0.1

Type RM Length L Ch R = 1,16420,202,202,202
BEGIN DESCRIPTION:
TRIB 5 TO IRISH CREEK 32.0
END DESCRIPTION:
XS GIS Cut Line= 3
      2553025.04     13597124.97      2552125.00     13597775.00
      2551525.03     13597775.00
#Sta/Elev= 30
  4077.0  256.19  4277.0  246.30  4656.8  230.30  4750.5  228.21  4779.9  228.57
  4786.1  226.60  4800.8  228.31  4829.5  228.49  4836.4  228.32  4842.5  226.27
  4851.1  228.47  4892.8  229.33  4965.2  228.55  4972.5  227.24  4978.7  228.36
  4991.4  220.98  4991.7  220.48  4995.4  220.98  5014.5  222.22  5022.8  224.27
  5029.0  223.59  5059.2  228.31  5080.0  229.23  5197.2  230.46  5237.2  230.35
  5257.2  229.14  5282.3  230.34  5407.2  233.87  5667.2  245.86  5787.2  250.30
#Mann=6,-1,0
  4077.0    0.12       0  4991.4    0.05       0  4995.4    0.12       0
  5059.2    0.04       0  5080.0    0.12       0  5282.3    0.04       0
Bank Sta=4991.4,4995.4
Exp/Cntr=0.3,0.1

Type RM Length L Ch R = 1,16218,382,382,382
BEGIN DESCRIPTION:
TRIB 5 TO IRISH CREEK 31.0
END DESCRIPTION:
XS GIS Cut Line= 3
      2552624.99     13597175.01      2552325.00     13597425.00
      2551725.01     13597724.99
#Sta/Elev= 30
  4441.7  239.99  4555.6  234.15  4676.0  229.22  4683.1  228.69  4704.0  225.11
  4717.5  225.98  4728.1  226.52  4754.1  228.21  4789.9  228.66  4932.6  227.25
  4944.0  225.58  4966.4  223.78  4974.7  221.51  4986.6  220.14  4986.8  219.64
  4990.9  220.14  4997.1  222.06  5011.1  223.37  5019.5  226.85  5025.1  224.06
  5029.8  224.68  5041.8  227.01  5044.1  226.31  5047.4  225.31  5055.8  226.97
  5069.8  227.65  5181.6  228.99  5308.5  233.51  5359.8  235.52  5503.0  241.52
#Mann=10,-1,0
  4441.7    0.12       0  4717.5    0.04       0  4728.1    0.12       0
  4932.6    0.04       0  4986.6    0.04       0  4990.9    0.04       0
  5029.8    0.05       0  5044.1    0.04       0  5308.5    0.05       0
  5359.8    0.04       0
Bank Sta=4986.6,4990.9
Exp/Cntr=0.3,0.1

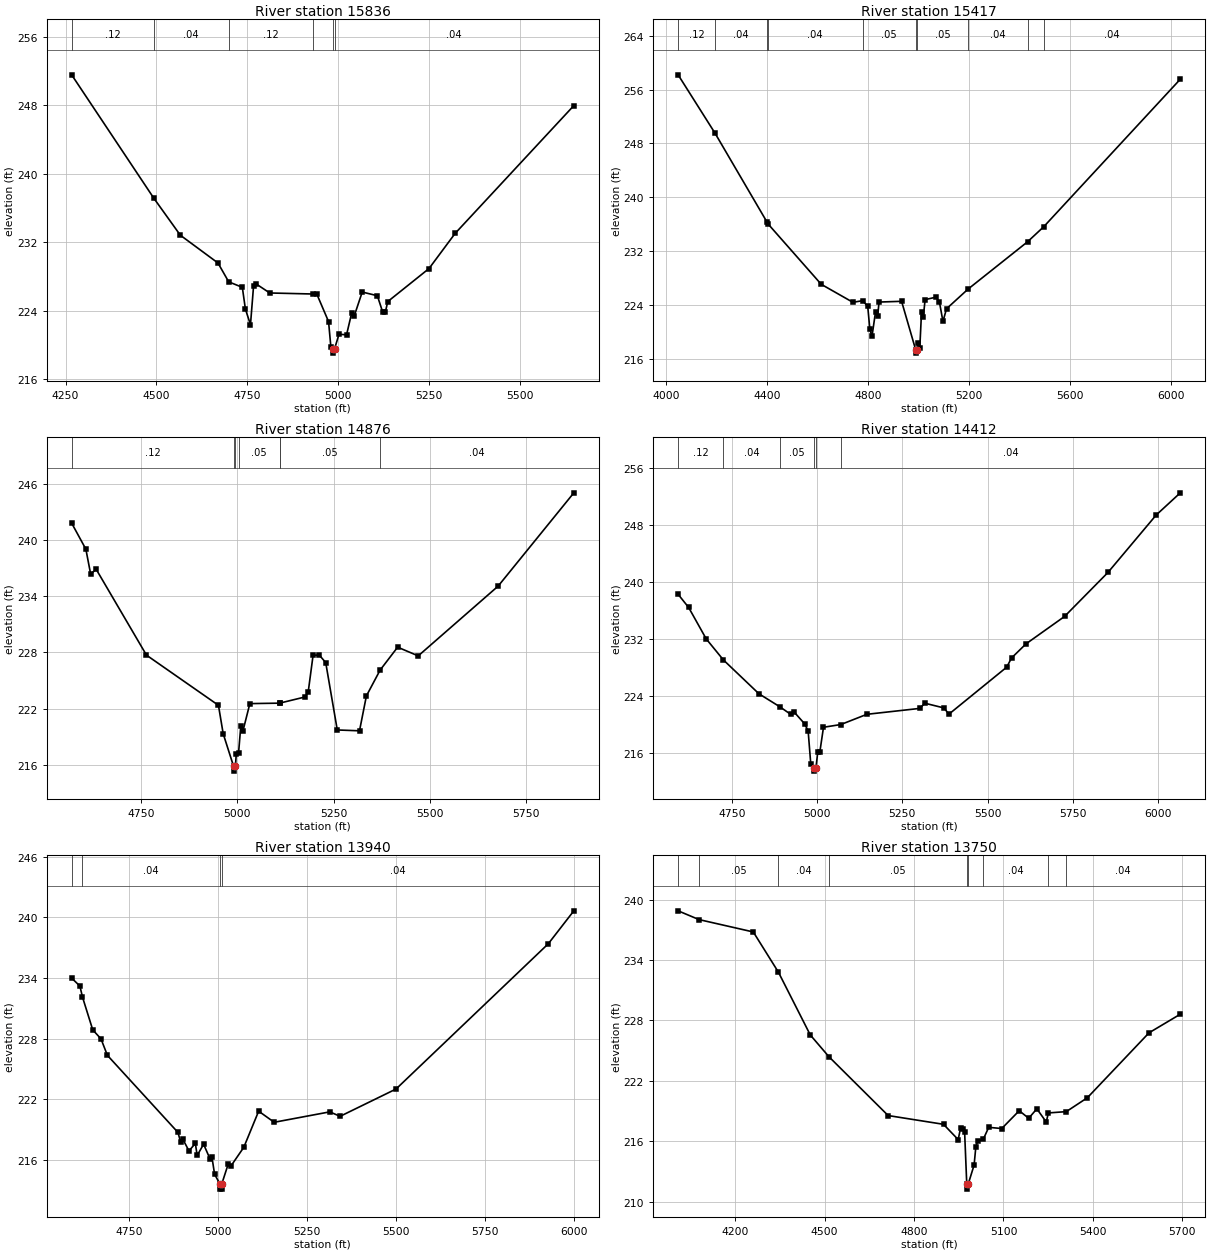
Type RM Length L Ch R = 1,15836,419,419,419
BEGIN DESCRIPTION:
TRIB 5 TO IRISH CREEK 30.0
END DESCRIPTION:
XS GIS Cut Line= 3
      2552674.97     13596825.01      2552075.00     13597125.00
      2551525.02     13597574.99
#Sta/Elev= 30
  4266.8  251.54  4492.5  237.16  4565.8  232.82  4669.3  229.58  4698.8  227.38
  4736.3  226.74  4744.7  224.21  4758.7  222.38  4767.1  226.84  4772.7  227.18
  4811.8  226.08  4930.2  225.96  4940.8  225.99  4973.5  222.74  4979.9  219.76
  4985.6  219.56  4985.9  219.06  4990.0  219.56  5002.2  221.26  5023.0  221.20
  5037.4  223.80  5043.8  223.36  5066.1  226.19  5107.7  225.76  5122.1  223.89
  5130.0  223.91  5136.4  225.08  5249.8  228.93  5321.6  233.03  5648.2  247.95
#Mann=6,-1,0
  4266.8    0.12       0  4492.5    0.04       0  4698.8    0.12       0
  4930.2    0.04       0  4985.6    0.04       0  4990.0    0.04       0
Bank Sta=4985.6,4990
Exp/Cntr=0.3,0.1

Type RM Length L Ch R = 1,15417,541,541,541
BEGIN DESCRIPTION:
TRIB 5 TO IRISH CREEK 29.0
END DESCRIPTION:
XS GIS Cut Line= 3
      2552674.97     13596375.01      2551875.00     13596775.00
      2551124.99     13597575.01
#Sta/Elev= 30
  4047.2  258.21  4193.8  249.51  4399.6  236.30  4402.4  236.08  4614.6  227.04
  4740.3  224.36  4779.1  224.61  4799.0  223.74  4807.4  220.33  4815.8  219.29
  4829.8  222.91  4838.2  222.27  4843.8  224.40  4933.2  224.51  4989.0  217.30
  4989.3  216.80  4993.4  217.30  4998.0  218.31  5005.3  217.55  5012.2  222.88
  5019.5  222.25  5026.4  224.76  5068.8  225.12  5083.0  224.45  5097.2  221.51
  5111.3  223.40  5196.8  226.33  5432.7  233.37  5497.1  235.62  6038.2  257.56
#Mann=10,-1,0
  4047.2    0.12       0  4193.8    0.04       0  4399.6    0.05       0
  4402.4    0.04       0  4779.1    0.05       0  4989.0    0.05       0
  4993.4    0.05       0  5196.8    0.04       0  5432.7    0.05       0
  5497.1    0.04       0
Bank Sta=4989,4993.4
Exp/Cntr=0.3,0.1

Type RM Length L Ch R = 1,14876,464,464,464
BEGIN DESCRIPTION:
TRIB 5 TO IRISH CREEK 28.0
END DESCRIPTION:
XS GIS Cut Line= 3
      2552225.03     13596124.98      2551875.00     13596375.00
      2551074.97     13596725.02
#Sta/Elev= 30
  4569.9  241.79  4606.8  239.01  4619.1  236.38  4633.8  236.85  4764.1  227.71
  4950.9  222.36  4963.2  219.33  4990.3  215.84  4990.6  215.34  4995.1  215.84
  4997.0  217.13  5003.0  217.23  5009.0  220.19  5014.5  219.63  5032.4  222.54
  5109.9  222.59  5111.7  222.61  5174.7  223.24  5183.7  223.73  5196.5  227.69
  5212.5  227.72  5229.3  226.92  5259.3  219.73  5317.0  219.64  5334.9  223.36
  5370.4  226.11  5416.0  228.56  5469.4  227.63  5676.8  235.07  5873.3  245.02
#Mann=7,-1,0
  4569.9    0.12       0  4990.3    0.05       0  4995.1    0.12       0
  5003.0    0.05       0  5109.9    0.04       0  5111.7    0.05       0
  5370.4    0.04       0
Bank Sta=4990.3,4995.1
Exp/Cntr=0.3,0.1

Type RM Length L Ch R = 1,14412,472,472,472
BEGIN DESCRIPTION:
TRIB 5 TO IRISH CREEK 27.0
END DESCRIPTION:
XS GIS Cut Line= 3
      2552074.98     13595875.00      2551675.00     13595975.00
      2550924.97     13596725.03
#Sta/Elev= 30
  4592.3  238.24  4623.2  236.39  4674.7  231.98  4725.0  229.03  4829.4  224.27
  4890.2  222.46  4922.1  221.40  4932.4  221.72  4963.4  220.05  4973.7  219.05
  4981.4  214.40  4991.8  213.91  4992.2  213.41  4996.7  213.91  5002.0  216.14
  5008.1  216.14  5018.7  219.57  5069.4  219.95  5146.0  221.39  5301.6  222.22
  5315.7  222.95  5372.3  222.28  5386.4  221.40  5556.1  228.01  5570.3  229.30
  5612.7  231.28  5725.8  235.13  5853.1  241.31  5994.5  249.37  6065.3  252.49
#Mann=6,-1,0
  4592.3    0.12       0  4725.0    0.04       0  4890.2    0.05       0
  4991.8    0.05       0  4996.7    0.05       0  5069.4    0.04       0
Bank Sta=4991.8,4996.7
Exp/Cntr=0.3,0.1

Type RM Length L Ch R = 1,13940,190,190,190
BEGIN DESCRIPTION:
TRIB 5 TO IRISH CREEK 26.0
END DESCRIPTION:
XS GIS Cut Line= 3
      2551875.01     13595675.00      2551475.00     13595575.00
      2550875.01     13596374.99
#Sta/Elev= 30
  4587.6  233.98  4610.8  233.19  4618.1  232.10  4646.9  228.86  4670.1  227.97
  4688.1  226.34  4886.5  218.72  4894.3  217.74  4899.4  218.11  4917.5  216.89
  4935.5  217.63  4940.6  216.44  4958.7  217.55  4976.7  216.10  4981.9  216.32
  4989.6  214.58  5004.8  213.61  5005.1  213.11  5009.3  213.11  5009.7  213.61
  5028.0  215.60  5036.4  215.44  5071.8  217.25  5113.5  220.82  5157.2  219.72
  5313.5  220.75  5342.6  220.31  5499.9  223.01  5928.0  237.37  5999.9  240.63
#Mann=4,-1,0
  4587.6    0.05       0  4618.1    0.04       0  5004.8    0.04       0
  5009.7    0.04       0
Bank Sta=5004.8,5009.7
Exp/Cntr=0.3,0.1

Type RM Length L Ch R = 1,13750,269,269,269
BEGIN DESCRIPTION:
Mapping XS af91ec89
END DESCRIPTION:
XS GIS Cut Line= 3
      2552174.05     13595762.25      2551641.10     13595274.09
      2550803.62     13595748.81
#Sta/Elev= 30
  4008.1  238.89  4078.2  238.02  4260.4  236.79  4344.8  232.79  4451.6  226.56
  4514.4  224.39  4713.0  218.55  4898.8  217.68  4948.0  216.16  4956.2  217.32
  4963.9  217.22  4969.7  216.87  4976.8  211.74  4977.1  211.24  4981.7  211.74
  5001.5  213.64  5007.2  215.42  5013.7  216.04  5032.0  216.18  5050.5  217.38
  5094.2  217.26  5152.9  219.03  5184.7  218.28  5212.0  219.22  5243.6  217.91
  5250.7  218.81  5310.9  218.94  5381.6  220.32  5588.5  226.77  5693.5  228.62
#Mann=9,-1,0
  4008.1    0.04       0  4078.2    0.05       0  4344.8    0.04       0
  4514.4    0.05       0  4976.8    0.05       0  4981.7    0.05       0
  5032.0    0.04       0  5250.7    0.12       0  5310.9    0.04       0
Bank Sta=4976.8,4981.7
Exp/Cntr=0.3,0.1

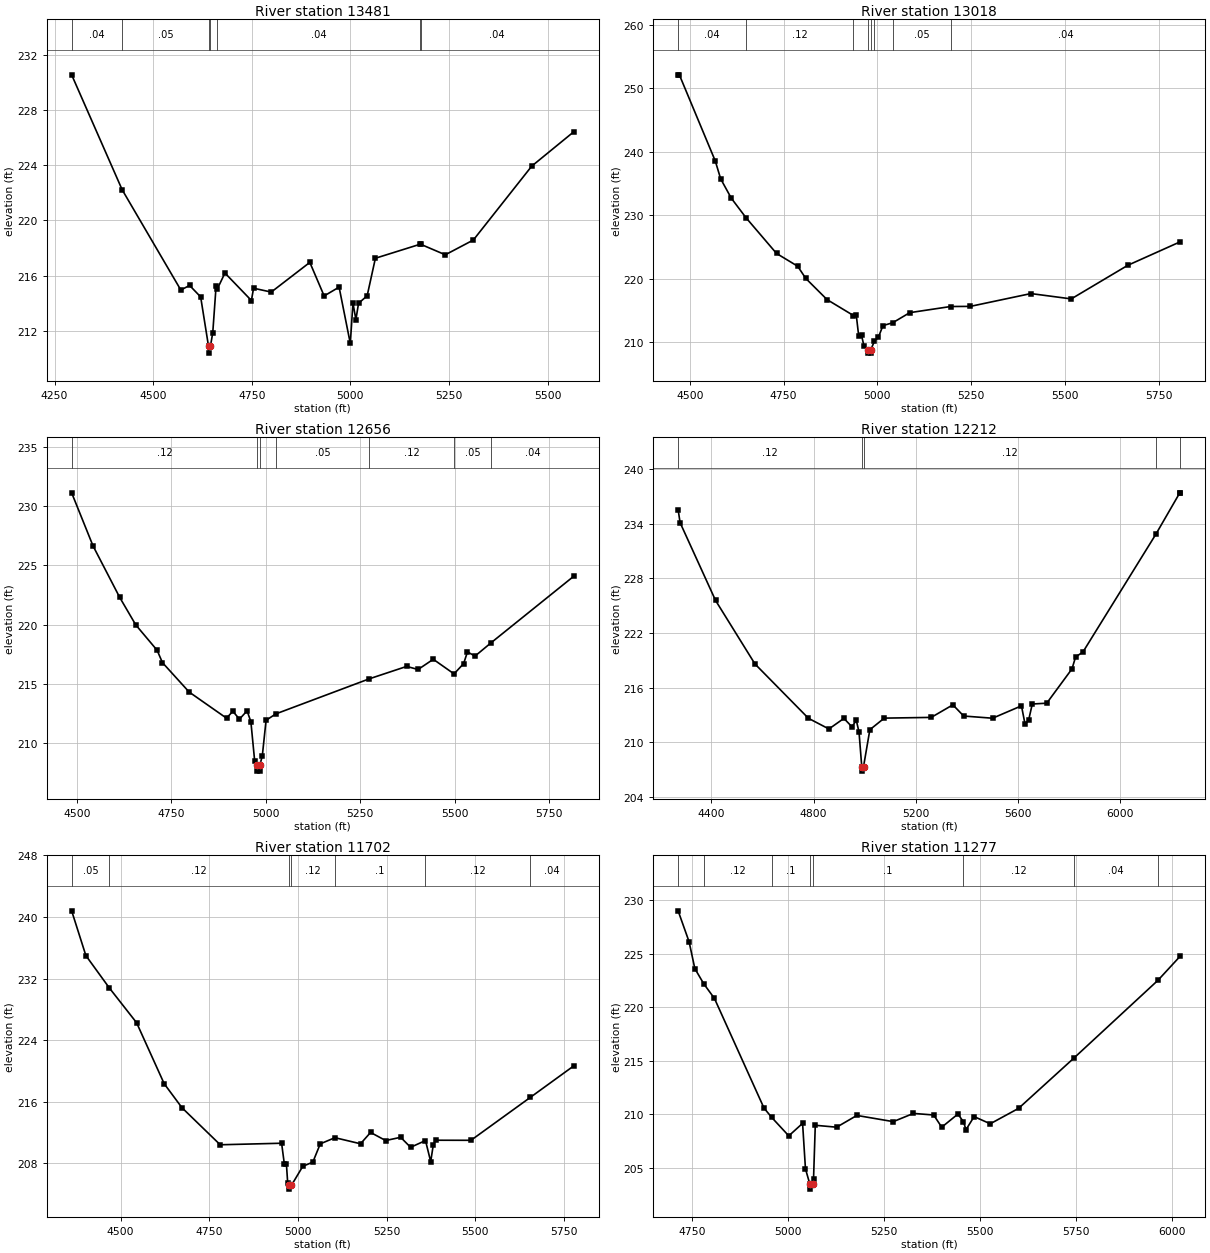
Type RM Length L Ch R = 1,13481,463,463,463
BEGIN DESCRIPTION:
TRIB 5 TO IRISH CREEK 25.0
END DESCRIPTION:
XS GIS Cut Line= 3
      2551574.98     13594575.04      2551275.00     13595175.00
      2550824.97     13595575.03
#Sta/Elev= 30
  4293.4  230.54  4421.4  222.22  4570.1  214.96  4592.4  215.29  4620.4  214.46
  4640.3  210.89  4640.6  210.39  4645.2  210.89  4651.1  211.88  4659.5  215.24
  4662.4  215.02  4681.9  216.19  4749.0  214.20  4754.5  215.09  4799.3  214.81
  4897.1  216.96  4933.4  214.53  4971.3  215.17  4999.7  211.09  5006.4  214.01
  5013.9  212.82  5020.6  214.00  5042.4  214.54  5063.3  217.26  5177.4  218.28
  5178.2  218.27  5240.5  217.51  5311.6  218.58  5459.6  223.93  5566.3  226.42
#Mann=7,-1,0
  4293.4    0.04       0  4421.4    0.05       0  4640.3    0.04       0
  4645.2    0.05       0  4662.4    0.04       0  5177.4    0.12       0
  5178.2    0.04       0
Bank Sta=4640.3,4645.2
Exp/Cntr=0.3,0.1

Type RM Length L Ch R = 1,13018,362,362,362
BEGIN DESCRIPTION:
TRIB 5 TO IRISH CREEK 24.0
END DESCRIPTION:
XS GIS Cut Line= 3
      2551475.00     13594375.01      2551125.00     13594775.00
      2550824.99     13595525.02
#Sta/Elev= 30
  4468.5  252.12  4471.8  252.12  4567.7  238.52  4581.9  235.73  4610.4  232.66
  4649.7  229.58  4730.9  223.96  4787.4  221.94  4808.8  220.03  4865.7  216.68
  4936.1  214.17  4943.5  214.30  4950.2  210.90  4957.8  211.02  4964.4  209.31
  4975.2  208.74  4975.7  208.24  4981.6  208.24  4982.1  208.74  4991.9  210.10
  5002.7  210.76  5014.8  212.58  5040.8  213.03  5086.2  214.62  5195.4  215.59
  5247.7  215.61  5409.3  217.63  5517.0  216.79  5667.8  222.09  5807.8  225.80
#Mann=8,-1,0
  4468.5    0.04       0  4649.7    0.12       0  4936.1    0.05       0
  4975.2    0.05       0  4982.1    0.05       0  4991.9    0.12       0
  5040.8    0.05       0  5195.4    0.04       0
Bank Sta=4975.2,4982.1
Exp/Cntr=0.3,0.1

Type RM Length L Ch R = 1,12656,444,444,444
BEGIN DESCRIPTION:
TRIB 5 TO IRISH CREEK 23.0
END DESCRIPTION:
XS GIS Cut Line= 3
      2551125.02     13594224.98      2550825.00     13594525.00
      2550725.00     13595424.97
#Sta/Elev= 30
  4486.1  231.11  4542.7  226.64  4613.4  222.30  4655.8  219.99  4712.4  217.85
  4726.5  216.81  4797.3  214.33  4896.2  212.13  4912.9  212.71  4930.5  212.05
  4950.6  212.75  4960.7  211.83  4970.8  208.50  4977.4  208.17  4977.9  207.67
  4983.8  207.67  4984.3  208.17  4990.9  208.94  5000.9  211.95  5026.7  212.49
  5274.7  215.45  5373.2  216.49  5403.4  216.23  5443.7  217.09  5498.7  215.86
  5524.1  216.73  5534.2  217.71  5554.3  217.36  5597.5  218.50  5815.9  224.09
#Mann=7,-1,0
  4486.1    0.12       0  4977.4    0.05       0  4984.3    0.12       0
  5026.7    0.05       0  5274.7    0.12       0  5498.7    0.05       0
  5597.5    0.04       0
Bank Sta=4977.4,4984.3
Exp/Cntr=0.3,0.1

Type RM Length L Ch R = 1,12212,510,510,510
BEGIN DESCRIPTION:
TRIB 5 TO IRISH CREEK 22.0
END DESCRIPTION:
XS GIS Cut Line= 3
      2551074.97     13594025.02      2550475.00     13594375.00
      2549574.98     13595275.02
#Sta/Elev= 30
  4269.6  235.53  4277.4  234.10  4416.3  225.56  4570.6  218.59  4780.2  212.62
  4860.4  211.45  4919.1  212.61  4950.5  211.69  4967.7  212.39  4978.3  211.11
  4989.0  207.32  4989.5  206.82  4996.0  207.32  5020.8  211.37  5077.3  212.64
  5261.2  212.72  5346.0  214.10  5388.4  212.87  5501.6  212.63  5614.7  213.99
  5628.9  211.96  5643.0  212.45  5657.1  214.19  5713.7  214.28  5812.7  218.05
  5826.9  219.37  5855.1  219.88  6141.4  232.84  6235.0  237.38  6237.0  237.38
#Mann=5,-1,0
  4269.6    0.12       0  4989.0    0.05       0  4996.0    0.12       0
  6141.4    0.05       0  6235.0    0.12       0
Bank Sta=4989,4996
Exp/Cntr=0.3,0.1

Type RM Length L Ch R = 1,11702,425,425,425
BEGIN DESCRIPTION:
TRIB 5 TO IRISH CREEK 21.0
END DESCRIPTION:
XS GIS Cut Line= 3
      2550025.00     13593575.00      2550075.00     13594175.00
      2549525.02     13594774.98
#Sta/Elev= 30
  4361.9  240.79  4402.0  234.98  4468.4  230.76  4545.0  226.26  4622.8  218.34
  4673.0  215.22  4780.8  210.41  4953.9  210.61  4961.5  207.95  4967.4  207.95
  4971.1  205.43  4974.0  205.15  4974.5  204.65  4981.7  205.15  5013.6  207.61
  5042.0  208.16  5062.9  210.53  5104.3  211.33  5176.4  210.54  5204.8  212.01
  5247.3  210.96  5289.6  211.38  5317.6  210.08  5359.6  210.96  5374.3  208.22
  5381.7  210.43  5388.5  211.00  5487.8  210.99  5655.1  216.56  5777.9  220.66
#Mann=7,-1,0
  4361.9    0.05       0  4468.4    0.12       0  4974.0    0.05       0
  4981.7    0.12       0  5104.3     0.1       0  5359.6    0.12       0
  5655.1    0.04       0
Bank Sta=4974,4981.7
Exp/Cntr=0.3,0.1

Type RM Length L Ch R = 1,11277,555,555,555
BEGIN DESCRIPTION:
TRIB 5 TO IRISH CREEK 20.0
END DESCRIPTION:
XS GIS Cut Line= 3
      2549925.01     13593674.98      2549725.00     13593975.00
      2549424.99     13594875.04
#Sta/Elev= 30
  4712.8  229.03  4741.4  226.14  4756.4  223.63  4779.6  222.21  4807.5  220.84
  4936.7  210.59  4956.9  209.71  5001.3  207.99  5037.3  209.16  5044.8  204.91
  5056.0  203.51  5056.5  203.01  5063.8  203.51  5065.9  204.00  5070.4  208.98
  5126.1  208.80  5178.8  209.90  5273.7  209.32  5326.4  210.09  5379.1  209.94
  5400.1  208.80  5442.3  210.03  5456.8  209.30  5463.4  208.57  5484.5  209.79
  5526.6  209.12  5600.4  210.56  5744.9  215.27  5963.7  222.53  6022.1  224.80
#Mann=8,-1,0
  4712.8    0.05       0  4779.6    0.12       0  4956.9     0.1       0
  5056.0    0.05       0  5063.8     0.1       0  5456.8    0.12       0
  5744.9    0.04       0  5963.7    0.05       0
Bank Sta=5056,5063.8
Exp/Cntr=0.3,0.1

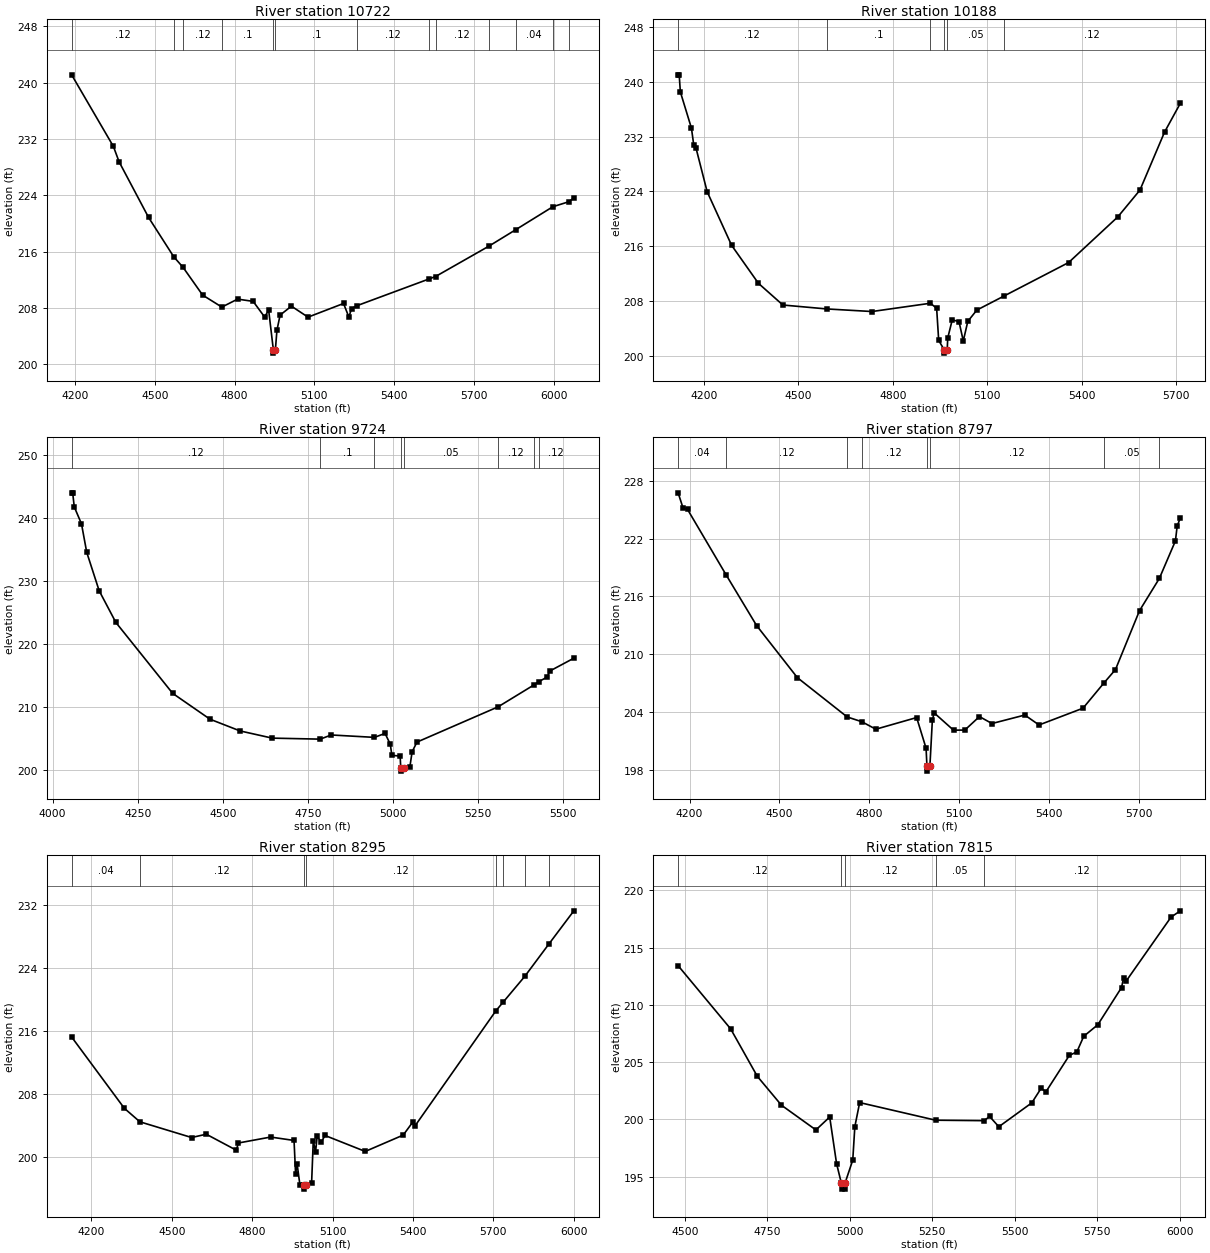
Type RM Length L Ch R = 1,10722,534,534,534
BEGIN DESCRIPTION:
TRIB 5 TO IRISH CREEK 19.0
END DESCRIPTION:
XS GIS Cut Line= 3
      2549688.53     13593231.95      2549275.00     13593925.00
      2549043.98     13594981.49
#Sta/Elev= 30
  4187.6  241.09  4344.6  230.92  4366.0  228.74  4477.0  220.83  4571.4  215.26
  4606.8  213.74  4680.2  209.81  4752.4  208.11  4811.7  209.24  4870.1  208.92
  4913.1  206.71  4928.5  207.66  4946.0  202.07  4946.5  201.57  4953.8  202.07
  4959.6  204.81  4971.4  206.97  5014.0  208.24  5076.5  206.68  5210.0  208.62
  5230.1  206.70  5240.3  207.90  5262.2  208.33  5532.1  212.11  5556.1  212.45
  5756.6  216.76  5856.9  219.08  5997.2  222.36  6057.4  223.07  6076.1  223.61
#Mann=13,-1,0
  4187.6    0.12       0  4571.4     0.1       0  4606.8    0.12       0
  4752.4     0.1       0  4946.0    0.05       0  4953.8     0.1       0
  5262.2    0.12       0  5532.1    0.05       0  5556.1    0.12       0
  5756.6    0.05       0  5856.9    0.04       0  5997.2    0.05       0
  6057.4    0.12       0
Bank Sta=4946,4953.8
Exp/Cntr=0.3,0.1

Type RM Length L Ch R = 1,10188,464,464,464
BEGIN DESCRIPTION:
TRIB 5 TO IRISH CREEK 18.0
END DESCRIPTION:
XS GIS Cut Line= 3
      2549375.02     13593274.97      2548825.00     13593875.00
      2548225.00     13594375.00
#Sta/Elev= 30
  4117.7  241.00  4121.1  241.00  4124.8  238.51  4160.0  233.22  4167.4  230.75
  4174.2  230.37  4209.9  223.95  4287.6  216.12  4372.7  210.58  4450.4  207.41
  4589.1  206.84  4733.4  206.46  4919.1  207.67  4938.8  206.93  4945.3  202.25
  4962.6  200.89  4963.1  200.39  4972.4  200.89  4974.0  202.59  4988.3  205.24
  5009.8  205.00  5023.4  202.17  5037.8  205.03  5066.4  206.67  5153.5  208.74
  5358.0  213.61  5514.2  220.27  5584.5  224.18  5662.6  232.64  5712.7  236.84
#Mann=6,-1,0
  4117.7    0.12       0  4589.1     0.1       0  4919.1    0.05       0
  4962.6    0.05       0  4972.4    0.05       0  5153.5    0.12       0
Bank Sta=4962.6,4972.4
Exp/Cntr=0.3,0.1

Type RM Length L Ch R = 1,9724,927,927,927
BEGIN DESCRIPTION:
TRIB 5 TO IRISH CREEK 17.0
END DESCRIPTION:
XS GIS Cut Line= 3
      2549275.03     13593124.98      2548475.00     13593625.00
      2548125.03     13594024.97
#Sta/Elev= 30
  4055.9  243.98  4058.9  243.98  4063.6  241.75  4084.8  239.06  4100.2  234.55
  4136.7  228.46  4185.7  223.44  4352.5  212.20  4462.2  208.10  4550.6  206.24
  4645.0  205.10  4785.9  204.94  4818.3  205.60  4945.2  205.22  4976.3  205.85
  4991.7  204.14  4996.4  202.37  5020.7  202.26  5022.4  200.37  5022.9  199.87
  5032.2  200.37  5049.2  200.53  5055.8  202.93  5070.0  204.47  5308.3  210.06
  5413.0  213.51  5427.1  214.02  5452.5  214.79  5460.1  215.73  5530.8  217.77
#Mann=8,-1,0
  4055.9    0.12       0  4785.9     0.1       0  4945.2    0.05       0
  5022.4    0.05       0  5032.2    0.05       0  5308.3    0.12       0
  5413.0    0.05       0  5427.1    0.12       0
Bank Sta=5022.4,5032.2
Exp/Cntr=0.3,0.1

Type RM Length L Ch R = 1,8797,502,502,502
BEGIN DESCRIPTION:
TRIB 5 TO IRISH CREEK 15.0
END DESCRIPTION:
XS GIS Cut Line= 3
      2548774.98     13592725.01      2547975.00     13592975.00
      2547725.00     13593775.01
#Sta/Elev= 30
  4161.9  226.74  4178.1  225.19  4193.3  225.02  4323.0  218.18  4423.8  212.97
  4560.0  207.56  4726.3  203.48  4774.9  202.99  4821.9  202.21  4958.1  203.42
  4989.6  200.23  4992.5  198.36  4993.0  197.86  5002.3  198.36  5010.5  203.12
  5016.3  203.91  5081.2  202.11  5118.9  202.12  5167.7  203.52  5209.6  202.80
  5319.1  203.68  5366.7  202.65  5513.4  204.39  5582.5  206.98  5621.8  208.40
  5702.0  214.51  5768.1  217.85  5821.9  221.75  5827.7  223.28  5838.2  224.14
#Mann=8,-1,0
  4161.9    0.04       0  4323.0    0.12       0  4726.3    0.04       0
  4774.9    0.12       0  4992.5    0.05       0  5002.3    0.12       0
  5582.5    0.05       0  5768.1    0.12       0
Bank Sta=4992.5,5002.3
Exp/Cntr=0.3,0.1

Type RM Length L Ch R = 1,8295,480,480,480
BEGIN DESCRIPTION:
TRIB 5 TO IRISH CREEK 14.0
END DESCRIPTION:
XS GIS Cut Line= 3
      2548374.99     13592525.00      2547575.00     13592875.00
      2546975.00     13593675.00
#Sta/Elev= 30
  4126.8  215.24  4323.3  206.22  4381.3  204.51  4574.3  202.52  4628.9  202.94
  4740.8  200.92  4749.0  201.83  4869.0  202.58  4956.3  202.15  4962.2  197.89
  4967.6  199.23  4978.2  196.53  4992.3  196.49  4992.8  195.99  5002.3  196.49
  5021.9  196.82  5028.1  202.14  5036.5  200.66  5042.7  202.69  5057.3  201.92
  5071.9  202.78  5221.9  200.76  5363.5  202.83  5400.0  204.51  5407.3  203.98
  5709.5  218.57  5735.3  219.61  5817.1  222.92  5905.6  226.95  6000.0  231.21
#Mann=8,-1,0
  4126.8    0.04       0  4381.3    0.12       0  4992.3    0.05       0
  5002.3    0.12       0  5709.5    0.05       0  5735.3    0.04       0
  5817.1    0.12       0  5905.6    0.05       0
Bank Sta=4992.3,5002.3
Exp/Cntr=0.3,0.1

Type RM Length L Ch R = 1,7815,458,458,458
BEGIN DESCRIPTION:
TRIB 5 TO IRISH CREEK 13.0
END DESCRIPTION:
XS GIS Cut Line= 3
      2547525.01     13591974.98      2547375.00     13592475.00
      2546775.02     13593274.97
#Sta/Elev= 30
  4479.5  213.43  4638.7  207.91  4719.6  203.76  4792.7  201.24  4897.1  199.08
  4938.9  200.21  4959.8  196.13  4974.4  194.41  4974.9  193.91  4984.6  193.91
  4985.1  194.41  5008.8  196.45  5015.1  199.37  5029.7  201.47  5260.1  199.93
  5407.2  199.89  5423.4  200.26  5451.5  199.36  5551.5  201.45  5579.7  202.72
  5594.2  202.41  5665.1  205.59  5688.0  205.90  5708.8  207.26  5751.5  208.27
  5823.4  211.52  5829.7  212.38  5838.0  212.11  5973.4  217.67  6001.5  218.22
#Mann=5,-1,0
  4479.5    0.12       0  4974.4    0.05       0  4985.1    0.12       0
  5260.1    0.05       0  5407.2    0.12       0
Bank Sta=4974.4,4985.1
Exp/Cntr=0.3,0.1