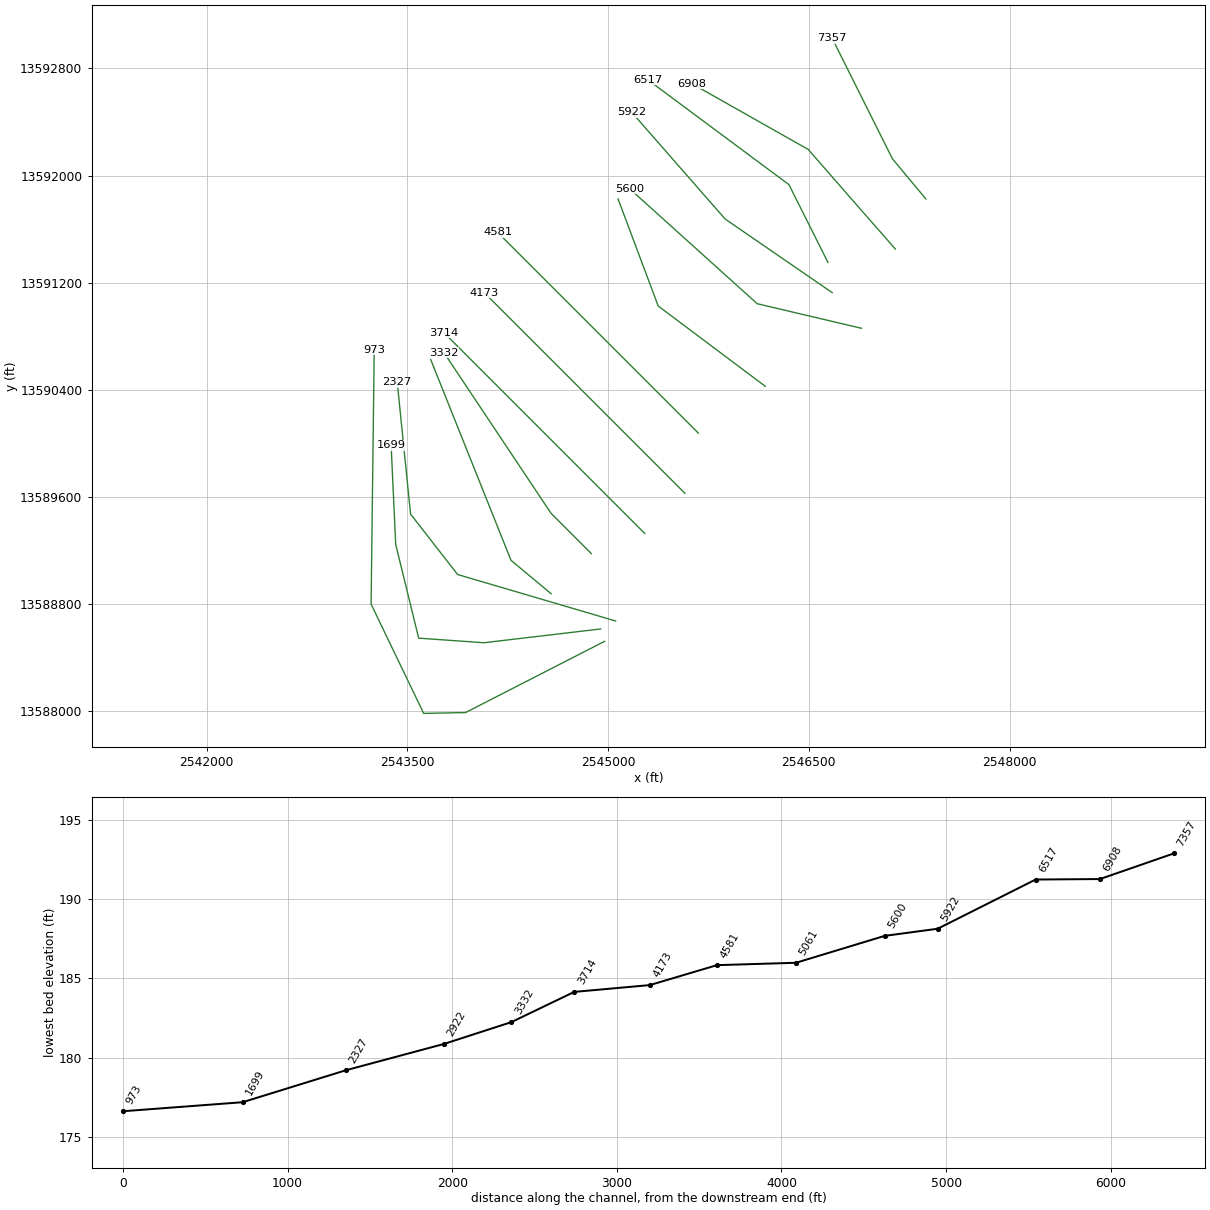
HEC-RAS study TRIB 5 TO IRISH CREEK.prj: TRIB 5 TO IRISH CREEK Base Level Engineering

--- TRIB 5 TO IRISH CREEK.g01 (geometry) --- (continued)

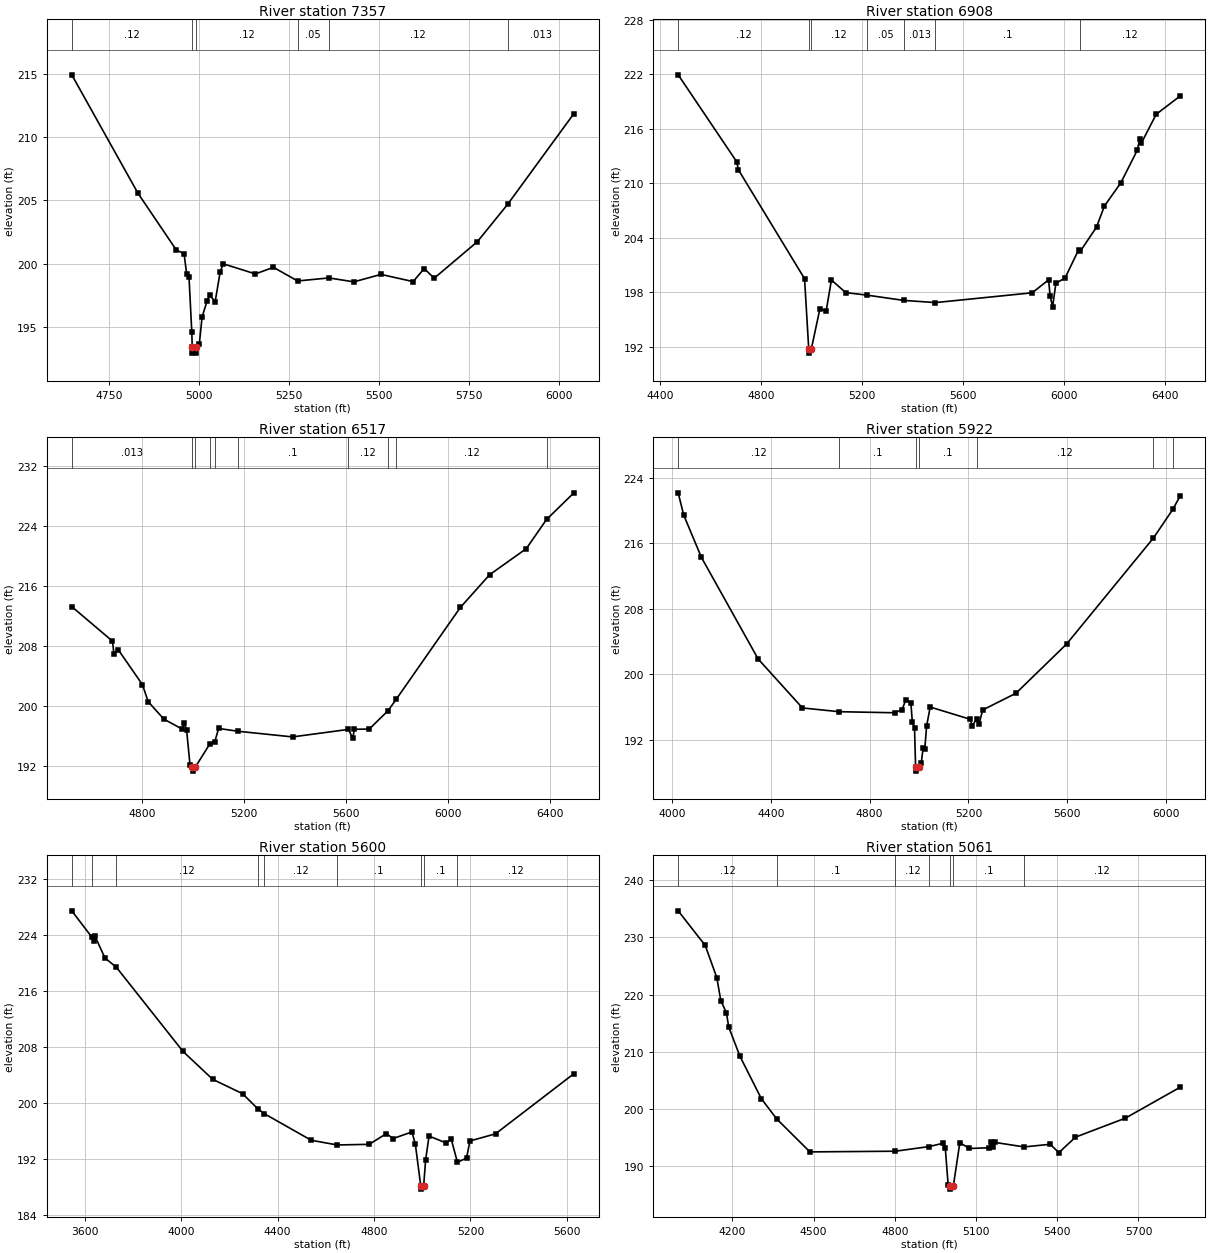
Type RM Length L Ch R = 1,7357,449,449,449
BEGIN DESCRIPTION:
TRIB 5 TO IRISH CREEK 12.0
END DESCRIPTION:
XS GIS Cut Line= 3
      2547374.98     13591825.02      2547125.00     13592125.00
      2546675.01     13593024.98
#Sta/Elev= 30
  4645.8  214.96  4830.0  205.57  4936.7  201.07  4958.2  200.78  4965.3  199.19
  4971.9  198.91  4979.7  194.54  4980.8  193.40  4981.3  192.90  4991.0  192.90
  4991.5  193.40  5000.5  193.60  5008.3  195.77  5022.6  197.07  5029.1  197.49
  5044.7  196.99  5058.6  199.33  5067.0  199.98  5156.5  199.18  5206.8  199.70
  5273.9  198.62  5361.0  198.86  5430.4  198.55  5505.9  199.14  5595.3  198.57
  5626.0  199.60  5654.0  198.84  5774.2  201.74  5858.6  204.71  6042.5  211.89
#Mann=6,-1,0
  4645.8    0.12       0  4980.8    0.05       0  4991.5    0.12       0
  5273.9    0.05       0  5361.0    0.12       0  5858.6   0.013       0
Bank Sta=4980.8,4991.5
Exp/Cntr=0.3,0.1

Type RM Length L Ch R = 1,6908,391,391,391
BEGIN DESCRIPTION:
TRIB 5 TO IRISH CREEK 11.0
END DESCRIPTION:
XS GIS Cut Line= 4
      2547147.05     13591450.51      2546775.00     13591875.00
      2546495.97     13592194.91      2545626.20     13592686.62
#Sta/Elev= 30
  4471.4  221.95  4703.2  212.37  4709.9  211.48  4971.8  199.48  4988.2  191.78
  4988.7  191.28  4999.0  191.78  5032.5  196.17  5057.2  195.91  5078.1  199.33
  5135.1  197.95  5219.1  197.67  5364.6  197.09  5490.2  196.85  5873.2  197.93
  5938.1  199.36  5943.9  197.58  5954.0  196.41  5966.9  198.98  6003.1  199.56
  6056.5  202.64  6063.7  202.51  6127.7  205.17  6159.0  207.49  6224.0  210.05
  6288.9  213.63  6299.1  214.89  6304.8  214.40  6364.0  217.60  6459.5  219.63
#Mann=7,-1,0
  4471.4    0.12       0  4988.2    0.05       0  4999.0    0.12       0
  5219.1    0.05       0  5364.6   0.013       0  5490.2     0.1       0
  6063.7    0.12       0
Bank Sta=4988.2,4999
Exp/Cntr=0.3,0.1

Type RM Length L Ch R = 1,6517,595,595,595
BEGIN DESCRIPTION:
TRIB 5 TO IRISH CREEK 10.0
END DESCRIPTION:
XS GIS Cut Line= 3
      2546643.23     13591351.05      2546351.87     13591931.74
      2545295.26     13592716.93
#Sta/Elev= 30
  4525.7  213.22  4685.1  208.61  4690.7  206.92  4707.4  207.48  4802.4  202.80
  4824.7  200.54  4886.1  198.20  4958.7  196.85  4966.5  197.74  4975.5  196.68
  4988.8  192.02  4998.0  191.75  4998.5  191.25  5008.8  191.75  5066.5  194.90
  5085.9  195.20  5100.7  196.95  5175.2  196.58  5390.0  195.82  5608.7  196.82
  5625.7  195.67  5632.5  196.84  5690.4  196.87  5763.6  199.30  5796.4  200.86
  6047.1  213.11  6161.8  217.48  6305.2  220.96  6384.9  224.87  6491.8  228.42
#Mann=10,-1,0
  4525.7   0.013       0  4998.0    0.03       0  5008.8   0.013       0
  5066.5    0.05       0  5085.9   0.013       0  5175.2     0.1       0
  5608.7    0.12       0  5763.6     0.1       0  5796.4    0.12       0
  6384.9    0.05       0
Bank Sta=4998,5008.8
Exp/Cntr=0.3,0.1

Type RM Length L Ch R = 1,5922,322,322,322
BEGIN DESCRIPTION:
TRIB 5 TO IRISH CREEK 9.0
END DESCRIPTION:
XS GIS Cut Line= 3
      2546675.00     13591125.00      2545875.00     13591675.00
      2545175.03     13592474.97
#Sta/Elev= 30
  4024.5  222.14  4046.8  219.43  4118.5  214.26  4348.6  201.83  4527.8  195.86
  4676.3  195.40  4901.3  195.27  4931.1  195.66  4946.0  196.78  4966.9  196.52
  4973.0  194.12  4981.8  193.42  4986.1  188.64  4986.6  188.14  4998.5  188.64
  5009.1  189.13  5016.7  191.00  5023.3  190.85  5030.9  193.67  5045.2  195.97
  5207.9  194.47  5215.0  193.69  5234.0  194.50  5243.5  193.92  5257.8  195.61
  5392.5  197.65  5597.5  203.66  5949.7  216.63  6028.2  220.13  6058.3  221.79
#Mann=7,-1,0
  4024.5    0.12       0  4676.3     0.1       0  4986.1    0.05       0
  4998.5     0.1       0  5234.0    0.12       0  5949.7    0.05       0
  6028.2    0.03       0
Bank Sta=4986.1,4998.5
Exp/Cntr=0.3,0.1

Type RM Length L Ch R = 1,5600,539,539,539
BEGIN DESCRIPTION:
Mapping XS a46f1ee3
END DESCRIPTION:
XS GIS Cut Line= 3
      2546893.98     13590858.42      2546114.79     13591042.02
      2545161.91     13591900.96
#Sta/Elev= 30
  3545.9  227.45  3629.4  223.68  3636.1  223.17  3641.2  223.89  3683.6  220.71
  3731.1  219.38  4007.2  207.37  4130.5  203.38  4254.7  201.32  4317.1  199.19
  4343.7  198.49  4539.5  194.67  4647.4  194.00  4780.1  194.09  4851.1  195.62
  4879.5  194.92  4957.2  195.86  4971.4  194.13  4993.6  188.19  4994.1  187.69
  5006.0  188.19  5014.0  191.84  5028.2  195.27  5099.2  194.29  5120.2  194.84
  5146.0  191.53  5183.7  192.12  5197.9  194.57  5304.0  195.59  5629.3  204.18
#Mann=9,-1,0
  3545.9    0.12       0  3629.4    0.05       0  3731.1    0.12       0
  4317.1     0.1       0  4343.7    0.12       0  4647.4     0.1       0
  4993.6    0.05       0  5006.0     0.1       0  5146.0    0.12       0
Bank Sta=4993.6,5006
Exp/Cntr=0.3,0.1

Type RM Length L Ch R = 1,5061,480,480,480
BEGIN DESCRIPTION:
TRIB 5 TO IRISH CREEK 7.0
END DESCRIPTION:
XS GIS Cut Line= 3
      2546175.03     13590424.98      2545375.00     13591025.00
      2545075.01     13591824.97
#Sta/Elev= 30
  4000.2  234.65  4100.2  228.59  4142.9  222.96  4157.5  218.97  4178.4  216.81
  4186.7  214.36  4228.4  209.21  4307.5  201.79  4363.8  198.28  4486.7  192.50
  4802.5  192.62  4928.1  193.44  4978.4  194.01  4986.7  193.17  4997.1  186.78
  5003.8  186.49  5004.3  185.99  5016.3  186.49  5040.3  194.10  5075.9  193.10
  5149.8  193.22  5156.0  194.31  5161.3  193.30  5171.1  194.15  5277.9  193.37
  5374.0  193.83  5406.1  192.37  5467.5  195.08  5651.7  198.40  5854.6  203.82
#Mann=7,-1,0
  4000.2    0.12       0  4363.8     0.1       0  4802.5    0.12       0
  4928.1     0.1       0  5003.8    0.05       0  5016.3     0.1       0
  5277.9    0.12       0
Bank Sta=5003.8,5016.3
Exp/Cntr=0.3,0.1

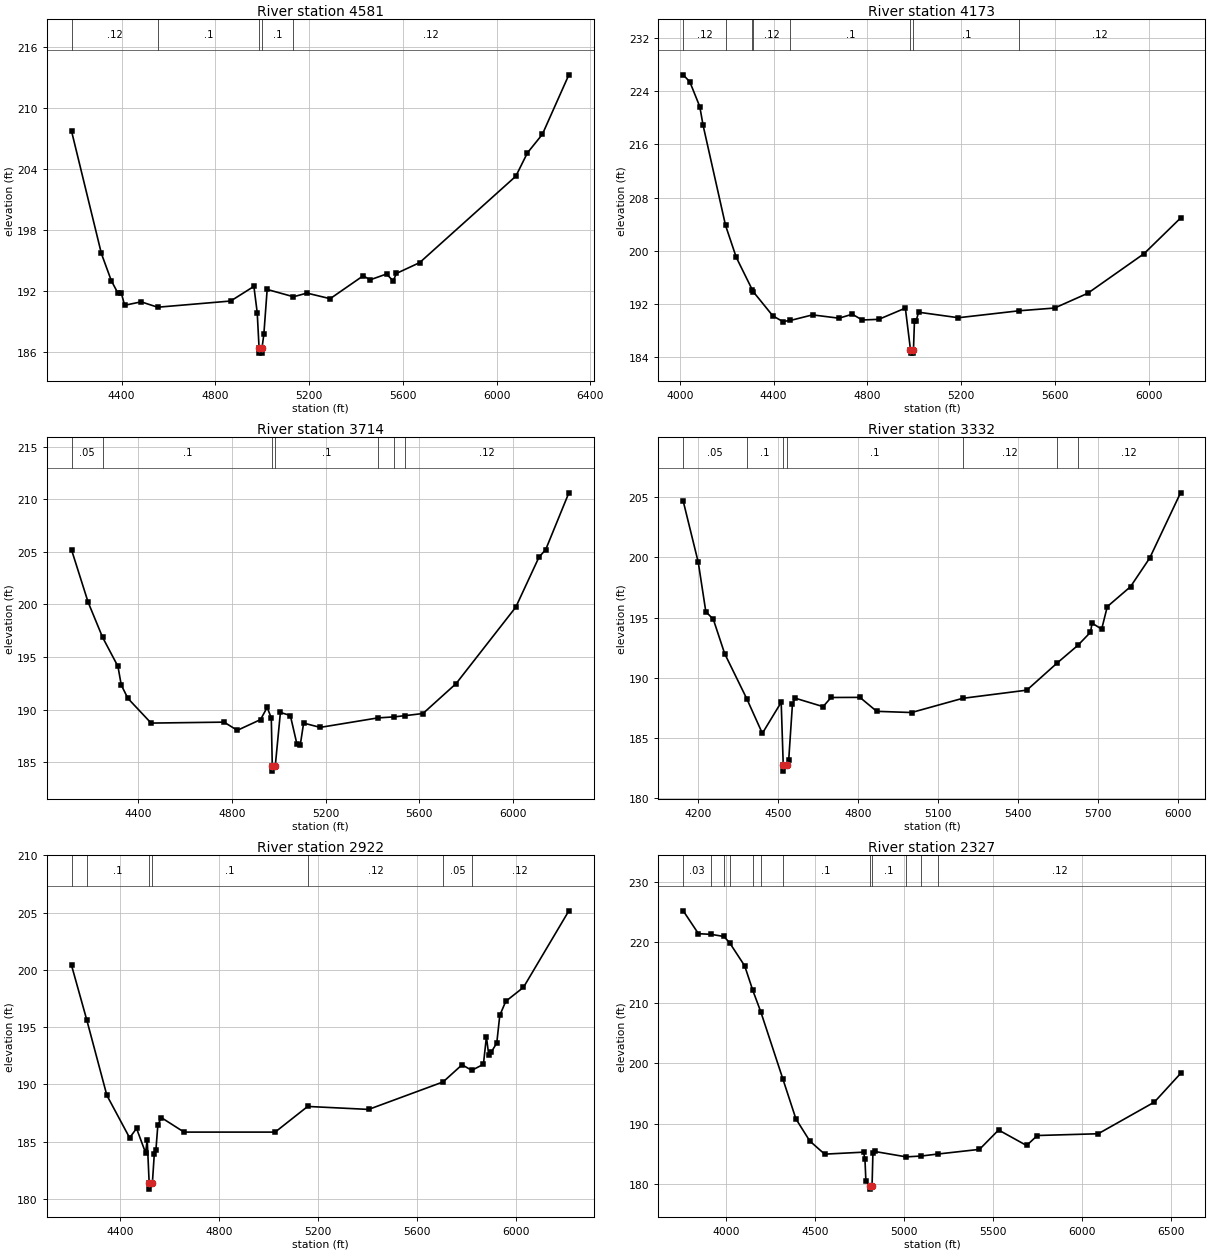
Type RM Length L Ch R = 1,4581,408,408,408
BEGIN DESCRIPTION:
TRIB 5 TO IRISH CREEK 6.0
END DESCRIPTION:
XS GIS Cut Line= 3
      2545675.02     13590074.98      2545075.00     13590675.00
      2544175.03     13591574.97
#Sta/Elev= 30
  4186.8  207.70  4314.1  195.65  4356.5  192.97  4384.8  191.74  4399.0  191.78
  4413.1  190.55  4483.8  190.89  4554.1  190.36  4865.6  190.97  4964.6  192.41
  4978.8  189.83  4986.7  186.34  4987.2  185.84  4998.7  185.84  4999.2  186.34
  5007.1  187.70  5021.2  192.11  5133.5  191.39  5190.9  191.75  5289.9  191.20
  5431.3  193.46  5459.6  193.05  5530.3  193.63  5558.6  192.95  5572.8  193.69
  5671.7  194.75  6081.9  203.26  6131.4  205.56  6195.0  207.38  6308.1  213.24
#Mann=5,-1,0
  4186.8    0.12       0  4554.1     0.1       0  4986.7    0.05       0
  4999.2     0.1       0  5133.5    0.12       0
Bank Sta=4986.7,4999.2
Exp/Cntr=0.3,0.1

Type RM Length L Ch R = 1,4173,459,459,459
BEGIN DESCRIPTION:
TRIB 5 TO IRISH CREEK 5.0
END DESCRIPTION:
XS GIS Cut Line= 3
      2545574.97     13589625.03      2544875.00     13590325.00
      2544074.99     13591125.01
#Sta/Elev= 30
  4014.9  226.49  4043.1  225.43  4085.6  221.70  4099.7  218.88  4195.5  203.81
  4241.1  199.01  4309.7  194.10  4314.5  193.79  4396.7  190.21  4439.1  189.34
  4472.1  189.50  4566.4  190.34  4679.5  189.84  4736.1  190.44  4778.5  189.57
  4849.2  189.67  4962.4  191.36  4984.3  185.08  4984.8  184.58  4996.5  184.58
  4997.0  185.08  5001.3  189.45  5008.3  189.45  5019.0  190.74  5188.7  189.91
  5448.3  190.96  5598.8  191.37  5740.2  193.59  5980.6  199.56  6136.2  204.92
#Mann=8,-1,0
  4014.9    0.12       0  4195.5    0.05       0  4309.7     0.1       0
  4314.5    0.12       0  4472.1     0.1       0  4984.3    0.05       0
  4997.0     0.1       0  5448.3    0.12       0
Bank Sta=4984.3,4997
Exp/Cntr=0.3,0.1

Type RM Length L Ch R = 1,3714,382,382,382
BEGIN DESCRIPTION:
TRIB 5 TO IRISH CREEK 4.0
END DESCRIPTION:
XS GIS Cut Line= 3
      2545274.98     13589325.02      2544675.00     13589925.00
      2543774.99     13590825.01
#Sta/Elev= 30
  4116.3  205.20  4187.0  200.22  4248.7  196.88  4314.3  194.11  4328.4  192.34
  4356.7  191.07  4455.7  188.72  4766.8  188.81  4823.4  188.03  4922.4  189.05
  4950.7  190.21  4968.3  189.21  4972.6  184.65  4973.1  184.15  4985.3  184.65
  5007.2  189.73  5049.6  189.44  5077.9  186.70  5092.1  186.66  5106.2  188.72
  5176.9  188.31  5422.2  189.21  5491.6  189.31  5536.7  189.42  5615.3  189.63
  5756.8  192.48  6011.3  199.75  6110.3  204.51  6138.6  205.21  6237.6  210.62
#Mann=7,-1,0
  4116.3    0.05       0  4248.7     0.1       0  4972.6    0.05       0
  4985.3     0.1       0  5422.2    0.12       0  5491.6     0.1       0
  5536.7    0.12       0
Bank Sta=4972.6,4985.3
Exp/Cntr=0.3,0.1

Type RM Length L Ch R = 1,3332,410,410,410
BEGIN DESCRIPTION:
TRIB 5 TO IRISH CREEK 3.0
END DESCRIPTION:
XS GIS Cut Line= 3
      2544874.99     13589175.01      2544575.00     13589475.00
      2543774.98     13590675.02
#Sta/Elev= 30
  4143.6  204.68  4200.2  199.58  4228.4  195.50  4256.7  194.85  4299.1  192.01
  4382.7  188.23  4440.6  185.38  4511.3  187.96  4519.0  182.74  4519.5  182.24
  4531.8  182.74  4539.6  183.19  4553.7  187.86  4564.3  188.30  4668.5  187.60
  4698.6  188.36  4806.7  188.37  4869.8  187.21  5000.5  187.11  5192.3  188.29
  5433.2  188.97  5547.2  191.23  5624.5  192.69  5672.0  193.78  5678.1  194.54
  5714.1  194.04  5735.1  195.91  5822.3  197.57  5894.4  199.95  6010.1  205.37
#Mann=7,-1,0
  4143.6    0.05       0  4382.7     0.1       0  4519.0    0.05       0
  4531.8     0.1       0  5192.3    0.12       0  5547.2    0.05       0
  5624.5    0.12       0
Bank Sta=4519,4531.8
Exp/Cntr=0.3,0.1

Type RM Length L Ch R = 1,2922,595,595,595
BEGIN DESCRIPTION:
TRIB 5 TO IRISH CREEK 2.0
END DESCRIPTION:
XS GIS Cut Line= 3
      2544575.00     13588875.00      2544275.00     13589125.00
      2543674.99     13590625.03
#Sta/Elev= 30
  4205.7  200.40  4266.7  195.67  4348.2  189.05  4440.0  185.34  4468.0  186.16
  4504.4  184.03  4511.0  185.17  4518.9  181.36  4519.4  180.86  4531.7  181.36
  4539.6  183.95  4546.1  184.28  4553.9  186.47  4568.2  187.10  4659.5  185.84
  5027.0  185.84  5158.2  188.08  5404.0  187.82  5704.5  190.22  5781.0  191.72
  5819.9  191.23  5867.1  191.76  5879.2  194.15  5888.7  192.56  5898.1  192.80
  5921.0  193.62  5933.1  196.03  5957.3  197.26  6028.7  198.48  6211.8  205.16
#Mann=7,-1,0
  4205.7    0.05       0  4266.7     0.1       0  4518.9    0.05       0
  4531.7     0.1       0  5158.2    0.12       0  5704.5    0.05       0
  5819.9    0.12       0
Bank Sta=4518.9,4531.7
Exp/Cntr=0.3,0.1

Type RM Length L Ch R = 1,2327,628,628,628
BEGIN DESCRIPTION:
Mapping XS 4b4e8cd6
END DESCRIPTION:
XS GIS Cut Line= 4
      2545057.01     13588671.32      2543876.43     13589018.55
      2543524.87     13589469.94      2543425.04     13590455.17
#Sta/Elev= 30
  3760.0  225.19  3845.5  221.41  3917.4  221.30  3988.8  220.95  4020.8  219.90
  4105.3  216.09  4150.8  212.04  4195.9  208.48  4318.8  197.48  4393.0  190.80
  4470.9  187.15  4554.3  184.98  4773.2  185.31  4780.7  184.10  4785.9  180.54
  4807.7  179.70  4808.2  179.20  4820.5  179.70  4825.3  185.12  4835.7  185.42
  5012.7  184.53  5096.6  184.67  5192.8  185.01  5423.8  185.77  5531.1  188.97
  5688.4  186.41  5748.7  188.06  6090.5  188.35  6405.9  193.58  6553.0  198.31
#Mann=12,-1,0
  3760.0    0.03       0  3917.4    0.05       0  3988.8    0.03       0
  4020.8    0.05       0  4150.8    0.04       0  4195.9    0.05       0
  4318.8     0.1       0  4807.7    0.05       0  4820.5     0.1       0
  5012.7    0.12       0  5096.6     0.1       0  5192.8    0.12       0
Bank Sta=4807.7,4820.5
Exp/Cntr=0.3,0.1

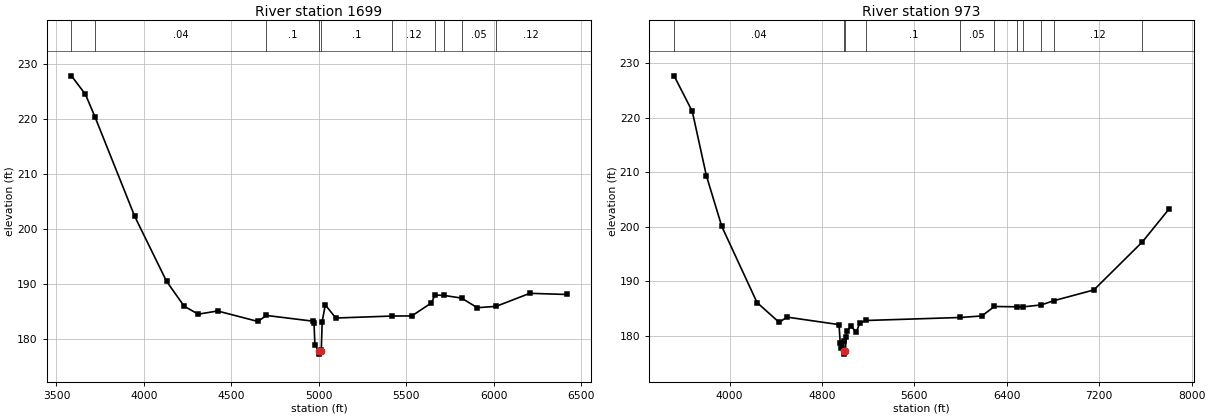
Type RM Length L Ch R = 1,1699,726,726,726
BEGIN DESCRIPTION:
Mapping XS 13caee9e
END DESCRIPTION:
XS GIS Cut Line= 5
      2544944.60     13588611.79      2544072.70     13588508.81
      2543585.28     13588543.13      2543413.65     13589243.37
      2543379.32     13589984.82
#Sta/Elev= 30
  3585.5  227.89  3665.7  224.51  3720.1  220.41  3947.6  202.26  4128.9  190.47
  4229.5  185.92  4310.1  184.46  4420.9  185.04  4651.6  183.13  4699.4  184.23
  4964.3  183.19  4971.9  182.84  4977.0  178.90  4998.9  177.68  4999.4  177.18
  5012.0  177.68  5013.5  177.90  5018.6  183.12  5036.4  186.15  5096.6  183.76
  5419.4  184.12  5530.6  184.14  5642.5  186.50  5663.1  187.95  5716.8  187.87
  5815.4  187.39  5904.9  185.64  6012.4  185.88  6205.3  188.26  6415.3  188.05
#Mann=10,-1,0
  3585.5    0.05       0  3720.1    0.04       0  4699.4     0.1       0
  4998.9    0.05       0  5012.0     0.1       0  5419.4    0.12       0
  5663.1    0.05       0  5716.8    0.12       0  5815.4    0.05       0
  6012.4    0.12       0
Bank Sta=4998.9,5012
Exp/Cntr=0.3,0.1

Type RM Length L Ch R = 1,973,0,0,0
BEGIN DESCRIPTION:
TRIB 5 TO IRISH CREEK 1.0
END DESCRIPTION:
XS GIS Cut Line= 5
      2544974.57     13588519.44      2543935.40     13587987.06
      2543622.46     13587981.05      2543229.73     13588797.19
      2543253.11     13590697.24
#Sta/Elev= 30
  3519.4  227.72  3676.8  221.19  3798.7  209.40  3931.9  200.08  4237.2  186.09
  4429.0  182.44  4496.4  183.41  4947.4  182.03  4957.5  178.65  4967.5  177.74
  4987.5  179.02  4989.7  177.11  4990.2  176.61  5002.8  177.11  5007.8  179.83
  5015.5  180.79  5047.5  181.72  5098.3  180.69  5126.5  182.36  5184.7  182.79
  5996.4  183.34  6183.5  183.62  6292.2  185.36  6489.3  185.30  6536.7  185.28
  6698.5  185.65  6806.5  186.42  7153.6  188.40  7573.7  197.23  7805.9  203.31
#Mann=11,-1,0
  3519.4    0.04       0  4989.7    0.04       0  5002.8    0.04       0
  5184.7     0.1       0  5996.4    0.05       0  6292.2    0.12       0
  6489.3    0.05       0  6536.7    0.12       0  6698.5    0.05       0
  6806.5    0.12       0  7573.7    0.05       0
Bank Sta=4989.7,5002.8
Exp/Cntr=0.3,0.1

Chan Stop Cuts=-1