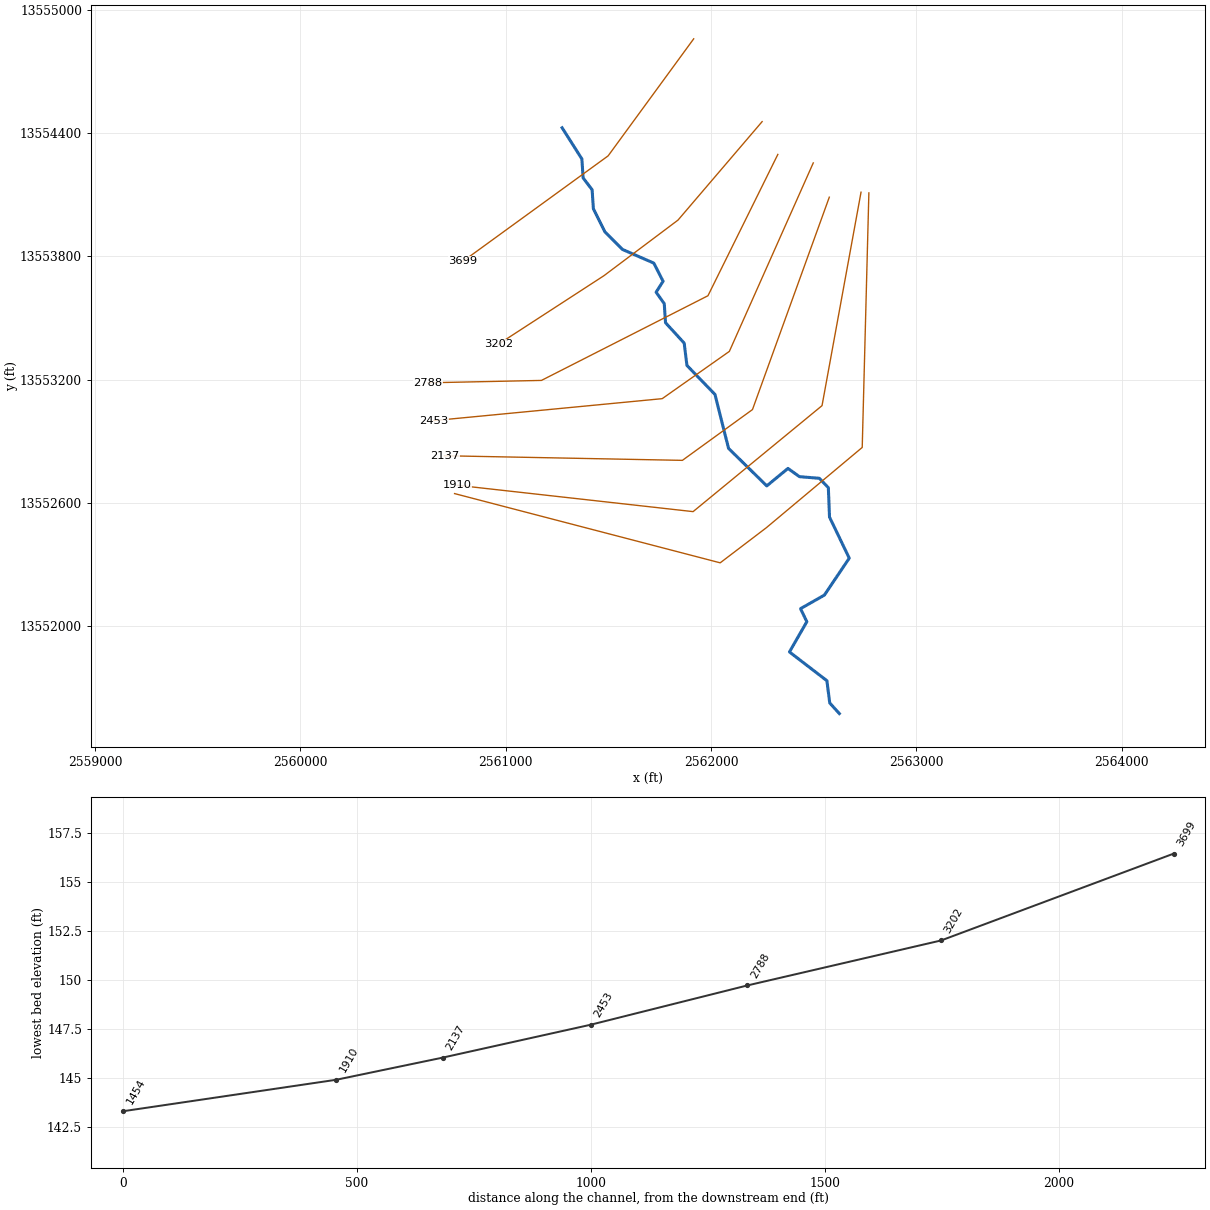
--- TRIB 5 TO PRICE CREEK.prj (project) ---

Proj Title=TRIB 5 TO PRICE CREEK Base Level Engineering
Current Plan=p01
Default Exp/Contr=0.3,0.1
English Units
Geom File=g01
Flow File=f01
Plan File=p01
BEGIN DESCRIPTION:
TRIB 5 TO PRICE CREEK
END DESCRIPTION:

--- TRIB 5 TO PRICE CREEK.p01 (plan) ---

Plan Title=Multiple Run
Short Identifier=Multiple
Geom File=g01
Flow File=f01
Subcritical Flow
K Sum by GR= 0
Std Step Tol= 0.01
Critical Tol= 0.01
Num of Std Step Trials= 20
Max Error Tol= 0.3
Flow Tol Ratio= 0.001
Split Flow NTrial= 30
Split Flow Tol= 0.02
Split Flow Ratio= 0.02
Log Output Level= 0
Friction Slope Method= 1
Unsteady Friction Slope Method= 2
Unsteady Bridges Friction Slope Method= 1
Parabolic Critical Depth
Global Vel Dist=  1 , 1 , 1
Global Log Level= 0
CheckData=True
Encroach Param= -1, 0, 0, 0
BEGIN DESCRIPTION:
Multiple Run
END DESCRIPTION:

--- TRIB 5 TO PRICE CREEK.f01 (steady flow) ---

Flow Title=Multiple
Number of Profiles=7
Profile Names=10-year,25-year,50-year,1pct_min,100-year,1pct_plu,500-year
River Rch & RM= TRIB 5 TO PRICE ,Reach-1,3699
     390     604     791     503    1004    2004    1597
Boundary for River Rch & Prof#=TRIB 5 TO PRICE ,Reach-1,1
Up Type=0
Dn Type=3
Dn Slope=0.005
Boundary for River Rch & Prof#=TRIB 5 TO PRICE ,Reach-1,2
Up Type=0
Dn Type=3
Dn Slope=0.005
Boundary for River Rch & Prof#=TRIB 5 TO PRICE ,Reach-1,3
Up Type=0
Dn Type=3
Dn Slope=0.005
Boundary for River Rch & Prof#=TRIB 5 TO PRICE ,Reach-1,4
Up Type=0
Dn Type=3
Dn Slope=0.005
Boundary for River Rch & Prof#=TRIB 5 TO PRICE ,Reach-1,5
Up Type=0
Dn Type=3
Dn Slope=0.005
Boundary for River Rch & Prof#=TRIB 5 TO PRICE ,Reach-1,6
Up Type=0
Dn Type=3
Dn Slope=0.005
Boundary for River Rch & Prof#=TRIB 5 TO PRICE ,Reach-1,7
Up Type=0
Dn Type=3
Dn Slope=0.005

--- TRIB 5 TO PRICE CREEK.g01 (geometry) ---

Geom Title=Existing Conditions

River Reach=TRIB 5 TO PRICE ,Reach-1
Reach XY= 30
      2561275.00     13554425.00      2561371.18     13554273.42
      2561377.35     13554180.97      2561421.15     13554123.40
      2561427.33     13554030.97      2561483.13     13553918.93
      2561568.93     13553833.13      2561721.54     13553766.52
      2561766.77     13553678.27      2561732.79     13553625.10
      2561772.45     13553569.11      2561778.62     13553476.50
      2561869.46     13553377.42      2561882.86     13553268.83
      2562019.48     13553127.43      2562085.52     13552865.21
      2562271.67     13552682.61      2562374.90     13552767.66
      2562430.90     13552727.57      2562527.71     13552719.60
      2562571.56     13552673.77      2562577.25     13552530.93
      2562673.38     13552331.04      2562552.13     13552151.16
      2562436.11     13552085.32      2562466.74     13552021.78
      2562382.20     13551874.70      2562564.50     13551734.81
      2562578.39     13551626.41      2562625.00     13551575.00

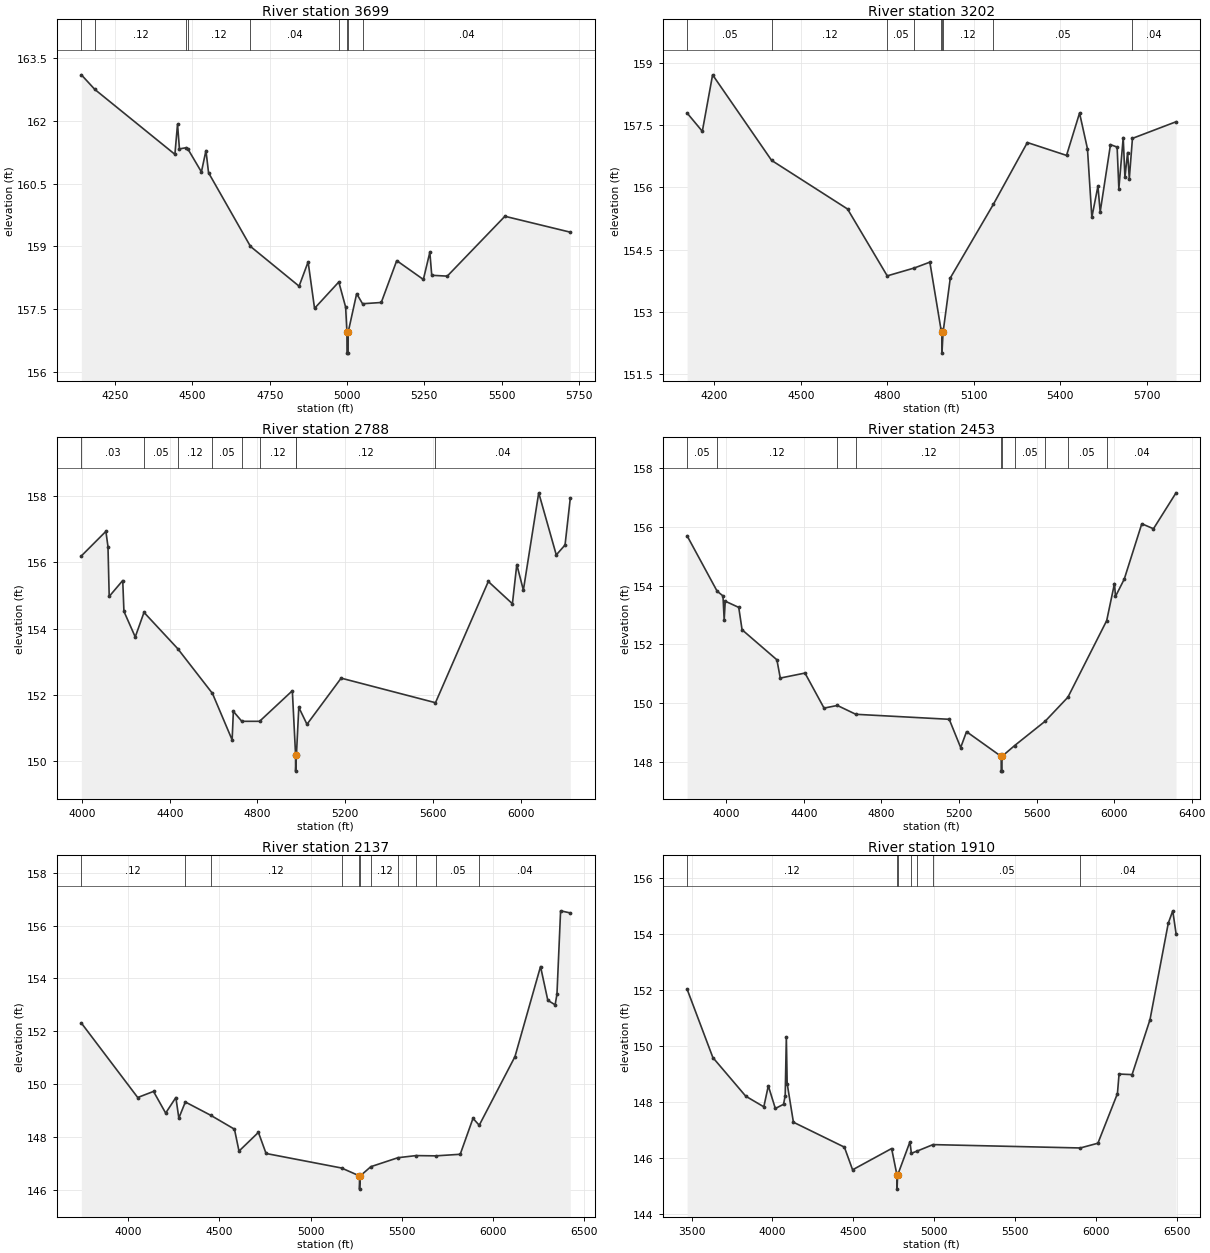
Type RM Length L Ch R = 1,3699,497,497,497
BEGIN DESCRIPTION:
LGII3067
END DESCRIPTION:
XS GIS Cut Line= 3
      2561915.83     13554857.80      2561499.15     13554288.34
      2560790.84     13553774.47
#Sta/Elev= 30
  4141.1  163.10  4184.8  162.75  4443.5  161.20  4452.0  161.92  4458.2  161.33
  4480.9  161.36  4486.1  161.32  4529.2  160.78  4543.9  161.29  4552.3  160.76
  4687.8  159.00  4845.0  158.05  4874.2  158.63  4895.0  157.52  4973.4  158.15
  4995.5  157.55  4999.7  156.95  5000.0  156.45  5003.5  156.45  5003.7  156.95
  5031.1  157.87  5050.2  157.63  5110.7  157.66  5160.7  158.66  5246.8  158.21
  5267.7  158.86  5273.9  158.31  5324.1  158.29  5510.4  159.72  5721.8  159.34
#Mann=9,-1,0
  4141.1    0.05       0  4184.8    0.12       0  4480.9    0.05       0
  4486.1    0.12       0  4687.8    0.04       0  4973.4   0.013       0
  4999.7    0.03       0  5003.7   0.013       0  5050.2    0.04       0
Bank Sta=4999.7,5003.7
Exp/Cntr=0.3,0.1

Type RM Length L Ch R = 1,3202,414,414,414
BEGIN DESCRIPTION:
LGII3066
END DESCRIPTION:
XS GIS Cut Line= 4
      2562249.16     13554455.02      2561839.43     13553975.84
      2561478.32     13553705.01      2560964.42     13553371.67
#Sta/Elev= 30
  4106.3  157.79  4159.0  157.35  4194.6  158.71  4399.1  156.65  4662.2  155.48
  4799.8  153.87  4893.7  154.06  4947.5  154.20  4985.6  152.60  4989.3  152.51
  4989.5  152.01  4993.3  152.51  5018.4  153.82  5167.4  155.59  5285.4  157.08
  5421.2  156.77  5466.3  157.79  5493.7  156.93  5508.9  155.28  5530.0  156.03
  5537.8  155.41  5573.5  157.03  5596.5  156.97  5602.5  155.97  5617.6  157.20
  5623.6  156.24  5632.8  156.84  5638.7  156.21  5649.6  157.18  5800.7  157.58
#Mann=9,-1,0
  4106.3    0.05       0  4399.1    0.12       0  4799.8    0.05       0
  4893.7   0.013       0  4985.6    0.12       0  4989.3    0.05       0
  4993.3    0.12       0  5167.4    0.05       0  5649.6    0.04       0
Bank Sta=4989.3,4993.3
Exp/Cntr=0.3,0.1

Type RM Length L Ch R = 1,2788,335,335,335
BEGIN DESCRIPTION:
LGII3065
END DESCRIPTION:
XS GIS Cut Line= 4
      2562325.55     13554295.31      2561985.26     13553607.79
      2561174.38     13553195.81      2560621.07     13553184.15
#Sta/Elev= 30
  3996.9  156.19  4108.8  156.93  4118.3  156.47  4123.9  154.97  4185.6  155.45
  4191.1  154.52  4242.7  153.75  4282.6  154.49  4436.1  153.40  4594.8  152.05
  4684.6  150.65  4690.2  151.51  4728.7  151.21  4809.8  151.21  4959.2  152.13
  4973.9  150.21  4974.1  149.71  4977.9  150.21  4988.7  151.63  5026.0  151.12
  5181.8  152.51  5612.1  151.77  5853.0  155.42  5963.0  154.75  5983.0  155.93
  6013.0  155.16  6083.0  158.09  6163.1  156.22  6203.1  156.52  6227.0  157.93
#Mann=9,-1,0
  3996.9    0.03       0  4282.6    0.05       0  4436.1    0.12       0
  4594.8    0.05       0  4728.7   0.013       0  4809.8    0.12       0
  4973.9    0.05       0  4977.9    0.12       0  5612.1    0.04       0
Bank Sta=4973.9,4977.9
Exp/Cntr=0.3,0.1

Type RM Length L Ch R = 1,2453,316,316,316
BEGIN DESCRIPTION:
LGII3064
END DESCRIPTION:
XS GIS Cut Line= 4
      2562498.11     13554253.99      2562089.43     13553336.95
      2561762.44     13553107.04      2560649.07     13553000.10
#Sta/Elev= 30
  3797.4  155.69  3952.2  153.81  3982.4  153.65  3988.6  152.84  3994.1  153.47
  4063.7  153.26  4080.9  152.50  4260.5  151.48  4278.0  150.86  4405.4  151.03
  4503.8  149.84  4572.5  149.93  4667.6  149.63  5149.5  149.46  5208.6  148.50
  5238.7  149.04  5417.5  148.20  5417.8  147.70  5421.3  147.70  5421.5  148.20
  5487.3  148.57  5645.3  149.40  5761.8  150.21  5961.8  152.81  6002.0  154.07
  6007.1  153.63  6052.4  154.22  6142.9  156.10  6203.1  155.93  6319.6  157.15
#Mann=10,-1,0
  3797.4    0.05       0  3952.2    0.12       0  4572.5   0.013       0
  4667.6    0.12       0  5417.5    0.05       0  5421.5    0.12       0
  5487.3    0.05       0  5645.3    0.04       0  5761.8    0.05       0
  5961.8    0.04       0
Bank Sta=5417.5,5421.5
Exp/Cntr=0.3,0.1

Type RM Length L Ch R = 1,2137,227,227,227
BEGIN DESCRIPTION:
4832
END DESCRIPTION:
XS GIS Cut Line= 4
      2562576.22     13554087.30      2562202.07     13553053.90
      2561860.72     13552806.87      2560701.94     13552829.33
#Sta/Elev= 30
  3743.0  152.31  4051.8  149.49  4138.4  149.72  4205.0  148.90  4260.9  149.49
  4277.2  148.71  4312.8  149.32  4451.0  148.82  4582.0  148.29  4606.9  147.46
  4713.3  148.17  4755.2  147.37  5168.8  146.82  5267.1  146.52  5267.4  146.02
  5271.1  146.52  5329.3  146.87  5478.1  147.21  5577.2  147.29  5685.7  147.28
  5819.2  147.34  5889.2  148.70  5923.4  148.44  6119.3  151.04  6259.3  154.45
  6299.3  153.17  6339.3  153.00  6349.3  153.40  6369.3  156.56  6422.4  156.48
#Mann=11,-1,0
  3743.0    0.12       0  4312.8   0.013       0  4451.0    0.12       0
  5168.8    0.05       0  5267.1    0.05       0  5271.1    0.05       0
  5329.3    0.12       0  5478.1    0.05       0  5577.2    0.04       0
  5685.7    0.05       0  5923.4    0.04       0
Bank Sta=5267.1,5271.1
Exp/Cntr=0.3,0.1

Type RM Length L Ch R = 1,1910,456,456,456
BEGIN DESCRIPTION:
LGII3063
END DESCRIPTION:
XS GIS Cut Line= 4
      2562730.74     13554111.61      2562540.82     13553073.07
      2561912.89     13552557.45      2560764.78     13552685.61
#Sta/Elev= 30
  3472.5  152.03  3631.7  149.59  3835.0  148.21  3946.8  147.83  3974.6  148.58
  4018.0  147.77  4068.8  147.92  4079.0  148.23  4086.1  150.33  4091.2  148.66
  4129.8  147.28  4445.0  146.39  4495.8  145.58  4737.1  146.34  4770.3  145.39
  4770.6  144.89  4774.3  145.39  4850.5  146.58  4859.2  146.17  4895.2  146.25
  4993.1  146.48  5904.0  146.36  6012.8  146.53  6133.5  148.30  6143.6  149.00
  6224.1  148.98  6334.8  150.94  6448.0  154.39  6475.7  154.83  6496.0  154.02
#Mann=7,-1,0
  3472.5    0.12       0  4770.3    0.05       0  4774.3    0.12       0
  4859.2    0.05       0  4895.2    0.12       0  4993.1    0.05       0
  5904.0    0.04       0
Bank Sta=4770.3,4774.3
Exp/Cntr=0.3,0.1

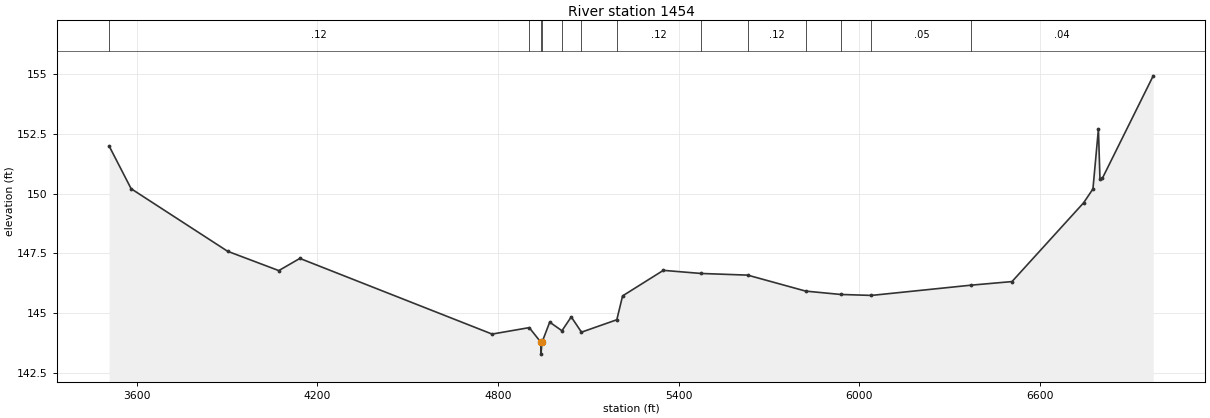
Type RM Length L Ch R = 1,1454,0,0,0
BEGIN DESCRIPTION:
4831
END DESCRIPTION:
XS GIS Cut Line= 5
      2562768.93     13554108.12      2562736.54     13552869.75
      2562269.44     13552479.00      2562044.87     13552308.32
      2560751.36     13552645.17
#Sta/Elev= 30
  3509.0  152.00  3582.1  150.21  3902.3  147.59  4072.3  146.78  4142.3  147.29
  4780.5  144.12  4903.8  144.39  4942.4  143.78  4942.7  143.28  4946.4  143.78
  4971.8  144.62  5012.4  144.26  5043.3  144.84  5077.3  144.20  5194.6  144.72
  5213.8  145.72  5349.1  146.79  5473.8  146.66  5629.1  146.59  5821.8  145.92
  5937.7  145.78  6040.1  145.74  6371.4  146.17  6506.7  146.32  6744.4  149.62
  6775.4  150.20  6793.6  152.71  6798.7  150.62  6806.4  150.64  6975.5  154.94
#Mann=13,-1,0
  3509.0    0.12       0  4903.8    0.05       0  4942.4    0.05       0
  4946.4    0.05       0  5012.4    0.12       0  5077.3    0.05       0
  5194.6    0.12       0  5473.8    0.05       0  5629.1    0.12       0
  5821.8    0.05       0  5937.7    0.12       0  6040.1    0.05       0
  6371.4    0.04       0
Bank Sta=4942.4,4946.4
Exp/Cntr=0.3,0.1

Chan Stop Cuts=-1