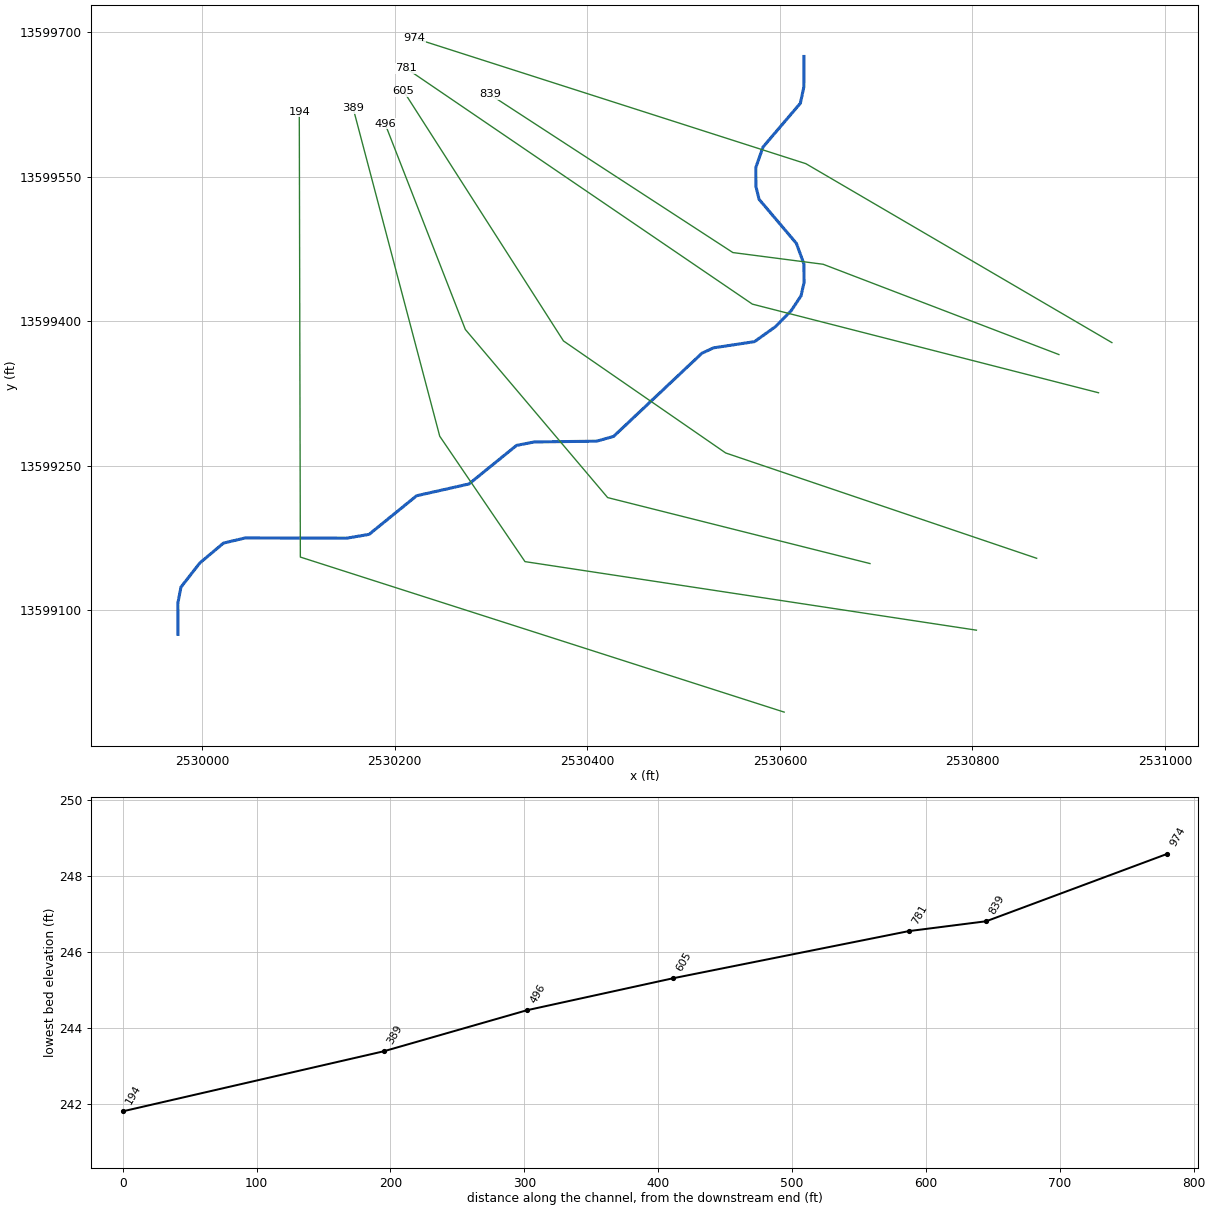
--- TRIB 5 TO SANDY FORK.prj (project) ---

Proj Title=TRIB 5 TO SANDY FORK Base Level Engineering
Current Plan=p01
Default Exp/Contr=0.3,0.1
English Units
Geom File=g01
Flow File=f01
Plan File=p01
BEGIN DESCRIPTION:
TRIB 5 TO SANDY FORK
END DESCRIPTION:

--- TRIB 5 TO SANDY FORK.p01 (plan) ---

Plan Title=Multiple Run
Short Identifier=Multiple
Geom File=g01
Flow File=f01
Subcritical Flow
K Sum by GR= 0
Std Step Tol= 0.01
Critical Tol= 0.01
Num of Std Step Trials= 20
Max Error Tol= 0.3
Flow Tol Ratio= 0.001
Split Flow NTrial= 30
Split Flow Tol= 0.02
Split Flow Ratio= 0.02
Log Output Level= 0
Friction Slope Method= 1
Unsteady Friction Slope Method= 2
Unsteady Bridges Friction Slope Method= 1
Parabolic Critical Depth
Global Vel Dist=  1 , 1 , 1
Global Log Level= 0
CheckData=True
Encroach Param= -1, 0, 0, 0
BEGIN DESCRIPTION:
Multiple Run
END DESCRIPTION:

--- TRIB 5 TO SANDY FORK.f01 (steady flow) ---

Flow Title=Multiple
Number of Profiles=7
Profile Names=10-year,25-year,50-year,1pct_min,100-year,1pct_plu,500-year
River Rch & RM= TRIB 5 TO SANDY ,Reach-1,974
     322     500     656     418     834    1664    1333
Boundary for River Rch & Prof#=TRIB 5 TO SANDY ,Reach-1,1
Up Type=0
Dn Type=3
Dn Slope=0.005
Boundary for River Rch & Prof#=TRIB 5 TO SANDY ,Reach-1,2
Up Type=0
Dn Type=3
Dn Slope=0.005
Boundary for River Rch & Prof#=TRIB 5 TO SANDY ,Reach-1,3
Up Type=0
Dn Type=3
Dn Slope=0.005
Boundary for River Rch & Prof#=TRIB 5 TO SANDY ,Reach-1,4
Up Type=0
Dn Type=3
Dn Slope=0.005
Boundary for River Rch & Prof#=TRIB 5 TO SANDY ,Reach-1,5
Up Type=0
Dn Type=3
Dn Slope=0.005
Boundary for River Rch & Prof#=TRIB 5 TO SANDY ,Reach-1,6
Up Type=0
Dn Type=3
Dn Slope=0.005
Boundary for River Rch & Prof#=TRIB 5 TO SANDY ,Reach-1,7
Up Type=0
Dn Type=3
Dn Slope=0.005

--- TRIB 5 TO SANDY FORK.g01 (geometry) ---

Geom Title=Existing Conditions

River Reach=TRIB 5 TO SANDY ,Reach-1
Reach XY= 30
      2530625.00     13599675.00      2530624.86     13599643.19
      2530621.31     13599626.49      2530582.52     13599581.00
      2530574.98     13599559.62      2530575.07     13599540.38
      2530578.39     13599526.71      2530617.17     13599480.91
      2530624.98     13599459.53      2530625.10     13599440.21
      2530621.96     13599426.42      2530612.02     13599411.43
      2530595.68     13599394.63      2530573.63     13599378.89
      2530531.10     13599372.44      2530518.98     13599366.81
      2530427.42     13599280.54      2530409.78     13599275.53
      2530345.10     13599274.76      2530326.59     13599271.17
      2530277.18     13599231.11      2530222.82     13599218.88
      2530173.44     13599178.76      2530150.08     13599174.81
      2530044.91     13599175.07      2530022.31     13599169.73
      2529997.76     13599149.15      2529978.12     13599124.02
      2529974.84     13599107.08      2529975.00     13599075.00

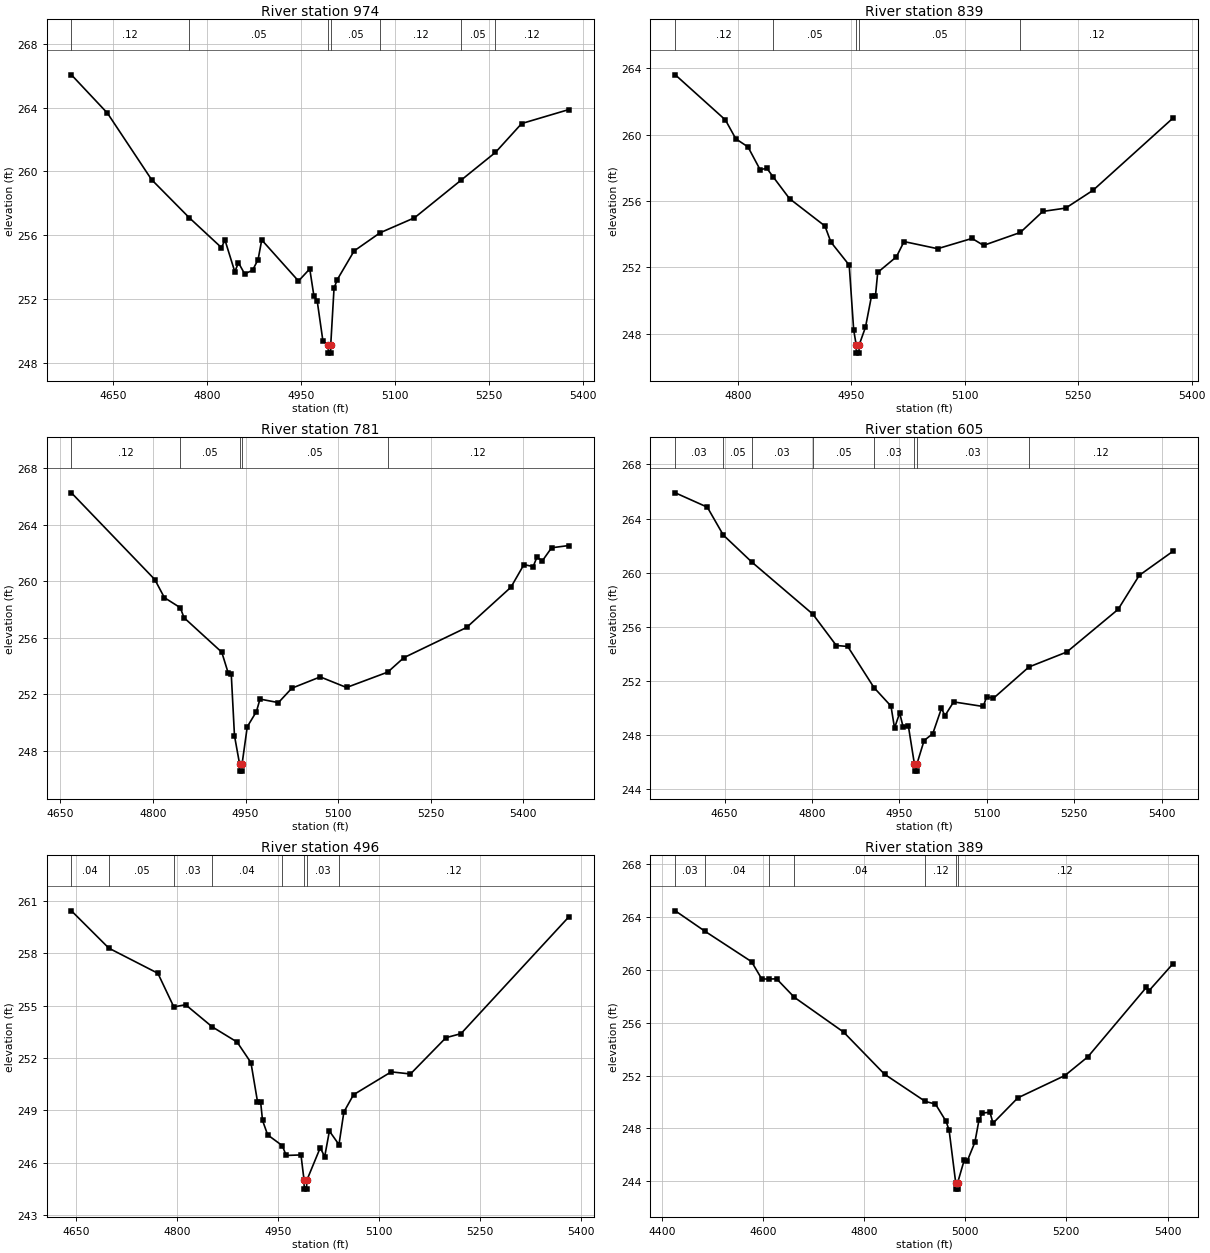
Type RM Length L Ch R = 1,974,135,135,135
BEGIN DESCRIPTION:
Mapping XS 51b91b71
END DESCRIPTION:
XS GIS Cut Line= 3
      2530944.75     13599377.89      2530627.02     13599563.67
      2530220.74     13599693.89
#Sta/Elev= 30
  4583.5  266.07  4641.1  263.66  4711.5  259.49  4771.6  257.10  4823.1  255.22
  4828.8  255.69  4844.5  253.70  4850.3  254.27  4860.2  253.57  4872.8  253.79
  4881.7  254.47  4887.5  255.70  4946.2  253.12  4964.2  253.88  4970.9  252.17
  4976.1  251.87  4985.2  249.36  4993.7  249.09  4993.9  248.59  4997.4  248.59
  4997.7  249.09  5003.0  252.67  5008.2  253.21  5035.1  255.01  5076.6  256.15
  5131.5  257.09  5205.5  259.44  5260.9  261.20  5302.7  263.01  5378.2  263.89
#Mann=7,-1,0
  4583.5    0.12       0  4771.6    0.05       0  4993.7    0.05       0
  4997.7    0.05       0  5076.6    0.12       0  5205.5    0.05       0
  5260.9    0.12       0
Bank Sta=4993.7,4997.7
Exp/Cntr=0.3,0.1

Type RM Length L Ch R = 1,839,58,58,58
BEGIN DESCRIPTION:
4835
END DESCRIPTION:
XS GIS Cut Line= 4
      2530889.72     13599365.49      2530644.93     13599459.24
      2530551.18     13599471.40      2530298.86     13599635.58
#Sta/Elev= 30
  4717.4  263.61  4783.6  260.89  4797.4  259.75  4813.5  259.26  4829.5  257.89
  4838.4  257.97  4846.5  257.47  4868.4  256.14  4915.2  254.49  4923.1  253.52
  4947.3  252.13  4953.2  248.23  4956.5  247.32  4956.8  246.82  4960.3  246.82
  4960.5  247.32  4968.8  248.38  4976.8  250.27  4982.0  250.27  4985.0  251.69
  5009.7  252.63  5019.8  253.55  5064.2  253.12  5109.7  253.74  5124.9  253.32
  5173.5  254.10  5203.3  255.37  5233.5  255.57  5269.8  256.65  5375.1  260.99
#Mann=5,-1,0
  4717.4    0.12       0  4846.5    0.05       0  4956.5    0.05       0
  4960.5    0.05       0  5173.5    0.12       0
Bank Sta=4956.5,4960.5
Exp/Cntr=0.3,0.1

Type RM Length L Ch R = 1,781,176,176,176
BEGIN DESCRIPTION:
Mapping XS a20baa72
END DESCRIPTION:
XS GIS Cut Line= 3
      2530930.87     13599325.82      2530571.46     13599417.84
      2530212.11     13599662.61
#Sta/Elev= 30
  4667.9  266.26  4803.0  260.12  4818.5  258.84  4844.2  258.13  4850.3  257.42
  4911.4  254.98  4921.6  253.54  4926.8  253.42  4932.0  249.07  4940.3  247.06
  4940.6  246.56  4944.1  246.56  4944.3  247.06  4952.7  249.70  4967.6  250.78
  4973.3  251.66  5003.2  251.41  5024.9  252.43  5070.9  253.23  5113.5  252.48
  5180.3  253.57  5206.3  254.59  5308.0  256.73  5379.8  259.58  5400.8  261.18
  5415.8  261.04  5421.8  261.70  5430.7  261.45  5445.6  262.37  5473.7  262.53
#Mann=5,-1,0
  4667.9    0.12       0  4844.2    0.05       0  4940.3    0.05       0
  4944.3    0.05       0  5180.3    0.12       0
Bank Sta=4940.3,4944.3
Exp/Cntr=0.3,0.1

Type RM Length L Ch R = 1,605,109,109,109
BEGIN DESCRIPTION:
Mapping XS 52e1489b
END DESCRIPTION:
XS GIS Cut Line= 4
      2530866.64     13599153.94      2530543.69     13599263.32
      2530375.28     13599379.64      2530209.33     13599638.94
#Sta/Elev= 30
  4565.5  265.90  4620.4  264.84  4647.8  262.78  4696.5  260.79  4801.4  256.93
  4841.7  254.61  4861.3  254.54  4906.3  251.50  4935.5  250.13  4941.6  248.51
  4950.4  249.62  4956.5  248.56  4965.3  248.67  4975.8  245.82  4976.1  245.32
  4979.6  245.32  4979.8  245.82  4992.3  247.58  5007.2  248.09  5022.1  249.96
  5028.1  249.42  5043.0  250.44  5093.7  250.10  5099.8  250.83  5111.1  250.70
  5172.1  253.02  5237.2  254.13  5325.1  257.28  5361.5  259.80  5419.0  261.57
#Mann=8,-1,0
  4565.5    0.03       0  4647.8    0.05       0  4696.5    0.03       0
  4801.4    0.05       0  4906.3    0.03       0  4975.8    0.03       0
  4979.8    0.03       0  5172.1    0.12       0
Bank Sta=4975.8,4979.8
Exp/Cntr=0.3,0.1

Type RM Length L Ch R = 1,496,107,107,107
BEGIN DESCRIPTION:
4834
END DESCRIPTION:
XS GIS Cut Line= 4
      2530693.57     13599148.47      2530421.16     13599216.97
      2530273.40     13599391.53      2530190.08     13599605.06
#Sta/Elev= 30
  4643.1  260.43  4698.7  258.29  4771.5  256.85  4795.2  254.92  4812.6  255.05
  4852.2  253.78  4889.1  252.91  4909.7  251.73  4919.4  249.50  4924.0  249.50
  4926.9  248.42  4934.5  247.59  4956.3  246.97  4962.0  246.41  4984.0  246.44
  4988.6  244.98  4988.8  244.48  4992.3  244.48  4992.6  244.98  5012.6  246.85
  5019.2  246.34  5026.2  247.81  5040.4  247.03  5047.7  248.90  5062.0  249.89
  5118.0  251.20  5146.6  251.08  5199.3  253.16  5221.6  253.39  5381.9  260.09
#Mann=8,-1,0
  4643.1    0.04       0  4698.7    0.05       0  4795.2    0.03       0
  4852.2    0.04       0  4956.3    0.03       0  4988.6    0.03       0
  4992.6    0.03       0  5040.4    0.12       0
Bank Sta=4988.6,4992.6
Exp/Cntr=0.3,0.1

Type RM Length L Ch R = 1,389,195,195,195
BEGIN DESCRIPTION:
Mapping XS 9a73ac56
END DESCRIPTION:
XS GIS Cut Line= 4
      2530804.09     13599079.30      2530335.35     13599150.48
      2530246.81     13599280.69      2530156.89     13599621.35
#Sta/Elev= 30
  4426.6  264.47  4485.8  262.91  4577.4  260.62  4597.6  259.31  4612.8  259.31
  4627.0  259.32  4662.1  257.92  4759.4  255.29  4840.4  252.10  4921.0  250.04
  4941.1  249.84  4962.1  248.53  4968.1  247.86  4981.1  243.90  4981.3  243.40
  4984.8  243.40  4985.1  243.90  4998.0  245.60  5004.1  245.54  5019.0  246.94
  5027.1  248.61  5033.9  249.16  5048.9  249.22  5054.9  248.39  5104.0  250.31
  5197.1  252.00  5242.6  253.42  5358.3  258.68  5363.4  258.42  5410.5  260.45
#Mann=7,-1,0
  4426.6    0.03       0  4485.8    0.04       0  4612.8    0.05       0
  4662.1    0.04       0  4921.0    0.12       0  4981.1    0.05       0
  4985.1    0.12       0
Bank Sta=4981.1,4985.1
Exp/Cntr=0.3,0.1

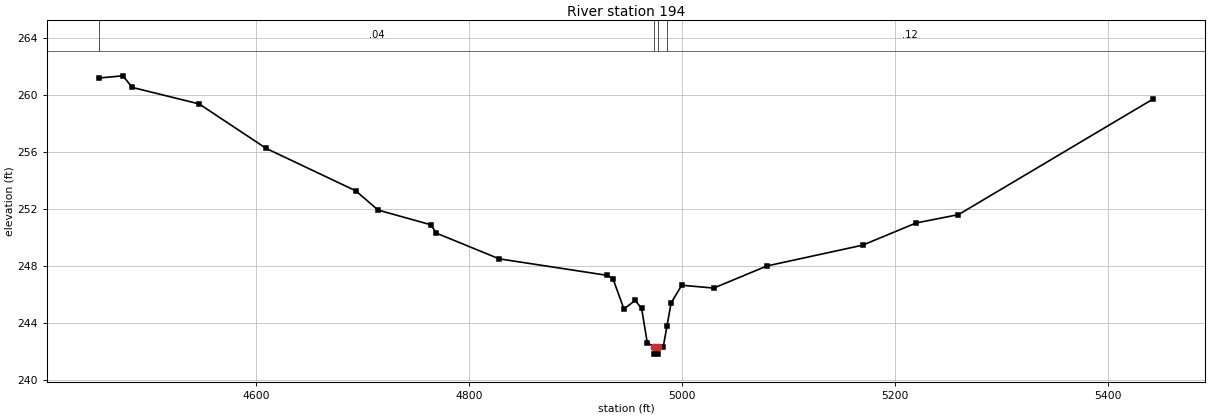
Type RM Length L Ch R = 1,194,0,0,0
BEGIN DESCRIPTION:
TRIB 5 TO SANDY FORK 1.0
END DESCRIPTION:
XS GIS Cut Line= 3
      2530604.46     13598994.22      2530102.08     13599155.21
      2530100.98     13599617.47
#Sta/Elev= 30
  4452.7  261.18  4475.0  261.33  4483.6  260.52  4546.6  259.36  4609.6  256.24
  4693.7  253.27  4714.7  251.92  4764.2  250.89  4769.5  250.30  4828.5  248.50
  4930.2  247.34  4935.4  247.10  4945.7  244.98  4956.2  245.59  4962.3  245.02
  4967.6  242.62  4974.1  242.32  4974.3  241.82  4977.8  241.82  4978.1  242.32
  4982.6  242.32  4986.1  243.78  4990.0  245.41  5000.0  246.65  5030.0  246.45
  5080.0  248.00  5170.0  249.46  5220.0  251.01  5260.0  251.60  5442.5  259.69
#Mann=4,-1,0
  4452.7    0.04       0  4974.1    0.05       0  4978.1    0.04       0
  4986.1    0.12       0
Bank Sta=4974.1,4978.1
Exp/Cntr=0.3,0.1

Chan Stop Cuts=-1