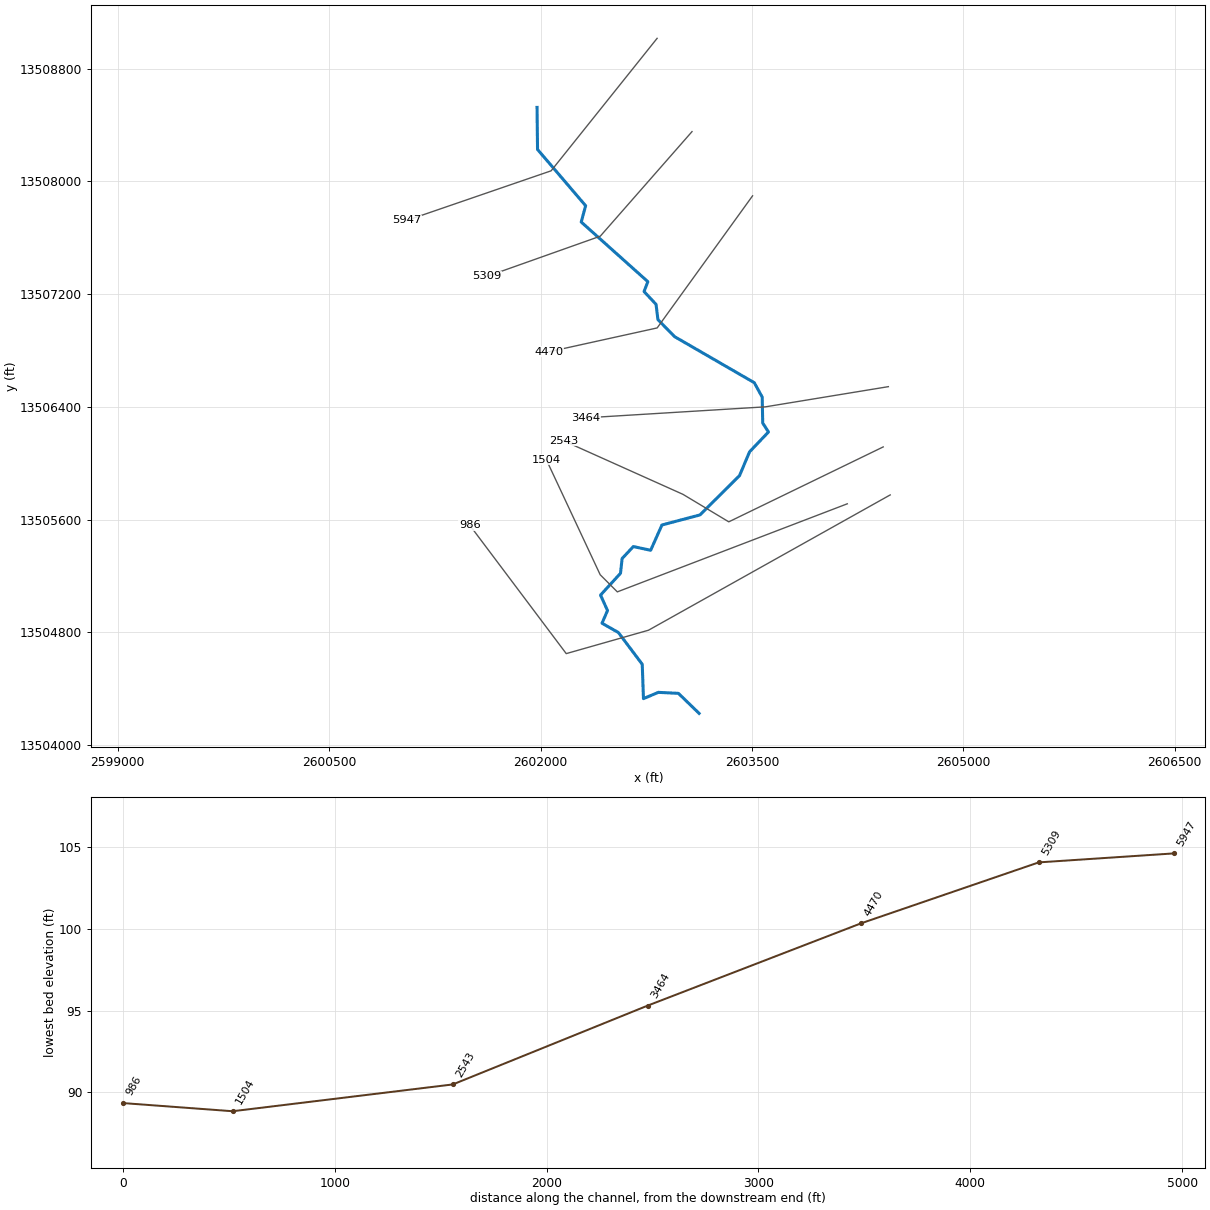
--- TRIB 5 TO SPRING CREEK.prj (project) ---

Proj Title=TRIB 5 TO SPRING CREEK Base Level Engineering
Current Plan=p01
Default Exp/Contr=0.3,0.1
English Units
Geom File=g01
Flow File=f01
Plan File=p01
Y Axis Title=Elevation
X Axis Title(PF)=Main Channel Distance
X Axis Title(XS)=Station
BEGIN DESCRIPTION:
TRIB 5 TO SPRING CREEK
END DESCRIPTION:
DSS Export Rating Curves= 0
DSS Export Rating Curve Sorted= 0
DSS Export Volume Flow Curves= 0
DXF OffsetX= 0
DXF OffsetY= 0
DXF ScaleX= 1
DXF ScaleY= 10

--- TRIB 5 TO SPRING CREEK.p01 (plan) ---

Plan Title=Multiple Run
Short Identifier=Multiple
Geom File=g01
Flow File=f01
Subcritical Flow
K Sum by GR= 0
Std Step Tol= 0.01
Critical Tol= 0.01
Num of Std Step Trials= 20
Max Error Tol= 0.3
Flow Tol Ratio= 0.001
Split Flow NTrial= 30
Split Flow Tol= 0.02
Split Flow Ratio= 0.02
Log Output Level= 0
Friction Slope Method= 1
Unsteady Friction Slope Method= 2
Unsteady Bridges Friction Slope Method= 1
Parabolic Critical Depth
Global Vel Dist=  1 , 1 , 1
Global Log Level= 0
CheckData=True
Encroach Param= -1, 0, 0, 0
BEGIN DESCRIPTION:
Multiple Run
END DESCRIPTION:

--- TRIB 5 TO SPRING CREEK.f01 (steady flow) ---

Flow Title=Multiple
Number of Profiles=7
Profile Names=10-year,25-year,50-year,1pct_min,100-year,1pct_plu,500-year
River Rch & RM= TRIB 5 TO SPRING,Reach-1,5947
     779    1220    1605    1020    2035    4060    3231
River Rch & RM= TRIB 5 TO SPRING,Reach-1,3464
     926    1469    1952    1253    2499    4987    4047
Boundary for River Rch & Prof#=TRIB 5 TO SPRING,Reach-1,1
Up Type=0
Dn Type=3
Dn Slope=0.005
Boundary for River Rch & Prof#=TRIB 5 TO SPRING,Reach-1,2
Up Type=0
Dn Type=3
Dn Slope=0.005
Boundary for River Rch & Prof#=TRIB 5 TO SPRING,Reach-1,3
Up Type=0
Dn Type=3
Dn Slope=0.005
Boundary for River Rch & Prof#=TRIB 5 TO SPRING,Reach-1,4
Up Type=0
Dn Type=3
Dn Slope=0.005
Boundary for River Rch & Prof#=TRIB 5 TO SPRING,Reach-1,5
Up Type=0
Dn Type=3
Dn Slope=0.005
Boundary for River Rch & Prof#=TRIB 5 TO SPRING,Reach-1,6
Up Type=0
Dn Type=3
Dn Slope=0.005
Boundary for River Rch & Prof#=TRIB 5 TO SPRING,Reach-1,7
Up Type=0
Dn Type=3
Dn Slope=0.005

--- TRIB 5 TO SPRING CREEK.g01 (geometry) ---

Geom Title=Existing Conditions
Program Version=4.10

River Reach=TRIB 5 TO SPRING,Reach-1
Reach XY= 30
        2601975.       13508525.      2601978.55     13508226.47
      2602319.88     13507827.29      2602288.54     13507711.62
      2602761.35     13507288.33      2602734.32     13507218.34
      2602819.45     13507127.43      2602832.86     13507018.83
      2602951.53     13506898.01      2603516.54      13506571.5
      2603572.77      13506469.1      2603576.39     13506285.43
      2603617.21     13506221.58      2603483.14     13506081.06
      2603411.46     13505911.46      2603131.06     13505633.14
      2602861.27      13505561.8      2602781.37     13505382.37
      2602658.26     13505408.71      2602578.61     13505323.53
      2602567.14     13505218.83       2602425.6     13505064.38
      2602475.19     13504954.79      2602435.98     13504864.63
      2602552.13     13504798.84      2602721.46     13504573.54
      2602730.17     13504329.59      2602835.68     13504374.16
      2602978.34     13504367.02        2603125.       13504225.

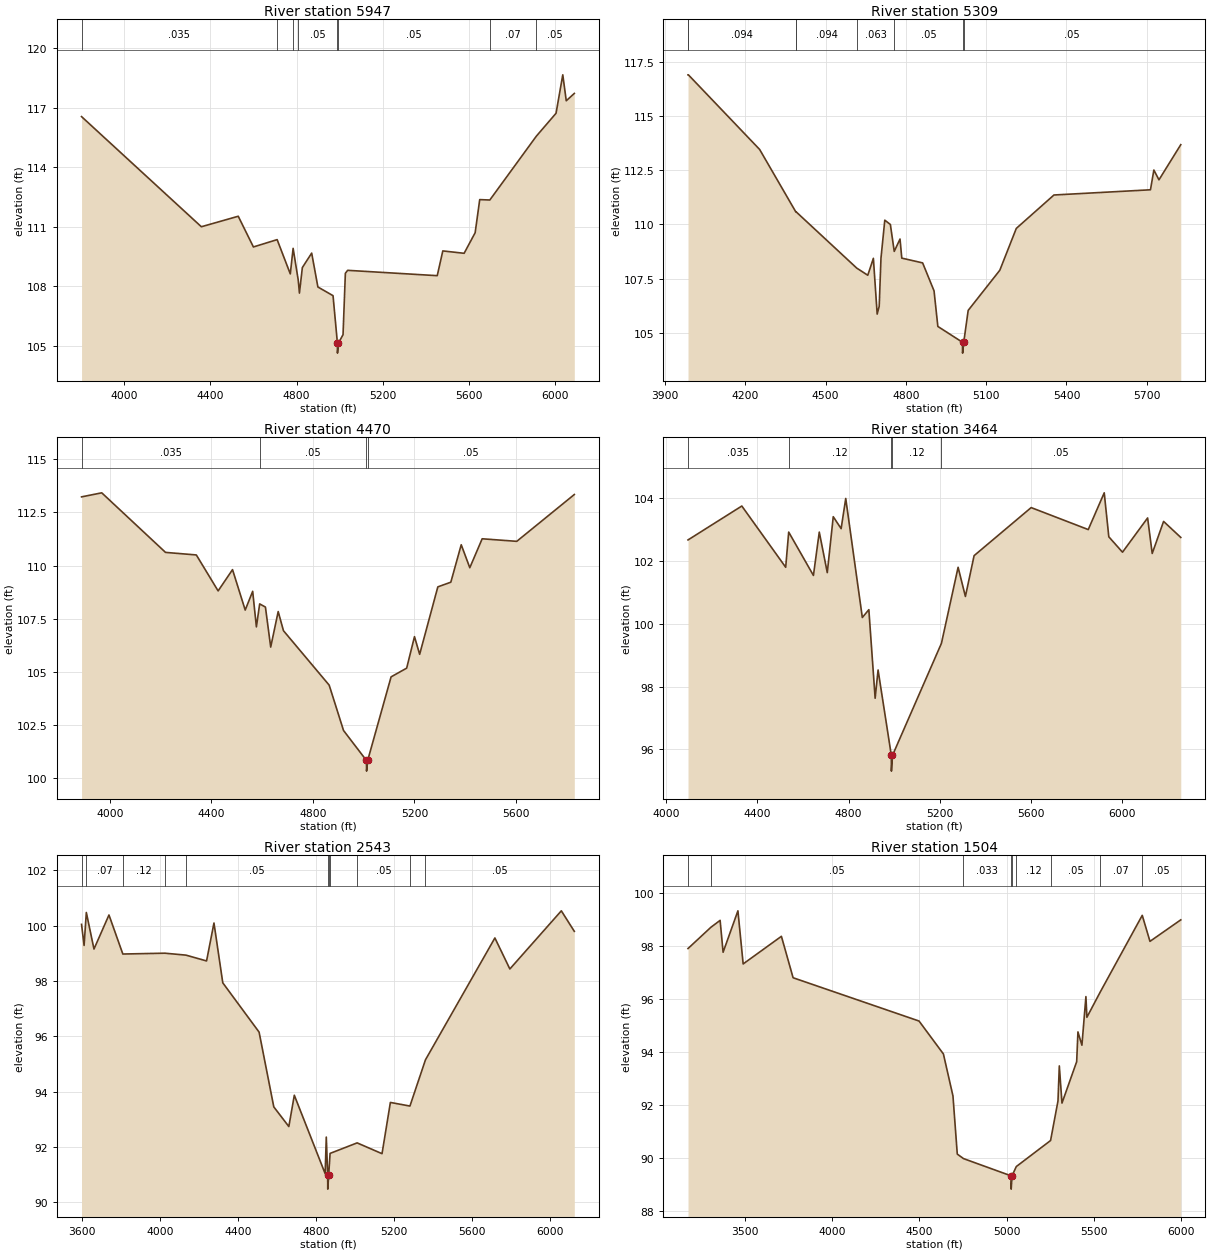
Type RM Length L Ch R = 1 ,5947    ,638,638,638
BEGIN DESCRIPTION:
TRIB 5 TO SPRING CREEK 5.0
END DESCRIPTION:
XS GIS Cut Line= 3
      2602827.02     13509015.03        2602075.       13508075.
      2601049.62     13507722.52
#Sta/Elev= 30
  3801.3  116.56  4357.6     111  4528.9  111.53  4599.3  109.98  4709.5  110.35
  4770.6  108.62  4783.7  109.91  4807.3  108.32    4813  107.65  4826.6  108.94
  4869.9  109.67  4898.7  107.96  4969.1  107.52  4989.4  105.12  4989.7  104.62
  4993.7  105.12  5015.5  105.55  5026.3  108.65  5036.9   108.8  5452.9  108.53
  5478.8  109.78  5577.8  109.66    5629   110.7  5650.2  112.37  5697.1  112.35
  5912.9  115.57  6004.6  116.73  6035.9  118.67    6052  117.36  6089.4  117.73
#Mann= 8 ,-1 , 0
  3801.3    .035       0  4709.5    .063       0  4783.7    .035       0
  4807.3     .05       0  4989.4     .05       0  4993.7     .05       0
  5697.1     .07       0  5912.9     .05       0
Bank Sta=4989.4,4993.7
XS Rating Curve= 0 ,0
Exp/Cntr=0.3,0.1

Type RM Length L Ch R = 1 ,5309    ,839,839,839
BEGIN DESCRIPTION:
Mapping XS 7584160a
END DESCRIPTION:
XS GIS Cut Line= 3
      2603074.78     13508353.28      2602423.76     13507611.11
      2601618.21     13507325.27
#Sta/Elev= 30
  3985.4   116.9  3986.7   116.9  4253.1  113.46  4388.9  110.57  4389.9  110.58
  4616.1  107.99  4657.4  107.66  4678.3  108.44  4692.5  105.87  4700.1  106.23
  4706.7  108.45    4721   110.2  4741.8     110  4756.3  108.76  4777.9  109.33
  4784.5  108.45  4862.4  108.23  4905.1  106.94  4919.3   105.3  5011.5  104.57
  5011.8  104.07  5016.1  104.57  5032.7  106.04  5150.9  107.89  5212.6  109.82
  5353.3  111.36  5714.1   111.6  5726.8  112.51  5745.9  112.06  5827.4  113.68
#Mann= 8 ,-1 , 0
  3985.4    .063       0  3986.7    .094       0  4388.9    .063       0
  4389.9    .094       0  4616.1    .063       0  4756.3     .05       0
  5011.5     .05       0  5016.1     .05       0
Bank Sta=5011.5,5016.1
XS Rating Curve= 0 ,0
Exp/Cntr=0.3,0.1

Type RM Length L Ch R = 1 ,4470    ,1006,1006,1006
BEGIN DESCRIPTION:
Mapping XS 6d4cf73d
END DESCRIPTION:
XS GIS Cut Line= 3
      2603504.47     13507897.54       2602827.4     13506960.06
      2602059.62     13506790.89
#Sta/Elev= 30
  3887.9  113.23  3967.5  113.42    4219  110.62  4340.4   110.5  4426.3  108.81
  4483.1  109.81  4533.1  107.91  4562.5  108.79  4577.2  107.12  4590.1   108.2
  4612.8  108.05  4633.6  106.17  4663.1  107.84  4683.9  106.94  4864.2  104.38
  4920.7  102.25  5011.1  100.84  5011.5  100.34  5015.9  100.84  5108.2  104.77
  5169.6  105.18  5200.4  106.66  5220.8  105.83  5292.5     109  5343.7  109.22
  5384.7  110.98  5418.5   109.9  5467.3  111.26  5603.6  111.14  5830.5  113.34
#Mann= 4 ,-1 , 0
  3887.9    .035       0  4590.1     .05       0  5011.1     .05       0
  5015.9     .05       0
Bank Sta=5011.1,5015.9
XS Rating Curve= 0 ,0
Exp/Cntr=0.3,0.1

Type RM Length L Ch R = 1 ,3464    ,921,921,921
BEGIN DESCRIPTION:
Mapping XS 1432f090
END DESCRIPTION:
XS GIS Cut Line= 3
      2604467.98     13506543.39      2603595.63     13506400.17
      2602319.75     13506322.05
#Sta/Elev= 30
  4095.5  102.67  4331.6  103.75  4524.1   101.8  4537.3  102.92  4645.8  101.54
  4671.5  102.92  4706.6  101.63  4732.8  103.41  4767.4  103.03  4787.6  103.99
  4860.4   100.2    4889  100.45  4916.6   97.63  4929.5   98.53  4987.7   95.81
    4988   95.31  4992.7   95.81  5207.6   99.38  5280.7   101.8  5312.7  100.87
  5350.9  102.17  5601.3   103.7  5851.8     103  5921.9  104.17    5942  102.77
  6002.1  102.28  6112.3  103.37  6132.5  102.24  6182.4  103.26  6257.8  102.75
#Mann= 5 ,-1 , 0
  4095.5    .035       0  4537.3     .12       0  4987.7     .05       0
  4992.7     .12       0  5207.6     .05       0
Bank Sta=4987.7,4992.7
XS Rating Curve= 0 ,0
Exp/Cntr=0.3,0.1

Type RM Length L Ch R = 1 ,2543    ,1039,1039,1039
BEGIN DESCRIPTION:
Mapping XS b822b76f
END DESCRIPTION:
XS GIS Cut Line= 4
      2604431.43      13506115.8      2603335.54     13505584.13
      2603010.02     13505779.45      2602163.69     13506159.21
#Sta/Elev= 30
  3598.9  100.04  3611.9   99.28  3623.4  100.47  3662.6   99.15  3739.4  100.38
  3810.5   98.97  4026.1      99    4134   98.93  4239.6   98.72  4277.5  100.09
  4322.7   97.93  4508.8   96.15  4584.1   93.45  4661.2   92.74  4689.3   93.87
  4847.3   91.04  4853.1   92.36  4860.3   90.98  4860.7   90.48  4865.3   90.98
  4872.6   91.77  5011.2   92.15  5138.8   91.76  5181.6   93.61  5281.8   93.48
  5361.4   95.15  5717.2   99.55  5793.9   98.43  6057.7  100.53  6124.2   99.79
#Mann= 11 ,-1 , 0
  3598.9    .035       0  3623.4     .07       0  3810.5     .12       0
  4026.1     .07       0    4134     .05       0  4860.3     .05       0
  4865.3     .05       0  4872.6     .07       0  5011.2     .05       0
  5281.8     .07       0  5361.4     .05       0
Bank Sta=4860.3,4865.3
XS Rating Curve= 0 ,0
Exp/Cntr=0.3,0.1

Type RM Length L Ch R = 1 ,1504    ,518,518,518
BEGIN DESCRIPTION:
Mapping XS 52e463e9
END DESCRIPTION:
XS GIS Cut Line= 4
      2604176.59     13505712.16      2602544.66     13505087.17
      2602423.13     13505208.69       2602041.2     13506024.65
#Sta/Elev= 30
  3176.4    97.9  3307.3    98.7  3360.1   98.96  3377.2   97.76    3462   99.32
    3492   97.32  3710.9   98.36  3777.8    96.8  4498.6   95.17  4638.1   93.93
  4692.8   92.35  4717.5   90.16    4753   89.99  5025.6   89.34    5026   88.84
  5030.9   89.34  5055.3   89.69  5251.5   90.67  5293.9   92.16  5301.5   93.48
  5316.8   92.08  5400.9   93.64  5408.1   94.76  5430.9   94.26  5453.8   96.09
  5459.3   95.31  5535.5   96.26  5776.2   99.15  5820.4   98.17  5996.7   98.98
#Mann= 9 ,-1 , 0
  3176.4     .07       0  3307.3     .05       0    4753    .033       0
  5025.6    .033       0  5030.9    .033       0  5055.3     .12       0
  5251.5     .05       0  5535.5     .07       0  5776.2     .05       0
Bank Sta=5025.6,5030.9
XS Rating Curve= 0 ,0
Exp/Cntr=0.3,0.1

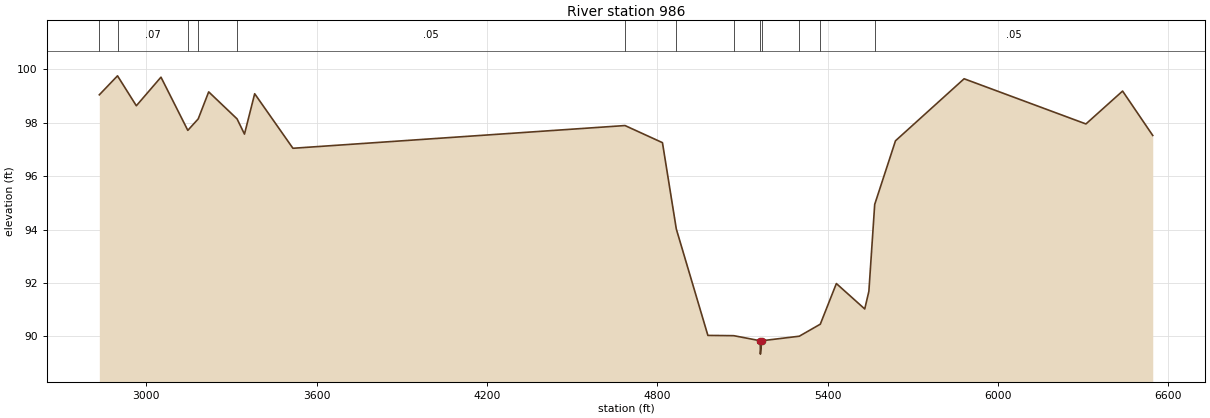
Type RM Length L Ch R = 1 ,986     ,0,0,0
BEGIN DESCRIPTION:
TRIB 5 TO SPRING CREEK 1.0
END DESCRIPTION:
XS GIS Cut Line= 4
      2604481.04     13505775.16      2602765.91     13504815.11
       2602182.2     13504649.05      2601498.91     13505558.44
#Sta/Elev= 30
    2835   99.04    2899   99.75  2965.3   98.63  3052.1    99.7  3146.6   97.71
  3183.3   98.14  3220.1   99.15    3320   98.14  3346.2   97.57  3382.1   99.08
  3516.8   97.04  4686.3   97.89  4818.2   97.25    4867   94.02  4978.2   90.04
  5069.3   90.03  5162.7   89.84  5163.1   89.34    5168   89.84  5300.1   90.01
  5374.1   90.46  5430.7   91.98  5530.6   91.03  5545.2   91.69  5565.7   94.94
  5638.9   97.32  5880.6   99.64  6309.6   97.95  6438.7   99.18  6544.9   97.52
#Mann= 13 ,-1 , 0
    2835     .05       0    2899     .07       0  3146.6     .05       0
  3183.3     .07       0    3320     .05       0  4686.3    .094       0
    4867    .035       0  5069.3    .033       0  5162.7    .035       0
    5168    .033       0  5300.1     .05       0  5374.1    .035       0
  5565.7     .05       0
Bank Sta=5162.7,5168
XS Rating Curve= 0 ,0
Exp/Cntr=0.3,0.1

Chan Stop Cuts=-1
Use User Specified Reach Order=0
Composite Channel Slope=5