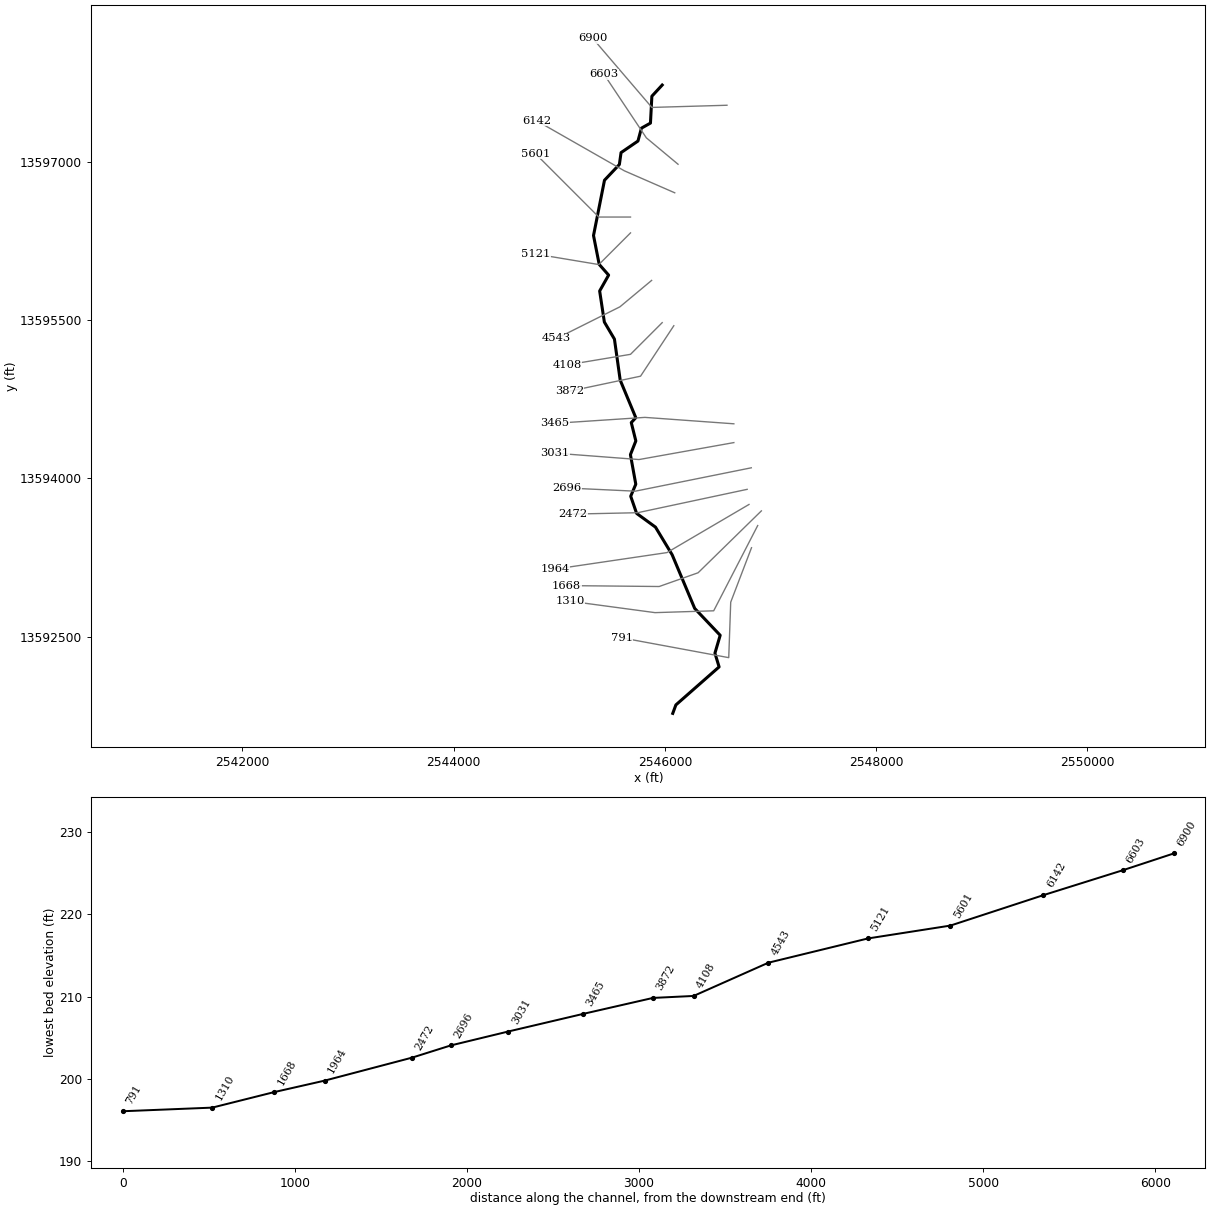
--- TRIB 5_1 TO IRISH CREEK.prj (project) ---

Proj Title=TRIB 5_1 TO IRISH CREEK Base Level Engineering
Current Plan=p01
Default Exp/Contr=0.3,0.1
English Units
Geom File=g01
Flow File=f01
Plan File=p01
BEGIN DESCRIPTION:
TRIB 5_1 TO IRISH CREEK
END DESCRIPTION:

--- TRIB 5_1 TO IRISH CREEK.p01 (plan) ---

Plan Title=Multiple Run
Short Identifier=Multiple
Geom File=g01
Flow File=f01
Subcritical Flow
K Sum by GR= 0
Std Step Tol= 0.01
Critical Tol= 0.01
Num of Std Step Trials= 20
Max Error Tol= 0.3
Flow Tol Ratio= 0.001
Split Flow NTrial= 30
Split Flow Tol= 0.02
Split Flow Ratio= 0.02
Log Output Level= 0
Friction Slope Method= 1
Unsteady Friction Slope Method= 2
Unsteady Bridges Friction Slope Method= 1
Parabolic Critical Depth
Global Vel Dist=  1 , 1 , 1
Global Log Level= 0
CheckData=True
Encroach Param= -1, 0, 0, 0
BEGIN DESCRIPTION:
Multiple Run
END DESCRIPTION:

--- TRIB 5_1 TO IRISH CREEK.f01 (steady flow) ---

Flow Title=Multiple
Number of Profiles=7
Profile Names=10-year,25-year,50-year,1pct_min,100-year,1pct_plu,500-year
River Rch & RM= TRIB 5_1 TO IRIS,Reach-1,6900
     416     651     859     550    1097    2189    1769
River Rch & RM= TRIB 5_1 TO IRIS,Reach-1,3465
     712    1151    1550    1011    2018    4027    3384
Boundary for River Rch & Prof#=TRIB 5_1 TO IRIS,Reach-1,1
Up Type=0
Dn Type=3
Dn Slope=0.005
Boundary for River Rch & Prof#=TRIB 5_1 TO IRIS,Reach-1,2
Up Type=0
Dn Type=3
Dn Slope=0.005
Boundary for River Rch & Prof#=TRIB 5_1 TO IRIS,Reach-1,3
Up Type=0
Dn Type=3
Dn Slope=0.005
Boundary for River Rch & Prof#=TRIB 5_1 TO IRIS,Reach-1,4
Up Type=0
Dn Type=3
Dn Slope=0.005
Boundary for River Rch & Prof#=TRIB 5_1 TO IRIS,Reach-1,5
Up Type=0
Dn Type=3
Dn Slope=0.005
Boundary for River Rch & Prof#=TRIB 5_1 TO IRIS,Reach-1,6
Up Type=0
Dn Type=3
Dn Slope=0.005
Boundary for River Rch & Prof#=TRIB 5_1 TO IRIS,Reach-1,7
Up Type=0
Dn Type=3
Dn Slope=0.005

--- TRIB 5_1 TO IRISH CREEK.g01 (geometry) ---

Geom Title=Existing Conditions

River Reach=TRIB 5_1 TO IRIS,Reach-1
Reach XY= 30
      2545975.00     13597725.00      2545877.22     13597619.09
      2545863.84     13597364.70      2545778.22     13597316.66
      2545745.51     13597194.74      2545585.39     13597085.10
      2545569.47     13596972.58      2545428.54     13596823.53
      2545324.60     13596300.00      2545378.56     13596026.46
      2545467.70     13595925.08      2545382.75     13595774.91
      2545427.25     13595480.93      2545522.75     13595319.07
      2545577.26     13594930.94      2545725.00     13594575.00
      2545682.23     13594528.45      2545725.39     13594354.87
      2545674.18     13594225.00      2545724.92     13593945.03
      2545676.82     13593831.12      2545732.85     13593668.81
      2545911.53     13593538.57      2546069.15     13593277.29
      2546282.86     13592768.83      2546524.07     13592514.52
      2546474.42     13592345.04      2546513.91     13592214.92
      2546104.65     13591855.22      2546075.00     13591775.00

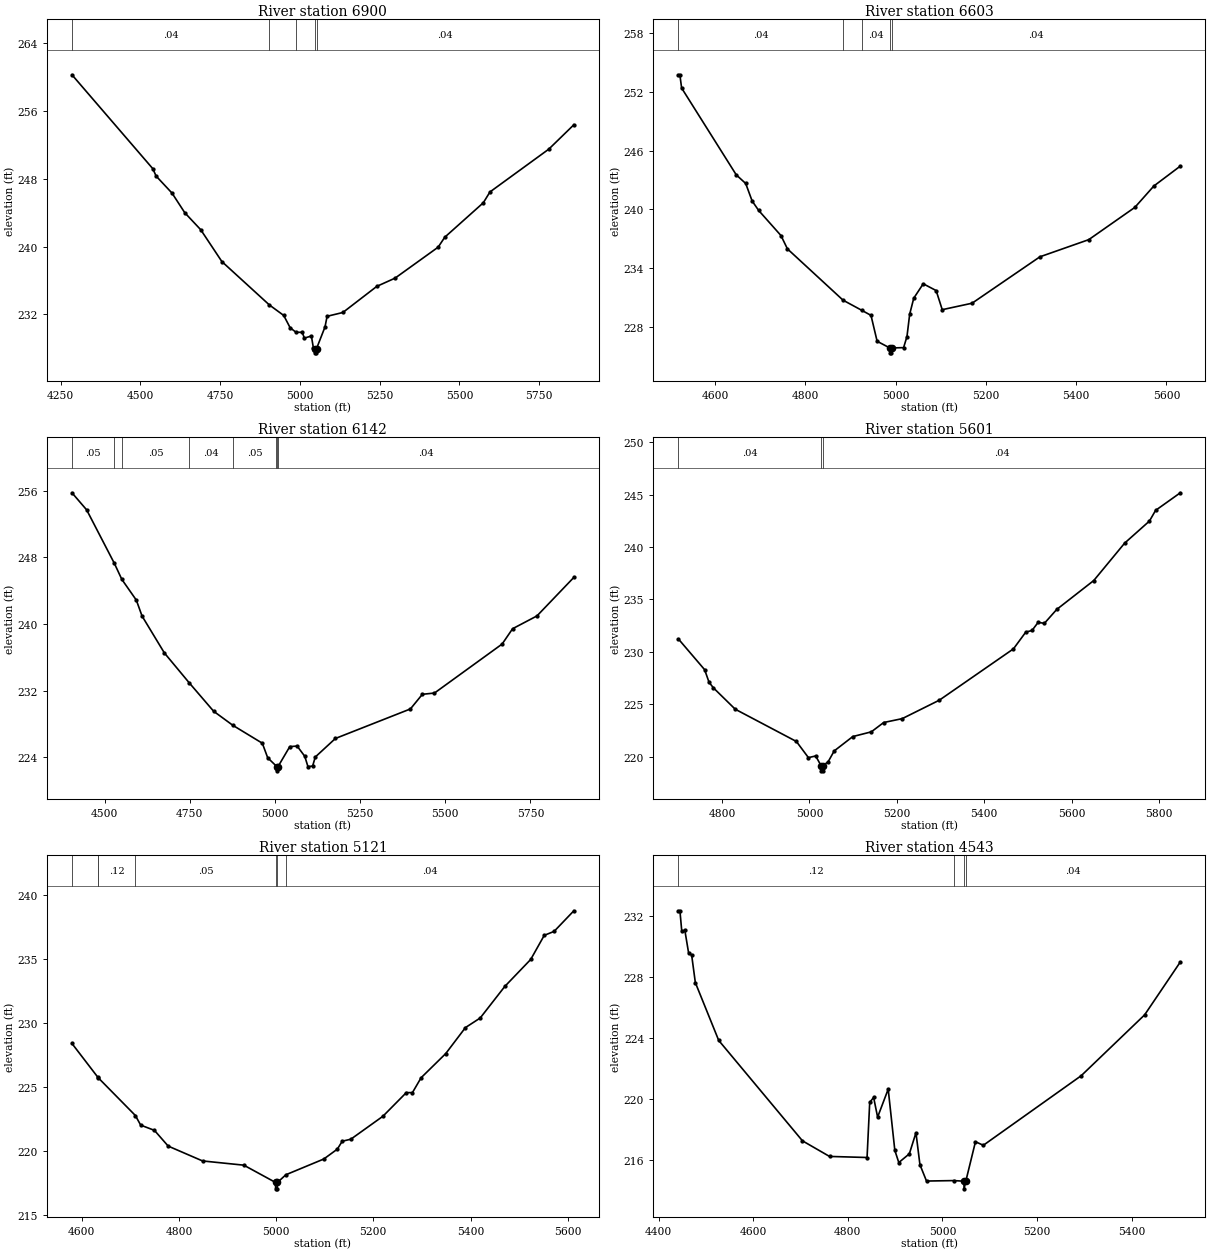
Type RM Length L Ch R = 1,6900,297,297,297
BEGIN DESCRIPTION:
TRIB 5_1 TO IRISH CREEK 12.0
END DESCRIPTION:
XS GIS Cut Line= 3
      2546588.54     13597533.62      2545876.96     13597513.03
      2545316.89     13598167.27
#Sta/Elev= 30
  4285.6  260.30  4539.2  249.19  4549.3  248.33  4599.3  246.31  4639.3  243.99
  4689.3  241.98  4755.5  238.22  4904.4  233.09  4949.4  231.85  4969.4  230.40
  4987.9  229.86  5007.4  229.86  5014.0  229.17  5036.0  229.42  5042.5  227.98
  5048.2  227.93  5048.5  227.43  5052.0  227.43  5052.2  227.93  5078.8  230.50
  5085.3  231.75  5134.7  232.20  5241.2  235.29  5298.3  236.26  5433.3  239.92
  5454.2  241.10  5574.9  245.17  5595.8  246.45  5780.2  251.51  5858.7  254.39
#Mann=5,-1,0
  4285.6    0.04       0  4904.4    0.05       0  4987.9    0.04       0
  5048.2    0.04       0  5052.2    0.04       0
Bank Sta=5048.2,5052.2
Exp/Cntr=0.3,0.1

Type RM Length L Ch R = 1,6603,461,461,461
BEGIN DESCRIPTION:
TRIB 5_1 TO IRISH CREEK 11.0
END DESCRIPTION:
XS GIS Cut Line= 3
      2546124.98     13596975.02      2545825.00     13597225.00
      2545425.00     13597825.00
#Sta/Elev= 30
  4519.2  253.73  4522.4  253.73  4526.3  252.38  4647.4  243.52  4668.2  242.65
  4682.5  240.86  4696.9  239.90  4746.3  237.34  4760.6  235.98  4883.8  230.75
  4924.7  229.73  4945.7  229.20  4959.3  226.56  4987.3  225.88  4987.6  225.38
  4991.1  225.38  4991.3  225.88  5017.9  225.91  5025.4  227.04  5031.4  229.32
  5040.4  230.95  5061.4  232.42  5090.0  231.73  5103.5  229.78  5169.6  230.44
  5319.8  235.17  5428.0  236.92  5530.1  240.21  5572.2  242.39  5630.8  244.42
#Mann=5,-1,0
  4519.2    0.04       0  4883.8    0.05       0  4924.7    0.04       0
  4987.3    0.04       0  4991.3    0.04       0
Bank Sta=4987.3,4991.3
Exp/Cntr=0.3,0.1

Type RM Length L Ch R = 1,6142,541,541,541
BEGIN DESCRIPTION:
Mapping XS e4030a16
END DESCRIPTION:
XS GIS Cut Line= 3
      2546093.76     13596704.64      2545616.35     13596912.96
      2544788.72     13597385.27
#Sta/Elev= 30
  4403.8  255.77  4446.9  253.72  4528.4  247.28  4550.3  245.36  4592.8  242.87
  4609.7  240.95  4675.2  236.52  4747.9  232.94  4819.9  229.51  4876.3  227.82
  4962.8  225.67  4978.6  223.92  5004.4  222.90  5004.8  222.85  5005.1  222.35
  5008.8  222.85  5043.4  225.26  5065.0  225.33  5087.4  224.10  5096.7  222.87
  5110.5  222.92  5118.3  224.01  5177.4  226.24  5397.7  229.79  5432.8  231.55
  5468.3  231.70  5667.0  237.59  5697.7  239.43  5769.3  240.97  5877.6  245.60
#Mann=8,-1,0
  4403.8    0.05       0  4528.4    0.04       0  4550.3    0.05       0
  4747.9    0.04       0  4876.3    0.05       0  5004.4    0.04       0
  5004.8    0.05       0  5008.8    0.04       0
Bank Sta=5004.8,5008.8
Exp/Cntr=0.3,0.1

Type RM Length L Ch R = 1,5601,480,480,480
BEGIN DESCRIPTION:
TRIB 5_1 TO IRISH CREEK 9.0
END DESCRIPTION:
XS GIS Cut Line= 3
      2545674.97     13596475.00      2545375.00     13596475.00
      2544775.00     13597075.00
#Sta/Elev= 30
  4700.1  231.22  4760.1  228.29  4770.1  227.10  4780.1  226.56  4830.1  224.52
  4970.1  221.44  4997.6  219.90  5014.2  220.06  5026.4  219.14  5026.6  218.64
  5030.1  218.64  5030.4  219.14  5042.5  219.49  5056.6  220.54  5099.1  221.91
  5141.5  222.36  5169.8  223.25  5212.2  223.62  5297.1  225.38  5466.8  230.28
  5495.0  231.88  5509.2  232.03  5523.3  232.81  5537.5  232.71  5565.8  234.04
  5650.6  236.80  5721.3  240.37  5777.9  242.47  5792.0  243.49  5848.6  245.17
#Mann=3,-1,0
  4700.1    0.04       0  5026.4    0.04       0  5030.4    0.04       0
Bank Sta=5026.4,5030.4
Exp/Cntr=0.3,0.1

Type RM Length L Ch R = 1,5121,578,578,578
BEGIN DESCRIPTION:
TRIB 5_1 TO IRISH CREEK 8.0
END DESCRIPTION:
XS GIS Cut Line= 3
      2545675.02     13596325.02      2545375.00     13596025.00
      2544774.96     13596125.01
#Sta/Elev= 30
  4580.0  228.43  4632.7  225.82  4633.8  225.76  4710.5  222.80  4721.4  222.05
  4749.7  221.64  4778.0  220.41  4848.7  219.25  4933.6  218.92  4998.8  217.57
  4999.0  217.07  5002.5  217.07  5002.8  217.57  5020.1  218.17  5098.1  219.40
  5125.9  220.17  5136.1  220.79  5153.8  220.95  5219.7  222.74  5267.9  224.59
  5280.5  224.59  5298.3  225.75  5349.0  227.64  5389.5  229.67  5419.9  230.42
  5470.6  232.89  5523.9  235.00  5551.7  236.88  5572.0  237.19  5612.6  238.80
#Mann=7,-1,0
  4580.0    0.12       0  4632.7    0.04       0  4633.8    0.12       0
  4710.5    0.05       0  4998.8    0.05       0  5002.8    0.05       0
  5020.1    0.04       0
Bank Sta=4998.8,5002.8
Exp/Cntr=0.3,0.1

Type RM Length L Ch R = 1,4543,435,435,435
BEGIN DESCRIPTION:
TRIB 5_1 TO IRISH CREEK 7.0
END DESCRIPTION:
XS GIS Cut Line= 3
      2545874.98     13595874.98      2545575.00     13595625.00
      2544975.00     13595325.00
#Sta/Elev= 30
  4441.8  232.31  4445.0  232.31  4448.9  230.97  4455.4  231.03  4463.2  229.58
  4469.8  229.41  4477.6  227.61  4527.0  223.83  4704.1  217.26  4761.3  216.24
  4840.7  216.17  4846.3  219.77  4854.6  220.10  4863.0  218.81  4885.4  220.64
  4899.4  216.64  4907.8  215.84  4930.1  216.41  4944.1  217.79  4952.5  215.70
  4966.4  214.63  5024.0  214.66  5045.5  214.62  5045.8  214.12  5049.5  214.62
  5069.9  217.20  5086.6  216.97  5293.5  221.52  5427.6  225.50  5503.1  228.96
#Mann=4,-1,0
  4441.8    0.12       0  5024.0    0.04       0  5045.5    0.05       0
  5049.5    0.04       0
Bank Sta=5045.5,5049.5
Exp/Cntr=0.3,0.1

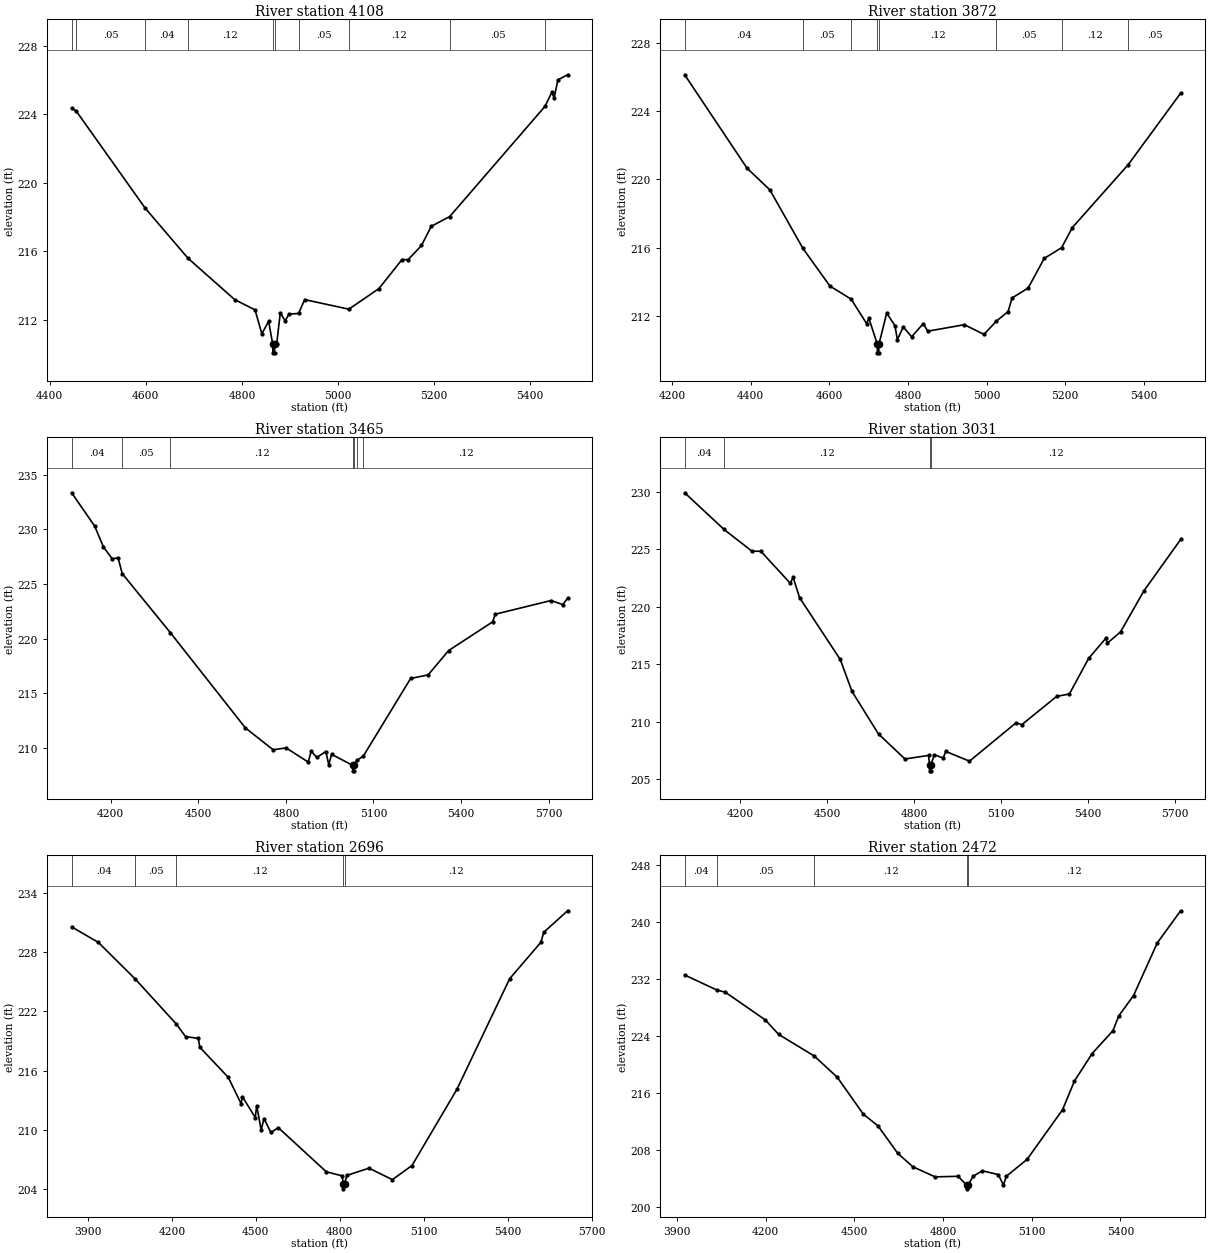
Type RM Length L Ch R = 1,4108,236,236,236
BEGIN DESCRIPTION:
TRIB 5_1 TO IRISH CREEK 6.0
END DESCRIPTION:
XS GIS Cut Line= 3
      2545975.01     13595475.01      2545675.00     13595175.00
      2545074.95     13595074.99
#Sta/Elev= 30
  4445.5  224.36  4455.3  224.18  4598.6  218.52  4687.9  215.59  4784.9  213.18
  4827.3  212.58  4841.5  211.18  4855.6  211.91  4864.2  210.57  4864.5  210.07
  4868.0  210.07  4868.2  210.57  4872.3  210.57  4879.9  212.41  4890.1  211.93
  4897.7  212.33  4918.0  212.37  4930.6  213.18  5022.6  212.62  5085.2  213.82
  5133.4  215.52  5146.0  215.51  5173.9  216.34  5194.2  217.46  5232.7  218.03
  5431.2  224.47  5445.1  225.28  5450.2  224.96  5457.8  226.01  5478.1  226.31
#Mann=10,-1,0
  4445.5    0.12       0  4455.3    0.05       0  4598.6    0.04       0
  4687.9    0.12       0  4864.2    0.05       0  4868.2    0.12       0
  4918.0    0.05       0  5022.6    0.12       0  5232.7    0.05       0
  5431.2    0.04       0
Bank Sta=4864.2,4868.2
Exp/Cntr=0.3,0.1

Type RM Length L Ch R = 1,3872,407,407,407
BEGIN DESCRIPTION:
Mapping XS e0929674
END DESCRIPTION:
XS GIS Cut Line= 3
      2546085.07     13595445.91      2545770.04     13594968.04
      2545095.55     13594825.29
#Sta/Elev= 30
  4231.8  226.14  4390.5  220.66  4448.5  219.39  4532.5  215.96  4601.3  213.75
  4655.3  212.98  4694.6  211.55  4700.6  211.85  4722.0  210.33  4722.2  209.83
  4725.7  209.83  4726.0  210.33  4745.8  212.16  4766.9  211.42  4772.9  210.60
  4788.0  211.35  4809.3  210.77  4838.9  211.55  4850.2  211.10  4943.5  211.48
  4993.3  210.91  5024.9  211.69  5054.6  212.25  5064.9  213.05  5105.7  213.63
  5146.6  215.37  5190.9  216.00  5218.2  217.18  5360.3  220.87  5493.6  225.06
#Mann=8,-1,0
  4231.8    0.04       0  4532.5    0.05       0  4655.3    0.12       0
  4722.0    0.05       0  4726.0    0.12       0  5024.9    0.05       0
  5190.9    0.12       0  5360.3    0.05       0
Bank Sta=4722,4726
Exp/Cntr=0.3,0.1

Type RM Length L Ch R = 1,3465,434,434,434
BEGIN DESCRIPTION:
Mapping XS c1c8709d
END DESCRIPTION:
XS GIS Cut Line= 3
      2546653.63     13594517.13      2545811.66     13594577.89
      2544958.27     13594521.58
#Sta/Elev= 30
  4065.9  233.35  4144.7  230.30  4174.8  228.39  4204.9  227.30  4224.9  227.40
  4239.1  225.95  4403.7  220.55  4661.3  211.81  4756.3  209.81  4800.9  209.98
  4876.6  208.68  4886.7  209.68  4905.9  209.11  4936.8  209.65  4946.8  208.46
  4956.8  209.39  5028.9  208.38  5029.2  207.88  5032.7  207.88  5032.9  208.38
  5043.4  208.84  5065.6  209.24  5227.4  216.34  5287.5  216.67  5357.7  218.90
  5508.0  221.52  5518.0  222.23  5708.4  223.48  5748.5  223.11  5765.3  223.68
#Mann=7,-1,0
  4065.9    0.04       0  4239.1    0.05       0  4403.7    0.12       0
  5028.9    0.05       0  5032.9    0.12       0  5043.4    0.05       0
  5065.6    0.12       0
Bank Sta=5028.9,5032.9
Exp/Cntr=0.3,0.1

Type RM Length L Ch R = 1,3031,335,335,335
BEGIN DESCRIPTION:
Mapping XS 5345a838
END DESCRIPTION:
XS GIS Cut Line= 3
      2546653.66     13594339.17      2545755.23     13594178.58
      2544958.30     13594239.22
#Sta/Elev= 30
  4008.2  229.91  4144.2  226.72  4240.5  224.83  4271.0  224.83  4372.5  222.05
  4382.7  222.55  4404.7  220.80  4545.2  215.42  4585.9  212.64  4677.3  208.94
  4768.7  206.77  4850.0  207.08  4853.5  206.24  4853.8  205.74  4857.3  205.74
  4857.5  206.24  4870.3  207.14  4900.8  206.85  4909.3  207.43  4991.3  206.58
  5151.8  209.91  5171.8  209.75  5292.2  212.21  5336.1  212.42  5402.5  215.51
  5462.2  217.27  5467.2  216.84  5512.8  217.82  5593.0  221.37  5720.1  225.85
#Mann=4,-1,0
  4008.2    0.04       0  4144.2    0.12       0  4853.5    0.05       0
  4857.5    0.12       0
Bank Sta=4853.5,4857.5
Exp/Cntr=0.3,0.1

Type RM Length L Ch R = 1,2696,224,224,224
BEGIN DESCRIPTION:
Mapping XS 6f2883de
END DESCRIPTION:
XS GIS Cut Line= 3
      2546818.65     13594100.47      2545720.51     13593879.11
      2545069.75     13593909.47
#Sta/Elev= 30
  3842.0  230.54  3937.5  228.97  4070.0  225.24  4215.1  220.74  4248.9  219.44
  4294.6  219.26  4299.7  218.37  4401.4  215.32  4447.1  212.67  4452.2  213.36
  4497.9  211.25  4503.0  212.46  4519.0  210.01  4529.2  211.14  4553.8  209.74
  4580.2  210.23  4751.9  205.76  4807.8  205.36  4812.8  204.54  4813.1  204.04
  4816.8  204.54  4825.0  205.40  4904.3  206.13  4987.8  204.97  5057.8  206.40
  5218.0  214.09  5406.8  225.30  5518.3  228.98  5528.4  229.99  5613.7  232.17
#Mann=5,-1,0
  3842.0    0.04       0  4070.0    0.05       0  4215.1    0.12       0
  4812.8    0.05       0  4816.8    0.12       0
Bank Sta=4812.8,4816.8
Exp/Cntr=0.3,0.1

Type RM Length L Ch R = 1,2472,508,508,508
BEGIN DESCRIPTION:
Mapping XS 5cf933b5
END DESCRIPTION:
XS GIS Cut Line= 3
      2546779.55     13593896.47      2545742.21     13593675.11
      2545125.94     13593662.09
#Sta/Elev= 30
  3926.5  232.57  4035.2  230.46  4064.1  230.15  4199.6  226.25  4244.0  224.24
  4365.0  221.19  4442.4  218.22  4530.9  213.03  4580.4  211.39  4646.9  207.55
  4698.0  205.66  4773.4  204.24  4851.4  204.32  4880.1  203.06  4880.3  202.56
  4884.1  203.06  4902.5  204.34  4933.2  205.09  4987.2  204.56  5004.4  203.09
  5014.4  204.33  5084.4  206.70  5204.5  213.67  5244.5  217.69  5304.5  221.55
  5374.5  224.74  5394.5  226.83  5444.5  229.69  5524.5  237.06  5603.6  241.58
#Mann=5,-1,0
  3926.5    0.04       0  4035.2    0.05       0  4365.0    0.12       0
  4880.1    0.05       0  4884.1    0.12       0
Bank Sta=4880.1,4884.1
Exp/Cntr=0.3,0.1

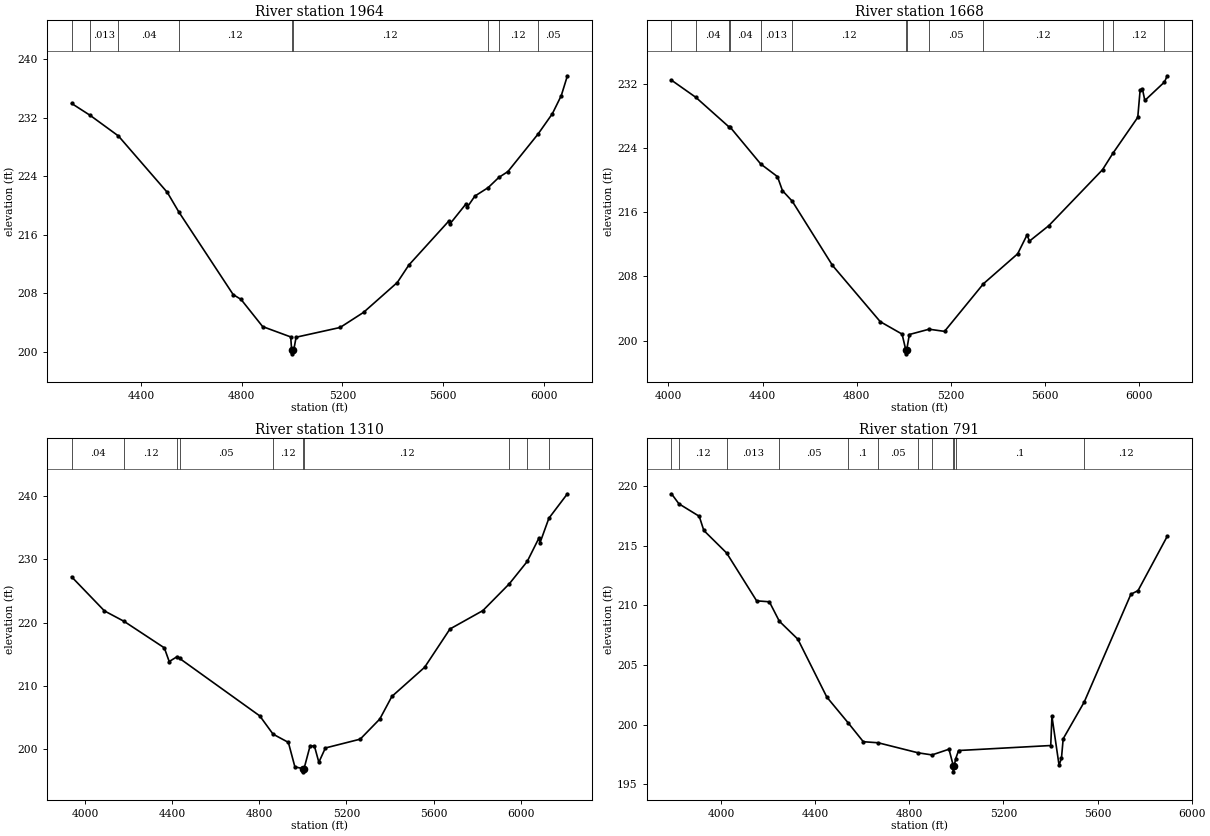
Type RM Length L Ch R = 1,1964,296,296,296
BEGIN DESCRIPTION:
Mapping XS 6de5e403
END DESCRIPTION:
XS GIS Cut Line= 3
      2546796.91     13593753.25      2546019.99     13593297.51
      2544960.98     13593141.26
#Sta/Elev= 30
  4123.3  233.95  4197.1  232.32  4309.3  229.51  4503.8  221.80  4549.0  219.16
  4765.6  207.85  4796.9  207.19  4882.8  203.48  4994.3  202.07  4998.1  200.26
  4998.3  199.76  5002.1  200.26  5006.6  200.32  5015.8  202.03  5190.8  203.36
  5283.9  205.42  5418.1  209.50  5463.7  211.87  5622.0  217.86  5627.0  217.48
  5691.6  220.25  5696.7  219.81  5726.5  221.30  5779.5  222.46  5821.5  223.84
  5857.9  224.65  5977.5  229.76  6034.7  232.55  6070.2  235.03  6094.5  237.73
#Mann=9,-1,0
  4123.3    0.05       0  4197.1   0.013       0  4309.3    0.04       0
  4549.0    0.12       0  4998.1    0.05       0  5002.1    0.12       0
  5779.5    0.05       0  5821.5    0.12       0  5977.5    0.05       0
Bank Sta=4998.1,5002.1
Exp/Cntr=0.3,0.1

Type RM Length L Ch R = 1,1668,358,358,358
BEGIN DESCRIPTION:
Mapping XS 3da70b13
END DESCRIPTION:
XS GIS Cut Line= 4
      2546914.08     13593692.47      2546315.13     13593106.54
      2545946.21     13592976.33      2545069.76     13592985.01
#Sta/Elev= 30
  4012.8  232.46  4115.9  230.33  4258.1  226.61  4261.0  226.64  4392.0  222.01
  4462.9  220.44  4484.2  218.69  4525.9  217.37  4696.4  209.38  4899.5  202.36
  4992.2  200.81  5007.9  198.85  5008.1  198.35  5011.9  198.85  5023.2  200.76
  5106.9  201.42  5172.5  201.15  5337.9  207.09  5483.1  210.82  5523.1  213.18
  5533.1  212.40  5615.5  214.33  5843.5  221.30  5887.4  223.34  5993.2  227.83
  6003.2  231.22  6013.2  231.34  6023.2  229.93  6106.6  232.23  6118.4  233.01
#Mann=13,-1,0
  4012.8    0.05       0  4115.9    0.04       0  4258.1   0.013       0
  4261.0    0.04       0  4392.0   0.013       0  4525.9    0.12       0
  5007.9    0.05       0  5011.9    0.12       0  5106.9    0.05       0
  5337.9    0.12       0  5843.5    0.05       0  5887.4    0.12       0
  6106.6    0.04       0
Bank Sta=5007.9,5011.9
Exp/Cntr=0.3,0.1

Type RM Length L Ch R = 1,1310,519,519,519
BEGIN DESCRIPTION:
Mapping XS 5acc0dbf
END DESCRIPTION:
XS GIS Cut Line= 4
      2546879.36     13593553.57      2546462.70     13592746.29
      2545907.14     13592728.93      2545099.89     13592837.43
#Sta/Elev= 30
  3936.7  227.20  4087.5  221.83  4177.5  220.19  4362.7  216.01  4385.2  213.85
  4421.8  214.63  4432.8  214.35  4801.6  205.28  4862.5  202.41  4932.9  201.11
  4962.9  197.25  5000.9  196.97  5001.2  196.47  5004.9  196.97  5033.0  200.59
  5053.0  200.49  5073.0  197.98  5103.0  200.23  5263.1  201.62  5353.1  204.79
  5408.6  208.35  5559.3  212.95  5675.6  218.98  5826.9  221.88  5948.4  226.10
  6030.7  229.62  6084.4  233.30  6089.5  232.56  6130.3  236.43  6215.5  240.29
#Mann=10,-1,0
  3936.7    0.04       0  4177.5    0.12       0  4421.8   0.013       0
  4432.8    0.05       0  4862.5    0.12       0  5000.9    0.05       0
  5004.9    0.12       0  5948.4    0.05       0  6030.7    0.03       0
  6130.3    0.05       0
Bank Sta=5000.9,5004.9
Exp/Cntr=0.3,0.1

Type RM Length L Ch R = 1,791,0,0,0
BEGIN DESCRIPTION:
4842
END DESCRIPTION:
XS GIS Cut Line= 4
      2546820.80     13593343.67      2546623.86     13592827.87
      2546605.10     13592302.71      2545593.02     13592490.14
#Sta/Elev= 30
  3789.3  219.38  3820.8  218.54  3907.3  217.49  3926.7  216.30  4023.6  214.41
  4151.2  210.39  4205.3  210.31  4247.6  208.68  4326.3  207.17  4449.4  202.31
  4540.7  200.13  4604.5  198.56  4667.8  198.47  4836.8  197.63  4896.5  197.45
  4968.7  197.93  4987.1  196.53  4987.3  196.03  4991.1  196.53  4997.1  197.13
  5009.4  197.82  5401.1  198.24  5406.2  200.69  5436.5  196.58  5446.7  197.18
  5454.0  198.81  5543.3  201.89  5741.6  210.94  5772.1  211.25  5896.2  215.81
#Mann=12,-1,0
  3789.3    0.04       0  3820.8    0.12       0  4023.6   0.013       0
  4247.6    0.05       0  4540.7     0.1       0  4667.8    0.05       0
  4836.8   0.013       0  4896.5    0.05       0  4987.1    0.05       0
  4991.1    0.05       0  4997.1     0.1       0  5543.3    0.12       0
Bank Sta=4987.1,4991.1
Exp/Cntr=0.3,0.1

Chan Stop Cuts=-1