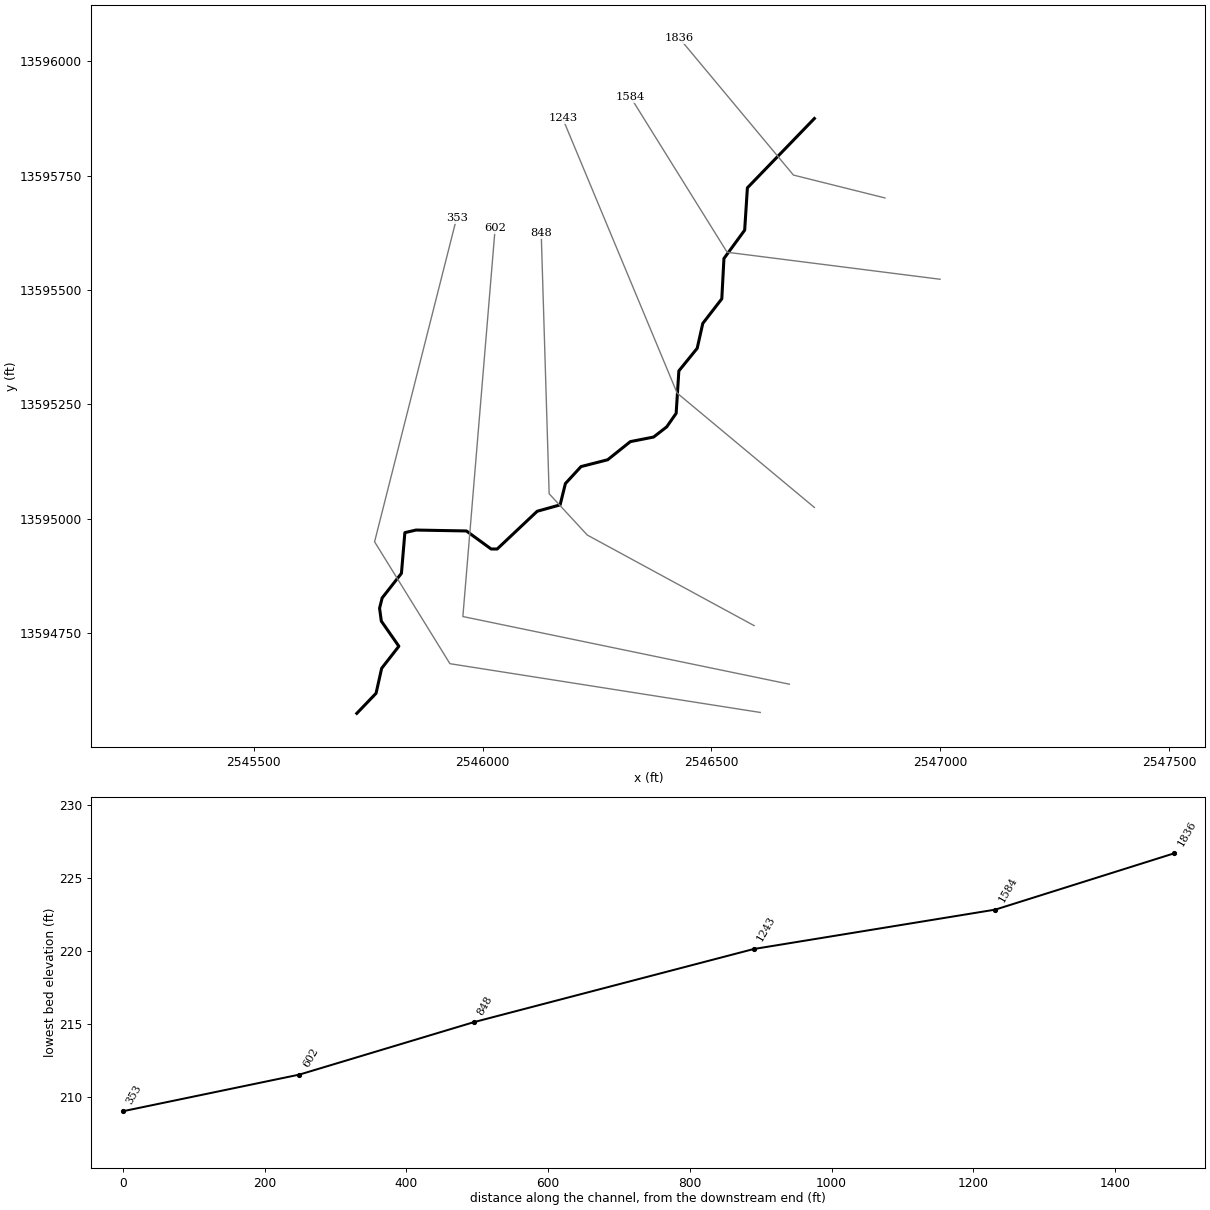
--- TRIB 5_1_1 TO IRISH CREEK.prj (project) ---

Proj Title=TRIB 5_1_1 TO IRISH CREEK Base Level Engineering
Current Plan=p01
Default Exp/Contr=0.3,0.1
English Units
Geom File=g01
Flow File=f01
Plan File=p01
BEGIN DESCRIPTION:
TRIB 5_1_1 TO IRISH CREEK
END DESCRIPTION:

--- TRIB 5_1_1 TO IRISH CREEK.p01 (plan) ---

Plan Title=Multiple Run
Short Identifier=Multiple
Geom File=g01
Flow File=f01
Subcritical Flow
K Sum by GR= 0
Std Step Tol= 0.01
Critical Tol= 0.01
Num of Std Step Trials= 20
Max Error Tol= 0.3
Flow Tol Ratio= 0.001
Split Flow NTrial= 30
Split Flow Tol= 0.02
Split Flow Ratio= 0.02
Log Output Level= 0
Friction Slope Method= 1
Unsteady Friction Slope Method= 2
Unsteady Bridges Friction Slope Method= 1
Parabolic Critical Depth
Global Vel Dist=  1 , 1 , 1
Global Log Level= 0
CheckData=True
Encroach Param= -1, 0, 0, 0
BEGIN DESCRIPTION:
Multiple Run
END DESCRIPTION:

--- TRIB 5_1_1 TO IRISH CREEK.f01 (steady flow) ---

Flow Title=Multiple
Number of Profiles=7
Profile Names=10-year,25-year,50-year,1pct_min,100-year,1pct_plu,500-year
River Rch & RM= TRIB 5_1_1 TO IR,Reach-1,1836
     253     385     498     314     626    1249     976
Boundary for River Rch & Prof#=TRIB 5_1_1 TO IR,Reach-1,1
Up Type=0
Dn Type=3
Dn Slope=0.005
Boundary for River Rch & Prof#=TRIB 5_1_1 TO IR,Reach-1,2
Up Type=0
Dn Type=3
Dn Slope=0.005
Boundary for River Rch & Prof#=TRIB 5_1_1 TO IR,Reach-1,3
Up Type=0
Dn Type=3
Dn Slope=0.005
Boundary for River Rch & Prof#=TRIB 5_1_1 TO IR,Reach-1,4
Up Type=0
Dn Type=3
Dn Slope=0.005
Boundary for River Rch & Prof#=TRIB 5_1_1 TO IR,Reach-1,5
Up Type=0
Dn Type=3
Dn Slope=0.005
Boundary for River Rch & Prof#=TRIB 5_1_1 TO IR,Reach-1,6
Up Type=0
Dn Type=3
Dn Slope=0.005
Boundary for River Rch & Prof#=TRIB 5_1_1 TO IR,Reach-1,7
Up Type=0
Dn Type=3
Dn Slope=0.005

--- TRIB 5_1_1 TO IRISH CREEK.g01 (geometry) ---

Geom Title=Existing Conditions

River Reach=TRIB 5_1_1 TO IR,Reach-1
Reach XY= 30
      2546725.00     13595875.00      2546578.61     13595723.51
      2546572.64     13595630.98      2546527.35     13595569.03
      2546522.67     13595480.97      2546481.11     13595427.18
      2546468.89     13595372.82      2546428.83     13595323.41
      2546422.93     13595230.71      2546402.28     13595201.10
      2546373.61     13595178.85      2546322.84     13595168.89
      2546273.24     13595129.20      2546215.02     13595114.31
      2546180.89     13595077.21      2546169.37     13595030.65
      2546119.25     13595016.68      2546031.73     13594934.15
      2546018.47     13594934.29      2545964.55     13594973.63
      2545854.42     13594975.63      2545830.08     13594969.98
      2545822.58     13594881.06      2545780.40     13594827.18
      2545774.79     13594804.79      2545778.61     13594776.64
      2545816.95     13594721.69      2545779.33     13594673.42
      2545767.12     13594618.86      2545725.00     13594575.00

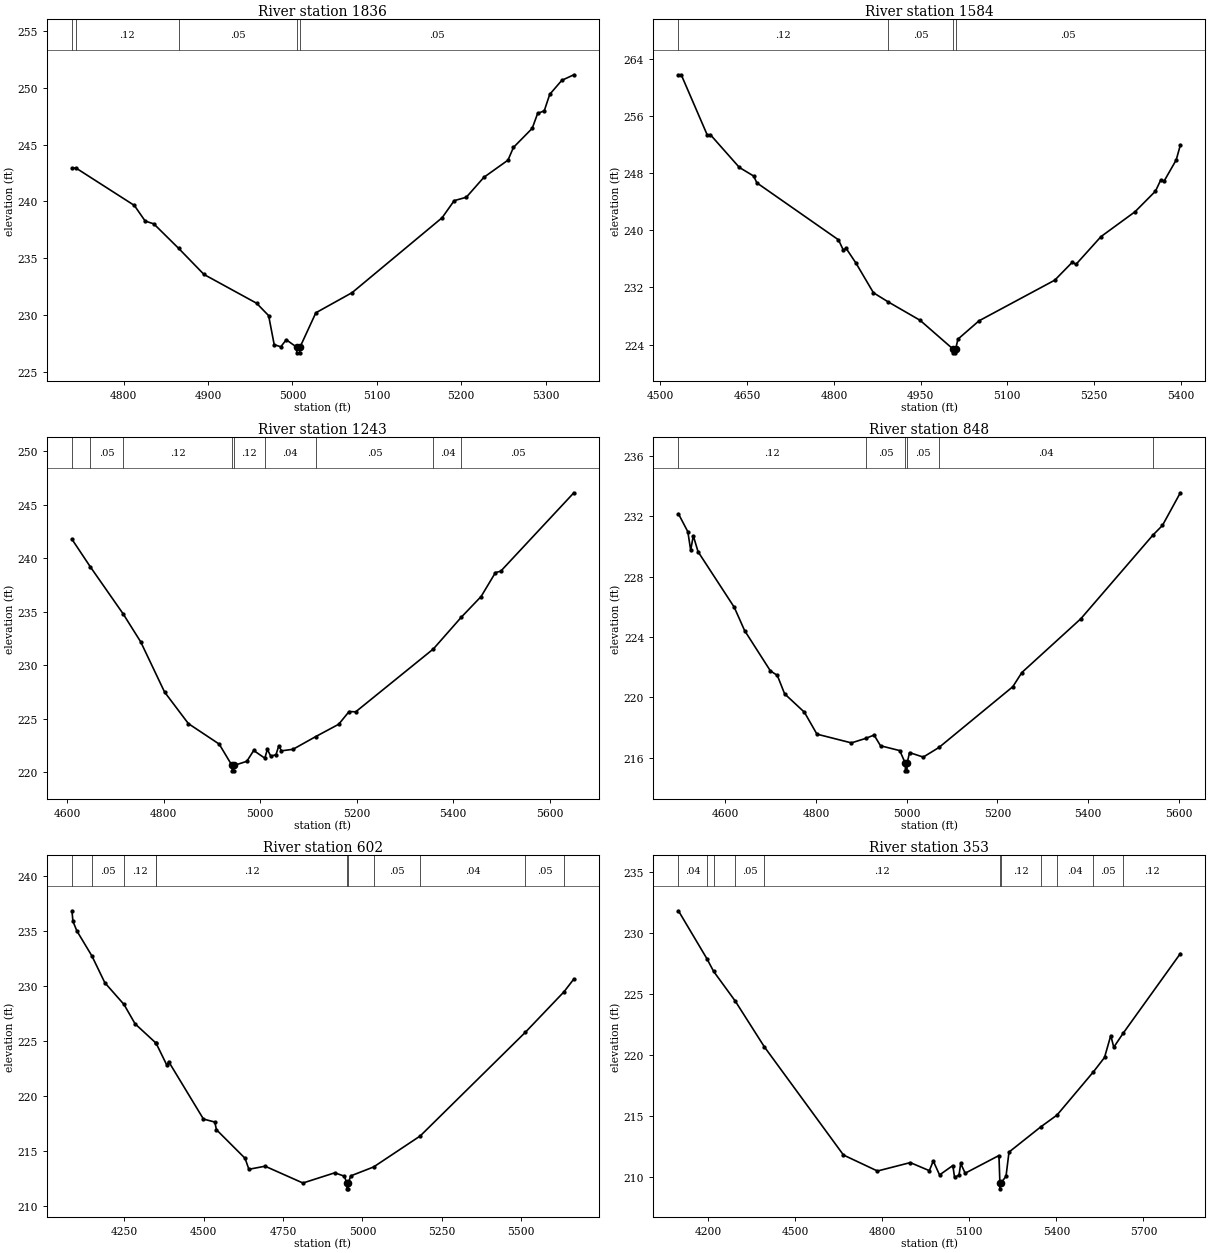
Type RM Length L Ch R = 1,1836,252,252,252
BEGIN DESCRIPTION:
TRIB 5_1-1 TO IRISH CREEK 3.0
END DESCRIPTION:
XS GIS Cut Line= 3
      2546879.18     13595701.39      2546679.17     13595751.39
      2546430.18     13596050.18
#Sta/Elev= 30
  4738.5  242.94  4743.4  242.93  4812.5  239.65  4825.3  238.28  4835.6  238.03
  4865.0  235.88  4895.0  233.59  4957.4  231.06  4971.7  229.97  4978.3  227.42
  4986.1  227.23  4992.6  227.85  5004.9  227.20  5005.1  226.70  5008.6  226.70
  5008.9  227.20  5027.7  230.22  5070.7  231.99  5177.4  238.57  5191.7  240.07
  5206.1  240.37  5226.9  242.12  5255.5  243.63  5262.0  244.75  5284.2  246.42
  5290.7  247.74  5298.5  247.96  5305.0  249.41  5319.3  250.64  5333.6  251.13
#Mann=5,-1,0
  4738.5    0.05       0  4743.4    0.12       0  4865.0    0.05       0
  5004.9    0.05       0  5008.9    0.05       0
Bank Sta=5004.9,5008.9
Exp/Cntr=0.3,0.1

Type RM Length L Ch R = 1,1584,341,341,341
BEGIN DESCRIPTION:
Mapping XS f00dff0f
END DESCRIPTION:
XS GIS Cut Line= 3
      2546999.61     13595523.69      2546534.29     13595582.72
      2546323.42     13595921.50
#Sta/Elev= 30
  4531.1  261.77  4536.0  261.77  4581.2  253.30  4586.2  253.40  4636.5  248.80
  4661.2  247.60  4666.8  246.64  4807.9  238.67  4816.3  237.24  4821.3  237.46
  4838.2  235.41  4868.4  231.26  4893.5  230.00  4949.0  227.41  5006.5  223.35
  5006.7  222.85  5010.2  222.85  5010.5  223.35  5014.6  224.77  5051.0  227.33
  5182.0  233.02  5212.7  235.56  5218.6  235.22  5262.0  239.12  5320.9  242.60
  5356.2  245.48  5365.0  246.98  5370.8  246.84  5392.1  249.85  5399.2  251.92
#Mann=4,-1,0
  4531.1    0.12       0  4893.5    0.05       0  5006.5    0.05       0
  5010.5    0.05       0
Bank Sta=5006.5,5010.5
Exp/Cntr=0.3,0.1

Type RM Length L Ch R = 1,1243,395,395,395
BEGIN DESCRIPTION:
TRIB 5_1-1 TO IRISH CREEK 2.0
END DESCRIPTION:
XS GIS Cut Line= 3
      2546724.96     13595025.03      2546425.00     13595275.00
      2546174.99     13595875.03
#Sta/Elev= 30
  4609.6  241.78  4647.3  239.23  4715.6  234.82  4752.1  232.20  4801.6  227.51
  4851.0  224.56  4914.8  222.65  4941.4  220.65  4941.7  220.15  4945.2  220.15
  4945.4  220.65  4972.1  221.04  4986.4  222.05  5009.5  221.33  5014.7  222.16
  5021.7  221.52  5032.6  221.66  5038.5  222.50  5043.9  222.02  5067.8  222.16
  5115.0  223.35  5162.6  224.50  5184.2  225.69  5197.8  225.66  5359.0  231.54
  5416.8  234.50  5457.8  236.43  5487.6  238.67  5498.4  238.79  5650.1  246.12
#Mann=9,-1,0
  4609.6    0.12       0  4647.3    0.05       0  4715.6    0.12       0
  4941.4    0.05       0  4945.4    0.12       0  5009.5    0.04       0
  5115.0    0.05       0  5359.0    0.04       0  5416.8    0.05       0
Bank Sta=4941.4,4945.4
Exp/Cntr=0.3,0.1

Type RM Length L Ch R = 1,848,246,246,246
BEGIN DESCRIPTION:
Mapping XS 2648e292
END DESCRIPTION:
XS GIS Cut Line= 4
      2546593.29     13594766.76      2546228.74     13594964.66
      2546145.40     13595054.94      2546128.04     13595624.41
#Sta/Elev= 30
  4496.3  232.16  4517.1  230.97  4523.4  229.74  4529.1  230.71  4539.6  229.65
  4619.5  225.97  4642.3  224.43  4699.2  221.76  4714.5  221.46  4730.6  220.24
  4774.3  219.02  4801.9  217.57  4878.0  216.99  4909.7  217.29  4928.0  217.51
  4942.2  216.80  4984.7  216.48  4996.9  215.64  4997.1  215.14  5000.6  215.14
  5000.9  215.64  5006.2  216.35  5036.5  216.05  5071.3  216.69  5234.1  220.71
  5254.1  221.65  5384.2  225.21  5543.3  230.75  5564.3  231.39  5603.7  233.55
#Mann=6,-1,0
  4496.3    0.12       0  4909.7    0.05       0  4996.9    0.05       0
  5000.9    0.05       0  5071.3    0.04       0  5543.3    0.05       0
Bank Sta=4996.9,5000.9
Exp/Cntr=0.3,0.1

Type RM Length L Ch R = 1,602,249,249,249
BEGIN DESCRIPTION:
TRIB 5_1-1 TO IRISH CREEK 1.0
END DESCRIPTION:
XS GIS Cut Line= 3
      2546670.29     13594638.79      2545956.82     13594786.62
      2546027.34     13595634.77
#Sta/Elev= 30
  4085.9  236.86  4089.0  235.90  4101.5  235.02  4148.7  232.75  4189.4  230.31
  4249.8  228.33  4284.6  226.57  4349.5  224.84  4350.7  224.81  4385.0  222.78
  4390.1  223.14  4499.8  217.90  4535.5  217.63  4540.7  216.93  4630.7  214.33
  4642.8  213.33  4693.8  213.61  4812.9  212.08  4913.2  213.01  4943.3  212.70
  4951.4  212.05  4951.6  211.55  4955.1  211.55  4955.4  212.05  4963.4  212.73
  5035.3  213.54  5181.9  216.36  5512.6  225.79  5634.4  229.48  5665.6  230.65
#Mann=11,-1,0
  4085.9    0.12       0  4148.7    0.05       0  4249.8    0.12       0
  4349.5    0.05       0  4350.7    0.12       0  4951.4    0.05       0
  4955.4    0.12       0  5035.3    0.05       0  5181.9    0.04       0
  5512.6    0.05       0  5634.4    0.12       0
Bank Sta=4951.4,4955.4
Exp/Cntr=0.3,0.1

Type RM Length L Ch R = 1,353,0,0,0
BEGIN DESCRIPTION:
LGII4040
END DESCRIPTION:
XS GIS Cut Line= 4
      2546606.76     13594577.01      2545928.59     13594683.58
      2545763.89     13594949.99      2545943.12     13595657.23
#Sta/Elev= 30
  4097.9  231.82  4195.9  227.90  4219.1  226.86  4293.8  224.42  4393.8  220.68
  4666.6  211.81  4783.7  210.50  4896.8  211.19  4962.4  210.53  4976.0  211.32
  4997.7  210.18  5043.4  210.95  5049.3  209.99  5064.7  210.16  5070.5  211.12
  5085.9  210.32  5202.3  211.77  5205.5  209.54  5205.7  209.04  5209.5  209.54
  5226.6  210.06  5236.9  212.05  5346.5  214.12  5402.2  215.08  5527.6  218.62
  5566.0  219.80  5587.6  221.60  5597.9  220.64  5630.0  221.78  5827.2  228.31
#Mann=11,-1,0
  4097.9    0.04       0  4195.9    0.05       0  4219.1    0.12       0
  4293.8    0.05       0  4393.8    0.12       0  5205.5    0.05       0
  5209.5    0.12       0  5346.5    0.05       0  5402.2    0.04       0
  5527.6    0.05       0  5630.0    0.12       0
Bank Sta=5205.5,5209.5
Exp/Cntr=0.3,0.1

Chan Stop Cuts=-1