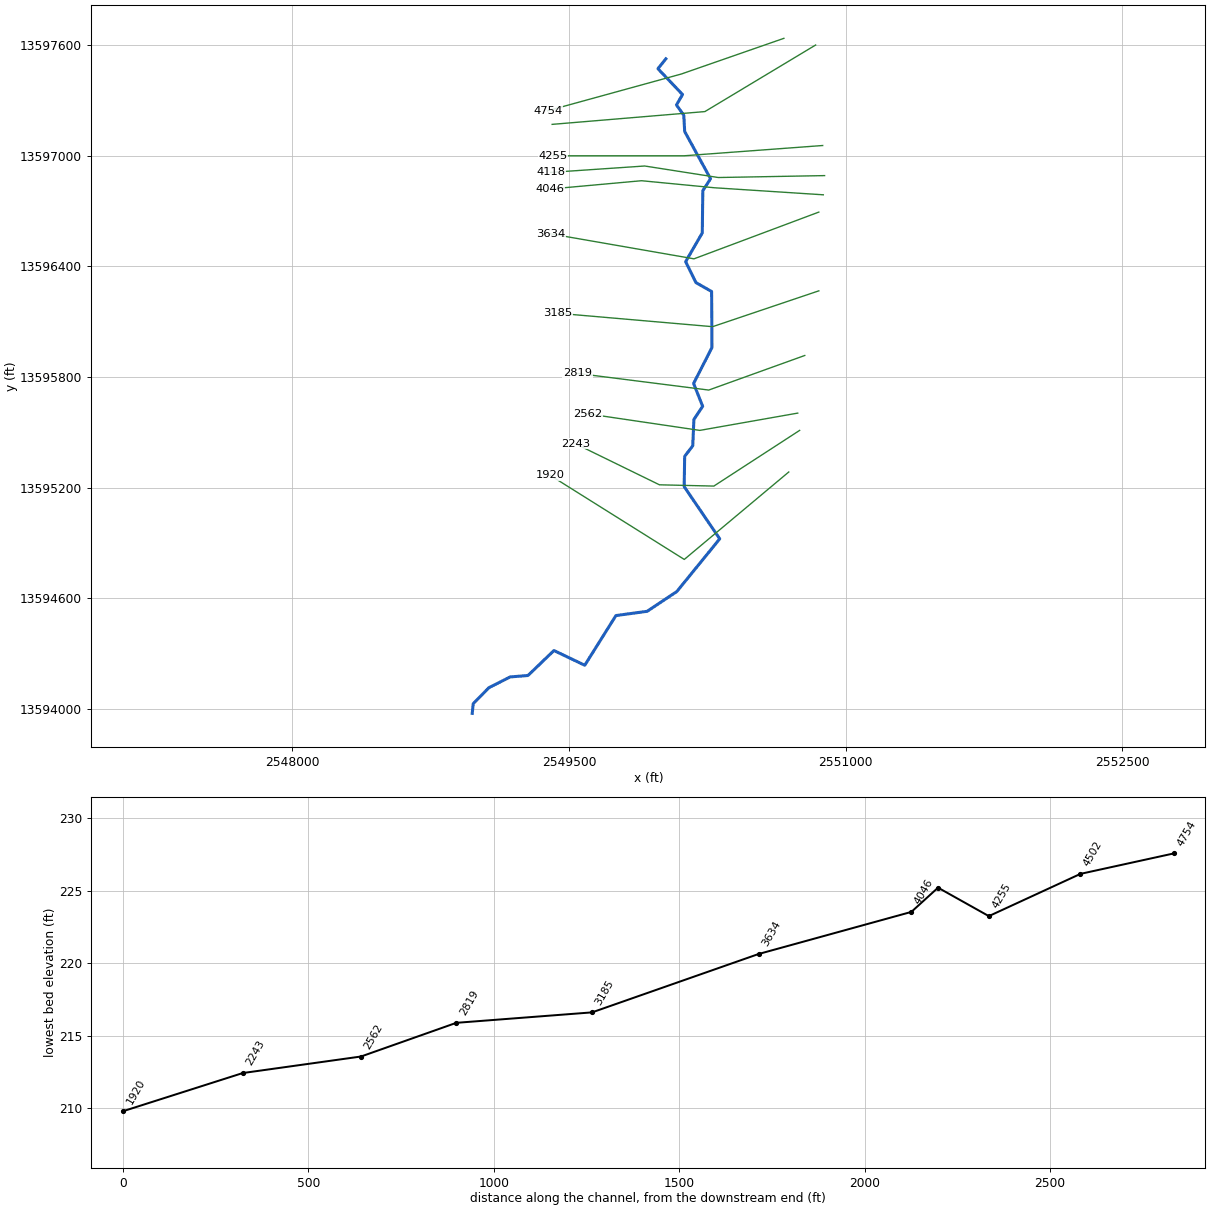
--- TRIB 5_2 TO IRISH CREEK.prj (project) ---

Proj Title=TRIB 5_2 TO IRISH CREEK Base Level Engineering
Current Plan=p01
Default Exp/Contr=0.3,0.1
English Units
Geom File=g01
Flow File=f01
Plan File=p01
BEGIN DESCRIPTION:
TRIB 5_2 TO IRISH CREEK
END DESCRIPTION:

--- TRIB 5_2 TO IRISH CREEK.p01 (plan) ---

Plan Title=Multiple Run
Short Identifier=Multiple
Geom File=g01
Flow File=f01
Subcritical Flow
K Sum by GR= 0
Std Step Tol= 0.01
Critical Tol= 0.01
Num of Std Step Trials= 20
Max Error Tol= 0.3
Flow Tol Ratio= 0.001
Split Flow NTrial= 30
Split Flow Tol= 0.02
Split Flow Ratio= 0.02
Log Output Level= 0
Friction Slope Method= 1
Unsteady Friction Slope Method= 2
Unsteady Bridges Friction Slope Method= 1
Parabolic Critical Depth
Global Vel Dist=  1 , 1 , 1
Global Log Level= 0
CheckData=True
Encroach Param= -1, 0, 0, 0
BEGIN DESCRIPTION:
Multiple Run
END DESCRIPTION:

--- TRIB 5_2 TO IRISH CREEK.f01 (steady flow) ---

Flow Title=Multiple
Number of Profiles=7
Profile Names=10-year,25-year,50-year,1pct_min,100-year,1pct_plu,500-year
River Rch & RM= TRIB 5_2 TO IRIS,Reach-1,4754
     501     797    1060     685    1367    2728    2248
River Rch & RM= TRIB 5_2 TO IRIS,Reach-1,3634
     639    1027    1377     895    1786    3563    2972
Boundary for River Rch & Prof#=TRIB 5_2 TO IRIS,Reach-1,1
Up Type=0
Dn Type=3
Dn Slope=0.005
Boundary for River Rch & Prof#=TRIB 5_2 TO IRIS,Reach-1,2
Up Type=0
Dn Type=3
Dn Slope=0.005
Boundary for River Rch & Prof#=TRIB 5_2 TO IRIS,Reach-1,3
Up Type=0
Dn Type=3
Dn Slope=0.005
Boundary for River Rch & Prof#=TRIB 5_2 TO IRIS,Reach-1,4
Up Type=0
Dn Type=3
Dn Slope=0.005
Boundary for River Rch & Prof#=TRIB 5_2 TO IRIS,Reach-1,5
Up Type=0
Dn Type=3
Dn Slope=0.005
Boundary for River Rch & Prof#=TRIB 5_2 TO IRIS,Reach-1,6
Up Type=0
Dn Type=3
Dn Slope=0.005
Boundary for River Rch & Prof#=TRIB 5_2 TO IRIS,Reach-1,7
Up Type=0
Dn Type=3
Dn Slope=0.005

--- TRIB 5_2 TO IRISH CREEK.g01 (geometry) ---

Geom Title=Existing Conditions

River Reach=TRIB 5_2 TO IRIS,Reach-1
Reach XY= 30
      2550025.00     13597525.00      2549982.25     13597471.67
      2550115.70     13597331.67      2550082.80     13597275.10
      2550122.46     13597219.11      2550127.33     13597130.97
      2550267.47     13596875.01      2550225.66     13596809.84
      2550222.76     13596580.93      2550132.50     13596425.00
      2550188.53     13596311.47      2550273.36     13596263.17
      2550275.44     13595959.82      2550175.75     13595764.31
      2550224.90     13595640.40      2550177.30     13595569.07
      2550171.21     13595426.57      2550127.26     13595369.06
      2550124.57     13595204.82      2550317.39     13594921.67
      2550084.68     13594635.78      2549923.53     13594528.55
      2549754.45     13594505.55      2549585.37     13594235.95
      2549418.27     13594315.89      2549277.43     13594180.52
      2549180.97     13594172.67      2549065.29     13594114.26
      2548980.30     13594027.54      2548975.00     13593975.00

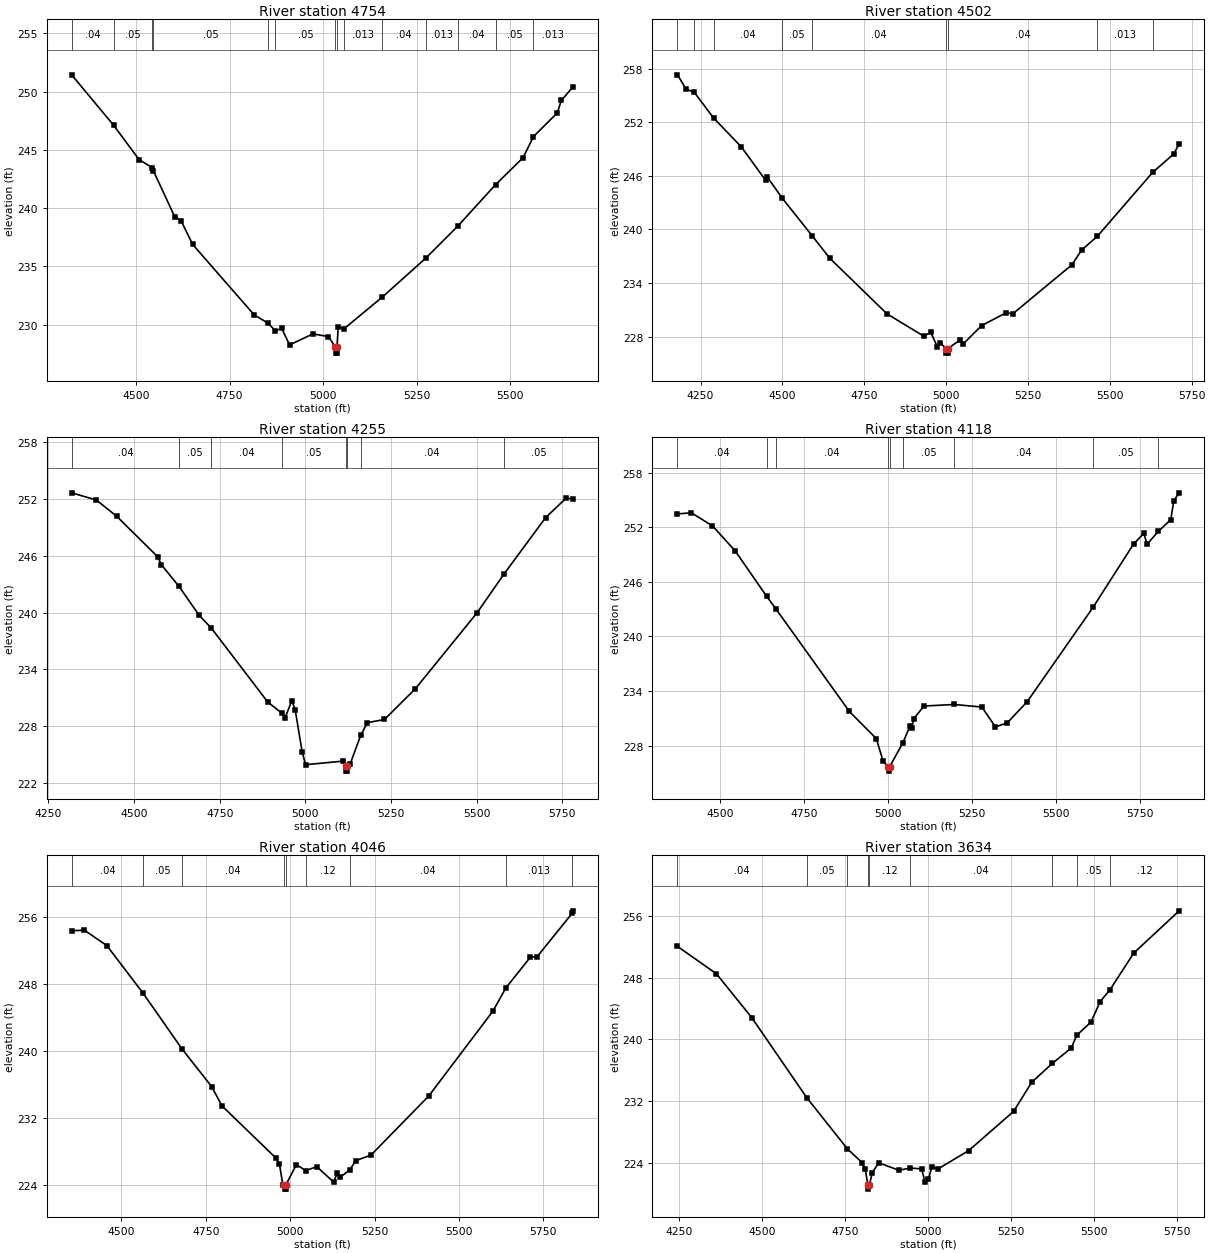
Type RM Length L Ch R = 1,4754,252,252,252
BEGIN DESCRIPTION:
TRIB 5_2 TO IRISH CREEK 6.0
END DESCRIPTION:
XS GIS Cut Line= 3
      2550665.40     13597636.37      2550109.36     13597442.96
      2549384.00     13597243.49
#Sta/Elev= 30
  4327.8  251.45  4440.1  247.12  4508.2  244.17  4543.2  243.48  4546.3  243.22
  4603.5  239.26  4620.3  238.93  4651.4  236.89  4815.3  230.86  4852.7  230.13
  4872.5  229.48  4889.4  229.68  4910.5  228.27  4972.9  229.21  5014.4  228.98
  5033.1  228.06  5033.4  227.56  5036.9  227.56  5037.1  228.06  5040.6  229.82
  5056.3  229.66  5157.6  232.35  5274.4  235.71  5360.1  238.46  5461.3  242.03
  5534.6  244.34  5562.5  246.15  5626.3  248.19  5636.7  249.25  5668.8  250.44
#Mann=14,-1,0
  4327.8    0.04       0  4440.1    0.05       0  4543.2    0.12       0
  4546.3    0.05       0  4852.7    0.04       0  4872.5    0.05       0
  5033.1    0.05       0  5037.1    0.05       0  5056.3   0.013       0
  5157.6    0.04       0  5274.4   0.013       0  5360.1    0.04       0
  5461.3    0.05       0  5562.5   0.013       0
Bank Sta=5033.1,5037.1
Exp/Cntr=0.3,0.1

Type RM Length L Ch R = 1,4502,247,247,247
BEGIN DESCRIPTION:
Mapping XS e0eb3f80
END DESCRIPTION:
XS GIS Cut Line= 3
      2550837.65     13597600.19      2550236.94     13597239.07
      2549408.53     13597169.74
#Sta/Elev= 30
  4179.6  257.32  4206.0  255.71  4230.5  255.38  4290.0  252.48  4374.6  249.25
  4448.5  245.52  4454.3  245.85  4499.0  243.53  4590.8  239.30  4644.7  236.78
  4819.5  230.55  4932.6  228.03  4952.7  228.51  4972.8  226.89  4982.8  227.27
  5000.9  226.65  5001.1  226.15  5004.6  226.15  5004.9  226.65  5043.0  227.62
  5053.0  227.21  5108.7  229.24  5183.5  230.67  5203.6  230.55  5384.2  236.04
  5414.3  237.71  5461.9  239.23  5630.9  246.39  5695.3  248.46  5711.8  249.58
#Mann=9,-1,0
  4179.6    0.04       0  4230.5    0.05       0  4290.0    0.04       0
  4499.0    0.05       0  4590.8    0.04       0  5000.9    0.04       0
  5004.9    0.04       0  5461.9   0.013       0  5630.9    0.05       0
Bank Sta=5000.9,5004.9
Exp/Cntr=0.3,0.1

Type RM Length L Ch R = 1,4255,137,137,137
BEGIN DESCRIPTION:
Mapping XS e9463ffc
END DESCRIPTION:
XS GIS Cut Line= 3
      2550875.81     13597055.04      2550125.83     13596999.48
      2549414.07     13596999.48
#Sta/Elev= 30
  4317.9  252.66  4390.0  251.90  4449.1  250.19  4569.4  245.89  4579.4  245.08
  4631.4  242.76  4689.7  239.73  4725.8  238.35  4890.3  230.54  4930.9  229.38
  4940.4  228.84  4960.5  230.70  4970.5  229.68  4990.5  225.30  5000.6  223.92
  5110.8  224.30  5118.8  223.74  5119.0  223.24  5122.5  223.24  5122.8  223.74
  5130.8  224.00  5161.5  227.03  5180.8  228.36  5230.8  228.70  5320.8  231.94
  5500.8  239.97  5579.1  244.05  5700.8  250.03  5760.8  252.10  5781.7  252.01
#Mann=8,-1,0
  4317.9    0.04       0  4631.4    0.05       0  4725.8    0.04       0
  4930.9    0.05       0  5118.8    0.05       0  5122.8    0.05       0
  5161.5    0.04       0  5579.1    0.05       0
Bank Sta=5118.8,5122.8
Exp/Cntr=0.3,0.1

Type RM Length L Ch R = 1,4118,72,72,72
BEGIN DESCRIPTION:
Mapping XS b395bd14
END DESCRIPTION:
XS GIS Cut Line= 4
      2550886.23     13596891.84      2550309.86     13596881.43
      2549910.55     13596943.93      2549400.16     13596909.21
#Sta/Elev= 30
  4373.4  253.45  4414.6  253.58  4477.5  252.14  4544.7  249.41  4638.2  244.42
  4666.6  243.00  4884.7  231.75  4964.9  228.77  4985.1  226.29  5000.8  225.70
  5001.1  225.20  5004.8  225.70  5043.1  228.25  5065.5  230.19  5070.6  229.99
  5076.2  230.95  5106.6  232.35  5196.6  232.52  5278.7  232.24  5319.2  230.06
  5354.0  230.49  5413.3  232.81  5609.7  243.20  5730.5  250.17  5760.5  251.31
  5770.5  250.13  5803.5  251.53  5840.7  252.83  5849.8  254.90  5865.6  255.77
#Mann=9,-1,0
  4373.4    0.04       0  4638.2    0.05       0  4666.6    0.04       0
  5000.8    0.04       0  5004.8    0.04       0  5043.1    0.05       0
  5196.6    0.04       0  5609.7    0.05       0  5803.5   0.013       0
Bank Sta=5000.8,5004.8
Exp/Cntr=0.3,0.1

Type RM Length L Ch R = 1,4046,412,412,412
BEGIN DESCRIPTION:
Mapping XS 05aba1ee
END DESCRIPTION:
XS GIS Cut Line= 4
      2550879.30     13596787.68      2550289.02     13596825.87
      2549893.19     13596864.07      2549398.31     13596819.08
#Sta/Elev= 30
  4352.7  254.39  4390.4  254.46  4457.2  252.61  4565.0  246.90  4679.4  240.29
  4767.9  235.76  4797.9  233.48  4958.3  227.23  4968.3  226.53  4978.4  224.05
  4983.3  224.03  4983.6  223.53  4987.1  223.53  4987.3  224.03  5018.6  226.45
  5046.5  225.74  5078.9  226.22  5129.1  224.36  5139.1  225.44  5149.2  224.97
  5176.3  225.82  5194.9  226.94  5239.6  227.60  5410.4  234.64  5601.1  244.81
  5639.3  247.57  5711.6  251.23  5731.7  251.29  5836.4  256.52  5838.8  256.77
#Mann=9,-1,0
  4352.7    0.04       0  4565.0    0.05       0  4679.4    0.04       0
  4983.3    0.04       0  4987.3    0.04       0  5046.5    0.12       0
  5176.3    0.04       0  5639.3   0.013       0  5836.4    0.05       0
Bank Sta=4983.3,4987.3
Exp/Cntr=0.3,0.1

Type RM Length L Ch R = 1,3634,449,449,449
BEGIN DESCRIPTION:
Mapping XS 84bedab9
END DESCRIPTION:
XS GIS Cut Line= 3
      2550855.02     13596693.94      2550177.91     13596440.46
      2549400.11     13596575.88
#Sta/Elev= 30
  4244.4  252.03  4361.9  248.48  4468.6  242.80  4634.0  232.47  4756.9  225.83
  4801.3  224.05  4810.3  223.22  4818.9  221.13  4819.1  220.63  4822.9  221.13
  4831.7  222.76  4851.2  224.04  4911.7  223.07  4945.9  223.36  4980.5  223.25
  4990.7  221.56  5000.8  221.89  5011.0  223.45  5031.3  223.28  5122.6  225.62
  5257.9  230.69  5312.5  234.46  5374.9  236.90  5431.7  238.89  5448.3  240.53
  5491.3  242.25  5518.5  244.86  5548.6  246.43  5620.0  251.16  5756.9  256.63
#Mann=9,-1,0
  4244.4    0.04       0  4634.0    0.05       0  4756.9    0.12       0
  4818.9    0.04       0  4822.9    0.12       0  4945.9    0.04       0
  5374.9   0.013       0  5448.3    0.05       0  5548.6    0.12       0
Bank Sta=4818.9,4822.9
Exp/Cntr=0.3,0.1

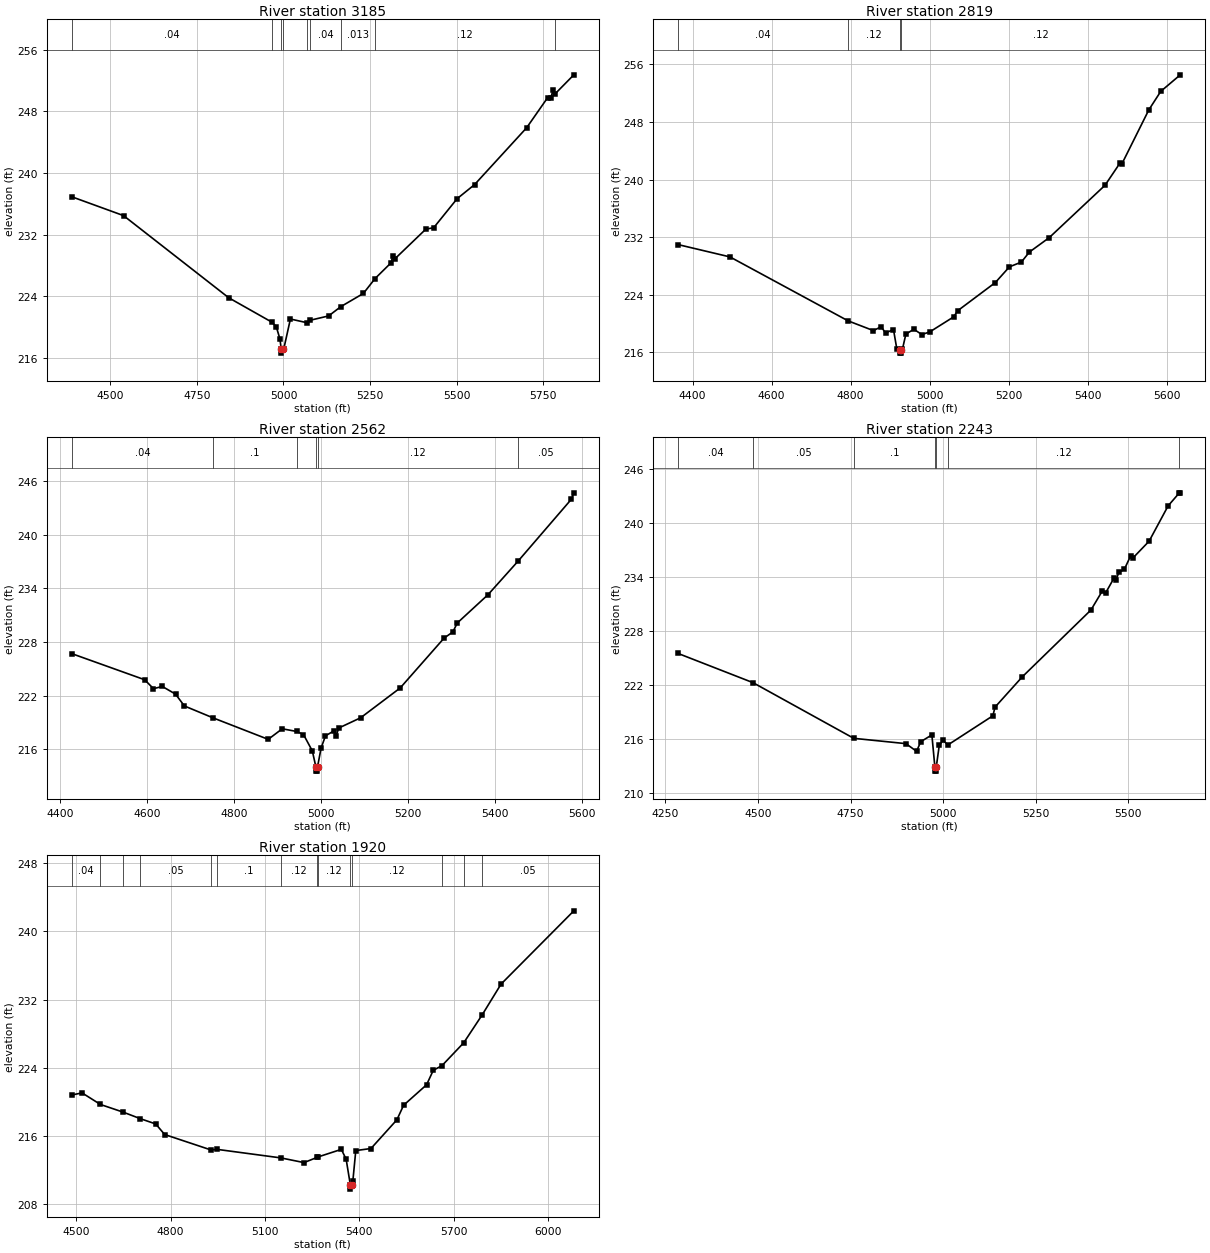
Type RM Length L Ch R = 1,3185,366,366,366
BEGIN DESCRIPTION:
Mapping XS 3f4c1281
END DESCRIPTION:
XS GIS Cut Line= 3
      2550855.01     13596266.85      2550278.61     13596072.40
      2549439.18     13596145.24
#Sta/Elev= 30
  4388.1  236.92  4537.9  234.47  4841.9  223.80  4966.3  220.64  4979.1  220.06
  4989.7  218.48  4993.7  217.11  4993.9  216.61  4997.7  217.11  5000.7  217.11
  5020.1  221.04  5066.9  220.57  5076.3  220.87  5130.5  221.44  5165.9  222.65
  5230.9  224.36  5264.8  226.30  5310.9  228.34  5316.0  229.20  5321.2  228.82
  5411.6  232.72  5434.0  232.89  5501.9  236.67  5552.1  238.49  5702.7  245.88
  5762.9  249.76  5772.9  249.75  5778.2  250.73  5784.4  250.26  5839.0  252.75
#Mann=9,-1,0
  4388.1    0.04       0  4966.3    0.12       0  4993.7    0.05       0
  4997.7    0.12       0  5066.9   0.013       0  5076.3    0.04       0
  5165.9   0.013       0  5264.8    0.12       0  5784.4    0.05       0
Bank Sta=4993.7,4997.7
Exp/Cntr=0.3,0.1

Type RM Length L Ch R = 1,2819,257,257,257
BEGIN DESCRIPTION:
Mapping XS c1997402
END DESCRIPTION:
XS GIS Cut Line= 3
      2550778.60     13595916.15      2550257.77     13595728.65
      2549545.93     13595818.93
#Sta/Elev= 30
  4363.3  230.97  4494.5  229.26  4793.7  220.37  4857.6  219.02  4877.3  219.56
  4888.3  218.69  4908.4  219.17  4916.9  216.47  4924.1  216.39  4924.4  215.89
  4927.9  215.89  4928.1  216.39  4931.2  216.47  4939.8  218.53  4960.0  219.21
  4980.1  218.47  5000.3  218.84  5060.8  220.93  5070.9  221.78  5166.3  225.70
  5201.9  227.88  5232.1  228.54  5252.3  229.93  5302.7  231.94  5443.8  239.21
  5481.5  242.28  5486.6  242.19  5554.7  249.69  5584.9  252.26  5634.4  254.56
#Mann=4,-1,0
  4363.3    0.04       0  4793.7    0.12       0  4924.1    0.05       0
  4928.1    0.12       0
Bank Sta=4924.1,4928.1
Exp/Cntr=0.3,0.1

Type RM Length L Ch R = 1,2562,319,319,319
BEGIN DESCRIPTION:
Mapping XS a0427beb
END DESCRIPTION:
XS GIS Cut Line= 3
      2550740.42     13595603.65      2550209.16     13595509.90
      2549599.64     13595599.94
#Sta/Elev= 30
  4425.8  226.70  4593.8  223.78  4614.1  222.78  4634.4  223.03  4664.9  222.17
  4685.2  220.85  4751.2  219.52  4878.1  217.12  4910.4  218.30  4943.6  218.00
  4959.3  217.66  4979.6  215.83  4987.7  214.07  4987.9  213.57  4991.4  213.57
  4991.7  214.07  4999.8  216.15  5009.9  217.51  5029.7  218.08  5034.8  217.54
  5040.2  218.38  5090.8  219.53  5181.8  222.86  5282.8  228.43  5303.0  229.12
  5313.2  230.12  5383.9  233.28  5453.1  237.03  5576.0  243.96  5581.4  244.66
#Mann=6,-1,0
  4425.8    0.04       0  4751.2     0.1       0  4943.6    0.12       0
  4987.7    0.05       0  4991.7    0.12       0  5453.1    0.05       0
Bank Sta=4987.7,4991.7
Exp/Cntr=0.3,0.1

Type RM Length L Ch R = 1,2243,323,323,323
BEGIN DESCRIPTION:
Mapping XS f7273103
END DESCRIPTION:
XS GIS Cut Line= 4
      2550750.81     13595509.89      2550285.55     13595207.82
      2549990.41     13595214.76      2549535.54     13595436.99
#Sta/Elev= 30
  4284.2  225.49  4486.4  222.25  4758.6  216.07  4899.5  215.48  4928.1  214.63
  4939.5  215.70  4969.5  216.45  4977.5  212.93  4977.8  212.43  4981.3  212.43
  4981.5  212.93  4989.5  215.31  4999.5  215.84  5012.9  215.34  5134.1  218.57
  5140.2  219.54  5213.5  222.89  5399.2  230.32  5429.5  232.41  5438.7  232.21
  5461.2  233.85  5466.8  233.61  5474.1  234.48  5489.3  234.83  5506.2  236.32
  5511.8  236.06  5556.1  237.95  5607.6  241.88  5637.9  243.32  5640.4  243.32
#Mann=7,-1,0
  4284.2    0.04       0  4486.4    0.05       0  4758.6     0.1       0
  4977.5    0.05       0  4981.5     0.1       0  5012.9    0.12       0
  5637.9    0.05       0
Bank Sta=4977.5,4981.5
Exp/Cntr=0.3,0.1

Type RM Length L Ch R = 1,1920,0,0,0
BEGIN DESCRIPTION:
TRIB 5_2 TO IRISH CREEK 1.0
END DESCRIPTION:
XS GIS Cut Line= 3
      2550691.83     13595284.23      2550125.15     13594809.94
      2549398.35     13595265.79
#Sta/Elev= 30
  4485.2  220.83  4518.3  221.08  4576.9  219.72  4649.3  218.82  4704.1  218.05
  4752.5  217.44  4781.0  216.20  4928.5  214.39  4947.6  214.46  5150.5  213.46
  5224.1  212.91  5265.6  213.52  5267.6  213.56  5342.8  214.46  5358.1  213.30
  5371.4  210.30  5371.6  209.80  5375.4  210.30  5379.3  210.72  5388.7  214.32
  5437.0  214.56  5519.5  217.93  5540.7  219.63  5613.8  222.03  5635.0  223.72
  5663.2  224.29  5732.1  226.96  5790.7  230.23  5850.6  233.83  6082.1  242.42
#Mann=14,-1,0
  4485.2    0.04       0  4576.9    0.05       0  4649.3    0.04       0
  4704.1    0.05       0  4928.5    0.12       0  4947.6     0.1       0
  5150.5    0.12       0  5265.6     0.1       0  5267.6    0.12       0
  5371.4    0.05       0  5375.4    0.12       0  5663.2    0.05       0
  5732.1    0.12       0  5790.7    0.05       0
Bank Sta=5371.4,5375.4
Exp/Cntr=0.3,0.1

Chan Stop Cuts=-1