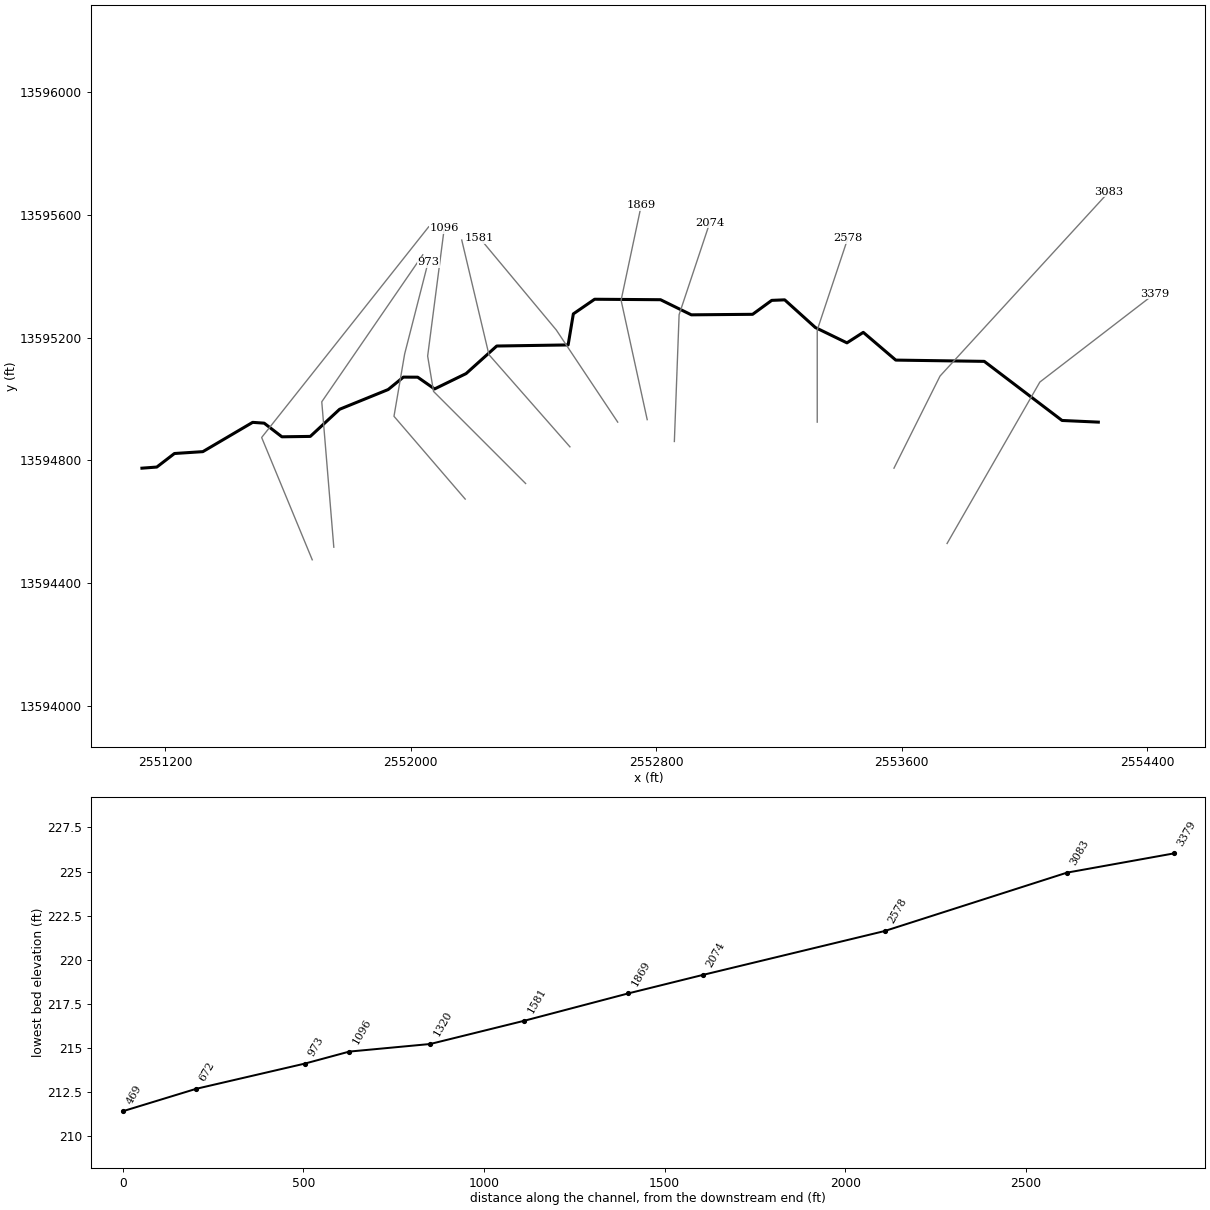
--- TRIB 5_3 TO IRISH CREEK.prj (project) ---

Proj Title=TRIB 5_3 TO IRISH CREEK Base Level Engineering
Current Plan=p01
Default Exp/Contr=0.3,0.1
English Units
Geom File=g01
Flow File=f01
Plan File=p01
BEGIN DESCRIPTION:
TRIB 5_3 TO IRISH CREEK
END DESCRIPTION:

--- TRIB 5_3 TO IRISH CREEK.p01 (plan) ---

Plan Title=Multiple Run
Short Identifier=Multiple
Geom File=g01
Flow File=f01
Subcritical Flow
K Sum by GR= 0
Std Step Tol= 0.01
Critical Tol= 0.01
Num of Std Step Trials= 20
Max Error Tol= 0.3
Flow Tol Ratio= 0.001
Split Flow NTrial= 30
Split Flow Tol= 0.02
Split Flow Ratio= 0.02
Log Output Level= 0
Friction Slope Method= 1
Unsteady Friction Slope Method= 2
Unsteady Bridges Friction Slope Method= 1
Parabolic Critical Depth
Global Vel Dist=  1 , 1 , 1
Global Log Level= 0
CheckData=True
Encroach Param= -1, 0, 0, 0
BEGIN DESCRIPTION:
Multiple Run
END DESCRIPTION:

--- TRIB 5_3 TO IRISH CREEK.f01 (steady flow) ---

Flow Title=Multiple
Number of Profiles=7
Profile Names=10-year,25-year,50-year,1pct_min,100-year,1pct_plu,500-year
River Rch & RM= TRIB 5_3 TO IRIS,Reach-1,3379
     674    1079    1443     935    1866    3723    3085
Boundary for River Rch & Prof#=TRIB 5_3 TO IRIS,Reach-1,1
Up Type=0
Dn Type=3
Dn Slope=0.005
Boundary for River Rch & Prof#=TRIB 5_3 TO IRIS,Reach-1,2
Up Type=0
Dn Type=3
Dn Slope=0.005
Boundary for River Rch & Prof#=TRIB 5_3 TO IRIS,Reach-1,3
Up Type=0
Dn Type=3
Dn Slope=0.005
Boundary for River Rch & Prof#=TRIB 5_3 TO IRIS,Reach-1,4
Up Type=0
Dn Type=3
Dn Slope=0.005
Boundary for River Rch & Prof#=TRIB 5_3 TO IRIS,Reach-1,5
Up Type=0
Dn Type=3
Dn Slope=0.005
Boundary for River Rch & Prof#=TRIB 5_3 TO IRIS,Reach-1,6
Up Type=0
Dn Type=3
Dn Slope=0.005
Boundary for River Rch & Prof#=TRIB 5_3 TO IRIS,Reach-1,7
Up Type=0
Dn Type=3
Dn Slope=0.005

--- TRIB 5_3 TO IRISH CREEK.g01 (geometry) ---

Geom Title=Existing Conditions

River Reach=TRIB 5_3 TO IRIS,Reach-1
Reach XY= 30
      2554240.76     13594925.00      2554122.52     13594930.40
      2553869.14     13595122.94      2553580.85     13595127.07
      2553475.00     13595217.44      2553421.77     13595183.25
      2553318.96     13595233.14      2553218.96     13595323.37
      2553176.75     13595321.66      2553114.50     13595276.24
      2552914.81     13595274.55      2552814.50     13595323.78
      2552599.78     13595325.33      2552530.43     13595277.65
      2552513.47     13595176.50      2552280.86     13595172.94
      2552181.04     13595083.14      2552078.31     13595033.07
      2552023.36     13595071.40      2551976.74     13595071.63
      2551927.20     13595031.16      2551768.95     13594966.84
      2551673.50     13594878.47      2551580.97     13594877.19
      2551523.26     13594921.63      2551485.68     13594924.25
      2551323.42     13594828.82      2551230.92     13594822.77
      2551173.49     13594778.64      2551125.00     13594775.00

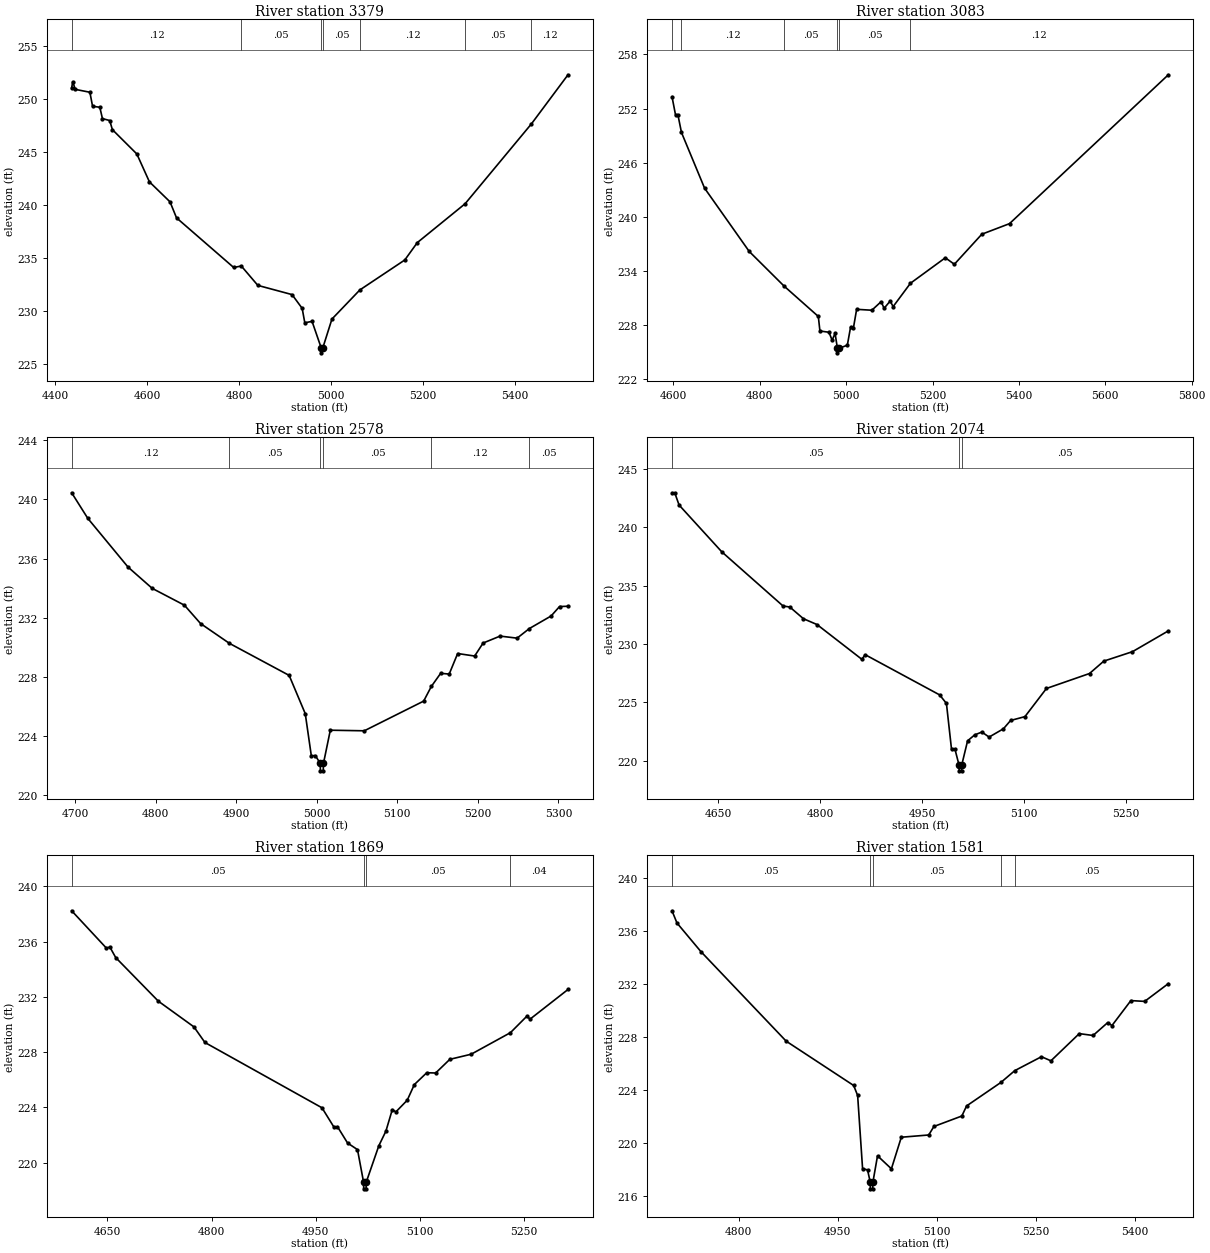
Type RM Length L Ch R = 1,3379,296,296,296
BEGIN DESCRIPTION:
Mapping XS 469203ff
END DESCRIPTION:
XS GIS Cut Line= 3
      2553747.99     13594529.65      2554050.20     13595055.49
      2554424.63     13595343.69
#Sta/Elev= 30
  4436.5  251.05  4438.7  251.64  4444.5  250.91  4476.1  250.64  4481.9  249.32
  4497.7  249.22  4503.4  248.15  4519.2  247.97  4525.0  247.11  4578.2  244.81
  4605.5  242.18  4650.3  240.29  4664.4  238.78  4788.7  234.09  4805.3  234.23
  4841.2  232.40  4915.6  231.53  4937.6  230.23  4943.3  228.87  4959.1  229.00
  4978.7  226.53  4978.9  226.03  4982.7  226.53  5002.3  229.22  5063.0  231.97
  5160.7  234.80  5187.9  236.44  5291.8  240.11  5436.1  247.66  5515.5  252.29
#Mann=7,-1,0
  4436.5    0.12       0  4805.3    0.05       0  4978.7    0.05       0
  4982.7    0.05       0  5063.0    0.12       0  5291.8    0.05       0
  5436.1    0.12       0
Bank Sta=4978.7,4982.7
Exp/Cntr=0.3,0.1

Type RM Length L Ch R = 1,3083,505,505,505
BEGIN DESCRIPTION:
TRIB 5_3 TO IRISH CREEK 6.0
END DESCRIPTION:
XS GIS Cut Line= 3
      2553575.02     13594775.04      2553725.00     13595075.00
      2554275.00     13595675.00
#Sta/Elev= 30
  4596.7  253.31  4605.0  251.26  4610.6  251.25  4618.6  249.35  4672.1  243.18
  4775.5  236.17  4856.3  232.33  4935.5  228.97  4939.2  227.36  4960.1  227.22
  4967.5  226.34  4974.3  227.10  4979.7  225.44  4979.9  224.94  4983.7  225.44
  5002.7  225.79  5010.1  227.77  5016.8  227.70  5024.2  229.76  5059.4  229.66
  5081.0  230.61  5087.8  229.87  5101.9  230.68  5108.7  230.06  5148.9  232.65
  5229.6  235.47  5250.5  234.75  5314.1  238.08  5378.2  239.25  5746.0  255.74
#Mann=6,-1,0
  4596.7    0.04       0  4618.6    0.12       0  4856.3    0.05       0
  4979.7    0.05       0  4983.7    0.05       0  5148.9    0.12       0
Bank Sta=4979.7,4983.7
Exp/Cntr=0.3,0.1

Type RM Length L Ch R = 1,2578,504,504,504
BEGIN DESCRIPTION:
TRIB 5_3 TO IRISH CREEK 5.0
END DESCRIPTION:
XS GIS Cut Line= 3
      2553325.00     13594924.99      2553325.00     13595225.00
      2553424.99     13595524.96
#Sta/Elev= 30
  4695.7  240.45  4715.7  238.72  4765.7  235.42  4795.7  233.98  4835.7  232.84
  4855.7  231.60  4891.5  230.26  4965.7  228.09  4985.7  225.50  4993.2  222.66
  4998.3  222.66  5004.3  222.13  5004.5  221.63  5008.0  221.63  5008.3  222.13
  5016.8  224.38  5059.0  224.34  5132.7  226.35  5142.2  227.34  5153.8  228.23
  5164.4  228.18  5174.9  229.57  5196.0  229.40  5206.5  230.28  5227.6  230.75
  5248.7  230.61  5263.9  231.26  5290.9  232.11  5301.4  232.75  5311.9  232.77
#Mann=6,-1,0
  4695.7    0.12       0  4891.5    0.05       0  5004.3    0.05       0
  5008.3    0.05       0  5142.2    0.12       0  5263.9    0.05       0
Bank Sta=5004.3,5008.3
Exp/Cntr=0.3,0.1

Type RM Length L Ch R = 1,2074,205,205,205
BEGIN DESCRIPTION:
TRIB 5_3 TO IRISH CREEK 4.0
END DESCRIPTION:
XS GIS Cut Line= 3
      2552859.53     13594861.91      2552875.00     13595275.00
      2552975.00     13595575.00
#Sta/Elev= 30
  4582.5  242.94  4586.5  242.94  4592.9  241.89  4655.6  237.89  4745.7  233.25
  4755.7  233.16  4775.7  232.16  4795.7  231.66  4861.5  228.69  4866.5  229.08
  4975.9  225.64  4985.9  224.91  4993.4  220.97  4998.5  220.97  5004.4  219.64
  5004.7  219.14  5008.2  219.14  5008.4  219.64  5017.0  221.71  5027.5  222.22
  5038.0  222.46  5048.6  222.03  5069.7  222.74  5080.2  223.45  5101.3  223.78
  5132.9  226.19  5196.2  227.47  5217.2  228.53  5259.4  229.34  5312.1  231.12
#Mann=3,-1,0
  4582.5    0.05       0  5004.4    0.05       0  5008.4    0.05       0
Bank Sta=5004.4,5008.4
Exp/Cntr=0.3,0.1

Type RM Length L Ch R = 1,1869,288,288,288
BEGIN DESCRIPTION:
Mapping XS 23564896
END DESCRIPTION:
XS GIS Cut Line= 3
      2552771.07     13594933.06      2552686.00     13595321.95
      2552751.69     13595631.37
#Sta/Elev= 30
  4598.7  238.24  4648.6  235.54  4653.7  235.61  4662.1  234.85  4723.5  231.69
  4774.7  229.83  4790.5  228.70  4959.0  223.97  4976.2  222.57  4981.3  222.60
  4995.8  221.42  5010.1  220.94  5018.8  218.60  5019.0  218.10  5022.5  218.10
  5022.8  218.60  5040.8  221.22  5051.0  222.28  5060.2  223.84  5065.3  223.67
  5081.7  224.52  5091.9  225.65  5109.8  226.51  5122.6  226.49  5143.0  227.48
  5173.7  227.85  5230.2  229.41  5253.6  230.59  5258.7  230.40  5313.1  232.54
#Mann=4,-1,0
  4598.7    0.05       0  5018.8    0.05       0  5022.8    0.05       0
  5230.2    0.04       0
Bank Sta=5018.8,5022.8
Exp/Cntr=0.3,0.1

Type RM Length L Ch R = 1,1581,261,261,261
BEGIN DESCRIPTION:
TRIB 5_3 TO IRISH CREEK 3.0
END DESCRIPTION:
XS GIS Cut Line= 3
      2552674.99     13594925.01      2552475.00     13595225.00
      2552224.97     13595525.03
#Sta/Elev= 30
  4699.1  237.51  4706.6  236.59  4742.7  234.44  4871.9  227.68  4974.0  224.34
  4980.0  223.59  4987.5  218.06  4995.0  217.98  4999.1  217.05  4999.3  216.55
  5002.8  216.55  5003.1  217.05  5010.1  219.04  5031.1  218.06  5046.1  220.44
  5087.6  220.61  5095.4  221.25  5137.7  222.04  5144.9  222.80  5196.8  224.57
  5217.8  225.46  5258.2  226.51  5272.5  226.20  5315.4  228.25  5336.3  228.11
  5358.4  229.08  5364.9  228.86  5393.5  230.74  5414.4  230.68  5450.2  232.02
#Mann=5,-1,0
  4699.1    0.05       0  4999.1    0.05       0  5003.1    0.05       0
  5196.8    0.04       0  5217.8    0.05       0
Bank Sta=4999.1,5003.1
Exp/Cntr=0.3,0.1

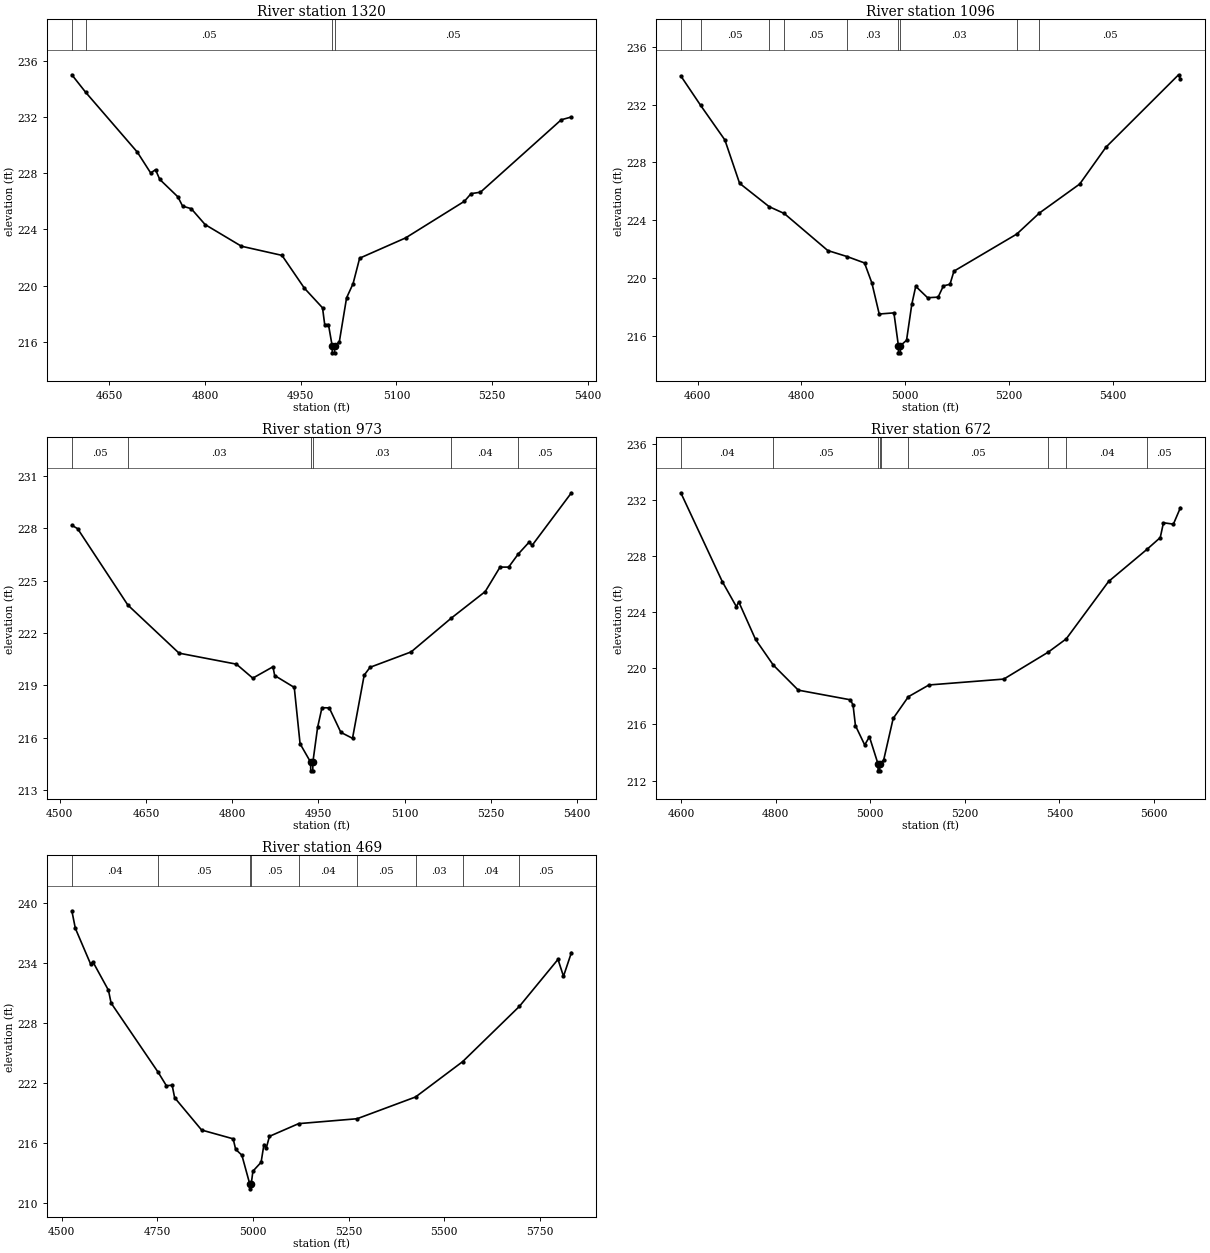
Type RM Length L Ch R = 1,1320,224,224,224
BEGIN DESCRIPTION:
Mapping XS 393dda82
END DESCRIPTION:
XS GIS Cut Line= 3
      2552519.32     13594844.54      2552255.44     13595144.87
      2552166.90     13595518.13
#Sta/Elev= 30
  4591.0  235.00  4612.6  233.76  4693.7  229.50  4714.6  228.02  4722.2  228.25
  4728.9  227.56  4757.3  226.32  4764.7  225.66  4778.2  225.48  4800.0  224.35
  4856.9  222.81  4920.5  222.16  4955.6  219.83  4984.1  218.43  4987.5  217.24
  4993.4  217.24  4999.2  215.73  4999.4  215.23  5002.9  215.23  5003.2  215.73
  5010.4  216.01  5021.8  219.14  5032.0  220.15  5042.3  221.96  5114.3  223.40
  5206.7  226.01  5217.0  226.55  5231.7  226.65  5358.4  231.80  5374.4  232.00
#Mann=4,-1,0
  4591.0    0.03       0  4612.6    0.05       0  4999.2    0.05       0
  5003.2    0.05       0
Bank Sta=4999.2,5003.2
Exp/Cntr=0.3,0.1

Type RM Length L Ch R = 1,1096,123,123,123
BEGIN DESCRIPTION:
TRIB 5_3 TO IRISH CREEK 2.0
END DESCRIPTION:
XS GIS Cut Line= 4
      2552374.97     13594725.03      2552075.00     13595025.00
      2552055.81     13595140.14      2552110.00     13595557.18
#Sta/Elev= 30
  4567.9  233.99  4606.0  231.95  4652.7  229.55  4681.0  226.55  4737.9  224.93
  4766.8  224.46  4850.7  221.89  4888.1  221.47  4921.4  221.03  4935.6  219.64
  4949.7  217.49  4978.0  217.57  4986.6  215.30  4986.8  214.80  4990.3  214.80
  4990.6  215.30  5002.3  215.67  5012.4  218.16  5020.0  219.41  5042.8  218.62
  5063.1  218.66  5073.2  219.44  5085.9  219.55  5093.5  220.46  5214.4  223.03
  5258.0  224.49  5335.6  226.50  5386.0  229.05  5525.8  234.07  5529.4  233.77
#Mann=9,-1,0
  4567.9    0.03       0  4606.0    0.05       0  4737.9    0.03       0
  4766.8    0.05       0  4888.1    0.03       0  4986.6    0.03       0
  4990.6    0.03       0  5214.4    0.04       0  5258.0    0.05       0
Bank Sta=4986.6,4990.6
Exp/Cntr=0.3,0.1

Type RM Length L Ch R = 1,973,301,301,301
BEGIN DESCRIPTION:
4845
END DESCRIPTION:
XS GIS Cut Line= 4
      2552178.10     13594674.31      2551946.13     13594943.98
      2551980.85     13595146.89      2552057.21     13595445.41
#Sta/Elev= 30
  4520.9  228.16  4530.9  227.97  4618.4  223.60  4707.5  220.85  4807.4  220.22
  4835.9  219.42  4871.0  220.07  4874.0  219.57  4908.1  218.89  4918.2  215.67
  4936.5  214.62  4936.8  214.12  4940.3  214.12  4940.5  214.62  4948.7  216.60
  4956.3  217.73  4969.0  217.72  4989.2  216.32  5009.5  215.98  5029.8  219.59
  5040.0  220.04  5111.5  220.92  5181.7  222.86  5240.5  224.37  5266.3  225.77
  5281.3  225.77  5297.8  226.51  5317.0  227.20  5322.1  227.01  5390.6  230.02
#Mann=6,-1,0
  4520.9    0.05       0  4618.4    0.03       0  4936.5    0.03       0
  4940.5    0.03       0  5181.7    0.04       0  5297.8    0.05       0
Bank Sta=4936.5,4940.5
Exp/Cntr=0.3,0.1

Type RM Length L Ch R = 1,672,203,203,203
BEGIN DESCRIPTION:
4844
END DESCRIPTION:
XS GIS Cut Line= 3
      2551750.08     13594517.54      2551710.87     13594991.25
      2552039.93     13595470.17
#Sta/Elev= 30
  4599.4  232.54  4687.2  226.19  4716.9  224.41  4721.9  224.75  4757.4  222.07
  4794.9  220.24  4847.8  218.45  4958.1  217.76  4963.6  217.38  4968.6  215.92
  4988.2  214.54  4998.2  215.12  5016.3  213.19  5016.5  212.69  5020.0  212.69
  5020.3  213.19  5022.6  213.27  5028.3  213.46  5048.4  216.43  5080.5  217.98
  5124.0  218.82  5282.3  219.24  5376.1  221.16  5414.3  222.11  5503.9  226.21
  5585.3  228.51  5613.1  229.34  5619.9  230.40  5640.9  230.30  5655.8  231.48
#Mann=9,-1,0
  4599.4    0.04       0  4794.9    0.05       0  5016.3    0.05       0
  5020.3    0.05       0  5022.6    0.04       0  5080.5    0.05       0
  5376.1    0.03       0  5414.3    0.04       0  5585.3    0.05       0
Bank Sta=5016.3,5020.3
Exp/Cntr=0.3,0.1

Type RM Length L Ch R = 1,469,0,0,0
BEGIN DESCRIPTION:
TRIB 5_3 TO IRISH CREEK 1.0
END DESCRIPTION:
XS GIS Cut Line= 3
      2551679.85     13594476.48      2551515.02     13594874.95
      2552059.03     13595561.16
#Sta/Elev= 30
  4526.2  239.27  4535.4  237.51  4575.7  233.90  4581.1  234.17  4622.0  231.31
  4628.9  230.03  4752.1  223.09  4773.5  221.75  4788.6  221.80  4795.1  220.55
  4865.7  217.31  4948.2  216.43  4954.7  215.38  4971.0  214.79  4991.5  211.92
  4991.8  211.42  4995.5  211.92  4999.9  213.19  5021.3  214.08  5028.7  215.86
  5035.1  215.55  5043.2  216.68  5119.4  217.95  5272.3  218.44  5425.3  220.62
  5548.5  224.16  5696.8  229.69  5797.9  234.40  5812.3  232.71  5833.1  235.09
#Mann=9,-1,0
  4526.2    0.04       0  4752.1    0.05       0  4991.5    0.05       0
  4995.5    0.05       0  5119.4    0.04       0  5272.3    0.05       0
  5425.3    0.03       0  5548.5    0.04       0  5696.8    0.05       0
Bank Sta=4991.5,4995.5
Exp/Cntr=0.3,0.1

Chan Stop Cuts=-1