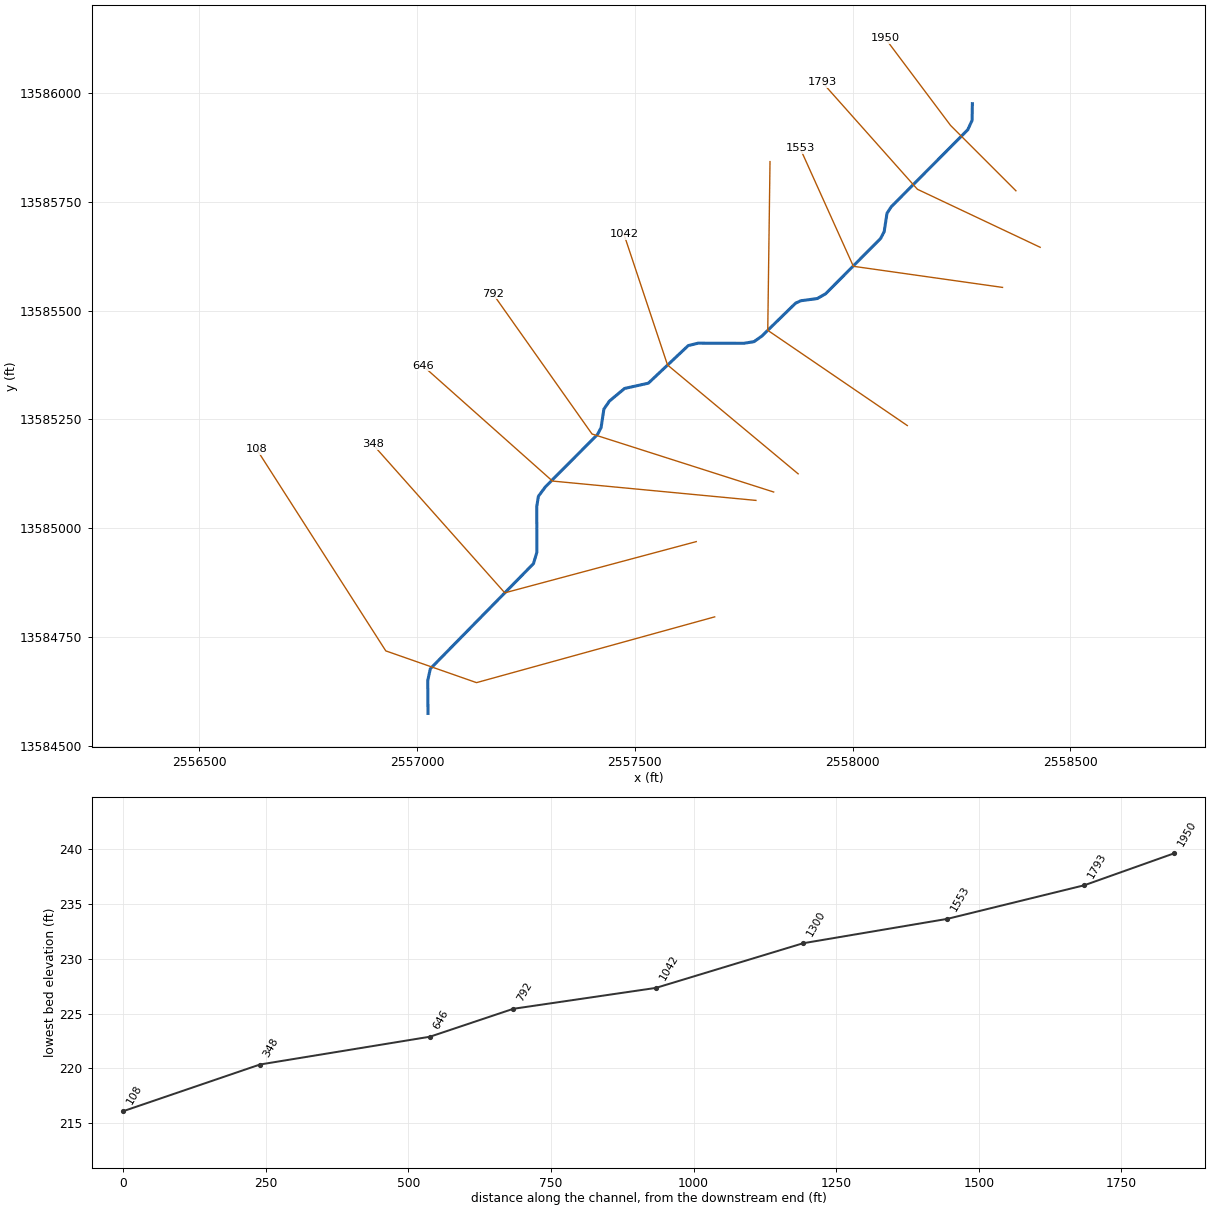
--- TRIB 6 TO CRITTENOON HOLLOW.prj (project) ---

Proj Title=TRIB 6 TO CRITTENOON HOLLOW Base Level Engineering
Current Plan=p01
Default Exp/Contr=0.3,0.1
English Units
Geom File=g01
Flow File=f01
Plan File=p01
BEGIN DESCRIPTION:
TRIB 6 TO CRITTENOON HOLLOW
END DESCRIPTION:

--- TRIB 6 TO CRITTENOON HOLLOW.p01 (plan) ---

Plan Title=Multiple Run
Short Identifier=Multiple
Geom File=g01
Flow File=f01
Subcritical Flow
K Sum by GR= 0
Std Step Tol= 0.01
Critical Tol= 0.01
Num of Std Step Trials= 20
Max Error Tol= 0.3
Flow Tol Ratio= 0.001
Split Flow NTrial= 30
Split Flow Tol= 0.02
Split Flow Ratio= 0.02
Log Output Level= 0
Friction Slope Method= 1
Unsteady Friction Slope Method= 2
Unsteady Bridges Friction Slope Method= 1
Parabolic Critical Depth
Global Vel Dist=  1 , 1 , 1
Global Log Level= 0
CheckData=True
Encroach Param= -1, 0, 0, 0
BEGIN DESCRIPTION:
Multiple Run
END DESCRIPTION:

--- TRIB 6 TO CRITTENOON HOLLOW.f01 (steady flow) ---

Flow Title=Multiple
Number of Profiles=7
Profile Names=10-year,25-year,50-year,1pct_min,100-year,1pct_plu,500-year
River Rch & RM= TRIB 6 TO CRITTE,Reach-1,1950
     290     439     566     355     709    1415    1096
Boundary for River Rch & Prof#=TRIB 6 TO CRITTE,Reach-1,1
Up Type=0
Dn Type=3
Dn Slope=0.005
Boundary for River Rch & Prof#=TRIB 6 TO CRITTE,Reach-1,2
Up Type=0
Dn Type=3
Dn Slope=0.005
Boundary for River Rch & Prof#=TRIB 6 TO CRITTE,Reach-1,3
Up Type=0
Dn Type=3
Dn Slope=0.005
Boundary for River Rch & Prof#=TRIB 6 TO CRITTE,Reach-1,4
Up Type=0
Dn Type=3
Dn Slope=0.005
Boundary for River Rch & Prof#=TRIB 6 TO CRITTE,Reach-1,5
Up Type=0
Dn Type=3
Dn Slope=0.005
Boundary for River Rch & Prof#=TRIB 6 TO CRITTE,Reach-1,6
Up Type=0
Dn Type=3
Dn Slope=0.005
Boundary for River Rch & Prof#=TRIB 6 TO CRITTE,Reach-1,7
Up Type=0
Dn Type=3
Dn Slope=0.005

--- TRIB 6 TO CRITTENOON HOLLOW.g01 (geometry) ---

Geom Title=Existing Conditions

River Reach=TRIB 6 TO CRITTE,Reach-1
Reach XY= 30
      2558275.00     13585975.00      2558274.41     13585936.84
      2558264.48     13585915.21      2558088.63     13585738.21
      2558078.98     13585723.35      2558072.47     13585681.05
      2558064.22     13585665.32      2557938.21     13585538.63
      2557918.95     13585527.53      2557881.05     13585522.46
      2557868.96     13585516.82      2557791.75     13585441.46
      2557773.53     13585428.55      2557750.11     13585424.73
      2557644.99     13585425.02      2557622.56     13585419.52
      2557531.02     13585333.19      2557476.43     13585321.11
      2557441.50     13585292.05      2557428.89     13585273.57
      2557422.45     13585231.09      2557414.21     13585215.34
      2557294.61     13585095.16      2557278.54     13585073.53
      2557274.73     13585050.11      2557275.02     13584944.99
      2557267.18     13584918.81      2557030.35     13584677.50
      2557024.41     13584650.25      2557025.00     13584575.00

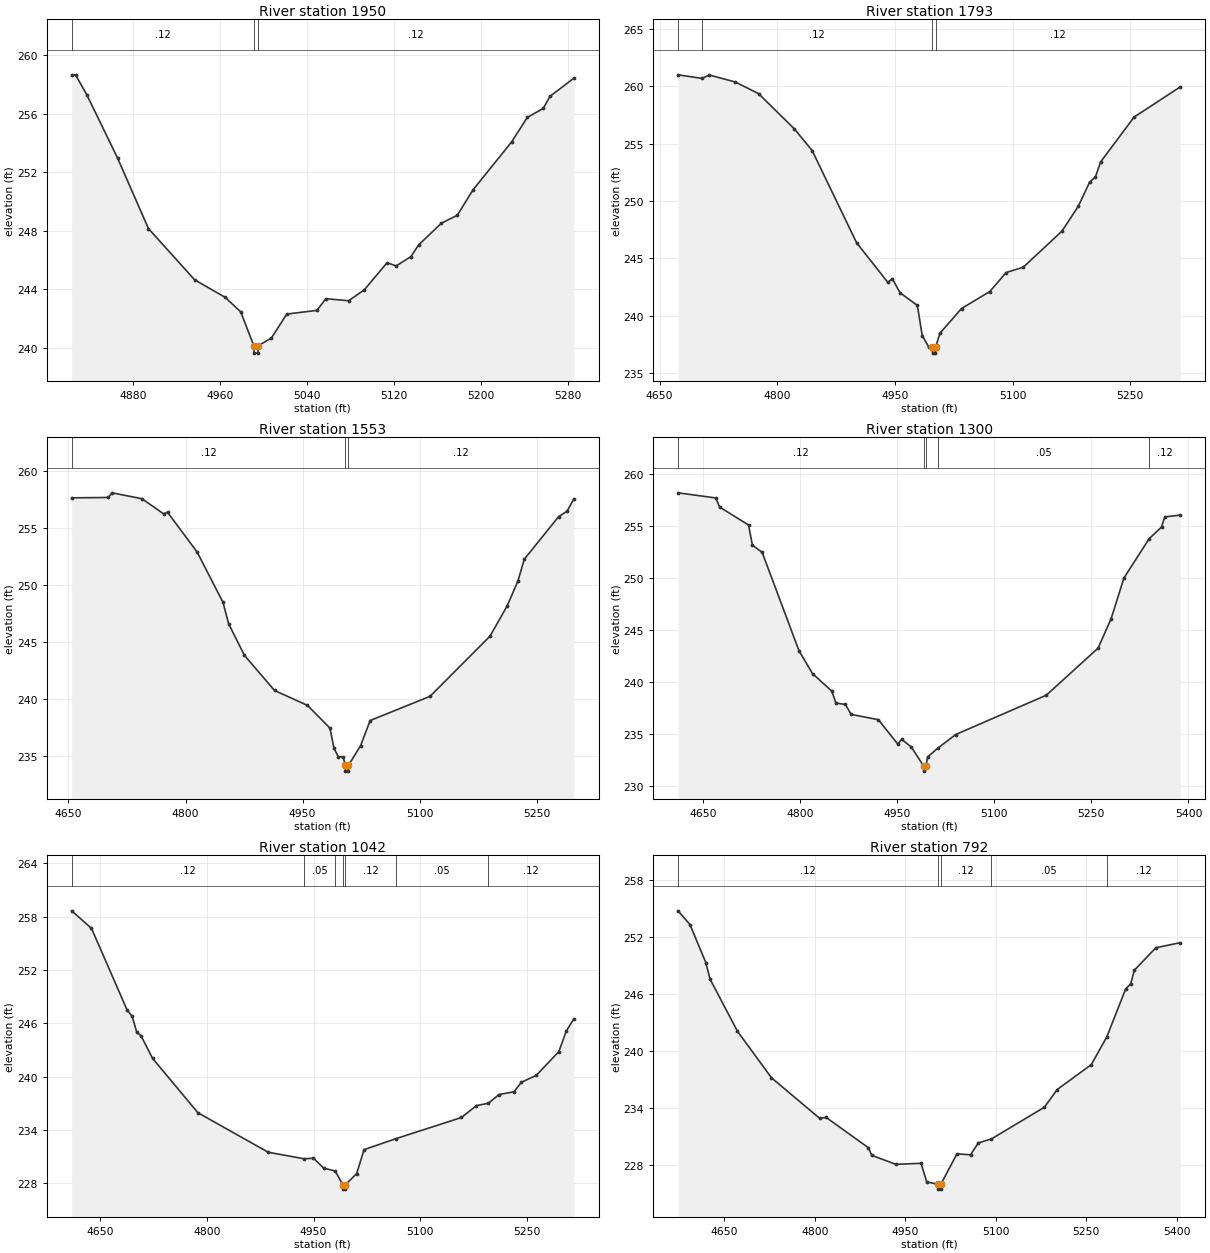
Type RM Length L Ch R = 1,1950,157,157,157
BEGIN DESCRIPTION:
TRIB 6 TO CRITTENOON HOLLOW 4.0
END DESCRIPTION:
XS GIS Cut Line= 3
      2558375.01     13585774.99      2558225.00     13585925.00
      2558074.97     13586125.04
#Sta/Elev= 30
  4823.5  258.65  4827.1  258.65  4837.7  257.25  4865.9  252.94  4894.2  248.14
  4936.7  244.64  4964.9  243.44  4979.1  242.45  4991.2  240.13  4991.5  239.63
  4995.0  239.63  4995.2  240.13  5007.4  240.67  5021.5  242.30  5049.2  242.55
  5057.5  243.35  5078.4  243.21  5092.9  243.96  5113.8  245.81  5122.1  245.59
  5135.7  246.22  5142.9  247.03  5163.8  248.51  5178.4  249.05  5192.9  250.79
  5228.4  254.06  5242.9  255.74  5257.5  256.35  5263.8  257.18  5285.7  258.42
#Mann=3,-1,0
  4823.5    0.12       0  4991.2    0.05       0  4995.2    0.12       0
Bank Sta=4991.2,4995.2
Exp/Cntr=0.3,0.1

Type RM Length L Ch R = 1,1793,240,240,240
BEGIN DESCRIPTION:
Mapping XS 97ea8025
END DESCRIPTION:
XS GIS Cut Line= 3
      2558430.69     13585645.24      2558148.82     13585778.45
      2557930.63     13586023.67
#Sta/Elev= 30
  4673.7  260.99  4704.1  260.68  4713.5  260.97  4746.4  260.37  4776.2  259.35
  4821.8  256.28  4844.5  254.39  4901.2  246.34  4941.1  242.88  4946.6  243.22
  4956.5  241.99  4978.6  240.88  4984.8  238.25  4993.1  237.26  4997.8  237.22
  4998.1  236.72  5001.6  236.72  5001.8  237.22  5007.3  238.45  5034.9  240.61
  5070.9  242.09  5091.8  243.75  5113.5  244.21  5162.9  247.36  5183.8  249.54
  5198.0  251.61  5205.5  252.08  5212.2  253.40  5254.9  257.31  5313.7  259.94
#Mann=4,-1,0
  4673.7    0.05       0  4704.1    0.12       0  4997.8    0.05       0
  5001.8    0.12       0
Bank Sta=4997.8,5001.8
Exp/Cntr=0.3,0.1

Type RM Length L Ch R = 1,1553,253,253,253
BEGIN DESCRIPTION:
TRIB 6 TO CRITTENOON HOLLOW 3.0
END DESCRIPTION:
XS GIS Cut Line= 3
      2558344.24     13585553.13      2558001.75     13585601.59
      2557879.38     13585872.87
#Sta/Elev= 30
  4654.1  257.68  4701.0  257.71  4706.0  258.12  4744.2  257.60  4772.0  256.27
  4777.0  256.41  4814.9  252.91  4848.1  248.48  4855.3  246.60  4875.5  243.83
  4914.1  240.74  4956.3  239.43  4985.1  237.43  4990.2  235.68  4995.8  234.90
  5002.1  234.90  5004.7  234.15  5005.0  233.65  5008.5  233.65  5008.7  234.15
  5024.4  235.90  5036.6  238.10  5113.4  240.23  5190.2  245.52  5212.2  248.18
  5225.9  250.36  5234.1  252.28  5278.0  256.02  5289.0  256.51  5297.6  257.59
#Mann=3,-1,0
  4654.1    0.12       0  5004.7    0.05       0  5008.7    0.12       0
Bank Sta=5004.7,5008.7
Exp/Cntr=0.3,0.1

Type RM Length L Ch R = 1,1300,258,258,258
BEGIN DESCRIPTION:
Mapping XS 2d57889c
END DESCRIPTION:
XS GIS Cut Line= 3
      2558125.66     13585235.87      2557805.17     13585454.58
      2557810.35     13585841.95
#Sta/Elev= 30
  4612.0  258.15  4669.9  257.66  4676.0  256.79  4720.7  255.06  4726.8  253.11
  4741.7  252.44  4798.6  242.99  4819.6  240.78  4849.4  239.10  4855.5  237.97
  4870.4  237.82  4879.1  236.87  4921.2  236.36  4951.1  234.02  4957.1  234.47
  4972.0  233.74  4991.0  231.92  4991.3  231.42  4995.0  231.92  4997.1  232.77
  5012.6  233.61  5040.4  234.93  5180.4  238.71  5260.4  243.23  5280.4  246.03
  5300.4  249.98  5339.5  253.76  5358.4  254.86  5363.4  255.84  5387.4  256.01
#Mann=5,-1,0
  4612.0    0.12       0  4991.0    0.05       0  4995.0    0.12       0
  5012.6    0.05       0  5339.5    0.12       0
Bank Sta=4991,4995
Exp/Cntr=0.3,0.1

Type RM Length L Ch R = 1,1042,250,250,250
BEGIN DESCRIPTION:
TRIB 6 TO CRITTENOON HOLLOW 2.0
END DESCRIPTION:
XS GIS Cut Line= 3
      2557874.96     13585125.03      2557575.00     13585375.00
      2557475.00     13585675.01
#Sta/Elev= 30
  4609.5  258.65  4637.4  256.68  4687.6  247.48  4694.7  246.78  4701.2  244.97
  4707.1  244.60  4723.4  242.05  4787.1  235.94  4886.1  231.49  4937.0  230.75
  4949.8  230.82  4964.2  229.70  4980.5  229.38  4990.8  227.84  4991.1  227.34
  4994.6  227.34  4994.8  227.84  5010.5  229.08  5021.0  231.78  5065.6  233.01
  5158.1  235.40  5179.2  236.74  5195.9  237.00  5210.8  237.98  5231.9  238.29
  5242.4  239.36  5263.5  240.15  5295.1  242.82  5305.7  245.15  5316.2  246.49
#Mann=7,-1,0
  4609.5    0.12       0  4937.0    0.05       0  4980.5    0.12       0
  4990.8    0.05       0  4994.8    0.12       0  5065.6    0.05       0
  5195.9    0.12       0
Bank Sta=4990.8,4994.8
Exp/Cntr=0.3,0.1

Type RM Length L Ch R = 1,792,146,146,146
BEGIN DESCRIPTION:
Mapping XS 96083a98
END DESCRIPTION:
XS GIS Cut Line= 3
      2557818.69     13585083.33      2557401.58     13585216.57
      2557173.74     13585539.02
#Sta/Elev= 30
  4573.5  254.78  4593.1  253.33  4619.4  249.33  4626.5  247.57  4671.9  242.08
  4728.2  237.18  4808.3  232.89  4818.8  233.00  4889.1  229.79  4894.4  229.00
  4934.3  228.05  4976.3  228.15  4985.7  226.20  5005.0  225.93  5005.2  225.43
  5008.7  225.43  5009.0  225.93  5035.8  229.15  5058.4  229.05  5071.4  230.31
  5092.9  230.72  5180.9  234.07  5202.0  235.93  5258.6  238.56  5284.4  241.50
  5315.6  246.54  5323.9  247.08  5330.0  248.52  5365.7  250.89  5406.2  251.42
#Mann=5,-1,0
  4573.5    0.12       0  5005.0    0.05       0  5009.0    0.12       0
  5092.9    0.05       0  5284.4    0.12       0
Bank Sta=5005,5009
Exp/Cntr=0.3,0.1

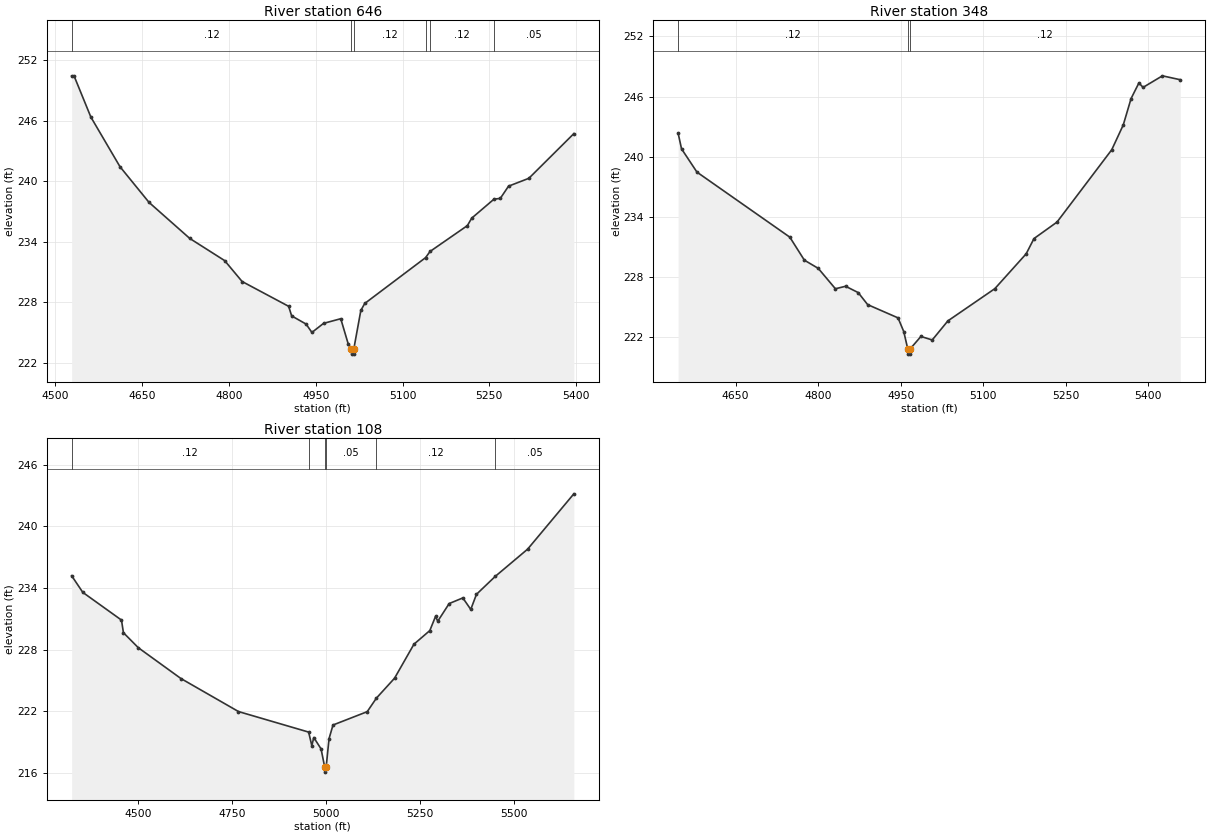
Type RM Length L Ch R = 1,646,298,298,298
BEGIN DESCRIPTION:
Mapping XS 7c7cb1a5
END DESCRIPTION:
XS GIS Cut Line= 3
      2557778.10     13585064.03      2557310.83     13585108.44
      2557013.45     13585373.00
#Sta/Elev= 30
  4528.5  250.47  4532.6  250.47  4561.7  246.38  4612.0  241.46  4662.2  237.92
  4732.5  234.35  4792.8  232.15  4822.9  230.08  4903.3  227.62  4908.5  226.67
  4933.4  225.86  4943.5  225.03  4963.6  225.93  4993.3  226.39  5006.3  223.87
  5011.8  223.38  5012.1  222.88  5015.6  222.88  5015.8  223.38  5028.0  227.21
  5034.7  227.90  5139.7  232.44  5147.6  233.06  5212.0  235.62  5219.5  236.36
  5257.9  238.24  5268.9  238.32  5283.1  239.53  5318.2  240.31  5395.9  244.74
#Mann=6,-1,0
  4528.5    0.12       0  5011.8    0.05       0  5015.8    0.12       0
  5139.7    0.05       0  5147.6    0.12       0  5257.9    0.05       0
Bank Sta=5011.8,5015.8
Exp/Cntr=0.3,0.1

Type RM Length L Ch R = 1,348,240,240,240
BEGIN DESCRIPTION:
TRIB 6 TO CRITTENOON HOLLOW 1.0
END DESCRIPTION:
XS GIS Cut Line= 3
      2557640.97     13584969.41      2557201.36     13584851.79
      2556897.62     13585193.42
#Sta/Elev= 30
  4545.7  242.35  4551.9  240.79  4579.9  238.47  4748.6  231.99  4775.0  229.70
  4800.3  228.88  4831.4  226.85  4849.9  227.10  4872.8  226.47  4890.0  225.27
  4945.2  223.95  4955.6  222.58  4962.9  220.84  4963.1  220.34  4966.6  220.34
  4966.9  220.84  4986.7  222.10  5007.3  221.75  5035.7  223.65  5121.0  226.86
  5177.9  230.33  5192.1  231.85  5233.9  233.49  5333.4  240.70  5354.3  243.17
  5368.5  245.80  5382.7  247.35  5390.3  246.91  5425.4  248.06  5457.9  247.67
#Mann=3,-1,0
  4545.7    0.12       0  4962.9    0.05       0  4966.9    0.12       0
Bank Sta=4962.9,4966.9
Exp/Cntr=0.3,0.1

Type RM Length L Ch R = 1,108,0,0,0
BEGIN DESCRIPTION:
LGII3818
END DESCRIPTION:
XS GIS Cut Line= 4
      2557683.30     13584796.62      2557136.43     13584645.58
      2556928.09     13584718.50      2556631.88     13585181.00
#Sta/Elev= 30
  4323.2  235.20  4352.9  233.58  4455.9  230.88  4461.1  229.65  4500.7  228.19
  4614.1  225.19  4767.5  221.97  4954.3  219.97  4962.7  218.65  4968.0  219.44
  4987.4  218.33  4997.0  216.57  4997.3  216.07  5001.0  216.57  5008.6  219.33
  5019.2  220.66  5110.3  221.96  5134.8  223.28  5183.1  225.22  5234.7  228.53
  5277.0  229.86  5292.2  231.24  5298.1  230.77  5328.5  232.49  5364.9  233.04
  5386.0  231.92  5401.2  233.39  5451.0  235.13  5537.4  237.79  5660.5  243.18
#Mann=6,-1,0
  4323.2    0.12       0  4954.3    0.05       0  4997.0    0.05       0
  5001.0    0.05       0  5134.8    0.12       0  5451.0    0.05       0
Bank Sta=4997,5001
Exp/Cntr=0.3,0.1

Chan Stop Cuts=-1