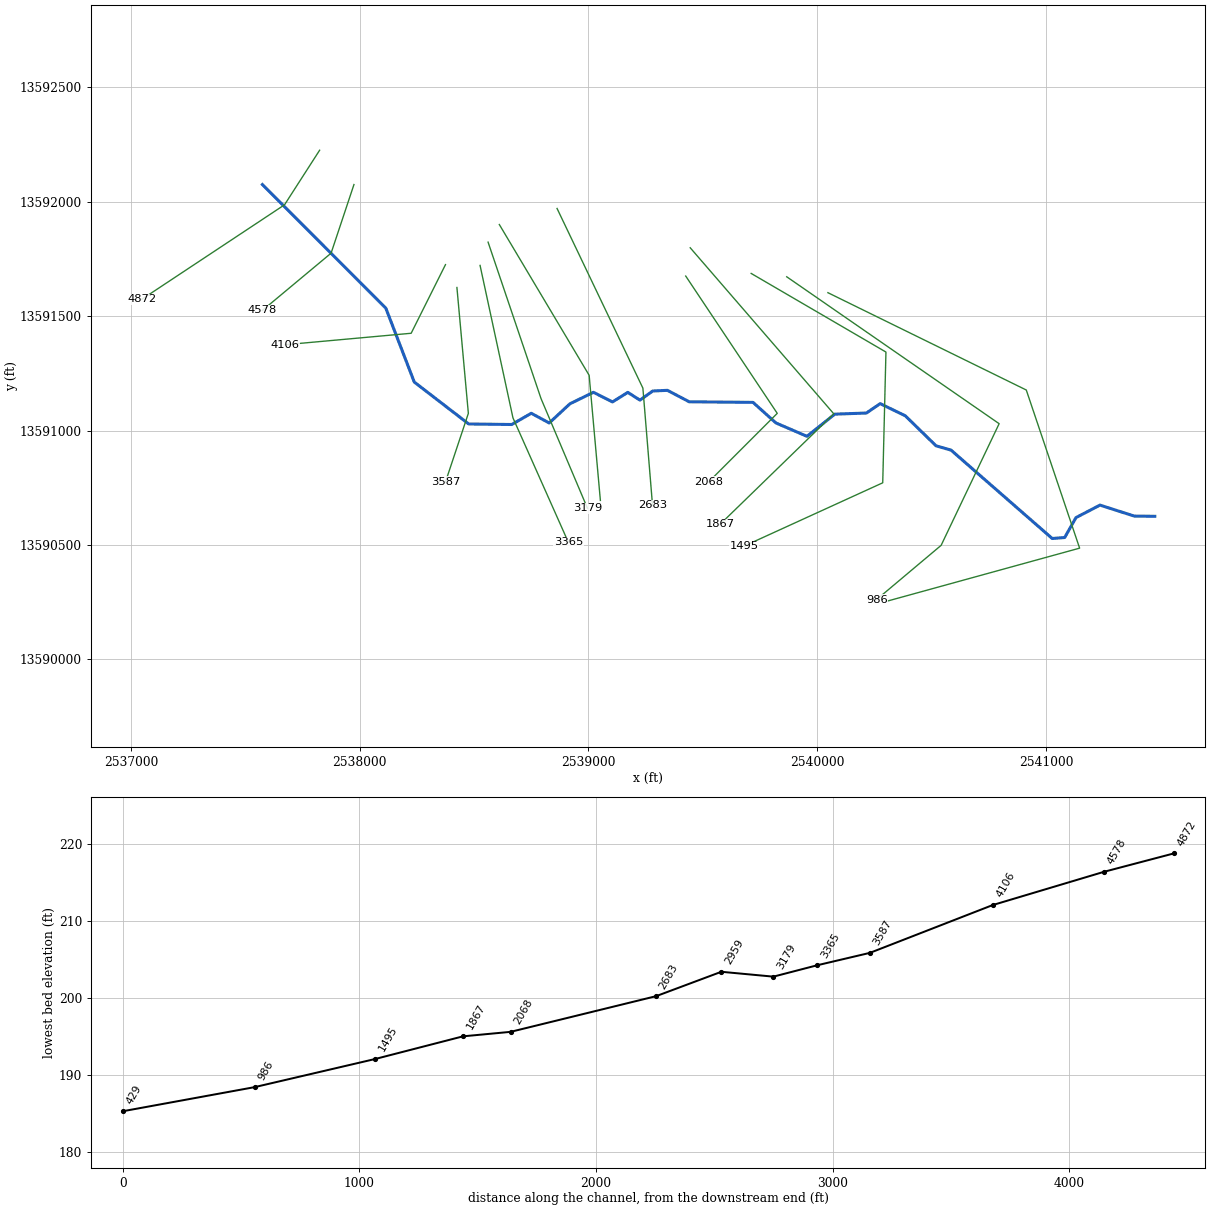
--- TRIB 6 TO IRISH CREEK.prj (project) ---

Proj Title=TRIB 6 TO IRISH CREEK Base Level Engineering
Current Plan=p01
Default Exp/Contr=0.3,0.1
English Units
Geom File=g01
Flow File=f01
Plan File=p01
BEGIN DESCRIPTION:
TRIB 6 TO IRISH CREEK
END DESCRIPTION:

--- TRIB 6 TO IRISH CREEK.p01 (plan) ---

Plan Title=Multiple Run
Short Identifier=Multiple
Geom File=g01
Flow File=f01
Subcritical Flow
K Sum by GR= 0
Std Step Tol= 0.01
Critical Tol= 0.01
Num of Std Step Trials= 20
Max Error Tol= 0.3
Flow Tol Ratio= 0.001
Split Flow NTrial= 30
Split Flow Tol= 0.02
Split Flow Ratio= 0.02
Log Output Level= 0
Friction Slope Method= 1
Unsteady Friction Slope Method= 2
Unsteady Bridges Friction Slope Method= 1
Parabolic Critical Depth
Global Vel Dist=  1 , 1 , 1
Global Log Level= 0
CheckData=True
Encroach Param= -1, 0, 0, 0
BEGIN DESCRIPTION:
Multiple Run
END DESCRIPTION:

--- TRIB 6 TO IRISH CREEK.f01 (steady flow) ---

Flow Title=Multiple
Number of Profiles=7
Profile Names=10-year,25-year,50-year,1pct_min,100-year,1pct_plu,500-year
River Rch & RM= TRIB 6 TO IRISH ,Reach-1,4872
     456     723     960     619    1235    2465    2022
Boundary for River Rch & Prof#=TRIB 6 TO IRISH ,Reach-1,1
Up Type=0
Dn Type=3
Dn Slope=0.005
Boundary for River Rch & Prof#=TRIB 6 TO IRISH ,Reach-1,2
Up Type=0
Dn Type=3
Dn Slope=0.005
Boundary for River Rch & Prof#=TRIB 6 TO IRISH ,Reach-1,3
Up Type=0
Dn Type=3
Dn Slope=0.005
Boundary for River Rch & Prof#=TRIB 6 TO IRISH ,Reach-1,4
Up Type=0
Dn Type=3
Dn Slope=0.005
Boundary for River Rch & Prof#=TRIB 6 TO IRISH ,Reach-1,5
Up Type=0
Dn Type=3
Dn Slope=0.005
Boundary for River Rch & Prof#=TRIB 6 TO IRISH ,Reach-1,6
Up Type=0
Dn Type=3
Dn Slope=0.005
Boundary for River Rch & Prof#=TRIB 6 TO IRISH ,Reach-1,7
Up Type=0
Dn Type=3
Dn Slope=0.005

--- TRIB 6 TO IRISH CREEK.g01 (geometry) ---

Geom Title=Existing Conditions

River Reach=TRIB 6 TO IRISH ,Reach-1
Reach XY= 30
      2537575.00     13592075.00      2538114.24     13591534.68
      2538238.61     13591211.76      2538476.47     13591028.55
      2538664.50     13591026.24      2538750.04     13591075.31
      2538828.40     13591032.83      2538918.95     13591116.84
      2539021.69     13591166.93      2539104.84     13591124.90
      2539171.77     13591166.68      2539224.90     13591132.80
      2539280.89     13591172.64      2539345.04     13591175.58
      2539440.22     13591125.52      2539719.14     13591122.94
      2539818.95     13591033.16      2539954.87     13590974.60
      2540076.47     13591071.44      2540214.56     13591076.40
      2540275.01     13591117.47      2540384.68     13591064.25
      2540518.95     13590933.16      2540584.68     13590914.22
      2541026.67     13590528.09      2541081.31     13590532.39
      2541130.62     13590619.37      2541235.53     13590673.92
      2541385.42     13590626.02      2541475.00     13590625.00

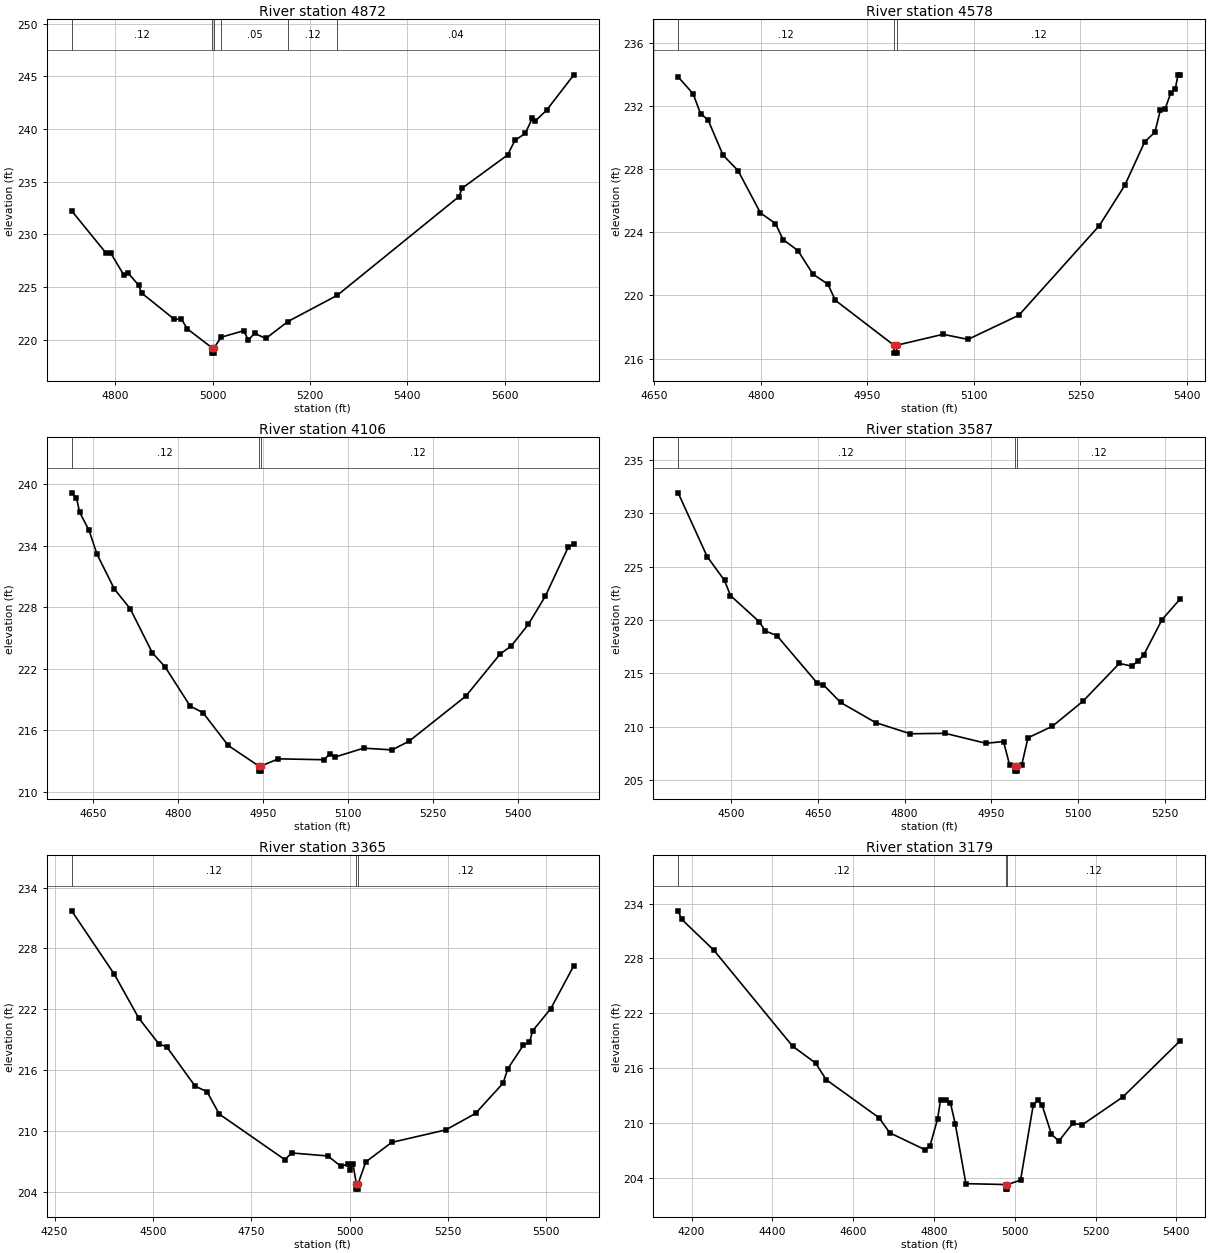
Type RM Length L Ch R = 1,4872,294,294,294
BEGIN DESCRIPTION:
TRIB 6 TO IRISH CREEK 8.0
END DESCRIPTION:
XS GIS Cut Line= 3
      2537824.99     13592224.98      2537671.58     13591986.43
      2537048.35     13591573.75
#Sta/Elev= 30
  4710.6  232.23  4781.9  228.18  4790.8  228.22  4817.9  226.12  4827.1  226.29
  4848.3  225.16  4854.2  224.43  4920.9  221.95  4936.1  221.93  4948.4  221.01
  4999.0  219.22  4999.2  218.72  5002.7  218.72  5003.0  219.22  5017.5  220.23
  5064.1  220.85  5073.2  219.95  5086.1  220.60  5109.3  220.11  5154.6  221.72
  5255.7  224.20  5505.8  233.58  5512.4  234.38  5605.7  237.53  5620.7  238.92
  5641.8  239.57  5656.8  241.05  5662.8  240.77  5685.7  241.78  5741.7  245.14
#Mann=6,-1,0
  4710.6    0.12       0  4999.0    0.05       0  5003.0    0.12       0
  5017.5    0.05       0  5154.6    0.12       0  5255.7    0.04       0
Bank Sta=4999,5003
Exp/Cntr=0.3,0.1

Type RM Length L Ch R = 1,4578,472,472,472
BEGIN DESCRIPTION:
TRIB 6 TO IRISH CREEK 7.0
END DESCRIPTION:
XS GIS Cut Line= 3
      2537974.99     13592074.98      2537875.00     13591775.00
      2537575.02     13591525.01
#Sta/Elev= 30
  4683.8  233.83  4704.9  232.76  4715.4  231.50  4725.9  231.11  4747.0  228.88
  4768.1  227.90  4799.7  225.22  4820.8  224.55  4831.4  223.54  4852.4  222.84
  4873.5  221.35  4894.6  220.71  4905.1  219.69  4987.5  216.85  4987.7  216.35
  4991.2  216.35  4991.5  216.85  5056.6  217.54  5091.8  217.22  5163.4  218.75
  5276.6  224.42  5312.4  226.97  5340.4  229.72  5354.7  230.33  5362.5  231.73
  5369.0  231.79  5376.9  232.79  5383.4  233.06  5387.3  233.96  5390.5  233.96
#Mann=3,-1,0
  4683.8    0.12       0  4987.5    0.05       0  4991.5    0.12       0
Bank Sta=4987.5,4991.5
Exp/Cntr=0.3,0.1

Type RM Length L Ch R = 1,4106,519,519,519
BEGIN DESCRIPTION:
TRIB 6 TO IRISH CREEK 6.0
END DESCRIPTION:
XS GIS Cut Line= 3
      2538375.02     13591725.04      2538225.00     13591425.00
      2537675.02     13591375.00
#Sta/Elev= 30
  4611.6  239.17  4620.0  238.69  4625.6  237.29  4642.4  235.50  4656.4  233.19
  4687.1  229.79  4715.1  227.87  4754.2  223.57  4776.6  222.21  4821.3  218.36
  4843.6  217.74  4888.4  214.53  4942.3  212.53  4942.5  212.03  4946.0  212.03
  4946.3  212.53  4977.2  213.23  5057.5  213.14  5067.5  213.69  5077.6  213.41
  5127.8  214.27  5178.0  214.10  5208.1  214.95  5308.5  219.35  5368.8  223.44
  5388.9  224.25  5419.0  226.35  5449.1  229.11  5489.3  233.86  5499.3  234.17
#Mann=3,-1,0
  4611.6    0.12       0  4942.3    0.05       0  4946.3    0.12       0
Bank Sta=4942.3,4946.3
Exp/Cntr=0.3,0.1

Type RM Length L Ch R = 1,3587,222,222,222
BEGIN DESCRIPTION:
TRIB 6 TO IRISH CREEK 5.0
END DESCRIPTION:
XS GIS Cut Line= 3
      2538425.00     13591624.99      2538475.00     13591075.00
      2538375.00     13590774.99
#Sta/Elev= 30
  4408.4  231.91  4458.6  225.94  4488.7  223.70  4498.8  222.29  4549.0  219.82
  4559.0  218.97  4579.1  218.54  4649.4  214.06  4659.4  213.94  4689.5  212.27
  4749.8  210.39  4810.0  209.34  4870.3  209.38  4940.6  208.45  4971.2  208.61
  4981.7  206.42  4990.3  206.34  4990.5  205.84  4994.0  205.84  4994.3  206.34
  5002.8  206.45  5013.4  208.96  5055.5  210.04  5108.2  212.37  5171.5  215.93
  5192.6  215.68  5203.1  216.11  5213.6  216.72  5245.3  220.03  5276.9  221.98
#Mann=3,-1,0
  4408.4    0.12       0  4990.3    0.05       0  4994.3    0.12       0
Bank Sta=4990.3,4994.3
Exp/Cntr=0.3,0.1

Type RM Length L Ch R = 1,3365,186,186,186
BEGIN DESCRIPTION:
Mapping XS 3bacfd74
END DESCRIPTION:
XS GIS Cut Line= 3
      2538526.14     13591721.54      2538669.88     13591055.44
      2538911.76     13590512.08
#Sta/Elev= 30
  4293.5  231.70  4402.0  225.44  4463.9  221.12  4515.0  218.58  4535.5  218.26
  4607.1  214.41  4637.8  213.84  4668.5  211.65  4835.3  207.15  4852.6  207.81
  4944.7  207.51  4978.1  206.48  4995.8  206.74  5001.3  206.15  5008.3  206.74
  5017.1  204.74  5017.3  204.24  5020.8  204.24  5021.1  204.74  5041.1  206.93
  5106.8  208.85  5244.7  210.09  5319.8  211.71  5389.6  214.68  5402.3  216.14
  5441.5  218.45  5457.0  218.72  5464.8  219.85  5511.2  222.06  5569.7  226.29
#Mann=3,-1,0
  4293.5    0.12       0  5017.1    0.05       0  5021.1    0.12       0
Bank Sta=5017.1,5021.1
Exp/Cntr=0.3,0.1

Type RM Length L Ch R = 1,3179,220,220,220
BEGIN DESCRIPTION:
Mapping XS c9250611
END DESCRIPTION:
XS GIS Cut Line= 3
      2538561.18     13591823.26      2538792.58     13591139.58
      2538995.75     13590659.69
#Sta/Elev= 30
  4166.7  233.20  4175.4  232.28  4255.6  228.87  4449.9  218.40  4507.0  216.55
  4533.2  214.73  4664.2  210.56  4690.4  208.92  4777.2  207.08  4789.9  207.47
  4808.9  210.44  4816.1  212.48  4830.0  212.52  4840.5  212.22  4852.8  209.86
  4878.9  203.36  4977.7  203.26  4977.9  202.76  4981.4  202.76  4981.7  203.26
  5014.2  203.74  5045.5  211.93  5056.2  212.47  5067.2  211.99  5090.7  208.76
  5109.0  208.02  5143.5  209.96  5167.2  209.80  5267.4  212.84  5409.6  219.00
#Mann=3,-1,0
  4166.7    0.12       0  4977.7    0.05       0  4981.7    0.12       0
Bank Sta=4977.7,4981.7
Exp/Cntr=0.3,0.1

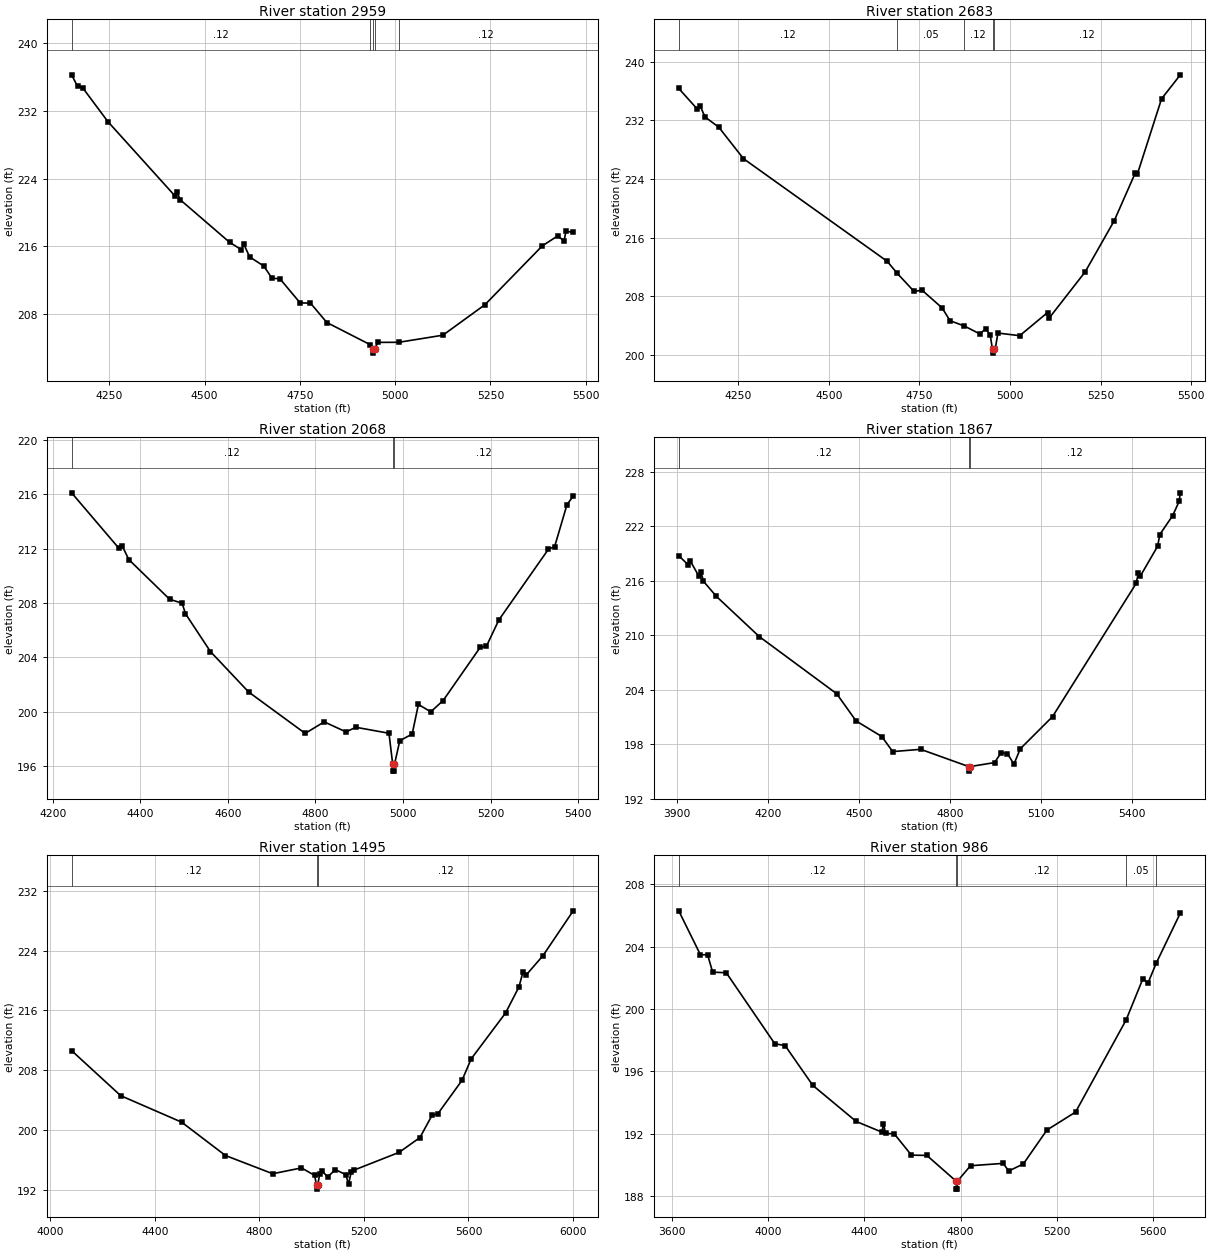
Type RM Length L Ch R = 1,2959,276,276,276
BEGIN DESCRIPTION:
Mapping XS c1f5b7e7
END DESCRIPTION:
XS GIS Cut Line= 3
      2538610.30     13591900.30      2539002.93     13591241.25
      2539052.00     13590694.39
#Sta/Elev= 30
  4151.1  236.29  4166.6  234.92  4180.6  234.73  4246.4  230.75  4421.6  222.01
  4427.4  222.43  4436.6  221.50  4565.7  216.49  4596.8  215.61  4602.7  216.29
  4618.3  214.76  4655.2  213.69  4676.7  212.26  4698.1  212.16  4750.7  209.33
  4777.9  209.30  4820.8  207.01  4934.6  204.39  4942.6  203.89  4942.8  203.39
  4946.6  203.89  4954.6  204.66  5009.8  204.67  5125.3  205.51  5235.8  209.12
  5386.4  216.08  5426.5  217.24  5443.2  216.66  5448.3  217.79  5467.3  217.67
#Mann=5,-1,0
  4151.1    0.12       0  4934.6    0.05       0  4942.6    0.05       0
  4946.6    0.05       0  5009.8    0.12       0
Bank Sta=4942.6,4946.6
Exp/Cntr=0.3,0.1

Type RM Length L Ch R = 1,2683,615,615,615
BEGIN DESCRIPTION:
Mapping XS 9c254e45
END DESCRIPTION:
XS GIS Cut Line= 3
      2538862.70     13591970.44      2539237.81     13591185.16
      2539279.88     13590673.36
#Sta/Elev= 30
  4086.2  236.34  4136.6  233.57  4145.8  233.89  4158.7  232.45  4196.7  231.05
  4264.8  226.76  4661.5  212.75  4688.3  211.15  4735.0  208.67  4757.7  208.80
  4812.6  206.41  4834.7  204.65  4873.7  203.94  4916.5  202.86  4933.6  203.56
  4945.6  202.66  4951.8  200.73  4952.0  200.23  4955.8  200.73  4959.1  200.73
  4966.7  202.97  5026.9  202.61  5103.7  205.77  5108.7  205.05  5207.5  211.32
  5287.7  218.30  5346.2  224.87  5351.2  224.61  5418.2  234.93  5470.0  238.20
#Mann=5,-1,0
  4086.2    0.12       0  4688.3    0.05       0  4873.7    0.12       0
  4951.8    0.05       0  4955.8    0.12       0
Bank Sta=4951.8,4955.8
Exp/Cntr=0.3,0.1

Type RM Length L Ch R = 1,2068,201,201,201
BEGIN DESCRIPTION:
TRIB 6 TO IRISH CREEK 2.0
END DESCRIPTION:
XS GIS Cut Line= 3
      2539425.03     13591674.96      2539825.00     13591075.00
      2539525.02     13590775.02
#Sta/Elev= 30
  4243.3  216.11  4351.4  212.02  4358.9  212.19  4374.0  211.19  4467.1  208.27
  4495.6  207.98  4503.2  207.21  4560.2  204.42  4647.4  201.44  4776.6  198.39
  4820.1  199.24  4869.7  198.50  4892.3  198.84  4967.9  198.40  4976.5  196.11
  4976.8  195.61  4980.3  195.61  4980.5  196.11  4992.6  197.85  5020.9  198.34
  5035.1  200.52  5063.4  199.98  5091.6  200.81  5176.5  204.74  5190.6  204.82
  5218.9  206.75  5332.1  211.96  5346.2  212.15  5374.5  215.25  5388.6  215.86
#Mann=3,-1,0
  4243.3    0.12       0  4976.5    0.05       0  4980.5    0.12       0
Bank Sta=4976.5,4980.5
Exp/Cntr=0.3,0.1

Type RM Length L Ch R = 1,1867,372,372,372
BEGIN DESCRIPTION:
Mapping XS c6b9e168
END DESCRIPTION:
XS GIS Cut Line= 3
      2539444.67     13591798.65      2540072.19     13591072.97
      2539574.77     13590589.56
#Sta/Elev= 30
  3906.4  218.74  3937.7  217.73  3944.7  218.14  3973.2  216.46  3979.8  216.98
  3987.5  215.94  4030.2  214.27  4171.7  209.84  4426.8  203.55  4490.9  200.55
  4575.4  198.84  4611.5  197.18  4703.7  197.43  4862.1  195.53  4862.3  195.03
  4866.1  195.53  4947.1  195.97  4968.5  197.04  4989.6  196.97  5010.9  195.79
  5032.0  197.49  5138.2  201.03  5414.0  215.70  5420.9  216.84  5428.1  216.53
  5484.7  219.79  5491.7  221.07  5534.1  223.15  5555.4  224.72  5559.4  225.66
#Mann=3,-1,0
  3906.4    0.12       0  4862.1    0.05       0  4866.1    0.12       0
Bank Sta=4862.1,4866.1
Exp/Cntr=0.3,0.1

Type RM Length L Ch R = 1,1495,509,509,509
BEGIN DESCRIPTION:
Mapping XS 8bb06883
END DESCRIPTION:
XS GIS Cut Line= 4
      2539711.06     13591686.51      2540300.07     13591342.92
      2540286.05     13590771.47      2539679.78     13590494.62
#Sta/Elev= 30
  4081.0  210.63  4268.8  204.60  4502.3  201.05  4669.8  196.59  4850.8  194.15
  4960.9  194.93  5010.9  193.93  5018.9  192.59  5019.1  192.09  5022.9  192.59
  5030.9  194.16  5040.9  194.48  5060.9  193.73  5090.9  194.70  5130.9  194.02
  5140.9  192.74  5150.9  194.34  5160.9  194.62  5334.5  197.01  5414.2  198.99
  5460.3  201.95  5483.3  202.20  5575.4  206.65  5610.5  209.53  5742.1  215.67
  5793.7  219.18  5808.4  221.14  5822.2  220.80  5885.3  223.34  6001.0  229.34
#Mann=3,-1,0
  4081.0    0.12       0  5018.9    0.05       0  5022.9    0.12       0
Bank Sta=5018.9,5022.9
Exp/Cntr=0.3,0.1

Type RM Length L Ch R = 1,986,557,557,557
BEGIN DESCRIPTION:
4849
END DESCRIPTION:
XS GIS Cut Line= 4
      2539866.47     13591671.85      2540794.82     13591029.78
      2540541.27     13590498.13      2540259.55     13590261.32
#Sta/Elev= 30
  3627.7  206.29  3718.0  203.47  3747.5  203.48  3768.7  202.36  3825.4  202.32
  4027.1  197.77  4070.1  197.65  4185.2  195.10  4365.4  192.79  4472.9  192.10
  4478.9  192.65  4487.7  192.02  4523.6  192.00  4595.2  190.63  4659.4  190.61
  4781.9  188.95  4782.2  188.45  4785.7  188.45  4785.9  188.95  4841.1  189.95
  4976.7  190.10  5000.0  189.61  5060.9  190.07  5158.8  192.24  5277.8  193.39
  5487.9  199.29  5558.1  201.95  5579.0  201.66  5613.4  202.94  5713.5  206.15
#Mann=5,-1,0
  3627.7    0.12       0  4781.9    0.05       0  4785.9    0.12       0
  5487.9    0.05       0  5613.4    0.04       0
Bank Sta=4781.9,4785.9
Exp/Cntr=0.3,0.1

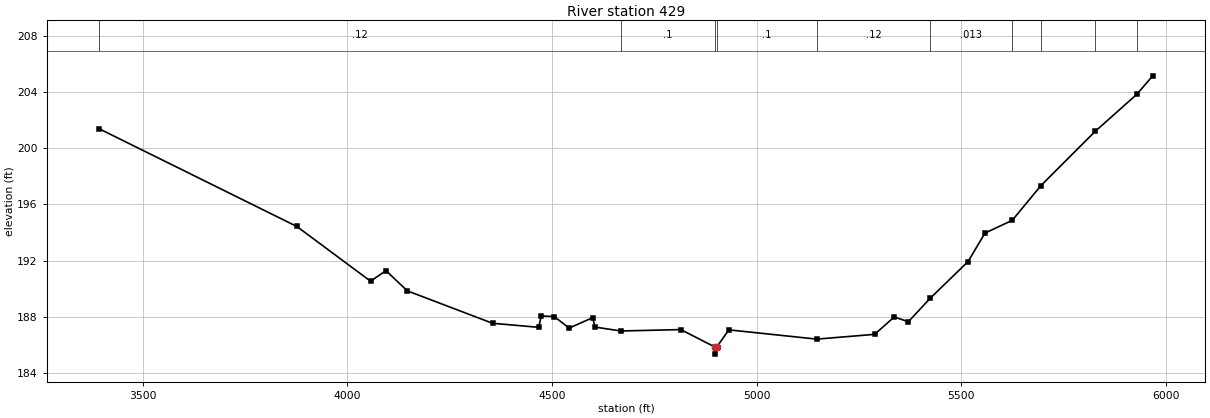
Type RM Length L Ch R = 1,429,0,0,0
BEGIN DESCRIPTION:
4850
END DESCRIPTION:
XS GIS Cut Line= 4
      2540046.39     13591602.34      2540913.42     13591177.00
      2541146.53     13590485.86      2540299.98     13590252.75
#Sta/Elev= 30
  3394.4  201.39  3876.9  194.43  4056.9  190.53  4094.6  191.28  4146.8  189.84
  4354.8  187.53  4467.8  187.24  4473.8  188.05  4505.3  188.01  4542.1  187.19
  4599.7  187.93  4605.0  187.26  4668.3  186.98  4814.8  187.08  4898.5  185.83
  4898.7  185.33  4902.5  185.83  4932.1  187.06  5146.8  186.40  5288.2  186.74
  5336.2  187.98  5370.6  187.64  5424.3  189.32  5516.4  191.93  5557.9  193.96
  5624.5  194.87  5694.6  197.35  5827.0  201.21  5928.2  203.84  5967.6  205.17
#Mann=10,-1,0
  3394.4    0.12       0  4668.3     0.1       0  4898.5    0.05       0
  4902.5     0.1       0  5146.8    0.12       0  5424.3   0.013       0
  5624.5    0.12       0  5694.6    0.04       0  5827.0    0.05       0
  5928.2    0.04       0
Bank Sta=4898.5,4902.5
Exp/Cntr=0.3,0.1

Chan Stop Cuts=-1