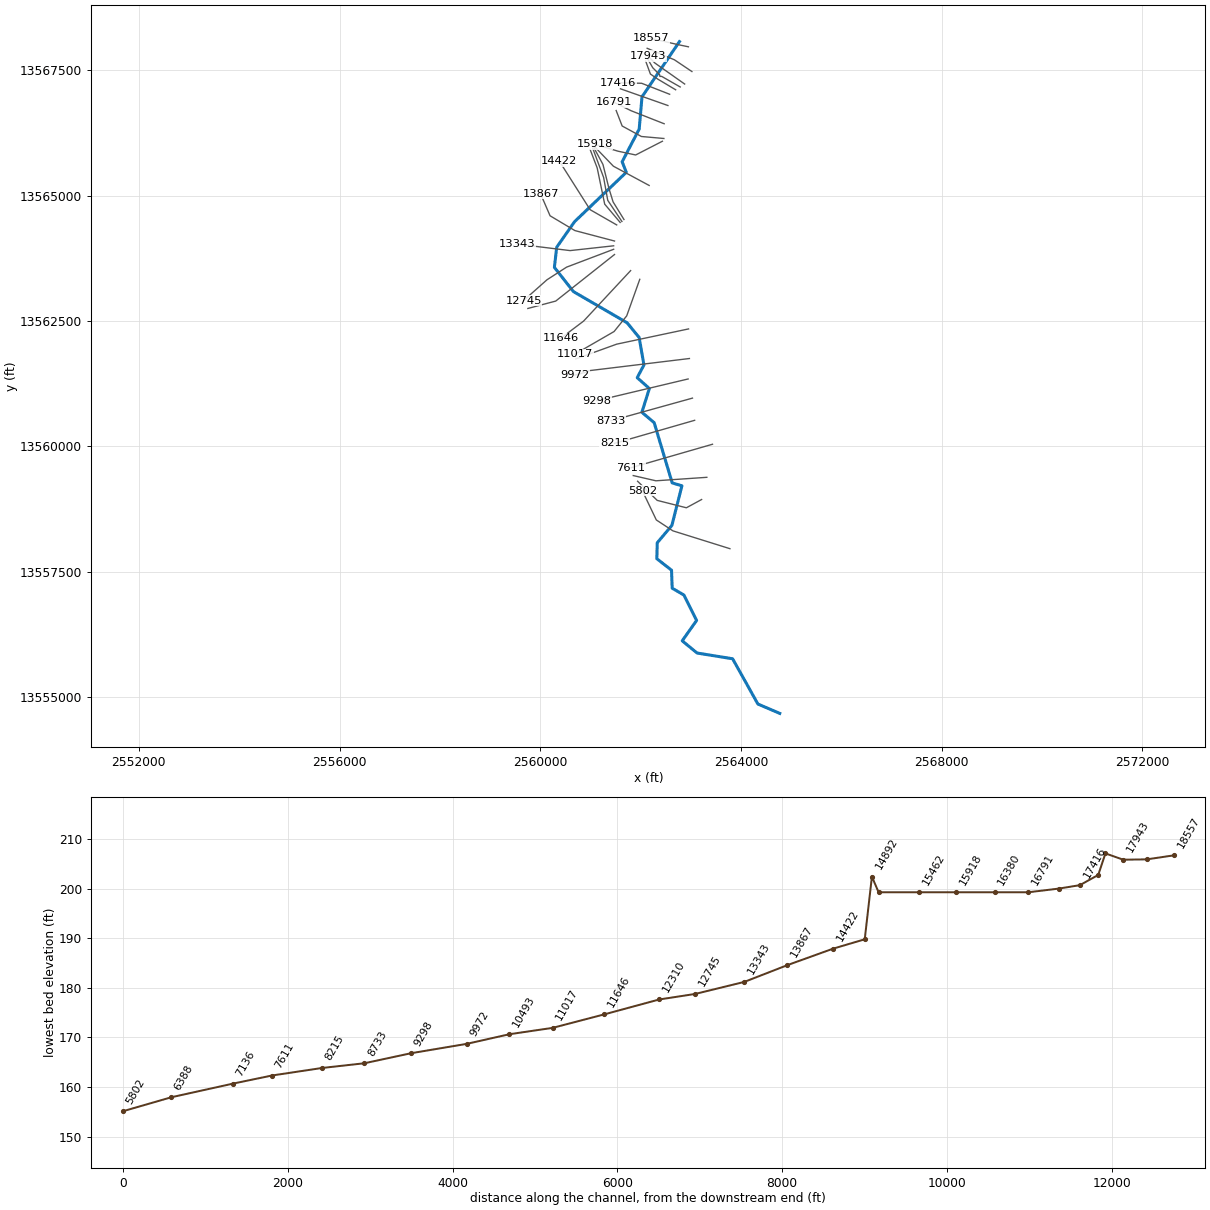
--- TRIB 6 TO PRICE CREEK.prj (project) ---

Proj Title=TRIB 6 TO PRICE CREEK Base Level Engineering
Current Plan=p01
Default Exp/Contr=0.3,0.1
English Units
Geom File=g01
Flow File=f01
Plan File=p01
BEGIN DESCRIPTION:
TRIB 6 TO PRICE CREEK
END DESCRIPTION:

--- TRIB 6 TO PRICE CREEK.p01 (plan) ---

Plan Title=Multiple Run
Short Identifier=Multiple
Geom File=g01
Flow File=f01
Subcritical Flow
K Sum by GR= 0
Std Step Tol= 0.01
Critical Tol= 0.01
Num of Std Step Trials= 20
Max Error Tol= 0.3
Flow Tol Ratio= 0.001
Split Flow NTrial= 30
Split Flow Tol= 0.02
Split Flow Ratio= 0.02
Log Output Level= 0
Friction Slope Method= 1
Unsteady Friction Slope Method= 2
Unsteady Bridges Friction Slope Method= 1
Parabolic Critical Depth
Global Vel Dist=  1 , 1 , 1
Global Log Level= 0
CheckData=True
Encroach Param= -1, 0, 0, 0
BEGIN DESCRIPTION:
Multiple Run
END DESCRIPTION:

--- TRIB 6 TO PRICE CREEK.f01 (steady flow) ---

Flow Title=Multiple
Number of Profiles=7
Profile Names=10-year,25-year,50-year,1pct_min,100-year,1pct_plu,500-year
River Rch & RM= TRIB 6 TO PRICE ,Reach-1,18557
     403     623     814     517    1031    2057    1633
River Rch & RM= TRIB 6 TO PRICE ,Reach-1,17416
     545     858    1135     728    1452    2897    2349
River Rch & RM= TRIB 6 TO PRICE ,Reach-1,15918
     781    1258    1688    1097    2190    4369    3643
River Rch & RM= TRIB 6 TO PRICE ,Reach-1,13343
    1019    1664    2256    1479    2952    5890    5001
River Rch & RM= TRIB 6 TO PRICE ,Reach-1,11646
    1042    1703    2309    1514    3022    6029    5120
River Rch & RM= TRIB 6 TO PRICE ,Reach-1,10493
    1334    2203    3008    1984    3959    7899    6789
River Rch & RM= TRIB 6 TO PRICE ,Reach-1,5802
    1632    2719    3734    2475    4938    9853    8554
River Rch & RM= TRIB 6 TO PRICE ,Reach-1,2523
    1700    2835    3895    2583    5155   10285    8938
Boundary for River Rch & Prof#=TRIB 6 TO PRICE ,Reach-1,1
Up Type=0
Dn Type=3
Dn Slope=0.005
Boundary for River Rch & Prof#=TRIB 6 TO PRICE ,Reach-1,2
Up Type=0
Dn Type=3
Dn Slope=0.005
Boundary for River Rch & Prof#=TRIB 6 TO PRICE ,Reach-1,3
Up Type=0
Dn Type=3
Dn Slope=0.005
Boundary for River Rch & Prof#=TRIB 6 TO PRICE ,Reach-1,4
Up Type=0
Dn Type=3
Dn Slope=0.005
Boundary for River Rch & Prof#=TRIB 6 TO PRICE ,Reach-1,5
Up Type=0
Dn Type=3
Dn Slope=0.005
Boundary for River Rch & Prof#=TRIB 6 TO PRICE ,Reach-1,6
Up Type=0
Dn Type=3
Dn Slope=0.005
Boundary for River Rch & Prof#=TRIB 6 TO PRICE ,Reach-1,7
Up Type=0
Dn Type=3
Dn Slope=0.005

--- TRIB 6 TO PRICE CREEK.g01 (geometry) ---

Geom Title=Existing Conditions

River Reach=TRIB 6 TO PRICE ,Reach-1
Reach XY= 30
      2562775.00     13568075.00      2562028.55     13566973.53
      2561972.94     13566330.85      2561633.07     13565678.30
      2561715.87     13565468.26      2560685.78     13564484.68
      2560328.54     13563973.53      2560282.50     13563571.42
      2560661.79     13563088.63      2561731.07     13562466.87
      2561971.71     13562173.64      2562067.47     13561624.99
      2561933.02     13561371.69      2562175.45     13561154.98
      2562026.58     13560681.04      2562271.47     13560473.55
      2562630.52     13559272.02      2562824.03     13559214.75
      2562625.00     13558425.00      2562332.82     13558078.41
      2562324.48     13557759.74      2562617.25     13557531.19
      2562630.42     13557172.32      2562864.35     13557035.00
      2563116.92     13556528.30      2562830.39     13556122.56
      2563126.46     13555878.54      2563834.80     13555764.52
      2564338.63     13554861.79      2564775.00     13554675.00

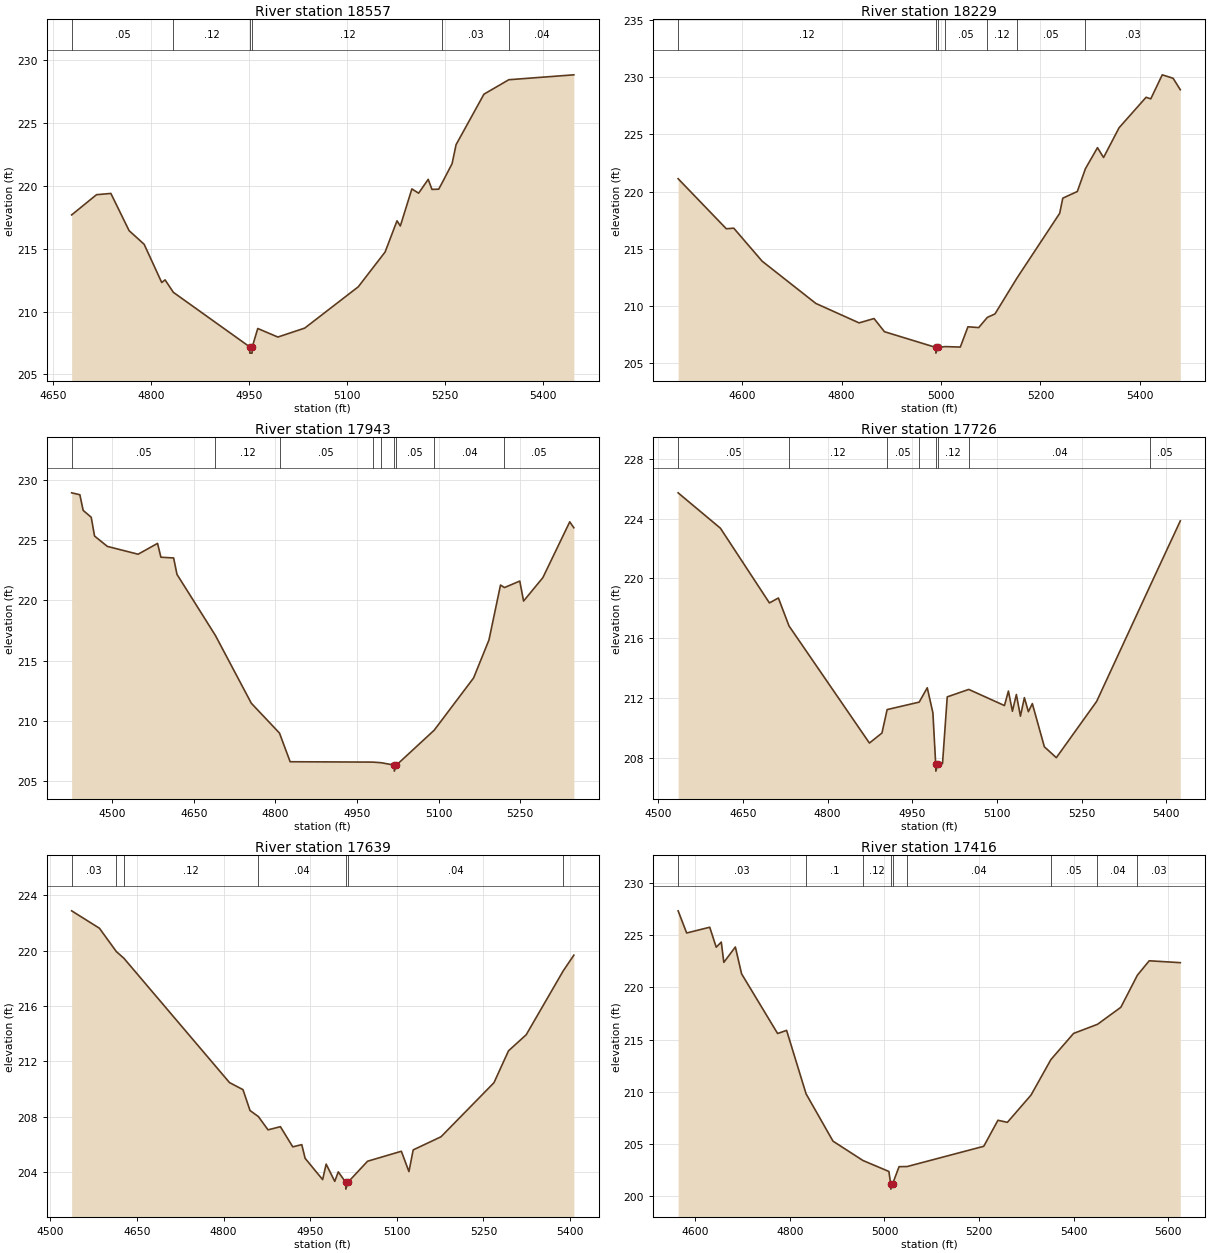
Type RM Length L Ch R = 1,18557,328,328,328
BEGIN DESCRIPTION:
LGII3103
END DESCRIPTION:
XS GIS Cut Line= 3
      2562953.79     13567971.47      2562739.52     13568016.32
      2562203.31     13568140.44
#Sta/Elev= 30
  4678.0  217.70  4716.1  219.31  4738.1  219.41  4766.0  216.45  4789.1  215.36
  4816.0  212.32  4821.1  212.53  4833.8  211.54  4950.7  207.20  4950.9  206.70
  4954.4  206.70  4954.7  207.20  4963.1  208.66  4993.9  207.98  5035.0  208.69
  5117.1  211.98  5158.2  214.75  5176.4  217.23  5181.5  216.82  5199.2  219.77
  5209.5  219.43  5224.2  220.53  5230.0  219.73  5240.3  219.75  5246.1  220.31
  5260.8  221.78  5266.9  223.29  5309.6  227.31  5347.7  228.46  5447.3  228.85
#Mann=6,-1,0
  4678.0    0.05       0  4833.8    0.12       0  4950.7    0.05       0
  4954.7    0.12       0  5246.1    0.03       0  5347.7    0.04       0
Bank Sta=4950.7,4954.7
Exp/Cntr=0.3,0.1

Type RM Length L Ch R = 1,18229,286,286,286
BEGIN DESCRIPTION:
LGII3102
END DESCRIPTION:
XS GIS Cut Line= 3
      2563023.58     13567478.12      2562674.74     13567712.34
      2562131.60     13567941.55
#Sta/Elev= 30
  4471.5  221.12  4568.4  216.75  4583.4  216.80  4640.4  213.92  4748.4  210.23
  4835.4  208.53  4865.4  208.91  4886.4  207.76  4989.5  206.39  4989.8  205.89
  4993.5  206.39  5008.5  206.46  5038.9  206.42  5054.2  208.19  5075.9  208.12
  5093.2  209.01  5108.5  209.31  5153.0  212.46  5238.7  218.10  5244.9  219.42
  5274.1  220.00  5290.5  222.00  5314.7  223.83  5326.9  222.97  5358.1  225.57
  5412.4  228.23  5421.8  228.09  5444.9  230.19  5466.7  229.89  5481.2  228.89
#Mann=7,-1,0
  4471.5    0.12       0  4989.5    0.05       0  4993.5    0.12       0
  5008.5    0.05       0  5093.2    0.12       0  5153.0    0.05       0
  5290.5    0.03       0
Bank Sta=4989.5,4993.5
Exp/Cntr=0.3,0.1

Type RM Length L Ch R = 1,17943,217,217,217
BEGIN DESCRIPTION:
LGII3101
END DESCRIPTION:
XS GIS Cut Line= 3
      2562879.03     13567228.97      2562286.04     13567647.56
      2562146.49     13567787.11
#Sta/Elev= 30
  4425.5  228.94  4440.6  228.78  4446.7  227.48  4461.5  226.91  4467.6  225.35
  4491.1  224.49  4547.7  223.84  4583.4  224.74  4589.6  223.59  4613.0  223.53
  4619.1  222.17  4689.8  217.09  4755.8  211.46  4807.6  208.98  4827.2  206.60
  4978.7  206.57  4994.3  206.52  5018.5  206.32  5018.7  205.82  5022.5  206.32
  5092.0  209.22  5164.4  213.56  5192.7  216.72  5213.9  221.28  5221.2  221.07
  5249.3  221.61  5256.3  219.95  5291.7  221.89  5341.2  226.53  5348.7  226.04
#Mann=9,-1,0
  4425.5    0.05       0  4689.8    0.12       0  4807.6    0.05       0
  4978.7    0.12       0  4994.3    0.05       0  5018.5    0.05       0
  5022.5    0.05       0  5092.0    0.04       0  5221.2    0.05       0
Bank Sta=5018.5,5022.5
Exp/Cntr=0.3,0.1

Type RM Length L Ch R = 1,17726,87,87,87
BEGIN DESCRIPTION:
4878
END DESCRIPTION:
XS GIS Cut Line= 6
      2562790.33     13567170.22      2562421.32     13567381.25
      2562386.06     13567380.91      2562380.02     13567415.16
      2562242.82     13567554.11      2562144.33     13567725.41
#Sta/Elev= 30
  4535.1  225.72  4610.1  223.35  4696.9  218.35  4712.8  218.68  4731.6  216.81
  4874.1  208.97  4896.3  209.64  4905.5  211.21  4962.3  211.71  4976.6  212.67
  4986.6  210.99  4991.5  207.59  4991.8  207.09  4995.5  207.59  5003.6  207.59
  5012.0  212.06  5050.1  212.56  5113.4  211.48  5120.4  212.45  5127.5  211.10
  5134.5  212.22  5141.7  210.77  5148.7  212.01  5155.8  211.07  5162.8  211.61
  5184.1  208.72  5205.3  207.99  5276.8  211.76  5371.8  219.52  5425.0  223.84
#Mann=8,-1,0
  4535.1    0.05       0  4731.6    0.12       0  4905.5    0.05       0
  4962.3    0.12       0  4991.5    0.05       0  4995.5    0.12       0
  5050.1    0.04       0  5371.8    0.05       0
Bank Sta=4991.5,4995.5
Exp/Cntr=0.3,0.1

Type RM Length L Ch R = 1,17639,223,223,223
BEGIN DESCRIPTION:
LGII3100
END DESCRIPTION:
XS GIS Cut Line= 4
      2562699.66     13567114.34      2562340.86     13567328.63
      2562196.34     13567428.29      2562101.65     13567687.46
#Sta/Elev= 30
  4537.1  222.89  4585.2  221.63  4614.5  219.94  4627.5  219.46  4810.4  210.46
  4833.7  209.95  4845.9  208.44  4860.4  208.00  4877.1  207.04  4898.5  207.27
  4919.9  205.81  4935.5  205.97  4941.3  204.98  4971.6  203.44  4977.7  204.56
  4992.6  203.31  4998.7  204.00  5011.5  203.25  5011.8  202.75  5015.5  203.25
  5049.4  204.77  5107.9  205.49  5121.0  204.02  5128.4  205.59  5176.6  206.54
  5268.2  210.45  5293.4  212.76  5324.0  213.92  5388.2  218.55  5406.5  219.68
#Mann=7,-1,0
  4537.1    0.03       0  4614.5    0.05       0  4627.5    0.12       0
  4860.4    0.04       0  5011.5    0.04       0  5015.5    0.04       0
  5388.2    0.05       0
Bank Sta=5011.5,5015.5
Exp/Cntr=0.3,0.1

Type RM Length L Ch R = 1,17416,255,255,255
BEGIN DESCRIPTION:
LGII3099
END DESCRIPTION:
XS GIS Cut Line= 3
      2562580.02     13567024.66      2562021.93     13567243.91
      2561559.25     13567253.86
#Sta/Elev= 30
  4563.4  227.32  4581.5  225.20  4630.3  225.75  4644.0  223.84  4654.7  224.33
  4660.1  222.39  4684.5  223.86  4697.7  221.29  4773.9  215.58  4792.9  215.88
  4834.1  209.81  4891.1  205.28  4954.4  203.43  5009.3  202.38  5013.1  201.19
  5013.4  200.69  5017.1  201.19  5030.8  202.84  5047.8  202.85  5210.0  204.79
  5240.0  207.28  5260.0  207.08  5310.0  209.69  5352.1  213.09  5400.0  215.59
  5450.6  216.46  5500.0  218.09  5535.0  221.16  5560.0  222.54  5625.8  222.36
#Mann=9,-1,0
  4563.4    0.03       0  4834.1     0.1       0  4954.4    0.12       0
  5013.1    0.05       0  5017.1    0.12       0  5047.8    0.04       0
  5352.1    0.05       0  5450.6    0.04       0  5535.0    0.03       0
Bank Sta=5013.1,5017.1
Exp/Cntr=0.3,0.1

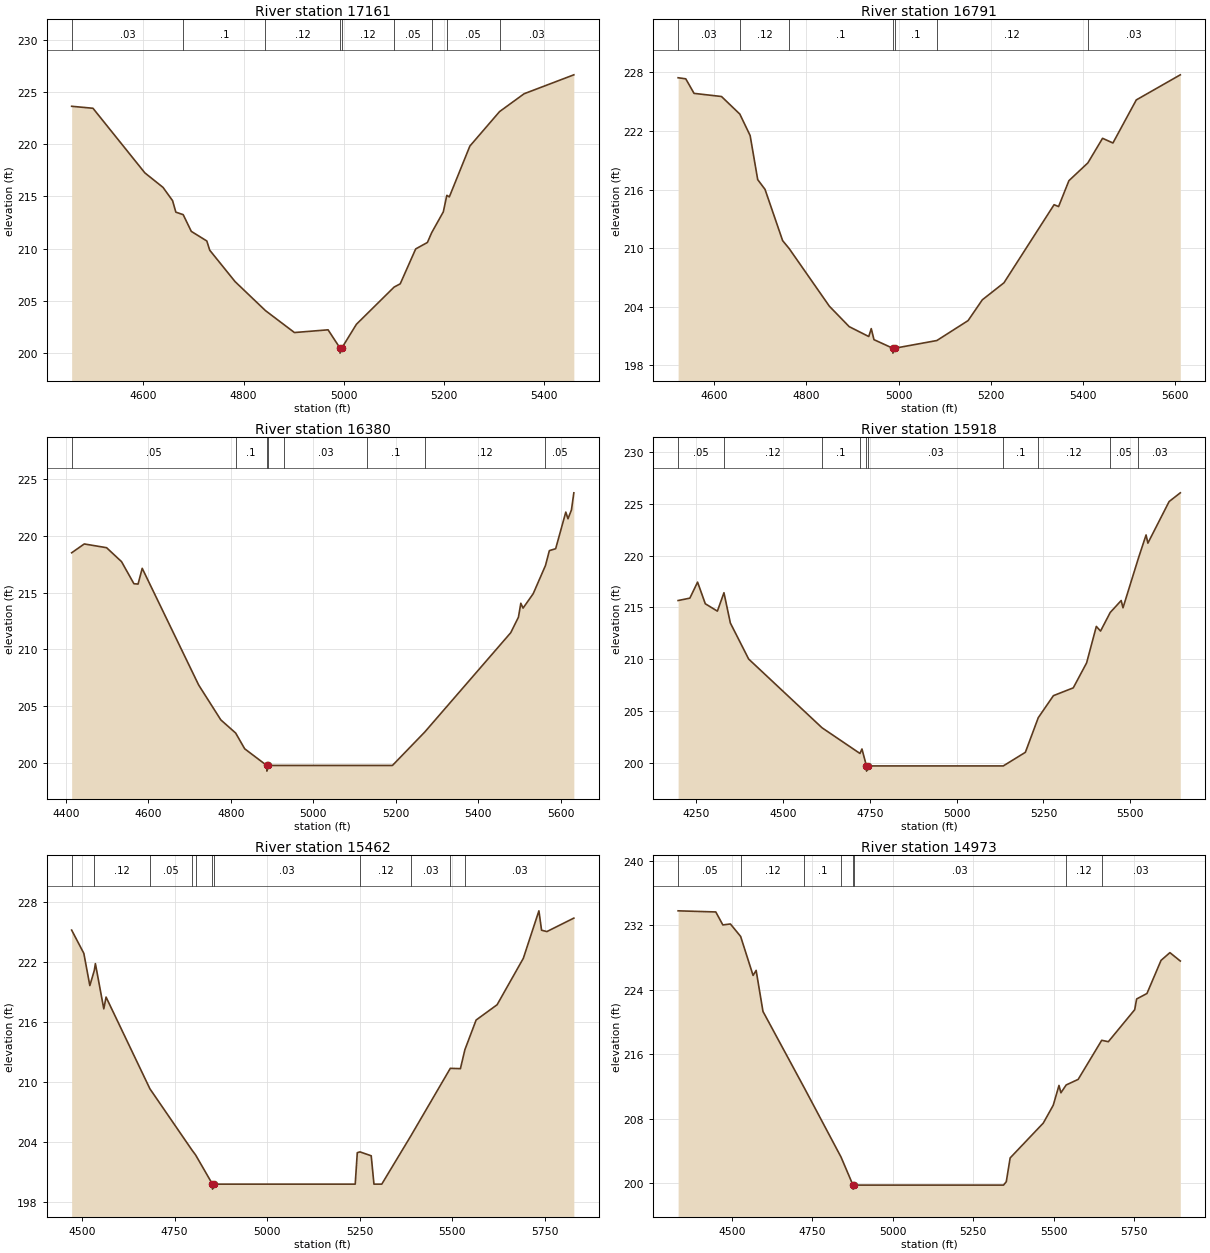
Type RM Length L Ch R = 1,17161,370,370,370
BEGIN DESCRIPTION:
LGII3098
END DESCRIPTION:
XS GIS Cut Line= 2
      2562545.14     13566800.41      2561599.14     13567134.00
#Sta/Elev= 30
  4456.7  223.62  4499.3  223.43  4602.9  217.25  4639.2  215.86  4658.3  214.59
  4664.8  213.49  4679.5  213.25  4695.7  211.65  4726.7  210.73  4732.5  209.85
  4783.2  206.84  4843.8  204.07  4901.7  201.97  4968.9  202.23  4992.5  200.50
  4992.8  200.00  4996.5  200.50  5025.5  202.76  5100.8  206.32  5113.0  206.63
  5143.9  209.97  5167.3  210.59  5175.8  211.52  5199.1  213.52  5206.1  215.10
  5211.1  214.95  5252.1  219.81  5311.4  223.11  5360.5  224.82  5459.8  226.63
#Mann=9,-1,0
  4456.7    0.03       0  4679.5     0.1       0  4843.8    0.12       0
  4992.5    0.05       0  4996.5    0.12       0  5100.8    0.05       0
  5175.8    0.03       0  5206.1    0.05       0  5311.4    0.03       0
Bank Sta=4992.5,4996.5
Exp/Cntr=0.3,0.1

Type RM Length L Ch R = 1,16791,411,411,411
BEGIN DESCRIPTION:
LGII3097
END DESCRIPTION:
XS GIS Cut Line= 3
      2562470.44     13566436.61      2561812.63     13566695.75
      2561469.35     13566864.90
#Sta/Elev= 30
  4521.7  227.46  4538.3  227.35  4556.3  225.86  4615.8  225.54  4655.6  223.74
  4678.0  221.54  4694.4  217.03  4710.3  216.03  4748.5  210.78  4762.5  209.98
  4850.0  204.06  4893.0  201.97  4935.4  200.96  4940.8  201.77  4946.7  200.64
  4987.5  199.76  4987.8  199.26  4991.5  199.76  5083.1  200.55  5150.9  202.59
  5181.8  204.72  5228.7  206.46  5337.5  214.46  5347.3  214.27  5369.7  216.92
  5410.8  218.74  5442.7  221.26  5465.2  220.78  5515.9  225.19  5611.4  227.76
#Mann=7,-1,0
  4521.7    0.03       0  4655.6    0.12       0  4762.5     0.1       0
  4987.5    0.05       0  4991.5     0.1       0  5083.1    0.12       0
  5410.8    0.03       0
Bank Sta=4987.5,4991.5
Exp/Cntr=0.3,0.1

Type RM Length L Ch R = 1,16380,462,462,462
BEGIN DESCRIPTION:
LGII3096
END DESCRIPTION:
XS GIS Cut Line= 4
      2562465.48     13566142.60      2562016.95     13566182.47
      2561633.23     13566391.77      2561513.77     13566700.37
#Sta/Elev= 30
  4413.7  218.52  4444.3  219.30  4498.4  218.97  4534.7  217.74  4564.8  215.79
  4574.8  215.76  4584.9  217.15  4721.8  206.86  4775.6  203.78  4811.6  202.62
  4833.5  201.23  4887.0  199.76  4887.3  199.26  4891.0  199.76  4928.8  199.76
  5130.4  199.76  5191.9  199.76  5270.1  202.70  5478.9  211.47  5497.6  212.84
  5503.4  214.07  5508.8  213.64  5533.4  214.91  5563.2  217.40  5572.6  218.71
  5587.9  218.88  5612.5  222.11  5617.8  221.52  5626.2  222.30  5632.0  223.81
#Mann=8,-1,0
  4413.7    0.05       0  4811.6     0.1       0  4887.0    0.03       0
  4891.0     0.1       0  4928.8    0.03       0  5130.4     0.1       0
  5270.1    0.12       0  5563.2    0.05       0
Bank Sta=4887,4891
Exp/Cntr=0.3,0.1

Type RM Length L Ch R = 1,15918,456,456,456
BEGIN DESCRIPTION:
LGII3095
END DESCRIPTION:
XS GIS Cut Line= 4
      2562435.52     13566087.78      2561902.33     13565813.71
      2561553.50     13565888.46      2561085.09     13566027.98
#Sta/Elev= 30
  4198.7  215.67  4232.5  215.90  4254.7  217.44  4276.9  215.36  4311.7  214.65
  4330.6  216.42  4349.0  213.51  4401.7  210.04  4612.8  203.43  4721.9  200.96
  4727.7  201.39  4740.6  199.76  4740.9  199.26  4744.7  199.76  5134.3  199.76
  5197.9  201.07  5235.0  204.40  5278.6  206.52  5335.7  207.27  5374.1  209.67
  5402.1  213.18  5414.2  212.73  5442.0  214.52  5473.6  215.67  5478.8  214.97
  5523.1  219.74  5545.2  221.98  5550.4  221.19  5611.5  225.19  5643.7  226.03
#Mann=10,-1,0
  4198.7    0.05       0  4330.6    0.12       0  4612.8     0.1       0
  4721.9    0.03       0  4740.6    0.03       0  4744.7    0.03       0
  5134.3     0.1       0  5235.0    0.12       0  5442.0    0.05       0
  5523.1    0.03       0
Bank Sta=4740.6,4744.7
Exp/Cntr=0.3,0.1

Type RM Length L Ch R = 1,15462,489,489,489
BEGIN DESCRIPTION:
LGII3094
END DESCRIPTION:
XS GIS Cut Line= 3
      2562171.45     13565205.74      2561458.82     13565589.46
      2561080.06     13565983.17
#Sta/Elev= 30
  4472.1  225.21  4505.0  222.88  4521.2  219.65  4533.2  221.16  4536.2  221.85
  4558.9  217.32  4565.0  218.50  4683.4  209.31  4796.8  203.18  4806.8  202.68
  4852.2  199.76  4852.4  199.26  4856.3  199.76  5237.6  199.76  5243.2  202.91
  5250.5  202.99  5280.8  202.60  5288.2  199.76  5309.3  199.76  5387.6  204.58
  5494.3  211.36  5521.6  211.33  5533.7  213.23  5564.0  216.20  5620.6  217.73
  5691.4  222.38  5733.5  227.14  5740.7  225.20  5754.9  225.06  5827.8  226.41
#Mann=11,-1,0
  4472.1    0.05       0  4533.2    0.12       0  4683.4    0.05       0
  4796.8    0.12       0  4806.8    0.03       0  4852.2    0.03       0
  4856.3    0.03       0  5250.5    0.12       0  5387.6    0.03       0
  5494.3    0.12       0  5533.7    0.03       0
Bank Sta=4852.2,4856.3
Exp/Cntr=0.3,0.1

Type RM Length L Ch R = 1,14973,81,81,81
BEGIN DESCRIPTION:
Mapping XS 2ee786e1
END DESCRIPTION:
XS GIS Cut Line= 5
      2561669.34     13564526.63      2561452.34     13564878.18
      2561372.04     13565138.59      2561250.51     13565624.70
      2561072.57     13565954.55
#Sta/Elev= 30
  4332.5  233.80  4449.7  233.66  4471.6  232.05  4495.1  232.17  4526.9  230.62
  4565.6  225.78  4575.1  226.41  4596.4  221.31  4724.4  211.86  4839.2  203.23
  4876.2  199.76  4876.5  199.26  4880.4  199.76  5344.3  199.76  5352.9  200.18
  5364.9  203.13  5468.0  207.46  5498.9  209.67  5516.8  212.13  5522.8  211.22
  5539.2  212.19  5576.4  212.88  5649.6  217.73  5670.3  217.56  5752.2  221.53
  5758.2  222.86  5790.3  223.54  5834.1  227.65  5861.7  228.61  5894.0  227.57
#Mann=8,-1,0
  4332.5    0.05       0  4526.9    0.12       0  4724.4     0.1       0
  4839.2    0.03       0  4876.2    0.03       0  4880.4    0.03       0
  5539.2    0.12       0  5649.6    0.03       0
Bank Sta=4876.2,4880.4
Exp/Cntr=0.3,0.1

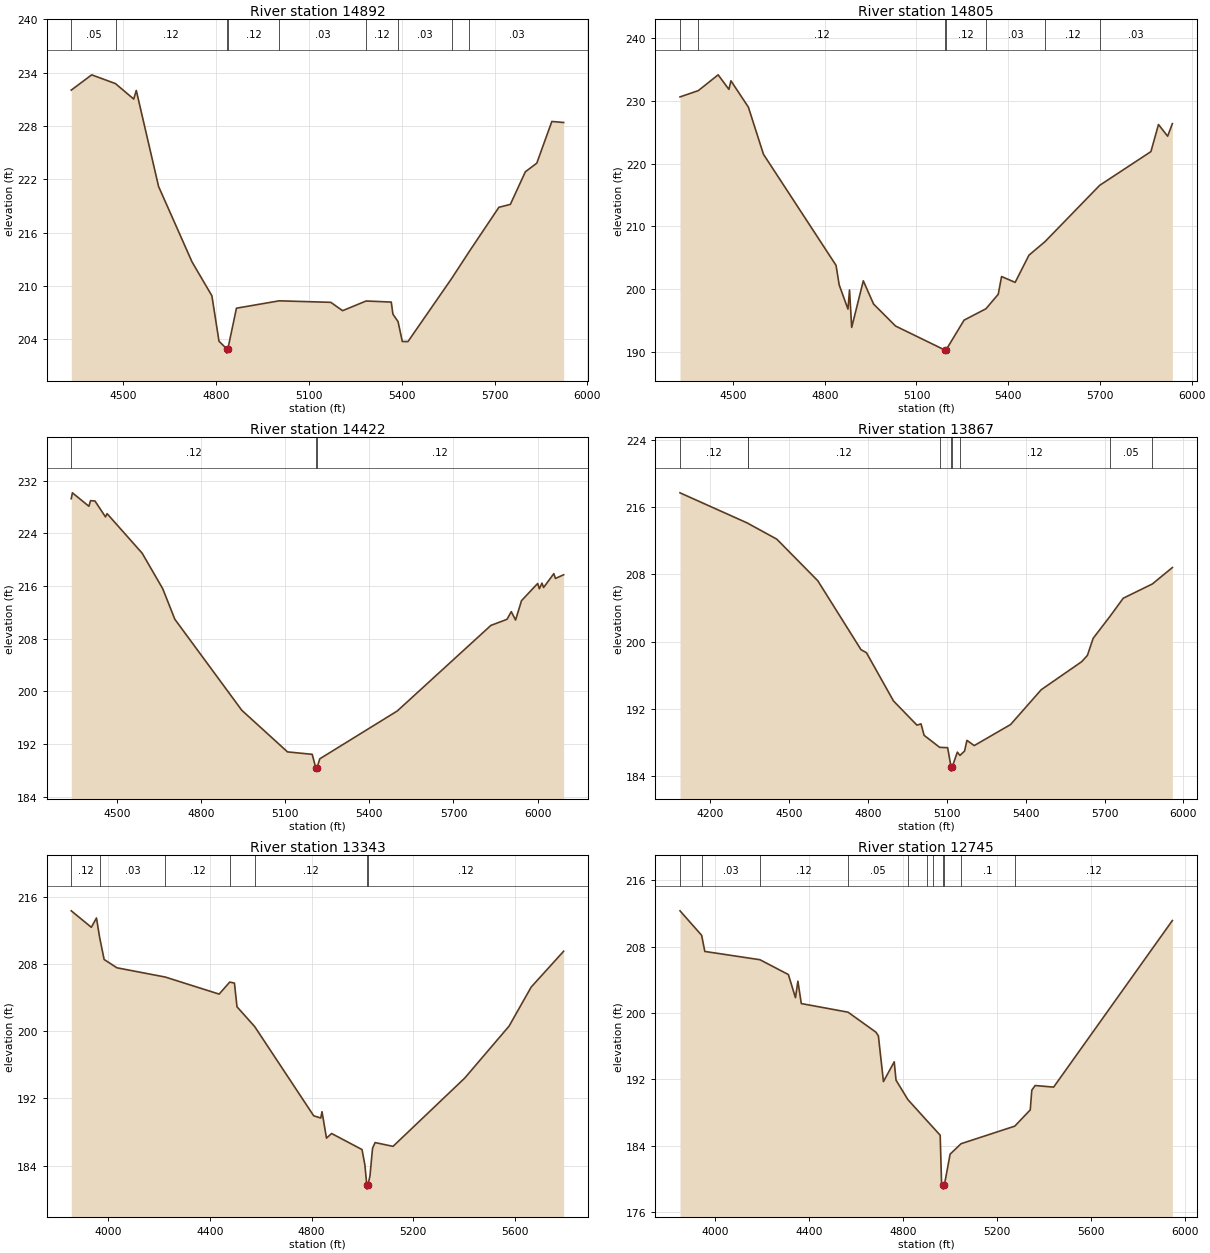
Type RM Length L Ch R = 1,14892,87,87,87
BEGIN DESCRIPTION:
LGII3092
END DESCRIPTION:
XS GIS Cut Line= 4
      2561628.10     13564487.26      2561345.85     13564909.41
      2561263.91     13565364.73      2561046.90     13565946.31
#Sta/Elev= 30
  4331.8  232.04  4397.8  233.76  4474.7  232.77  4533.6  231.03  4541.9  232.00
  4614.0  221.18  4722.1  212.69  4786.2  208.88  4809.2  203.76  4833.8  202.92
  4834.0  202.42  4838.0  202.92  4865.6  207.48  5003.9  208.31  5170.4  208.14
  5208.7  207.20  5284.6  208.29  5365.9  208.17  5371.3  206.81  5387.9  205.97
  5401.6  203.73  5419.9  203.72  5560.8  210.81  5618.3  213.88  5713.7  218.84
  5750.8  219.17  5799.3  222.84  5836.2  223.81  5884.9  228.51  5923.0  228.39
#Mann=9,-1,0
  4331.8    0.05       0  4474.7    0.12       0  4833.8    0.05       0
  4838.0    0.12       0  5003.9    0.03       0  5284.6    0.12       0
  5387.9    0.03       0  5560.8    0.12       0  5618.3    0.03       0
Bank Sta=4833.8,4838
Exp/Cntr=0.3,0.1

Type RM Length L Ch R = 1,14805,383,383,383
BEGIN DESCRIPTION:
Mapping XS caef2df0
END DESCRIPTION:
XS GIS Cut Line= 4
      2561593.37     13564468.05      2561285.23     13564832.60
      2561135.50     13565555.26      2560994.44     13565924.17
#Sta/Elev= 30
  4326.6  230.63  4386.4  231.63  4451.4  234.15  4486.5  231.83  4493.1  233.20
  4550.2  229.00  4599.6  221.48  4837.0  203.77  4847.2  200.66  4875.9  196.80
  4881.0  199.84  4888.1  193.88  4926.1  201.31  4959.6  197.61  5031.5  194.10
  5192.4  190.28  5192.6  189.78  5196.6  190.28  5255.7  195.04  5327.1  196.85
  5367.4  199.16  5378.3  201.99  5422.7  201.06  5467.8  205.39  5520.7  207.57
  5699.1  216.53  5866.8  221.91  5891.5  226.23  5921.5  224.36  5936.9  226.37
#Mann=7,-1,0
  4326.6    0.05       0  4386.4    0.12       0  5192.4    0.05       0
  5196.6    0.12       0  5327.1    0.03       0  5520.7    0.12       0
  5699.1    0.03       0
Bank Sta=5192.4,5196.6
Exp/Cntr=0.3,0.1

Type RM Length L Ch R = 1,14422,555,555,555
BEGIN DESCRIPTION:
LGII3093
END DESCRIPTION:
XS GIS Cut Line= 3
      2561524.34     13564418.54      2560994.81     13564722.37
      2560381.40     13565689.79
#Sta/Elev= 30
  4337.0  229.26  4341.0  230.15  4399.9  228.11  4405.7  228.96  4421.5  228.91
  4458.9  226.50  4464.7  226.99  4589.9  220.98  4663.1  215.60  4706.3  210.96
  4945.1  197.14  5108.2  190.82  5196.3  190.45  5209.0  188.40  5209.3  187.90
  5213.2  188.40  5223.4  189.77  5499.6  197.03  5833.5  210.02  5891.1  210.95
  5906.3  212.11  5921.6  210.84  5942.8  213.78  6000.4  216.39  6006.3  215.59
  6015.6  216.44  6021.6  215.78  6058.0  217.88  6063.9  217.15  6093.0  217.71
#Mann=3,-1,0
  4337.0    0.12       0  5209.0    0.05       0  5213.2    0.12       0
Bank Sta=5209,5213.2
Exp/Cntr=0.3,0.1

Type RM Length L Ch R = 1,13867,524,524,524
BEGIN DESCRIPTION:
LGII3091
END DESCRIPTION:
XS GIS Cut Line= 4
      2561480.88     13564097.38      2560690.99     13564305.70
      2560196.20     13564600.84      2560006.01     13565041.74
#Sta/Elev= 30
  4084.5  217.69  4343.5  214.06  4344.5  214.03  4452.7  212.18  4608.7  207.23
  4773.1  199.03  4793.8  198.67  4896.7  192.93  4986.0  190.05  5001.5  190.20
  5013.2  188.84  5072.4  187.41  5102.7  187.37  5115.8  185.08  5116.1  184.58
  5120.1  185.08  5139.7  186.84  5149.5  186.45  5167.0  186.96  5176.2  188.24
  5203.9  187.62  5342.1  190.12  5458.9  194.27  5612.7  197.60  5634.5  198.35
  5656.3  200.38  5719.6  202.96  5770.8  205.15  5881.7  206.85  5957.7  208.80
#Mann=9,-1,0
  4084.5    0.12       0  4343.5    0.05       0  4344.5    0.12       0
  5072.4    0.05       0  5115.8    0.05       0  5120.1    0.05       0
  5149.5    0.12       0  5719.6    0.05       0  5881.7    0.12       0
Bank Sta=5115.8,5120.1
Exp/Cntr=0.3,0.1

Type RM Length L Ch R = 1,13343,598,598,598
BEGIN DESCRIPTION:
LGII3090
END DESCRIPTION:
XS GIS Cut Line= 3
      2561463.57     13564001.89      2560595.50     13563906.40
      2559538.27     13564036.39
#Sta/Elev= 30
  3853.7  214.31  3932.7  212.35  3952.9  213.46  3965.0  211.20  3983.0  208.52
  4033.4  207.53  4223.6  206.43  4435.8  204.40  4477.5  205.83  4496.1  205.71
  4506.2  202.89  4576.2  200.52  4808.1  189.92  4835.9  189.65  4840.9  190.40
  4858.5  187.26  4878.6  187.81  4998.4  185.90  5009.6  184.09  5017.2  181.69
  5017.6  181.19  5022.1  181.69  5029.8  182.80  5039.8  186.05  5049.9  186.73
  5120.5  186.28  5402.6  194.40  5577.4  200.59  5664.5  205.24  5792.2  209.50
#Mann=7,-1,0
  3853.7    0.12       0  3965.0    0.03       0  4223.6    0.12       0
  4477.5    0.05       0  4576.2    0.12       0  5017.2    0.05       0
  5022.1    0.12       0
Bank Sta=5017.2,5022.1
Exp/Cntr=0.3,0.1

Type RM Length L Ch R = 1,12745,435,435,435
BEGIN DESCRIPTION:
LGII3089
END DESCRIPTION:
XS GIS Cut Line= 4
      2561463.59     13563932.45      2560526.06     13563576.54
      2560135.43     13563324.80      2559667.73     13562909.06
#Sta/Elev= 30
  3851.4  212.34  3943.3  209.39  3956.9  207.44  4191.3  206.44  4312.2  204.65
  4342.3  201.86  4352.6  203.85  4367.1  201.15  4565.9  200.11  4684.2  197.70
  4694.9  197.25  4716.3  191.74  4762.2  194.12  4769.8  191.91  4820.0  189.57
  4900.2  187.05  4925.4  186.27  4957.6  185.26  4963.5  179.36  4970.2  179.26
  4970.6  178.76  4975.4  179.26  4999.8  182.98  5046.3  184.24  5274.7  186.36
  5340.4  188.32  5347.1  190.70  5361.3  191.26  5439.9  191.07  5944.7  211.17
#Mann=11,-1,0
  3851.4    0.12       0  3943.3    0.03       0  4191.3    0.12       0
  4565.9    0.05       0  4820.0    0.12       0  4900.2    0.05       0
  4925.4    0.12       0  4970.2    0.05       0  4975.4    0.12       0
  5046.3     0.1       0  5274.7    0.12       0
Bank Sta=4970.2,4975.4
Exp/Cntr=0.3,0.1

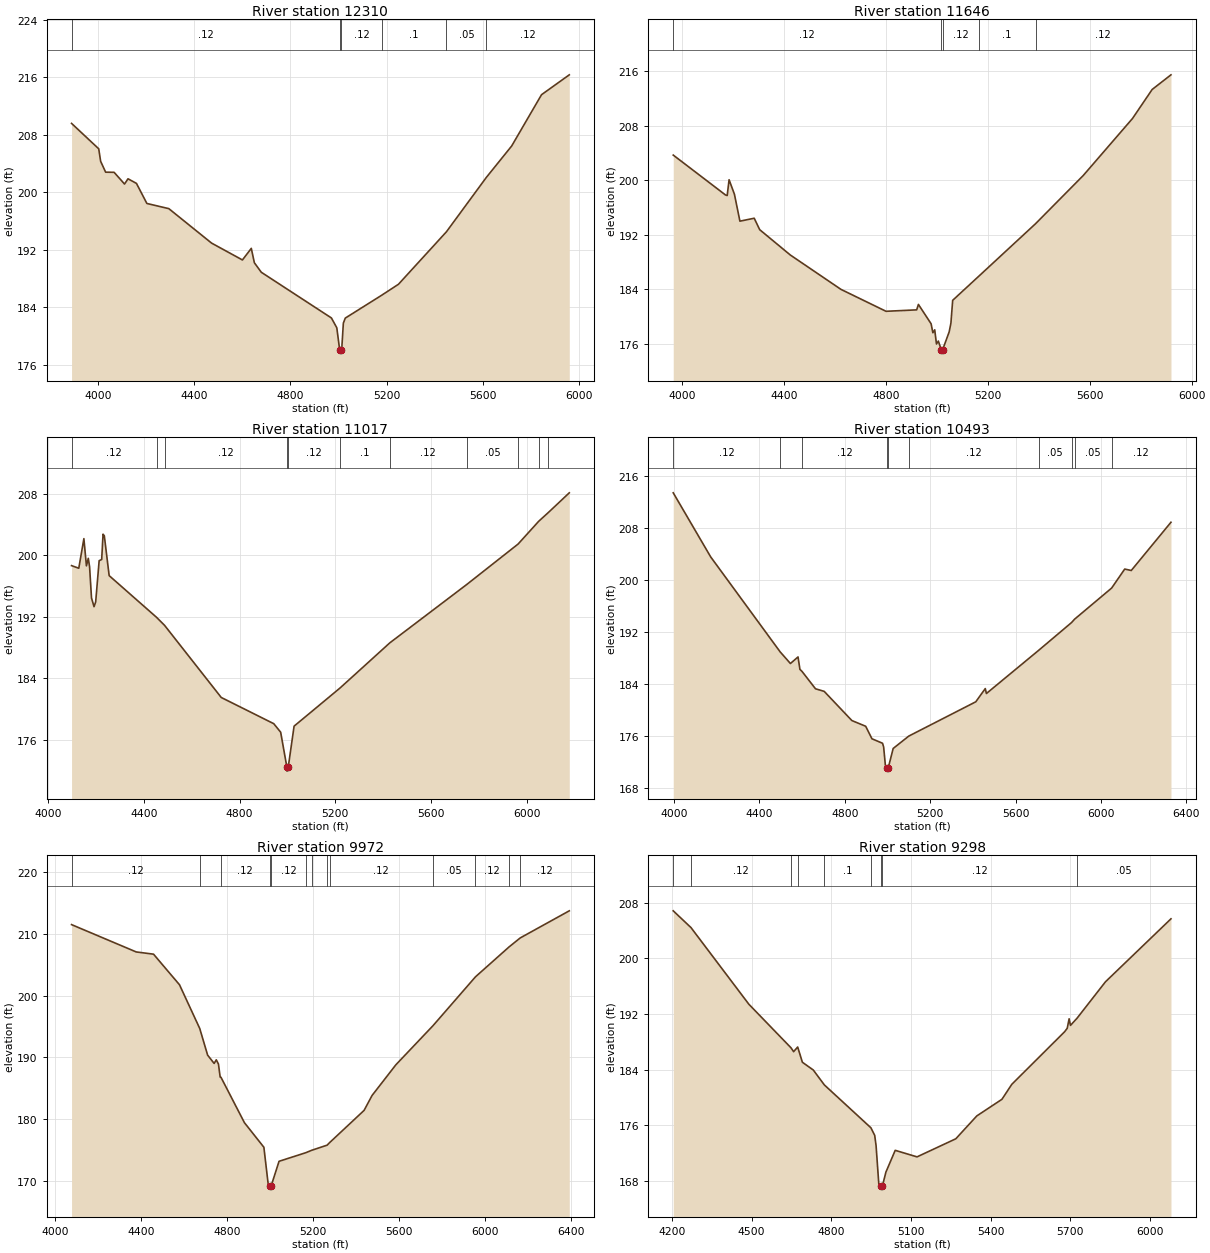
Type RM Length L Ch R = 1,12310,664,664,664
BEGIN DESCRIPTION:
LGII3088
END DESCRIPTION:
XS GIS Cut Line= 3
      2561480.93     13563828.28      2560309.05     13562899.45
      2559753.45     13562751.87
#Sta/Elev= 30
  3890.0  209.58  4003.0  206.05  4011.0  204.31  4031.8  202.80  4067.1  202.78
  4110.4  201.15  4124.8  201.88  4160.0  201.24  4203.3  198.45  4294.6  197.73
  4472.5  192.94  4600.7  190.60  4637.6  192.21  4650.4  190.21  4679.2  188.89
  4970.8  182.54  4993.3  181.17  5005.0  178.15  5005.4  177.65  5010.3  178.15
  5014.1  178.39  5020.5  181.82  5028.6  182.52  5181.1  185.72  5249.7  187.22
  5449.1  194.51  5614.9  202.06  5720.6  206.44  5844.8  213.57  5960.2  216.33
#Mann=6,-1,0
  3890.0    0.12       0  5005.0    0.05       0  5010.3    0.12       0
  5181.1     0.1       0  5449.1    0.05       0  5614.9    0.12       0
Bank Sta=5005,5010.3
Exp/Cntr=0.3,0.1

Type RM Length L Ch R = 1,11646,629,629,629
BEGIN DESCRIPTION:
LGII3087
END DESCRIPTION:
XS GIS Cut Line= 3
      2561802.13     13563507.12      2560864.60     13562500.15
      2560404.56     13562152.95
#Sta/Elev= 30
  3966.7  203.73  4171.5  197.88  4178.3  197.79  4185.7  200.11  4206.7  197.98
  4228.2  194.03  4284.3  194.46  4305.8  192.78  4426.0  189.06  4624.4  184.02
  4801.3  180.80  4921.5  181.01  4928.3  181.81  4978.1  178.97  4985.0  177.65
  4992.3  178.08  4999.1  176.00  5006.5  176.43  5017.9  175.16  5018.4  174.66
  5023.3  175.16  5049.0  177.78  5055.8  179.08  5062.7  182.41  5164.6  185.93
  5387.6  193.65  5574.5  200.72  5768.0  209.10  5845.1  213.36  5918.9  215.51
#Mann=5,-1,0
  3966.7    0.12       0  5017.9    0.05       0  5023.3    0.12       0
  5164.6     0.1       0  5387.6    0.12       0
Bank Sta=5017.9,5023.3
Exp/Cntr=0.3,0.1

Type RM Length L Ch R = 1,11017,524,524,524
BEGIN DESCRIPTION:
LGII3086
END DESCRIPTION:
XS GIS Cut Line= 4
      2561984.39     13563333.47      2561723.98     13562604.32
      2561472.24     13562291.82      2560691.00     13561840.43
#Sta/Elev= 30
  4098.7  198.66  4128.9  198.32  4150.2  202.17  4160.8  198.63  4168.6  199.61
  4174.0  198.50  4182.0  194.45  4192.6  193.32  4199.4  193.93  4213.9  199.30
  4224.5  199.46  4230.2  202.75  4235.5  202.54  4255.7  197.36  4454.1  191.92
  4486.8  190.90  4723.6  181.51  4942.9  178.10  4971.7  176.99  4997.7  172.43
  4998.1  171.93  5003.2  172.43  5027.7  177.78  5219.4  182.74  5427.5  188.62
  5748.6  196.21  5962.9  201.47  6048.6  204.42  6089.5  205.58  6176.5  208.13
#Mann=11,-1,0
  4098.7    0.12       0  4454.1    0.05       0  4486.8    0.12       0
  4997.7    0.05       0  5003.2    0.12       0  5219.4     0.1       0
  5427.5    0.12       0  5748.6    0.05       0  5962.9    0.12       0
  6048.6    0.05       0  6089.5    0.12       0
Bank Sta=4997.7,5003.2
Exp/Cntr=0.3,0.1

Type RM Length L Ch R = 1,10493,521,521,521
BEGIN DESCRIPTION:
LGII3085
END DESCRIPTION:
XS GIS Cut Line= 3
      2562956.65     13562343.91      2561524.32     13562040.08
      2560709.21     13561745.25
#Sta/Elev= 30
  3996.9  213.40  4172.4  203.55  4497.6  188.97  4545.7  187.18  4581.3  188.19
  4590.2  186.28  4600.2  185.96  4663.1  183.30  4703.9  182.90  4833.4  178.42
  4898.2  177.54  4927.5  175.62  4977.2  174.93  4982.3  174.35  4990.2  171.60
  4997.0  171.15  4997.5  170.65  5003.8  171.15  5026.9  174.13  5099.9  176.03
  5413.8  181.30  5458.2  183.33  5463.5  182.57  5708.1  189.20  5862.2  193.47
  5876.5  193.99  6050.0  198.77  6111.3  201.69  6141.9  201.47  6327.9  208.88
#Mann=10,-1,0
  3996.9    0.12       0  4497.6   0.013       0  4600.2    0.12       0
  4997.0    0.03       0  5003.8    0.12       0  5099.9    0.12       0
  5708.1    0.05       0  5862.2    0.12       0  5876.5    0.05       0
  6050.0    0.12       0
Bank Sta=4997,5003.8
Exp/Cntr=0.3,0.1

Type RM Length L Ch R = 1,9972,674,674,674
BEGIN DESCRIPTION:
LGII3084
END DESCRIPTION:
XS GIS Cut Line= 4
      2562973.94     13561753.62      2560968.77     13561510.57
      2560960.09     13561493.20      2560690.97     13561423.75
#Sta/Elev= 30
  4076.7  211.48  4377.8  207.06  4458.4  206.70  4579.3  201.75  4673.5  194.68
  4710.2  190.37  4740.5  189.03  4750.5  189.61  4760.6  188.93  4768.6  186.82
  4772.2  186.80  4881.5  179.45  4972.1  175.47  4992.3  169.46  4998.9  169.20
  4999.4  168.70  5005.8  169.20  5042.7  173.20  5167.2  174.59  5196.1  175.00
  5266.5  175.81  5277.7  176.21  5438.5  181.43  5475.8  183.85  5586.6  188.81
  5759.6  195.14  5957.0  203.03  6113.8  207.88  6165.7  209.33  6393.9  213.71
#Mann=13,-1,0
  4076.7    0.12       0  4673.5   0.013       0  4772.2    0.12       0
  4998.9    0.05       0  5005.8    0.12       0  5167.2   0.013       0
  5196.1    0.12       0  5266.5   0.013       0  5277.7    0.12       0
  5759.6    0.05       0  5957.0    0.12       0  6113.8    0.05       0
  6165.7    0.12       0
Bank Sta=4998.9,5005.8
Exp/Cntr=0.3,0.1

Type RM Length L Ch R = 1,9298,565,565,565
BEGIN DESCRIPTION:
LGII3083
END DESCRIPTION:
XS GIS Cut Line= 3
      2562947.96     13561345.64      2561671.89     13561041.82
      2561125.02     13560911.61
#Sta/Elev= 30
  4205.3  206.85  4272.1  204.44  4489.9  193.42  4648.6  187.15  4658.5  186.59
  4673.8  187.26  4691.5  185.07  4732.6  183.95  4774.2  181.81  4949.6  175.64
  4963.8  174.55  4969.0  173.05  4979.3  167.52  4986.1  167.32  4986.6  166.82
  4993.1  167.32  5005.9  169.26  5041.0  172.40  5123.2  171.46  5269.1  174.06
  5348.2  177.35  5442.8  179.74  5479.8  181.89  5678.3  189.44  5688.6  189.95
  5695.7  191.32  5700.8  190.37  5725.5  191.40  5832.5  196.64  6079.2  205.70
#Mann=9,-1,0
  4205.3    0.05       0  4272.1    0.12       0  4648.6   0.013       0
  4673.8    0.12       0  4774.2     0.1       0  4949.6    0.12       0
  4986.1    0.05       0  4993.1    0.12       0  5725.5    0.05       0
Bank Sta=4986.1,4993.1
Exp/Cntr=0.3,0.1

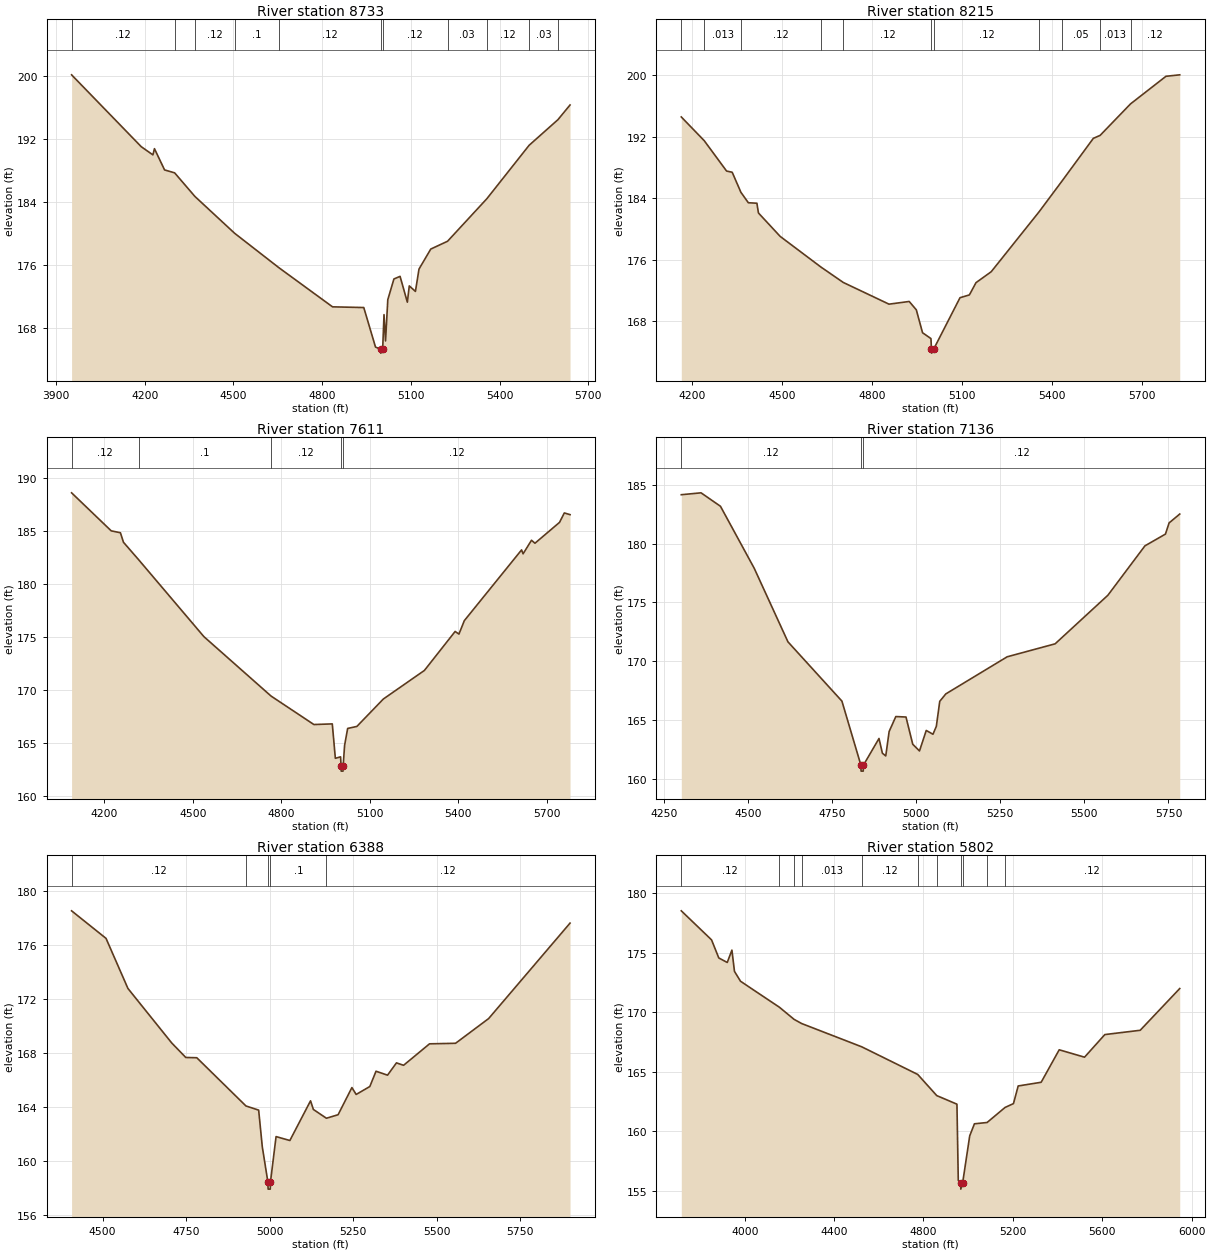
Type RM Length L Ch R = 1,8733,518,518,518
BEGIN DESCRIPTION:
LGII3082
END DESCRIPTION:
XS GIS Cut Line= 2
      2563034.72     13560963.68      2561411.51     13560512.31
#Sta/Elev= 30
  3953.1  200.15  4188.6  191.02  4228.0  189.98  4233.2  190.77  4267.4  188.07
  4301.4  187.70  4370.0  184.70  4504.0  180.03  4653.5  175.66  4835.1  170.68
  4940.7  170.59  4980.4  165.57  4997.6  165.30  4998.1  164.80  5004.6  165.30
  5009.1  169.69  5014.3  166.35  5021.9  171.59  5042.6  174.22  5063.4  174.55
  5088.0  171.27  5094.5  173.34  5115.3  172.64  5127.4  175.48  5167.2  178.02
  5223.9  179.01  5356.9  184.42  5499.6  191.20  5596.9  194.45  5637.9  196.32
#Mann=11,-1,0
  3953.1    0.12       0  4301.4   0.013       0  4370.0    0.12       0
  4504.0     0.1       0  4653.5    0.12       0  4997.6    0.05       0
  5004.6    0.12       0  5223.9    0.03       0  5356.9    0.12       0
  5499.6    0.03       0  5596.9    0.12       0
Bank Sta=4997.6,5004.6
Exp/Cntr=0.3,0.1

Type RM Length L Ch R = 1,8215,604,604,604
BEGIN DESCRIPTION:
LGII3081
END DESCRIPTION:
XS GIS Cut Line= 2
      2563078.10     13560520.97      2561480.94     13560060.92
#Sta/Elev= 30
  4164.2  194.56  4240.8  191.47  4315.3  187.52  4333.9  187.37  4363.0  184.76
  4387.8  183.40  4416.3  183.34  4421.5  182.07  4494.0  179.02  4630.1  175.03
  4704.4  173.03  4856.8  170.21  4924.2  170.56  4947.9  169.47  4968.7  166.49
  4996.7  165.73  4998.4  164.34  4998.9  163.84  5005.5  164.34  5093.6  171.05
  5124.8  171.41  5147.0  173.01  5197.7  174.43  5357.6  182.24  5434.2  186.25
  5538.2  191.78  5560.7  192.16  5662.2  196.26  5780.4  199.85  5826.3  200.04
#Mann=11,-1,0
  4164.2    0.12       0  4240.8   0.013       0  4363.0    0.12       0
  4630.1     0.1       0  4704.4    0.12       0  4998.4    0.05       0
  5005.5    0.12       0  5357.6     0.1       0  5434.2    0.05       0
  5560.7   0.013       0  5662.2    0.12       0
Bank Sta=4998.4,5005.5
Exp/Cntr=0.3,0.1

Type RM Length L Ch R = 1,7611,475,475,475
BEGIN DESCRIPTION:
LGII3080
END DESCRIPTION:
XS GIS Cut Line= 2
      2563434.03     13560043.55      2561810.76     13559574.80
#Sta/Elev= 30
  4089.1  188.61  4223.4  185.02  4254.6  184.84  4265.0  183.94  4316.8  182.28
  4537.6  175.03  4765.2  169.42  4910.4  166.73  4972.8  166.79  4983.2  163.54
  5000.9  163.68  5002.5  162.83  5003.0  162.33  5009.2  162.33  5009.7  162.83
  5014.5  164.76  5024.9  166.36  5056.1  166.55  5145.9  169.14  5285.1  171.84
  5389.2  175.52  5402.1  175.27  5420.4  176.54  5614.4  183.22  5619.6  182.85
  5648.0  184.13  5659.8  183.85  5743.1  185.82  5759.3  186.71  5778.7  186.55
#Mann=5,-1,0
  4089.1    0.12       0  4316.8     0.1       0  4765.2    0.12       0
  5002.5    0.05       0  5009.7    0.12       0
Bank Sta=5002.5,5009.7
Exp/Cntr=0.3,0.1

Type RM Length L Ch R = 1,7136,748,748,748
BEGIN DESCRIPTION:
LGII3079
END DESCRIPTION:
XS GIS Cut Line= 3
      2563321.16     13559383.83      2562305.57     13559314.38
      2561854.20     13559418.55
#Sta/Elev= 30
  4302.3  184.14  4361.0  184.30  4418.7  183.16  4519.0  177.90  4619.2  171.66
  4779.6  166.63  4836.1  161.19  4836.6  160.69  4842.9  160.69  4843.4  161.19
  4889.8  163.46  4899.9  162.21  4909.9  161.98  4919.9  164.05  4939.8  165.32
  4970.0  165.28  4990.1  162.97  5010.1  162.40  5030.2  164.14  5050.2  163.82
  5060.2  164.49  5070.3  166.61  5088.3  167.24  5270.7  170.39  5413.2  171.49
  5569.9  175.61  5680.0  179.80  5741.0  180.80  5751.9  181.75  5783.5  182.50
#Mann=3,-1,0
  4302.3    0.12       0  4836.1    0.05       0  4843.4    0.12       0
Bank Sta=4836.1,4843.4
Exp/Cntr=0.3,0.1

Type RM Length L Ch R = 1,6388,586,586,586
BEGIN DESCRIPTION:
LGII3078
END DESCRIPTION:
XS GIS Cut Line= 4
      2563217.06     13558941.14      2562913.21     13558776.19
      2562331.62     13558923.76      2561940.98     13559305.71
#Sta/Elev= 30
  4407.1  178.55  4510.2  176.51  4575.8  172.80  4707.0  168.76  4749.0  167.69
  4781.9  167.67  4929.0  164.10  4967.1  163.79  4978.0  161.07  4994.9  158.44
  4995.4  157.94  5001.8  157.94  5002.3  158.44  5019.2  161.83  5060.5  161.54
  5122.4  164.48  5130.9  163.84  5169.9  163.19  5204.9  163.45  5246.2  165.46
  5259.0  164.95  5299.9  165.54  5318.4  166.67  5352.9  166.38  5379.6  167.29
  5400.9  167.11  5478.6  168.70  5556.5  168.74  5655.5  170.57  5899.2  177.64
#Mann=5,-1,0
  4407.1    0.12       0  4929.0     0.1       0  4994.9    0.05       0
  5002.3     0.1       0  5169.9    0.12       0
Bank Sta=4994.9,5002.3
Exp/Cntr=0.3,0.1

Type RM Length L Ch R = 1,5802,607,607,607
BEGIN DESCRIPTION:
LGII3077
END DESCRIPTION:
XS GIS Cut Line= 4
      2563781.26     13557960.22      2562644.12     13558316.12
      2562314.25     13558533.13      2562036.48     13559114.72
#Sta/Elev= 30
  3716.0  178.52  3851.4  176.08  3883.8  174.56  3921.7  174.18  3942.6  175.22
  3954.0  173.43  3981.2  172.60  4154.9  170.42  4220.7  169.40  4254.3  169.05
  4523.7  167.09  4774.1  164.77  4859.4  162.99  4949.7  162.27  4955.7  155.86
  4966.5  155.63  4967.0  155.13  4975.0  155.63  5006.9  159.61  5028.0  160.62
  5084.7  160.73  5164.7  161.99  5202.7  162.32  5223.8  163.80  5326.6  164.11
  5407.4  166.84  5520.8  166.22  5611.6  168.12  5769.9  168.48  5946.9  171.99
#Mann=11,-1,0
  3716.0    0.12       0  4154.9     0.1       0  4220.7    0.12       0
  4254.3   0.013       0  4523.7    0.12       0  4774.1     0.1       0
  4859.4    0.12       0  4966.5    0.05       0  4975.0    0.12       0
  5084.7     0.1       0  5164.7    0.12       0
Bank Sta=4966.5,4975
Exp/Cntr=0.3,0.1