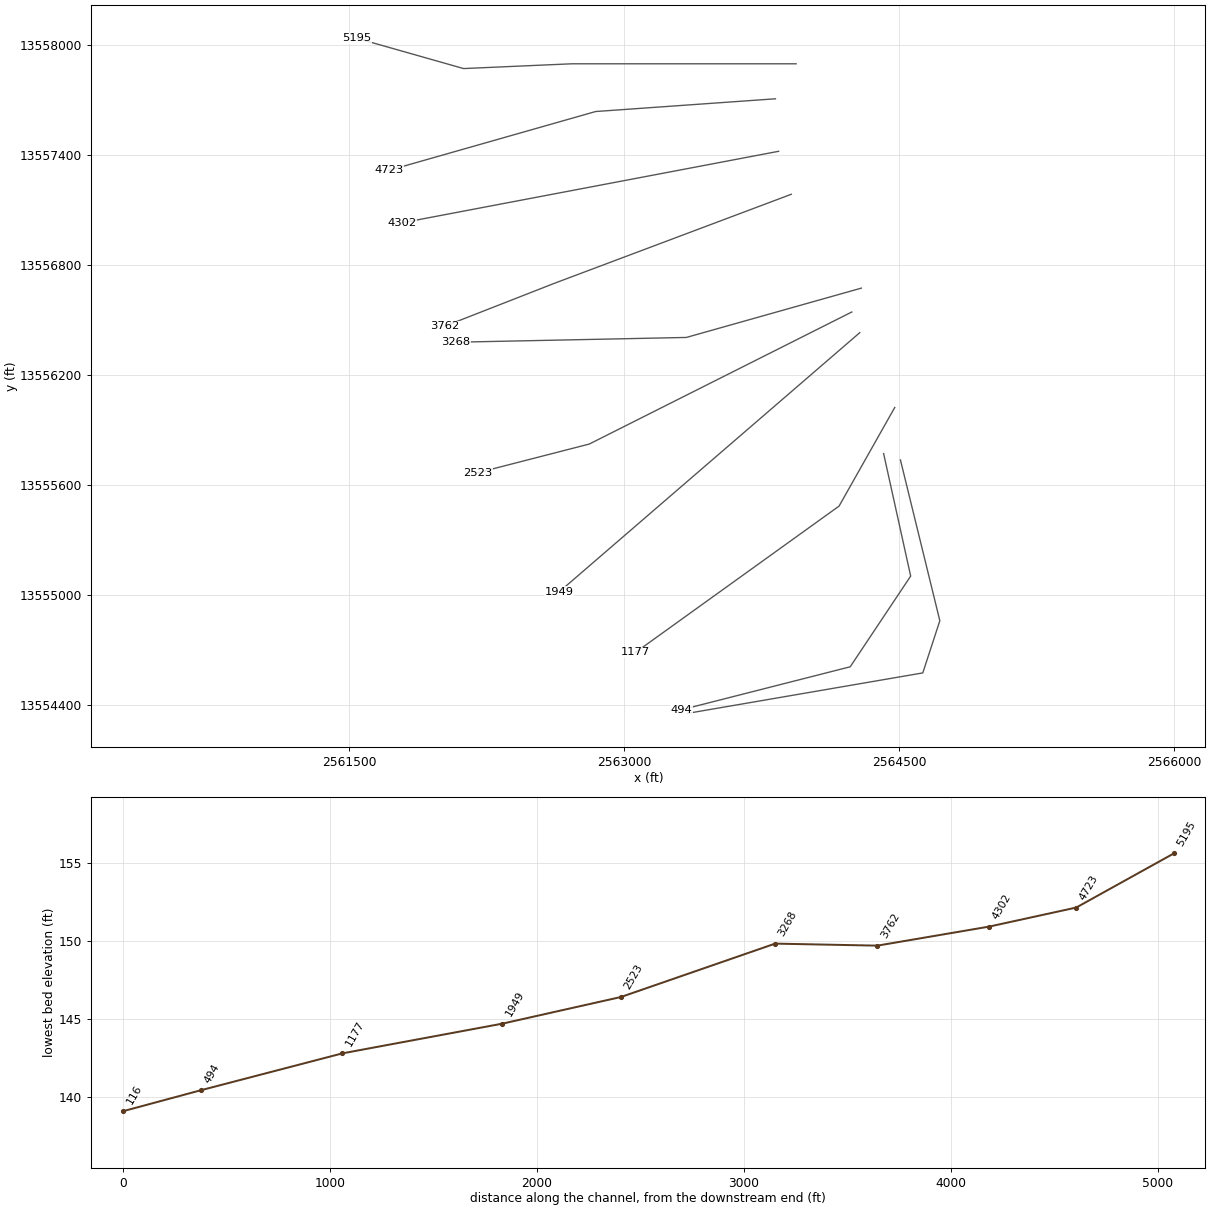
HEC-RAS study TRIB 6 TO PRICE CREEK.prj: TRIB 6 TO PRICE CREEK Base Level Engineering

--- TRIB 6 TO PRICE CREEK.g01 (geometry) --- (continued)

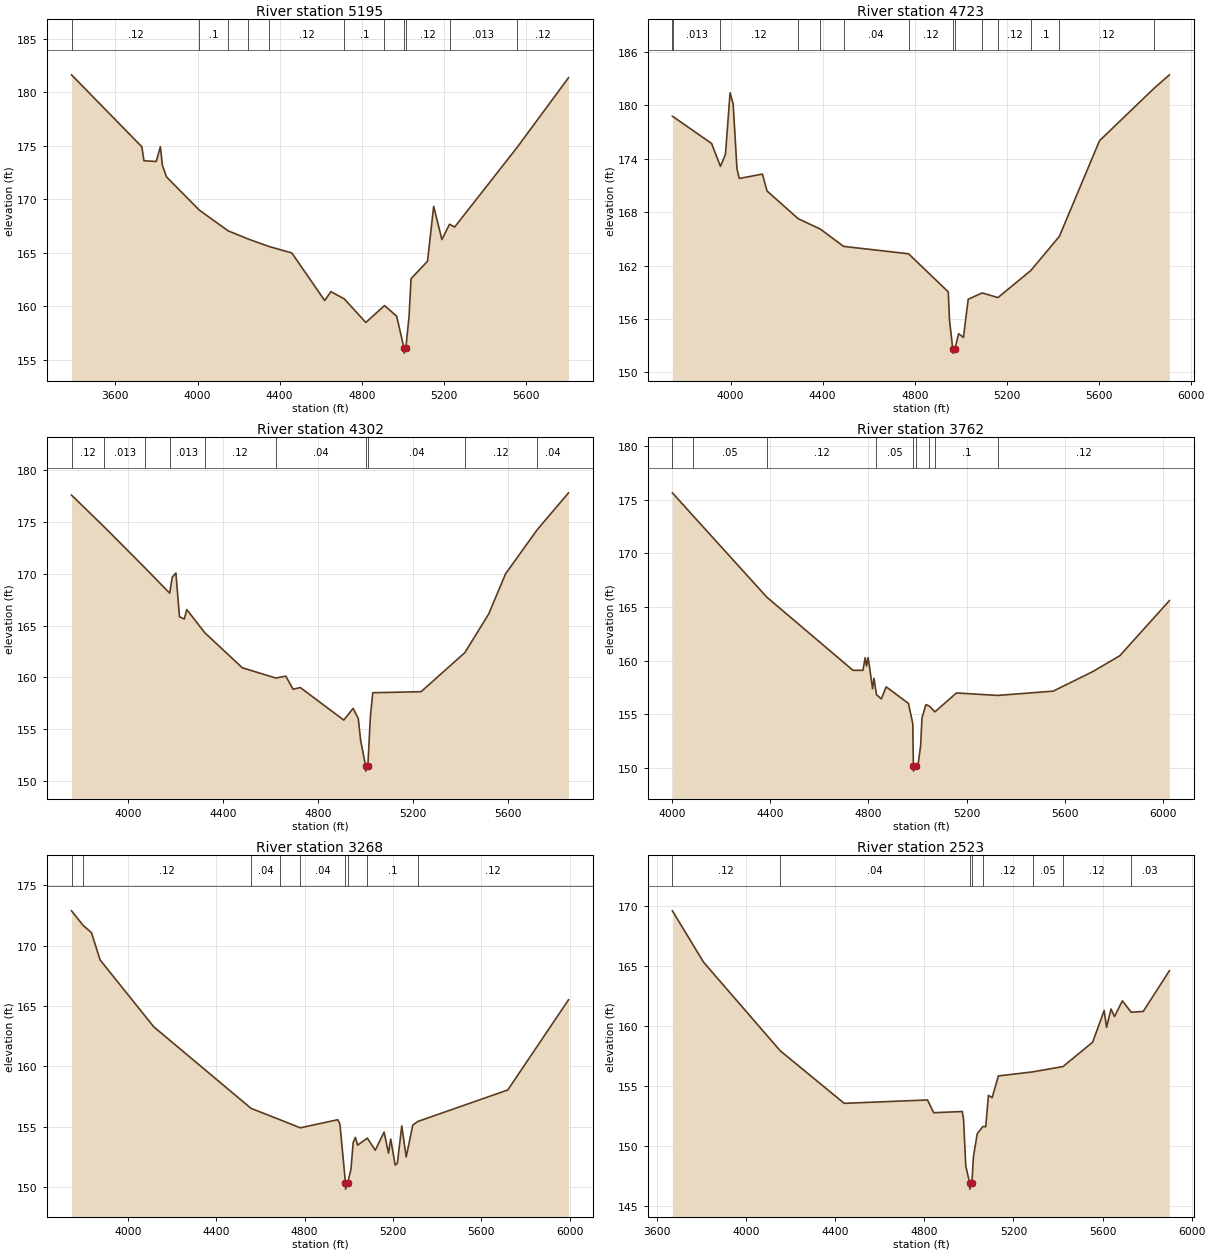
Type RM Length L Ch R = 1,5195,472,472,472
BEGIN DESCRIPTION:
LGII3076
END DESCRIPTION:
XS GIS Cut Line= 4
      2563937.48     13557899.45      2562713.56     13557899.45
      2562123.28     13557873.41      2561541.69     13558038.34
#Sta/Elev= 30
  3386.7  181.61  3729.2  174.89  3739.2  173.59  3799.2  173.52  3819.2  174.90
  3829.2  173.16  3849.2  172.08  4009.0  168.98  4148.8  167.05  4247.2  166.28
  4349.1  165.58  4459.2  164.98  4619.2  160.54  4649.2  161.37  4714.8  160.69
  4819.4  158.49  4910.2  160.07  4969.5  159.08  5004.9  156.13  5005.4  155.63
  5014.2  156.13  5029.6  159.02  5039.6  162.58  5119.7  164.21  5149.7  169.34
  5189.7  166.23  5226.8  167.66  5251.7  167.40  5555.6  174.83  5806.0  181.34
#Mann=11,-1,0
  3386.7    0.12       0  4009.0     0.1       0  4148.8   0.013       0
  4247.2    0.04       0  4349.1    0.12       0  4714.8     0.1       0
  4910.2    0.12       0  5004.9    0.05       0  5014.2    0.12       0
  5226.8   0.013       0  5555.6    0.12       0
Bank Sta=5004.9,5014.2
Exp/Cntr=0.3,0.1

Type RM Length L Ch R = 1,4723,421,421,421
BEGIN DESCRIPTION:
LGII3075
END DESCRIPTION:
XS GIS Cut Line= 3
      2563824.64     13557708.48      2562843.77     13557639.04
      2561715.31     13557317.86
#Sta/Elev= 30
  3747.9  178.76  3748.8  178.76  3918.0  175.71  3956.3  173.14  3978.1  174.50
  3998.2  181.40  4011.4  180.17  4028.2  172.84  4038.3  171.78  4138.5  172.27
  4158.6  170.37  4293.8  167.26  4390.0  166.09  4490.6  164.15  4772.5  163.32
  4945.0  159.04  4950.2  155.91  4964.3  152.66  4964.8  152.16  4973.8  152.66
  4989.9  154.34  5010.7  153.93  5031.5  158.21  5091.8  158.92  5160.7  158.40
  5303.2  161.44  5426.9  165.27  5601.3  176.02  5837.7  181.90  5904.5  183.42
#Mann=14,-1,0
  3747.9    0.12       0  3748.8   0.013       0  3956.3    0.12       0
  4293.8   0.013       0  4390.0    0.12       0  4490.6    0.04       0
  4772.5    0.12       0  4964.3    0.05       0  4973.8    0.12       0
  5091.8     0.1       0  5160.7    0.12       0  5303.2     0.1       0
  5426.9    0.12       0  5837.7    0.04       0
Bank Sta=4964.3,4973.8
Exp/Cntr=0.3,0.1

Type RM Length L Ch R = 1,4302,540,540,540
BEGIN DESCRIPTION:
LGII3074
END DESCRIPTION:
XS GIS Cut Line= 2
      2563842.06     13557422.03      2561784.71     13557031.39
#Sta/Elev= 30
  3761.6  177.59  3899.9  174.51  4071.1  170.57  4175.2  168.12  4186.1  169.67
  4201.4  170.07  4216.6  165.84  4237.0  165.63  4247.2  166.54  4323.6  164.29
  4481.3  160.92  4622.3  159.93  4664.5  160.11  4695.0  158.85  4725.6  159.01
  4908.8  155.87  4948.1  157.00  4969.9  156.02  4980.0  153.88  5000.7  151.44
  5001.2  150.94  5010.2  151.44  5020.8  156.19  5030.9  158.51  5234.5  158.61
  5418.9  162.38  5519.5  166.12  5590.4  169.99  5723.2  174.23  5855.7  177.81
#Mann=10,-1,0
  3761.6    0.12       0  3899.9   0.013       0  4071.1    0.12       0
  4175.2   0.013       0  4323.6    0.12       0  4622.3    0.04       0
  5000.7    0.04       0  5010.2    0.04       0  5418.9    0.12       0
  5723.2    0.04       0
Bank Sta=5000.7,5010.2
Exp/Cntr=0.3,0.1

Type RM Length L Ch R = 1,3762,494,494,494
BEGIN DESCRIPTION:
LGII3073
END DESCRIPTION:
XS GIS Cut Line= 3
      2563911.46     13557187.64      2562618.07     13556701.54
      2562019.59     13556467.35
#Sta/Elev= 30
  4001.3  175.64  4085.6  173.50  4386.1  165.92  4736.8  159.11  4777.4  159.11
  4786.6  160.29  4791.9  159.51  4798.7  160.29  4816.8  157.39  4822.2  158.37
  4832.6  156.84  4852.4  156.45  4872.0  157.57  4962.7  156.03  4980.4  154.15
  4982.8  150.22  4983.3  149.72  4992.4  150.22  5001.7  150.28  5012.4  152.10
  5017.8  154.68  5033.8  155.91  5047.9  155.78  5070.5  155.24  5158.3  157.00
  5326.3  156.77  5552.3  157.17  5715.2  159.01  5823.8  160.47  6025.7  165.60
#Mann=9,-1,0
  4001.3    0.12       0  4085.6    0.05       0  4386.1    0.12       0
  4832.6    0.05       0  4982.8    0.05       0  4992.4    0.05       0
  5047.9    0.04       0  5070.5     0.1       0  5326.3    0.12       0
Bank Sta=4982.8,4992.4
Exp/Cntr=0.3,0.1

Type RM Length L Ch R = 1,3268,745,745,745
BEGIN DESCRIPTION:
LGII3072
END DESCRIPTION:
XS GIS Cut Line= 3
      2564293.39     13556675.49      2563338.56     13556406.40
      2562079.95     13556380.36
#Sta/Elev= 30
  3744.4  172.87  3797.8  171.65  3834.7  171.07  3873.9  168.81  4116.7  163.28
  4557.6  156.53  4690.0  155.58  4780.4  154.92  4950.0  155.59  4960.0  155.24
  4985.2  150.35  4985.7  149.85  4994.9  150.35  5010.0  151.50  5020.0  153.70
  5030.0  154.13  5040.0  153.49  5084.1  154.07  5120.1  153.07  5160.1  154.57
  5180.1  152.83  5190.1  153.99  5210.1  151.84  5220.1  151.99  5240.1  155.08
  5260.1  152.51  5290.1  155.15  5313.0  155.45  5720.2  158.05  5995.3  165.51
#Mann=9,-1,0
  3744.4    0.05       0  3797.8    0.12       0  4557.6    0.04       0
  4690.0    0.05       0  4780.4    0.04       0  4985.2    0.04       0
  4994.9    0.04       0  5084.1     0.1       0  5313.0    0.12       0
Bank Sta=4985.2,4994.9
Exp/Cntr=0.3,0.1

Type RM Length L Ch R = 1,2523,574,574,574
BEGIN DESCRIPTION:
LGII3071
END DESCRIPTION:
XS GIS Cut Line= 3
      2564241.32     13556545.28      2562809.05     13555824.80
      2562201.39     13555668.55
#Sta/Elev= 30
  3669.4  169.59  3809.9  165.30  4153.1  157.95  4440.5  153.57  4814.3  153.85
  4842.3  152.79  4970.6  152.89  4976.2  152.23  4986.2  148.36  5003.6  146.93
  5004.1  146.43  5013.5  146.93  5020.8  149.17  5037.6  151.04  5062.7  151.64
  5075.7  151.62  5087.8  154.23  5104.5  154.04  5132.4  155.85  5287.3  156.19
  5422.6  156.63  5555.6  158.66  5607.3  161.30  5618.0  159.90  5638.2  161.42
  5653.5  160.79  5689.1  162.10  5728.6  161.15  5782.8  161.22  5900.1  164.61
#Mann=8,-1,0
  3669.4    0.12       0  4153.1    0.04       0  5003.6    0.04       0
  5013.5    0.04       0  5062.7    0.12       0  5287.3    0.05       0
  5422.6    0.12       0  5728.6    0.03       0
Bank Sta=5003.6,5013.5
Exp/Cntr=0.3,0.1

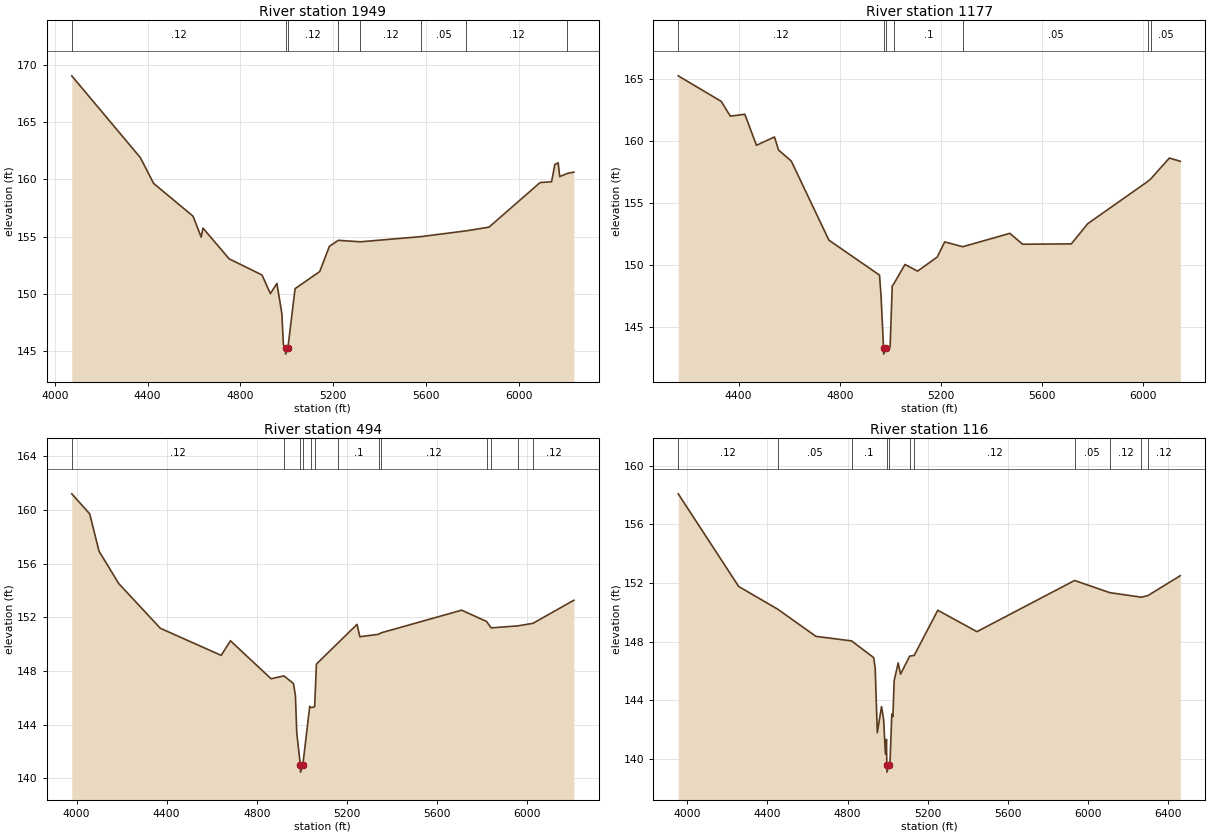
Type RM Length L Ch R = 1,1949,772,772,772
BEGIN DESCRIPTION:
LGII3070
END DESCRIPTION:
XS GIS Cut Line= 2
      2564284.73     13556432.43      2562645.53     13555018.73
#Sta/Elev= 30
  4073.4  169.05  4369.1  161.90  4426.1  159.65  4596.2  156.78  4631.3  154.95
  4639.0  155.74  4752.0  153.05  4893.5  151.64  4929.7  150.01  4957.8  150.90
  4979.1  148.28  4985.7  145.57  4994.9  145.22  4995.4  144.72  5005.0  145.22
  5036.1  150.44  5142.5  151.94  5184.2  154.15  5222.7  154.67  5317.6  154.54
  5578.0  154.99  5774.4  155.50  5872.1  155.82  6092.5  159.72  6141.9  159.79
  6156.2  161.30  6170.4  161.45  6177.0  160.24  6208.6  160.51  6238.0  160.63
#Mann=8,-1,0
  4073.4    0.12       0  4994.9    0.05       0  5005.0    0.12       0
  5222.7     0.1       0  5317.6    0.12       0  5578.0    0.05       0
  5774.4    0.12       0  6208.6    0.05       0
Bank Sta=4994.9,5005
Exp/Cntr=0.3,0.1

Type RM Length L Ch R = 1,1177,683,683,683
BEGIN DESCRIPTION:
LGII3069
END DESCRIPTION:
XS GIS Cut Line= 3
      2564475.69     13556024.42      2564171.89     13555486.26
      2563060.80     13554687.66
#Sta/Elev= 30
  4161.1  165.26  4331.2  163.20  4367.1  162.01  4424.6  162.16  4470.5  159.66
  4542.0  160.33  4557.9  159.28  4608.3  158.39  4757.2  152.01  4957.5  149.19
  4963.7  147.43  4973.3  143.32  4973.8  142.82  4983.5  143.32  4999.3  143.41
  5007.8  148.32  5015.2  148.53  5058.2  150.05  5107.8  149.51  5185.9  150.65
  5215.3  151.87  5286.8  151.48  5473.1  152.56  5523.4  151.68  5716.2  151.71
  5781.3  153.34  6019.7  156.76  6030.5  156.95  6104.1  158.63  6147.4  158.37
#Mann=7,-1,0
  4161.1    0.12       0  4973.3    0.05       0  4983.5    0.12       0
  5015.2     0.1       0  5286.8    0.05       0  6019.7    0.12       0
  6030.5    0.05       0
Bank Sta=4973.3,4983.5
Exp/Cntr=0.3,0.1

Type RM Length L Ch R = 1,494,378,378,378
BEGIN DESCRIPTION:
LGII3068
END DESCRIPTION:
XS GIS Cut Line= 4
      2564414.96     13555772.67      2564562.52     13555104.32
      2564232.66     13554609.52      2563312.55     13554375.16
#Sta/Elev= 30
  3978.7  161.20  4058.2  159.71  4099.6  156.93  4186.9  154.52  4371.9  151.18
  4642.0  149.16  4683.0  150.25  4863.3  147.42  4921.0  147.63  4962.8  147.06
  4971.5  146.15  4977.5  143.36  4993.6  140.96  4994.1  140.46  5004.0  140.96
  5034.9  145.36  5041.7  145.27  5056.8  145.33  5064.6  148.51  5162.4  150.12
  5244.9  151.47  5257.5  150.55  5340.3  150.73  5351.8  150.84  5709.4  152.53
  5819.6  151.69  5840.3  151.21  5958.8  151.36  6025.9  151.55  6207.3  153.27
#Mann=13,-1,0
  3978.7    0.12       0  4921.0     0.1       0  4993.6    0.05       0
  5004.0     0.1       0  5041.7    0.05       0  5056.8    0.12       0
  5162.4     0.1       0  5340.3    0.05       0  5351.8    0.12       0
  5819.6    0.05       0  5840.3    0.12       0  5958.8    0.05       0
  6025.9    0.12       0
Bank Sta=4993.6,5004
Exp/Cntr=0.3,0.1

Type RM Length L Ch R = 1,116,0,0,0
BEGIN DESCRIPTION:
4851
END DESCRIPTION:
XS GIS Cut Line= 4
      2564506.68     13555738.04      2564721.64     13554860.78
      2564628.69     13554576.12      2563344.79     13554355.36
#Sta/Elev= 30
  3954.8  158.09  4256.5  151.77  4451.5  150.22  4641.8  148.37  4819.7  148.06
  4930.1  146.92  4937.7  146.18  4948.2  141.80  4969.3  143.58  4979.8  142.69
  4988.6  140.34  4993.9  141.34  4995.6  139.61  4996.1  139.11  5006.0  139.61
  5011.4  139.68  5020.5  143.08  5025.8  142.89  5032.4  145.35  5052.4  146.56
  5064.0  145.79  5109.7  147.02  5132.2  147.07  5250.0  150.15  5445.3  148.69
  5932.7  152.18  6108.3  151.35  6266.1  151.04  6298.6  151.15  6460.2  152.51
#Mann=11,-1,0
  3954.8    0.12       0  4451.5    0.05       0  4819.7     0.1       0
  4995.6    0.05       0  5006.0     0.1       0  5109.7    0.05       0
  5132.2    0.12       0  5932.7    0.05       0  6108.3    0.12       0
  6266.1    0.05       0  6298.6    0.12       0
Bank Sta=4995.6,5006
Exp/Cntr=0.3,0.1

Chan Stop Cuts=-1