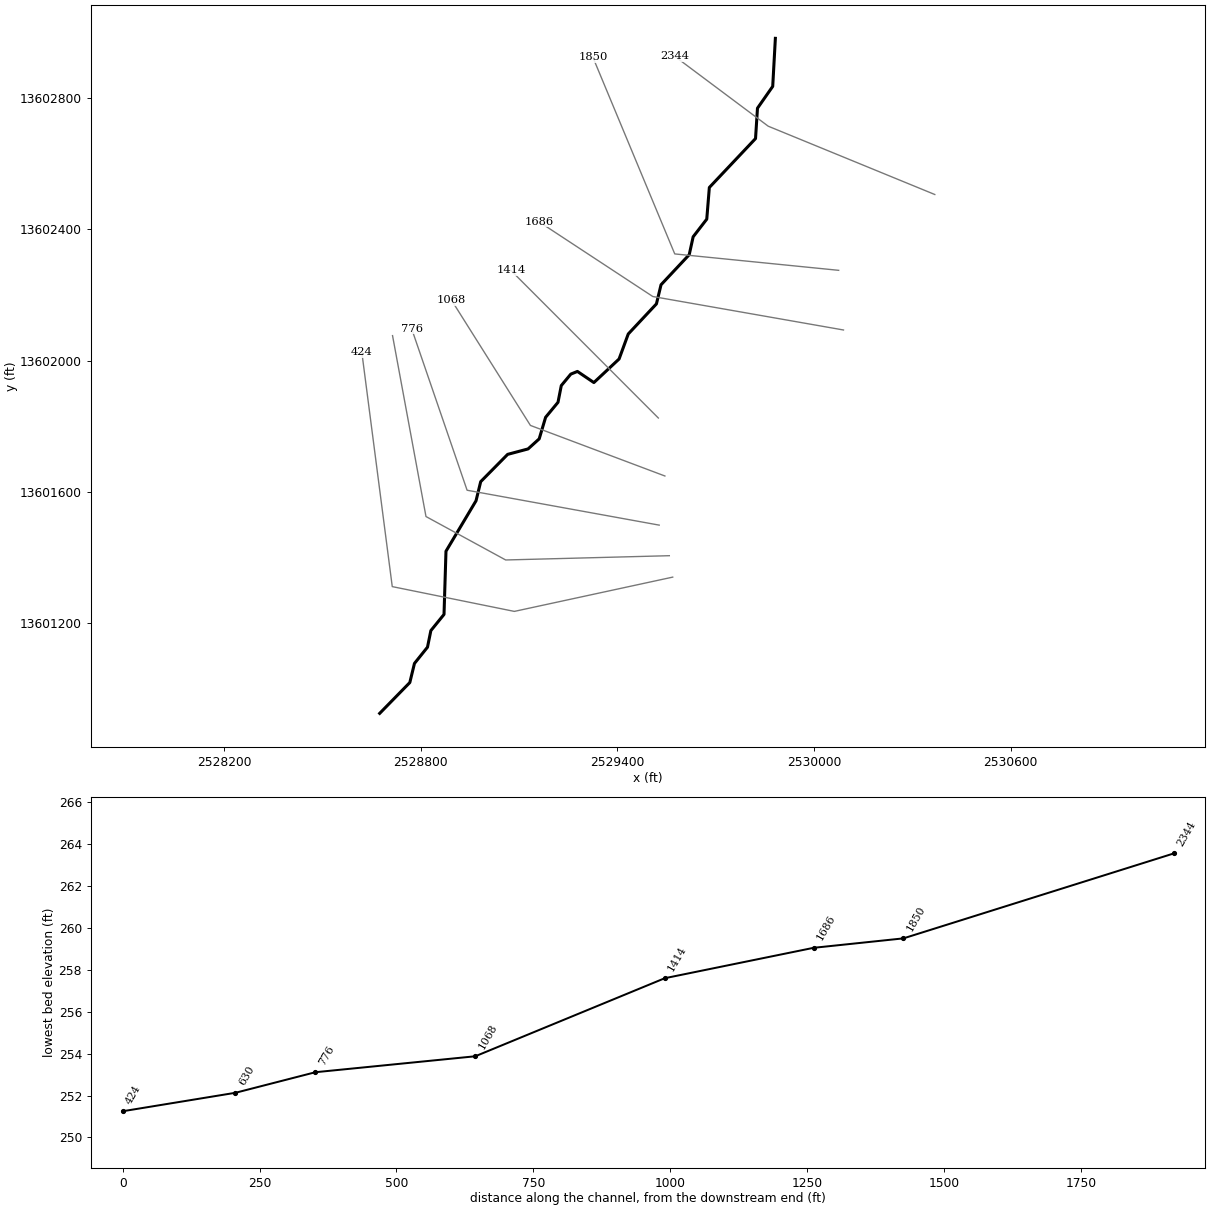
--- TRIB 6 TO SANDY FORK.prj (project) ---

Proj Title=TRIB 6 TO SANDY FORK Base Level Engineering
Current Plan=p01
Default Exp/Contr=0.3,0.1
English Units
Geom File=g01
Flow File=f01
Plan File=p01
BEGIN DESCRIPTION:
TRIB 6 TO SANDY FORK
END DESCRIPTION:

--- TRIB 6 TO SANDY FORK.p01 (plan) ---

Plan Title=Multiple Run
Short Identifier=Multiple
Geom File=g01
Flow File=f01
Subcritical Flow
K Sum by GR= 0
Std Step Tol= 0.01
Critical Tol= 0.01
Num of Std Step Trials= 20
Max Error Tol= 0.3
Flow Tol Ratio= 0.001
Split Flow NTrial= 30
Split Flow Tol= 0.02
Split Flow Ratio= 0.02
Log Output Level= 0
Friction Slope Method= 1
Unsteady Friction Slope Method= 2
Unsteady Bridges Friction Slope Method= 1
Parabolic Critical Depth
Global Vel Dist=  1 , 1 , 1
Global Log Level= 0
CheckData=True
Encroach Param= -1, 0, 0, 0
BEGIN DESCRIPTION:
Multiple Run
END DESCRIPTION:

--- TRIB 6 TO SANDY FORK.f01 (steady flow) ---

Flow Title=Multiple
Number of Profiles=7
Profile Names=10-year,25-year,50-year,1pct_min,100-year,1pct_plu,500-year
River Rch & RM= TRIB 6 TO SANDY ,Reach-1,2344
     602     972    1308     854    1703    3399    2857
Boundary for River Rch & Prof#=TRIB 6 TO SANDY ,Reach-1,1
Up Type=0
Dn Type=3
Dn Slope=0.005
Boundary for River Rch & Prof#=TRIB 6 TO SANDY ,Reach-1,2
Up Type=0
Dn Type=3
Dn Slope=0.005
Boundary for River Rch & Prof#=TRIB 6 TO SANDY ,Reach-1,3
Up Type=0
Dn Type=3
Dn Slope=0.005
Boundary for River Rch & Prof#=TRIB 6 TO SANDY ,Reach-1,4
Up Type=0
Dn Type=3
Dn Slope=0.005
Boundary for River Rch & Prof#=TRIB 6 TO SANDY ,Reach-1,5
Up Type=0
Dn Type=3
Dn Slope=0.005
Boundary for River Rch & Prof#=TRIB 6 TO SANDY ,Reach-1,6
Up Type=0
Dn Type=3
Dn Slope=0.005
Boundary for River Rch & Prof#=TRIB 6 TO SANDY ,Reach-1,7
Up Type=0
Dn Type=3
Dn Slope=0.005

--- TRIB 6 TO SANDY FORK.g01 (geometry) ---

Geom Title=Existing Conditions

River Reach=TRIB 6 TO SANDY ,Reach-1
Reach XY= 30
      2529881.90     13602981.90      2529873.82     13602835.49
      2529827.36     13602769.02      2529821.39     13602676.50
      2529680.52     13602527.43      2529672.67     13602430.97
      2529631.14     13602377.17      2529619.16     13602322.71
      2529533.18     13602231.04      2529519.13     13602172.72
      2529433.18     13602081.04      2529405.21     13602004.83
      2529328.34     13601933.00      2529278.15     13601966.92
      2529257.96     13601958.76      2529228.95     13601923.83
      2529218.90     13601872.86      2529181.11     13601827.17
      2529161.53     13601761.43      2529127.54     13601730.75
      2529065.32     13601714.22      2528983.13     13601631.07
      2528968.90     13601572.82      2528877.24     13601419.07
      2528871.25     13601226.55      2528831.12     13601177.18
      2528820.84     13601126.72      2528781.10     13601077.19
      2528766.91     13601018.92      2528675.00     13600925.00

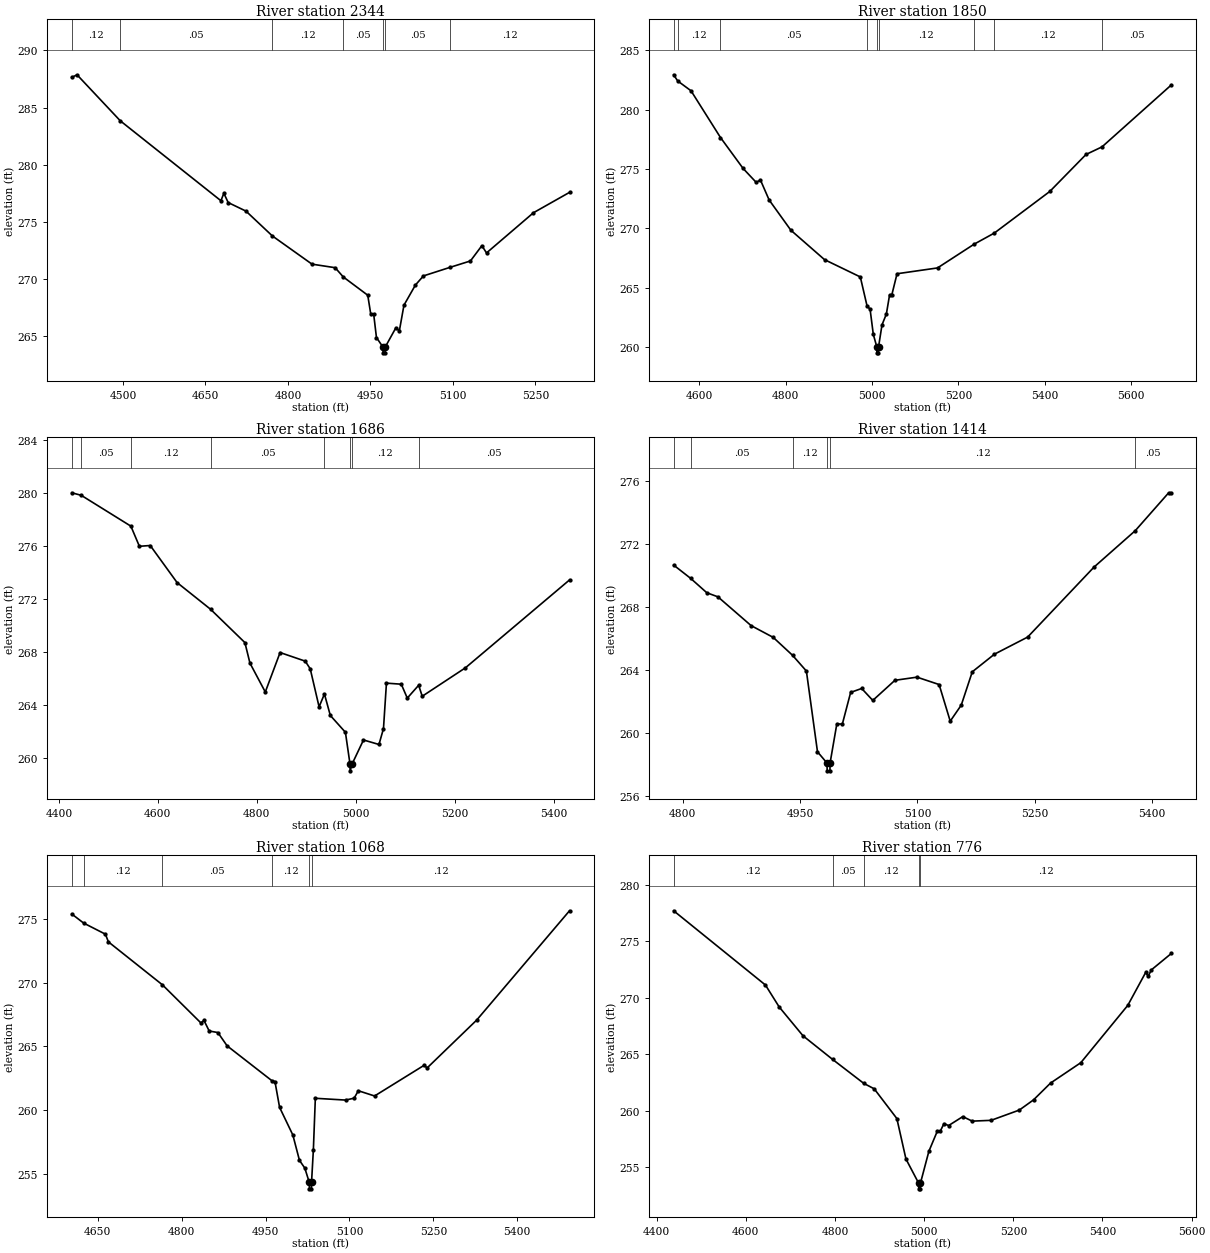
Type RM Length L Ch R = 1,2344,494,494,494
BEGIN DESCRIPTION:
TRIB 6 TO SANDY FORK 4.0
END DESCRIPTION:
XS GIS Cut Line= 3
      2530368.16     13602506.05      2529860.11     13602714.17
      2529574.90     13602927.18
#Sta/Elev= 30
  4407.0  287.64  4416.6  287.87  4495.3  283.84  4678.2  276.85  4683.6  277.50
  4691.4  276.69  4723.8  275.94  4771.7  273.77  4843.8  271.30  4885.9  270.99
  4900.7  270.18  4945.2  268.58  4950.7  266.91  4956.0  266.91  4961.0  264.88
  4972.9  264.04  4973.1  263.54  4976.6  263.54  4976.9  264.04  4996.4  265.74
  5002.6  265.45  5011.0  267.71  5031.8  269.47  5046.4  270.27  5094.1  271.01
  5131.9  271.58  5152.7  272.92  5161.1  272.28  5246.5  275.80  5312.0  277.58
#Mann=7,-1,0
  4407.0    0.12       0  4495.3    0.05       0  4771.7    0.12       0
  4900.7    0.05       0  4972.9    0.05       0  4976.9    0.05       0
  5094.1    0.12       0
Bank Sta=4972.9,4976.9
Exp/Cntr=0.3,0.1

Type RM Length L Ch R = 1,1850,164,164,164
BEGIN DESCRIPTION:
TRIB 6 TO SANDY FORK 3.0
END DESCRIPTION:
XS GIS Cut Line= 3
      2530075.05     13602275.00      2529575.00     13602325.00
      2529325.02     13602924.96
#Sta/Elev= 30
  4540.6  282.94  4549.9  282.42  4580.8  281.59  4649.0  277.65  4701.4  275.04
  4731.6  273.87  4741.6  274.06  4761.7  272.38  4812.0  269.83  4889.9  267.35
  4972.8  265.89  4988.4  263.44  4995.4  263.17  5002.9  261.04  5011.0  259.99
  5011.2  259.49  5014.7  259.49  5015.0  259.99  5023.0  261.85  5033.1  262.76
  5040.6  264.39  5045.8  264.39  5057.8  266.16  5151.5  266.65  5236.1  268.65
  5283.0  269.59  5411.5  273.10  5495.4  276.22  5532.4  276.86  5693.1  282.09
#Mann=9,-1,0
  4540.6    0.05       0  4549.9    0.12       0  4649.0    0.05       0
  4988.4    0.12       0  5011.0    0.05       0  5015.0    0.12       0
  5236.1    0.05       0  5283.0    0.12       0  5532.4    0.05       0
Bank Sta=5011,5015
Exp/Cntr=0.3,0.1

Type RM Length L Ch R = 1,1686,272,272,272
BEGIN DESCRIPTION:
Mapping XS 70815f56
END DESCRIPTION:
XS GIS Cut Line= 3
      2530089.68     13602093.21      2529508.05     13602195.21
      2529160.84     13602423.07
#Sta/Elev= 30
  4426.0  280.03  4445.1  279.84  4545.5  277.51  4562.7  275.99  4584.6  276.05
  4638.9  273.25  4706.4  271.24  4775.9  268.72  4786.1  267.17  4817.1  264.99
  4847.0  267.97  4897.8  267.32  4907.9  266.74  4925.8  263.87  4936.6  264.84
  4948.5  263.22  4979.0  261.95  4988.3  259.54  4988.5  259.04  4992.3  259.54
  5015.5  261.37  5046.8  261.03  5055.9  262.23  5061.9  265.66  5091.9  265.58
  5104.0  264.53  5127.0  265.50  5134.2  264.67  5221.6  266.82  5431.8  273.45
#Mann=8,-1,0
  4426.0    0.04       0  4445.1    0.05       0  4545.5    0.12       0
  4706.4    0.05       0  4936.6    0.12       0  4988.3    0.05       0
  4992.3    0.12       0  5127.0    0.05       0
Bank Sta=4988.3,4992.3
Exp/Cntr=0.3,0.1

Type RM Length L Ch R = 1,1414,346,346,346
BEGIN DESCRIPTION:
TRIB 6 TO SANDY FORK 2.0
END DESCRIPTION:
XS GIS Cut Line= 3
      2529525.01     13601824.99      2529375.00     13601975.00
      2529075.00     13602275.00
#Sta/Elev= 30
  4788.4  270.68  4810.0  269.84  4830.8  268.92  4845.0  268.66  4887.4  266.83
  4915.7  266.08  4940.4  264.94  4958.1  263.94  4972.3  258.80  4984.4  258.09
  4984.7  257.59  4988.2  257.59  4988.4  258.09  4997.0  260.57  5004.1  260.57
  5014.7  262.58  5028.8  262.83  5043.0  262.07  5071.3  263.35  5099.5  263.55
  5127.8  263.08  5142.0  260.75  5156.1  261.77  5170.2  263.89  5198.5  265.01
  5241.0  266.10  5325.8  270.55  5378.6  272.87  5421.3  275.28  5424.8  275.28
#Mann=6,-1,0
  4788.4    0.12       0  4810.0    0.05       0  4940.4    0.12       0
  4984.4    0.05       0  4988.4    0.12       0  5378.6    0.05       0
Bank Sta=4984.4,4988.4
Exp/Cntr=0.3,0.1

Type RM Length L Ch R = 1,1068,292,292,292
BEGIN DESCRIPTION:
Mapping XS 78f449b4
END DESCRIPTION:
XS GIS Cut Line= 3
      2529544.96     13601648.33      2529134.78     13601802.42
      2528893.91     13602184.34
#Sta/Elev= 30
  4603.6  275.36  4624.8  274.65  4663.8  273.78  4669.1  273.18  4765.7  269.82
  4834.5  266.84  4839.9  267.04  4849.3  266.21  4864.8  266.09  4881.3  265.05
  4961.5  262.32  4966.8  262.26  4975.1  260.24  4998.8  258.08  5010.6  256.10
  5020.2  255.49  5028.2  254.37  5028.5  253.87  5032.0  253.87  5032.2  254.37
  5035.5  256.93  5039.0  260.95  5093.1  260.81  5108.4  260.96  5115.8  261.54
  5144.9  261.13  5233.1  263.52  5239.0  263.33  5327.3  267.06  5493.3  275.61
#Mann=6,-1,0
  4603.6    0.05       0  4624.8    0.12       0  4765.7    0.05       0
  4961.5    0.12       0  5028.2    0.05       0  5032.2    0.12       0
Bank Sta=5028.2,5032.2
Exp/Cntr=0.3,0.1

Type RM Length L Ch R = 1,776,146,146,146
BEGIN DESCRIPTION:
Mapping XS 618f0a7b
END DESCRIPTION:
XS GIS Cut Line= 3
      2529527.59     13601498.60      2528941.64     13601604.93
      2528772.37     13602097.55
#Sta/Elev= 30
  4438.2  277.71  4644.1  271.14  4674.9  269.20  4728.3  266.65  4794.7  264.56
  4864.6  262.44  4888.0  261.96  4938.8  259.33  4959.2  255.75  4987.7  253.61
  4987.9  253.11  4991.4  253.11  4991.7  253.61  5010.6  256.43  5029.5  258.21
  5036.2  258.21  5044.4  258.88  5054.9  258.71  5086.7  259.50  5107.8  259.10
  5150.1  259.17  5213.5  260.08  5245.3  260.98  5283.6  262.47  5351.4  264.27
  5456.7  269.34  5497.1  272.27  5502.3  271.90  5509.6  272.48  5554.6  273.94
#Mann=5,-1,0
  4438.2    0.12       0  4794.7    0.05       0  4864.6    0.12       0
  4987.7    0.05       0  4991.7    0.12       0
Bank Sta=4987.7,4991.7
Exp/Cntr=0.3,0.1

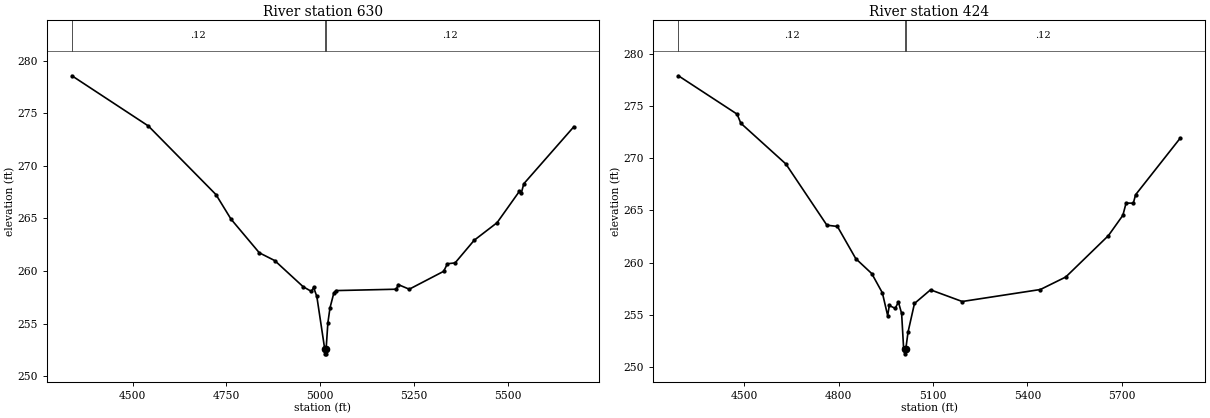
Type RM Length L Ch R = 1,630,206,206,206
BEGIN DESCRIPTION:
Mapping XS 99cd4fc7
END DESCRIPTION:
XS GIS Cut Line= 4
      2529558.44     13601405.45      2529059.29     13601392.43
      2528816.23     13601524.81      2528714.23     13602076.06
#Sta/Elev= 30
  4338.7  278.55  4542.2  273.78  4722.3  267.26  4762.3  264.93  4837.7  261.73
  4878.8  260.99  4954.7  258.50  4976.6  258.06  4982.3  258.44  4990.9  257.58
  5011.7  252.63  5012.0  252.13  5015.5  252.13  5015.7  252.63  5020.3  255.08
  5026.0  256.51  5036.4  257.94  5042.1  258.14  5202.7  258.27  5207.8  258.71
  5237.0  258.27  5328.6  259.97  5338.7  260.69  5359.1  260.77  5409.9  262.92
  5470.9  264.59  5530.3  267.57  5535.4  267.40  5542.1  268.29  5675.4  273.71
#Mann=3,-1,0
  4338.7    0.12       0  5011.7    0.05       0  5015.7    0.12       0
Bank Sta=5011.7,5015.7
Exp/Cntr=0.3,0.1

Type RM Length L Ch R = 1,424,0,0,0
BEGIN DESCRIPTION:
Mapping XS 9d0a2753
END DESCRIPTION:
XS GIS Cut Line= 4
      2529568.82     13601340.18      2529085.76     13601235.74
      2528713.37     13601311.26      2528620.46     13602025.95
#Sta/Elev= 30
  4291.1  277.92  4477.6  274.24  4489.4  273.37  4632.6  269.46  4762.9  263.59
  4796.3  263.47  4854.7  260.38  4905.4  258.95  4939.2  257.10  4956.1  254.91
  4961.2  255.89  4980.0  255.61  4990.2  256.22  5000.4  255.12  5006.7  251.77
  5009.8  251.75  5010.1  251.25  5013.8  251.75  5020.8  253.34  5041.2  256.08
  5092.2  257.39  5192.9  256.27  5441.3  257.42  5522.0  258.62  5657.5  262.59
  5703.5  264.54  5713.6  265.71  5736.6  265.70  5743.9  266.51  5886.0  271.95
#Mann=3,-1,0
  4291.1    0.12       0  5009.8    0.05       0  5013.8    0.12       0
Bank Sta=5009.8,5013.8
Exp/Cntr=0.3,0.1

Chan Stop Cuts=-1