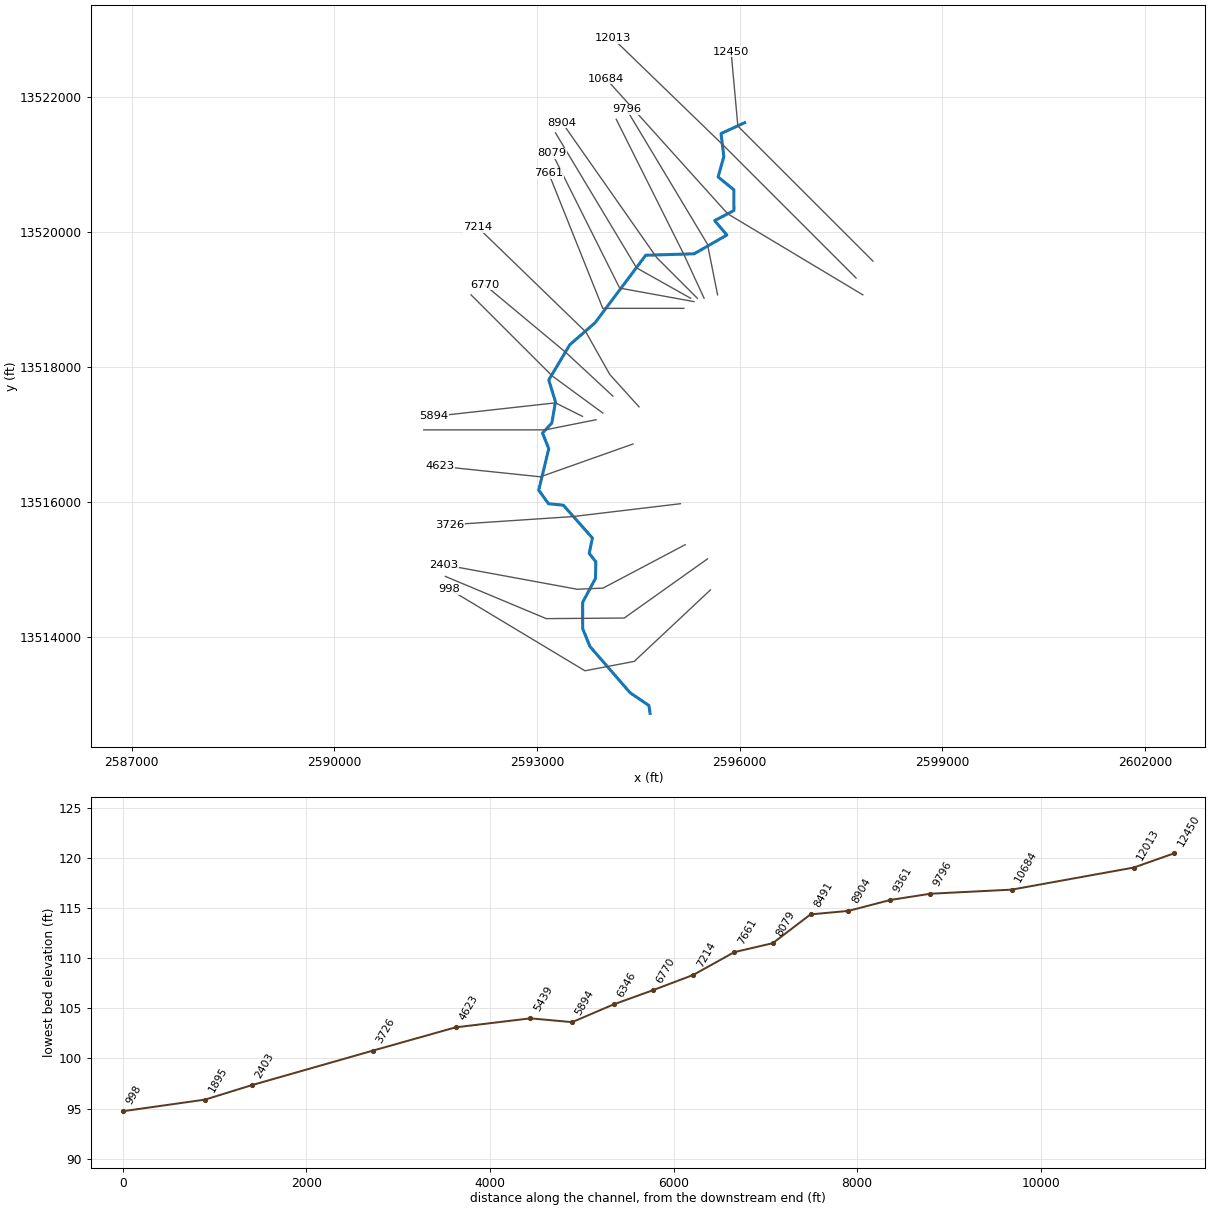
--- TRIB 6 TO SPRING CREEK.prj (project) ---

Proj Title=TRIB 6 TO SPRING CREEK Base Level Engineering
Current Plan=p01
Default Exp/Contr=0.3,0.1
English Units
Geom File=g01
Flow File=f01
Plan File=p01
Y Axis Title=Elevation
X Axis Title(PF)=Main Channel Distance
X Axis Title(XS)=Station
BEGIN DESCRIPTION:
TRIB 6 TO SPRING CREEK
END DESCRIPTION:
DSS File=dss
DSS Export Rating Curves= 0
DSS Export Rating Curve Sorted= 0
DSS Export Volume Flow Curves= 0
DXF OffsetX= 0
DXF OffsetY= 0
DXF ScaleX= 1
DXF ScaleY= 10

--- TRIB 6 TO SPRING CREEK.p01 (plan) ---

Plan Title=Multiple Run
Program Version=4.10
Short Identifier=Multiple Run
Geom File=g01
Flow File=f01
Subcritical Flow
K Sum by GR= 0
Std Step Tol= 0.01
Critical Tol= 0.01
Num of Std Step Trials= 20
Max Error Tol= 0.3
Flow Tol Ratio= 0.001
Split Flow NTrial= 30
Split Flow Tol= 0.02
Split Flow Ratio= 0.02
Log Output Level= 0
Friction Slope Method= 1
Unsteady Friction Slope Method= 2
Unsteady Bridges Friction Slope Method= 1
Parabolic Critical Depth
Global Vel Dist= 1 , 1 , 1
Global Log Level= 0
CheckData=True
Encroach Param=-1 ,0,0, 0
BEGIN DESCRIPTION:
Multiple Run
END DESCRIPTION:
Computation Interval=1HOUR
Output Interval=1HOUR
Run HTab= 0
Run UNet= 0
Run PostProcess= 0
Run WQNet= 0
UNET Theta= 1
UNET Theta Warmup= 1
UNET ZTol= 0.02
UNET ZSATol= 0.05
UNET MxIter= 20
UNET MaxInSteps= 0
UNET DtIC= 0
UNET DtMin= 0
UNET MaxCRTS= 20
UNET WFStab= 2
UNET SFStab= 1
UNET WFX= 1
UNET SFX= 1
UNET DSS MLevel= 4
UNET DZMax Abort= 100
UNET Convert EG Bridges= 0
UNET Use Existing IB Tables=-1
UNET Froude Reduction=False
UNET Froude Limit= 1
UNET Froude Power= 10
UNET Time Slicing=0,0, 5
UNET Junction Losses=0
Instantaneous Interval=1HOUR
DSS File=dss
Write IC File= 0
Write IC File at Sim End=0
Echo Input=False
Echo Parameters=False
Echo Output=False
Write Detailed= 0
WQ AD Non Conservative
WQ ULTIMATE=-1
WQ Max Comp Step=1HOUR
WQ Output Interval=15MIN
WQ Output Selected Increments= 0
WQ Output face flow=0
WQ Output face velocity=0
WQ Output face area=0
WQ Output face dispersion=0
WQ Output cell volume=0
WQ Output cell surface area=0
WQ Output cell continuity=0
WQ Output cumulative cell continuity=0
WQ Output face conc=0
WQ Output face dconc_dx=0
WQ Output face courant=0
WQ Output face peclet=0
WQ Output face adv mass=0
WQ Output face disp mass=0
WQ Output cell mass=0
WQ Output cell source sink temp=0
WQ Output cell source sink nsm=0
WQ Output MaxMinRange=-1
WQ Daily Max Min Mean=-1
WQ Daily Range=0
WQ Daily Time=0
WQ Create Restart=0
WQ Fixed Restart=0
WQ System Summary=0
WQ Use Fixed Temperature=0
Sorting and Armoring Iterations= 10
XS Update Threshold= 0.02
Hydraulics Update Threshold= 0.02
Energy Slope Method= 1
Volume Change Method= 0
XS Weighting Method= 0
Number of US Weighted Cross Sections= 1
Number of DS Weighted Cross Sections= 1
Upstream XS Weight=0.25
Main XS Weight=0.5
Downstream XS Weight=0.25
Number of DS XS's Weighted with US Boundary= 1
Upstream Boundary Weight= 1
Weight of XSs Associated with US Boundary= 0
Number of US XS's Weighted with DS Boundary= 1
Downstream Boundary Weight= 0.5
Weight of XSs Associated with DS Boundary= 0.5
Sediment Output Level= 4
Mass or Volume Output= 0
Output Increment Type= 1
Profile and TS Output Increment= 10
XS Output Flag= 0
XS Output Increment= 10
Disregard all LS=0
Disregard all Conn=0
Disregard all Breaches=0
Disregard all Pumps=0

--- TRIB 6 TO SPRING CREEK.f01 (steady flow) ---

Flow Title=Multiple
Number of Profiles=7
Profile Names=10-year,25-year,50-year,1pct_min,100-year,1pct_plu,500-year
River Rch & RM= TRIB 6 TO SPRING,Reach-1,12450
    1008    1618    2165    1399    2791    5568    4584
River Rch & RM= TRIB 6 TO SPRING,Reach-1,10684
    1424    2318    3132    2042    4074    8128    6811
River Rch & RM= TRIB 6 TO SPRING,Reach-1,9796
    1578    2587    3512    2299    4587    9152    7737
River Rch & RM= TRIB 6 TO SPRING,Reach-1,7214
    1775    2925    3985    2617    5221   10417    8862
River Rch & RM= TRIB 6 TO SPRING,Reach-1,4623
    1910    3158    4311    2836    5658   11290    9639
Boundary for River Rch & Prof#=TRIB 6 TO SPRING,Reach-1,1
Up Type=0
Dn Type=3
Dn Slope=0.005
Boundary for River Rch & Prof#=TRIB 6 TO SPRING,Reach-1,2
Up Type=0
Dn Type=3
Dn Slope=0.005
Boundary for River Rch & Prof#=TRIB 6 TO SPRING,Reach-1,3
Up Type=0
Dn Type=3
Dn Slope=0.005
Boundary for River Rch & Prof#=TRIB 6 TO SPRING,Reach-1,4
Up Type=0
Dn Type=3
Dn Slope=0.005
Boundary for River Rch & Prof#=TRIB 6 TO SPRING,Reach-1,5
Up Type=0
Dn Type=3
Dn Slope=0.005
Boundary for River Rch & Prof#=TRIB 6 TO SPRING,Reach-1,6
Up Type=0
Dn Type=3
Dn Slope=0.005
Boundary for River Rch & Prof#=TRIB 6 TO SPRING,Reach-1,7
Up Type=0
Dn Type=3
Dn Slope=0.005

--- TRIB 6 TO SPRING CREEK.g01 (geometry) ---

Geom Title=Existing Conditions
Program Version=4.10

River Reach=TRIB 6 TO SPRING,Reach-1
Reach XY= 30
        2596075.       13521625.      2595726.04     13521464.57
      2595767.44       13521125.      2595682.69     13520821.33
       2595915.7     13520631.67      2595917.74      13520324.7
      2595632.07     13520175.02      2595811.74     13519961.31
      2595328.31     13519683.07      2594611.35     13519661.81
      2593861.37     13518661.79      2593485.77      13518334.7
       2593175.6     13517814.38      2593274.91     13517490.39
      2593221.46     13517176.46      2593082.79     13517028.42
      2593175.39     13516795.13      2593027.24     13516180.93
      2593172.53     13515980.45       2593391.8     13515958.58
      2593821.86     13515473.36      2593774.94     13515244.99
      2593872.94     13515119.14      2593867.24     13514875.08
      2593676.97     13514519.11      2593677.25     13514130.94
      2593785.76     13513865.32      2594380.25     13513180.44
      2594658.57     13512991.77        2594675.       13512875.

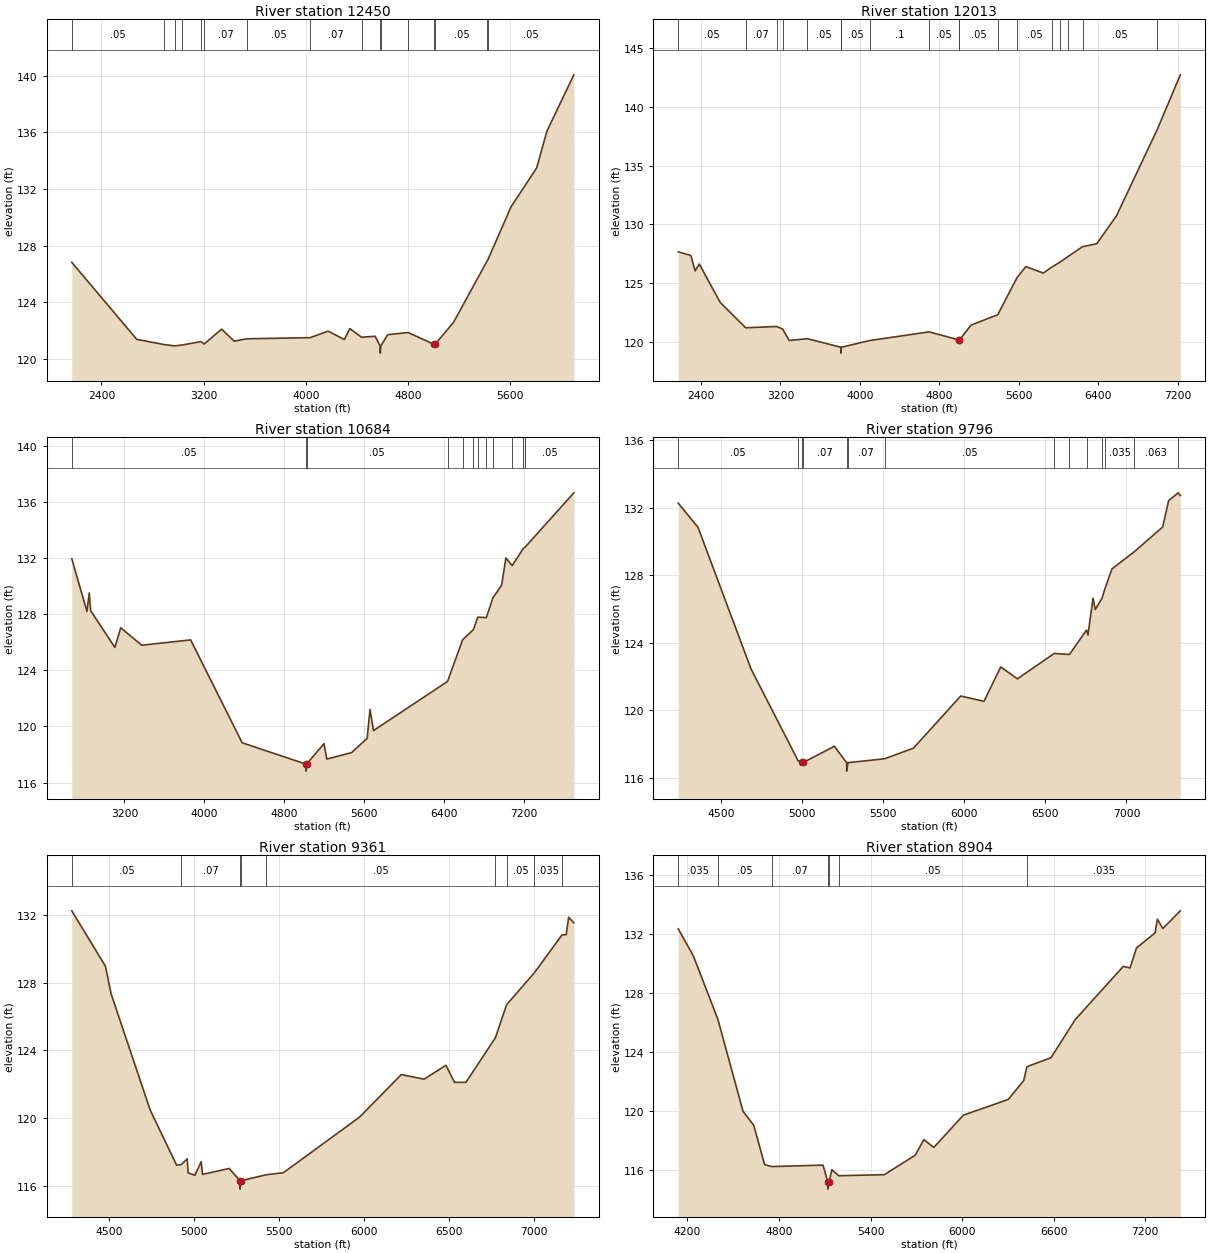
Type RM Length L Ch R = 1 ,12450   ,437,437,437
BEGIN DESCRIPTION:
TRIB 6 TO SPRING CREEK 22.0
END DESCRIPTION:
XS GIS Cut Line= 3
      2597974.99     13519575.01        2595975.       13521575.
        2595875.     13522675.04
#Sta/Elev= 30
  2167.4  126.83  2676.5   121.4  2893.4  121.03  2975.5  120.94  3030.1     121
  3179.4  121.24  3204.5  121.07  3341.2  122.12  3440.2  121.27    3538  121.44
  4034.5  121.52  4175.6  121.98  4302.9  121.39  4345.3  122.16  4437.6  121.55
  4543.3  121.62  4583.7  120.93  4583.9  120.43  4587.7  120.93  4642.3  121.73
  4802.2  121.88  5005.9  121.05  5015.9  121.08  5156.5  122.58  5422.7  126.95
  5426.9  127.01  5608.3  130.74  5809.2  133.49  5889.5  136.08  6100.4  140.05
#Mann= 16 ,-1 , 0
  2167.4     .05       0  2893.4    .035       0  2975.5     .07       0
  3030.1    .035       0  3179.4     .05       0  3204.5     .07       0
    3538     .05       0  4034.5     .07       0  4437.6      .1       0
  4583.7     .05       0  4587.7      .1       0  4802.2     .05       0
  5005.9     .05       0  5015.9     .05       0  5422.7     .07       0
  5426.9     .05       0
Bank Sta=5005.9,5015.9
XS Rating Curve= 0 ,0
Exp/Cntr=0.3,0.1

Type RM Length L Ch R = 1 ,12013   ,1329,1329,1329
BEGIN DESCRIPTION:
TRIB 6 TO SPRING CREEK 21.0
END DESCRIPTION:
XS GIS Cut Line= 3
      2597725.02     13519324.98        2595725.       13521325.
      2594125.02     13522874.98
#Sta/Elev= 30
  2171.5  127.65  2298.8  127.34  2341.2  126.03  2383.7  126.61  2595.8  123.32
  2851.1  121.18  3162.6  121.29  3222.9  121.07  3288.8   120.1  3472.4  120.25
  3809.2  119.52  3809.7  119.02  3814.8  119.52  4097.6  120.09  4697.1  120.83
    5000  120.14  5003.4  120.14  5120.2  121.41  5388.9  122.29  5583.8  125.46
  5671.7  126.39  5848.7  125.84  5940.3  126.39  6012.1  126.75  6098.8  127.26
  6242.7  128.09  6386.1  128.34  6584.1  130.71  6995.9  138.08  7227.6  142.73
#Mann= 18 ,-1 , 0
  2171.5     .05       0  2851.1     .07       0  3162.6     .05       0
  3222.9     .07       0  3472.4     .05       0  3809.2     .05       0
  3814.8     .05       0  4097.6      .1       0  4697.1     .05       0
    5000     .05       0  5003.4     .05       0  5388.9     .07       0
  5583.8     .05       0  5940.3    .035       0  6012.1     .05       0
  6098.8    .035       0  6242.7     .05       0  6995.9     .07       0
Bank Sta=5000,5003.4
XS Rating Curve= 0 ,0
Exp/Cntr=0.3,0.1

Type RM Length L Ch R = 1 ,10684   ,888,888,888
BEGIN DESCRIPTION:
TRIB 6 TO SPRING CREEK 20.0
END DESCRIPTION:
XS GIS Cut Line= 3
      2597825.03     13519074.98        2595825.       13520275.
      2594025.03     13522274.97
#Sta/Elev= 30
  2673.8  131.96  2825.4   128.2  2848.8  129.52  2862.4  128.26  3105.3  125.63
  3163.6  127.04  3373.6  125.79  3863.4  126.17  4378.4  118.84  5016.7  117.32
  5017.2  116.82  5023.3  117.32  5197.2  118.78  5225.6  117.68  5473.7  118.14
  5629.2  119.16  5657.6  121.22  5692.7  119.71  6433.2  123.21  6584.2  126.18
    6692   126.9  6735.8  127.79  6821.4  127.76  6887.5  129.17  6974.6  130.07
  7017.2  132.01  7080.2  131.46  7190.8  132.68  7209.6  132.78  7696.9  136.65
#Mann= 12 ,-1 , 0
  2673.8     .05       0  5016.7     .05       0  5023.3     .05       0
  6433.2     .07       0  6584.2     .12       0    6692     .07       0
  6735.8    .035       0  6821.4     .05       0  6887.5    .063       0
  7080.2     .05       0  7190.8    .035       0  7209.6     .05       0
Bank Sta=5016.7,5023.3
XS Rating Curve= 0 ,0
Exp/Cntr=0.3,0.1

Type RM Length L Ch R = 1 ,9796    ,435,435,435
BEGIN DESCRIPTION:
TRIB 6 TO SPRING CREEK 19.0
END DESCRIPTION:
XS GIS Cut Line= 3
        2595675.     13519075.01        2595525.       13519825.
      2594325.01     13521824.98
#Sta/Elev= 30
  4234.9  132.26  4357.3  130.82  4683.6  122.46  4974.5  117.02  4997.2  116.93
  5007.5  116.93    5198  117.88  5273.7  116.91  5274.2  116.41  5281.7  116.91
  5507.7  117.14  5685.9  117.77  5977.4  120.85  6121.2  120.54  6224.2  122.57
  6327.3  121.87  6554.2  123.37  6648.2  123.31  6753.4  124.75  6762.6  124.46
  6793.7  126.65  6807.3  125.97  6848.6  126.62  6866.5  127.18  6910.4  128.37
  7048.9  129.39  7223.3  130.85  7260.2  132.41  7318.9  132.87  7332.1  132.71
#Mann= 14 ,-1 , 0
  4234.9     .05       0  4974.5     .07       0  4997.2     .05       0
  5007.5     .07       0  5273.7     .07       0  5281.7     .07       0
  5507.7     .05       0  6554.2     .07       0  6648.2     .12       0
  6753.4     .07       0  6848.6     .05       0  6866.5    .035       0
  7048.9    .063       0  7318.9    .035       0
Bank Sta=4997.2,5007.5
XS Rating Curve= 0 ,0
Exp/Cntr=0.3,0.1

Type RM Length L Ch R = 1 ,9361    ,457,457,457
BEGIN DESCRIPTION:
TRIB 6 TO SPRING CREEK 18.0
END DESCRIPTION:
XS GIS Cut Line= 3
      2595474.99     13519025.03        2595175.       13519675.
      2594175.01     13521674.98
#Sta/Elev= 30
    4280  132.24  4477.8  128.97  4511.7  127.32  4741.2  120.46  4896.7   117.2
  4924.7  117.25  4958.7  117.58  4964.2  116.75  5004.2  116.61  5040.6  117.41
    5049  116.66  5205.5  117.01  5268.6  116.29  5269.1  115.79  5276.6  116.29
  5423.4  116.64  5524.1  116.76  5971.3  120.04  6217.3  122.56  6351.5  122.29
    6480  123.11  6530.4   122.1  6597.4   122.1  6770.8  124.74  6836.4  126.69
  6999.1  128.57  7162.6  130.82  7187.2  130.83  7201.2  131.86  7231.9  131.53
#Mann= 9 ,-1 , 0
    4280     .05       0  4924.7     .07       0  5268.6     .05       0
  5276.6     .07       0  5423.4     .05       0  6770.8    .035       0
  6836.4     .05       0  6999.1    .035       0  7162.6    .063       0
Bank Sta=5268.6,5276.6
XS Rating Curve= 0 ,0
Exp/Cntr=0.3,0.1

Type RM Length L Ch R = 1 ,8904    ,413,413,413
BEGIN DESCRIPTION:
TRIB 6 TO SPRING CREEK 17.0
END DESCRIPTION:
XS GIS Cut Line= 3
      2595375.03     13519024.97        2594775.       13519625.
      2593374.99     13521625.02
#Sta/Elev= 30
  4140.1  132.37  4239.1  130.53  4399.9  126.23  4564.4  119.99  4635.1  119.03
  4705.8  116.37  4751.5  116.23  5088.5  116.33  5120.2   115.2  5120.7   114.7
  5128.2   115.2  5147.4  116.02  5191.3  115.61  5490.4  115.68  5692.7     117
  5749.4  118.06  5814.8  117.53  6008.4  119.72  6303.1  120.79  6404.2  122.08
    6425  123.01  6582.9  123.62  6740.7   126.2  7056.4  129.82  7100.4  129.71
  7142.7  131.07  7264.8  132.09  7279.6  133.03  7315.3  132.39    7430  133.59
#Mann= 7 ,-1 , 0
  4140.1    .035       0  4399.9     .05       0  4751.5     .07       0
  5120.2     .05       0  5128.2     .07       0  5191.3     .05       0
    6425    .035       0
Bank Sta=5120.2,5128.2
XS Rating Curve= 0 ,0
Exp/Cntr=0.3,0.1

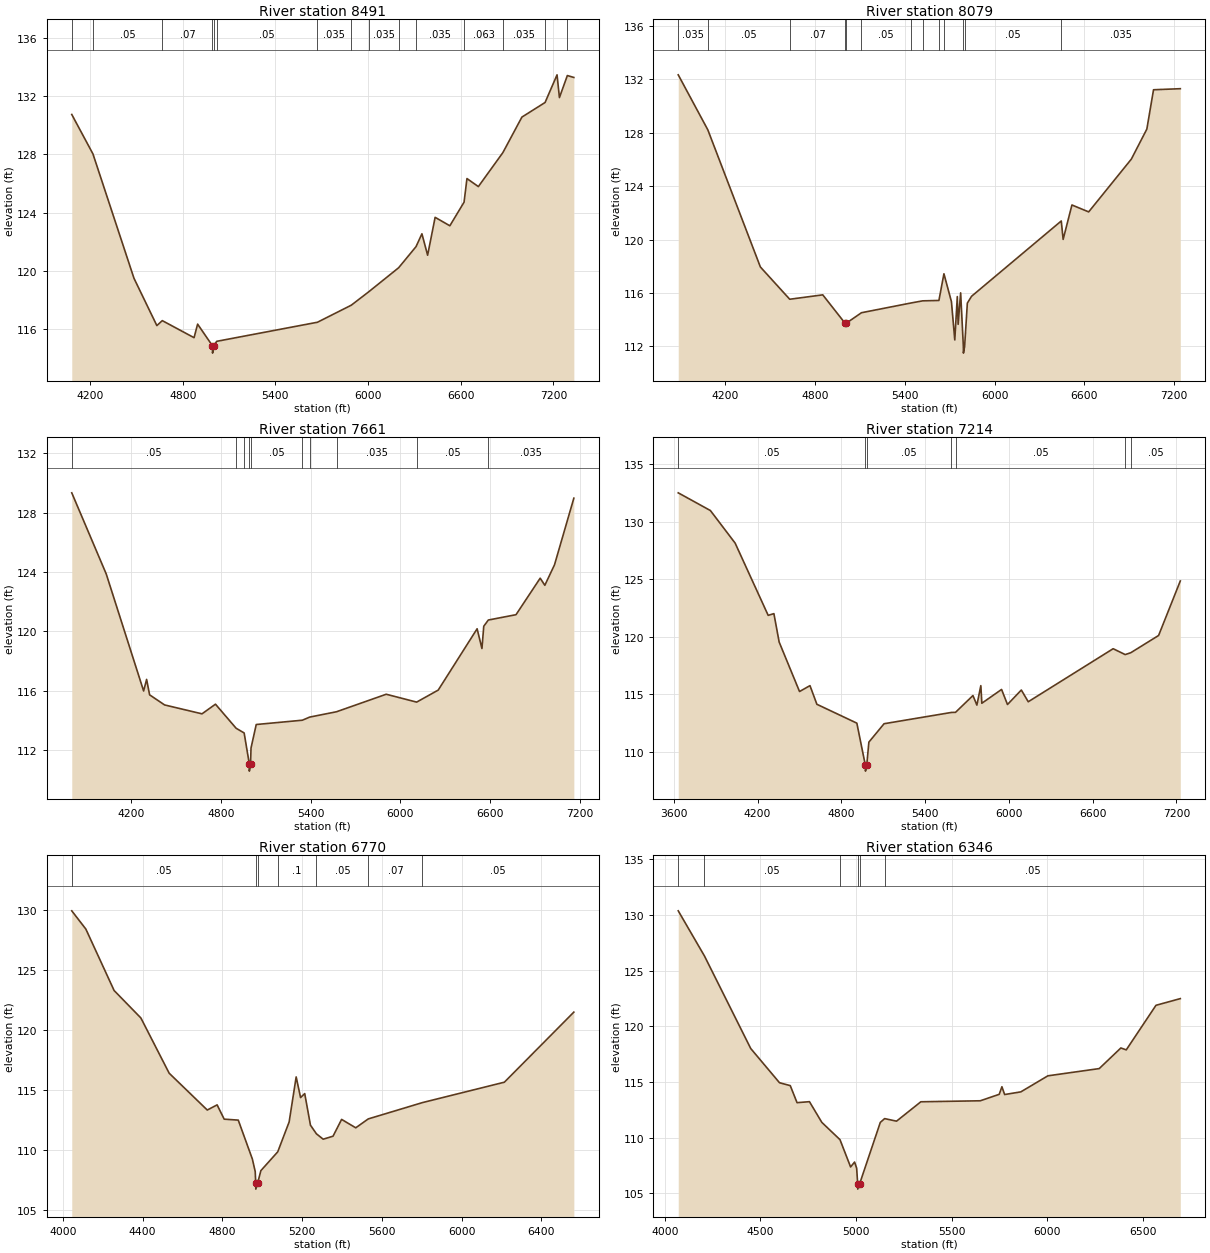
Type RM Length L Ch R = 1 ,8491    ,412,412,412
BEGIN DESCRIPTION:
TRIB 6 TO SPRING CREEK 16.0
END DESCRIPTION:
XS GIS Cut Line= 3
      2595275.04     13519024.98        2594475.       13519475.
        2593275.       13521475.
#Sta/Elev= 30
  4081.9  130.73  4219.1  128.02  4484.5  119.49  4632.7  116.24    4668  116.58
  4873.6  115.41  4896.6  116.34  4992.9  114.85  4993.4  114.35  5001.1  114.85
  5020.4  115.16  5672.5  116.47  5891.4  117.64  6004.5  118.56    6198  120.21
  6310.7  121.66  6348.7  122.54  6385.6  121.07  6434.2  123.67  6529.5  123.09
  6621.5  124.71  6640.3  126.33  6714.1  125.78  6872.7  128.11    6996  130.55
  7145.9  131.55  7223.4  133.45  7238.9  131.89  7290.2   133.4  7332.2  133.27
#Mann= 15 ,-1 , 0
  4081.9    .035       0  4219.1     .05       0    4668     .07       0
  4992.9     .05       0  5001.1     .07       0  5020.4     .05       0
  5672.5    .035       0  5891.4     .05       0  6004.5    .035       0
    6198     .05       0  6310.7    .035       0  6621.5    .063       0
  6872.7    .035       0  7145.9    .063       0  7290.2    .035       0
Bank Sta=4992.9,5001.1
XS Rating Curve= 0 ,0
Exp/Cntr=0.3,0.1

Type RM Length L Ch R = 1 ,8079    ,418,418,418
BEGIN DESCRIPTION:
TRIB 6 TO SPRING CREEK 15.0
END DESCRIPTION:
XS GIS Cut Line= 3
      2595324.96     13518975.01        2594225.       13519175.
      2593224.98     13521175.04
#Sta/Elev= 30
  3886.5  132.35  4084.4  128.22  4435.3  117.94  4631.3  115.52    4852  115.85
  5001.9  113.71  5007.3  113.71  5110.6  114.51  5441.5  115.24  5519.3   115.4
    5628  115.43  5661.5  117.43  5711.6  115.34    5734  112.47  5750.8  115.72
  5756.4  113.64  5773.1     116  5791.3  111.98  5791.8  111.48  5799.7  111.98
  5817.9  115.23  5845.8  115.74  6445.3  121.39  6457.9  120.01  6516.6  122.59
  6628.4  122.07  6913.5  126.03    7017  128.28  7061.7  131.23  7240.6  131.31
#Mann= 13 ,-1 , 0
  3886.5    .035       0  4084.4     .05       0  4631.3     .07       0
  5001.9     .05       0  5007.3     .07       0  5110.6     .05       0
  5441.5    .035       0  5519.3     .05       0    5628     .07       0
  5661.5     .05       0  5791.3     .07       0  5799.7     .05       0
  6445.3    .035       0
Bank Sta=5001.9,5007.3
XS Rating Curve= 0 ,0
Exp/Cntr=0.3,0.1

Type RM Length L Ch R = 1 ,7661    ,447,447,447
BEGIN DESCRIPTION:
TRIB 6 TO SPRING CREEK 14.0
END DESCRIPTION:
XS GIS Cut Line= 3
      2595174.98       13518875.        2593975.       13518875.
      2593175.02     13520874.96
#Sta/Elev= 30
  3804.8  129.34  4034.8  123.88  4284.8  115.99  4304.8  116.77  4324.8  115.73
  4424.8  115.05  4674.8  114.45  4764.8   115.1  4902.6  113.48  4956.4  113.16
  4990.6  111.09  4991.1  110.59    4999  111.09  5002.3  112.15  5037.1  113.73
    5345  114.02    5394  114.23  5573.3  114.59  5905.4  115.77  6108.7  115.24
  6252.8  116.05  6512.6  120.18  6544.9  118.85    6557  120.35  6587.5  120.77
  6772.5  121.13    6934  123.59    6965  123.11  7029.6  124.49  7158.8  128.98
#Mann= 10 ,-1 , 0
  3804.8     .05       0  4902.6     .07       0  4956.4     .05       0
  4990.6     .05       0    4999     .05       0    5345     .07       0
    5394     .05       0  5573.3    .035       0  6108.7     .05       0
  6587.5    .035       0
Bank Sta=4990.6,4999
XS Rating Curve= 0 ,0
Exp/Cntr=0.3,0.1

Type RM Length L Ch R = 1 ,7214    ,444,444,444
BEGIN DESCRIPTION:
TRIB 6 TO SPRING CREEK 13.0
END DESCRIPTION:
XS GIS Cut Line= 4
       2594511.9     13517416.13      2594079.88     13517894.11
        2593725.       13518525.        2592125.       13520075.
#Sta/Elev= 30
  3631.9  132.51  3862.3  130.97  4039.4  128.14  4276.1  121.86    4317  122.01
  4354.7  119.54  4500.6  115.24  4575.5  115.75  4624.9  114.13  4911.1  112.49
  4972.3  108.82  4972.8  108.32  4981.9  108.82  4997.2  110.84  5106.1  112.44
    5588  113.42  5617.8  113.43  5742.6  114.89  5770.8  114.06  5799.1  115.75
  5806.3  114.22  5947.6  115.42    5990  114.11  6089.1  115.37  6138.7  114.35
  6746.8  118.96    6833  118.45  6872.7  118.61  7072.2  120.11  7227.7  124.85
#Mann= 7 ,-1 , 0
  3631.9     .05       0  4972.3     .05       0  4981.9     .05       0
    5588     .07       0  5617.8     .05       0    6833    .035       0
  6872.7     .05       0
Bank Sta=4972.3,4981.9
XS Rating Curve= 0 ,0
Exp/Cntr=0.3,0.1

Type RM Length L Ch R = 1 ,6770    ,424,424,424
BEGIN DESCRIPTION:
TRIB 6 TO SPRING CREEK 12.0
END DESCRIPTION:
XS GIS Cut Line= 3
      2594124.97     13517575.03        2593425.       13518225.
      2592224.97     13519225.03
#Sta/Elev= 30
    4045  129.97  4115.6  128.45  4257.3  123.33  4391.6  121.04  4533.3  116.44
  4724.4  113.37  4773.7   113.8  4809.2  112.61  4879.8  112.53  4950.6  109.28
  4964.8  108.24  4967.3  107.28  4967.8  106.78  4976.9  107.28  4993.1  108.32
  5077.8  109.89  5134.9  112.38  5170.1  116.13  5192.2  114.41    5213  114.74
  5241.7  112.11  5271.6  111.39  5305.5  110.94  5354.9  111.19  5397.9  112.59
  5468.8  111.89  5531.5  112.63  5803.2  113.99    6214  115.69  6562.3  121.53
#Mann= 7 ,-1 , 0
    4045     .05       0  4967.3     .05       0  4976.9     .05       0
  5077.8      .1       0  5271.6     .05       0  5531.5     .07       0
  5803.2     .05       0
Bank Sta=4967.3,4976.9
XS Rating Curve= 0 ,0
Exp/Cntr=0.3,0.1

Type RM Length L Ch R = 1 ,6346    ,452,452,452
BEGIN DESCRIPTION:
TRIB 6 TO SPRING CREEK 11.0
END DESCRIPTION:
XS GIS Cut Line= 3
      2593975.01     13517324.99        2593225.       13517875.
      2592025.02     13519074.98
#Sta/Elev= 30
  4069.9  130.36    4207  126.31  4449.3     118  4599.8  114.93  4656.1  114.67
  4691.6  113.14  4756.5  113.23  4821.3  111.37  4916.3  109.82  4971.8  107.37
  4992.6  107.81  5003.5  107.26  5008.7  105.88  5009.2  105.38  5019.5  105.88
  5127.3  111.37    5150  111.71  5212.1  111.48  5339.4  113.22  5650.5  113.31
  5749.5  113.89  5763.6  114.57  5777.8  113.87  5862.6  114.11  6004.1  115.55
  6272.8   116.2  6385.9  118.05  6414.2  117.88  6569.7  121.88    6697  122.48
#Mann= 6 ,-1 , 0
  4069.9    .035       0    4207     .05       0  4916.3     .07       0
  5008.7     .05       0  5019.5     .07       0    5150     .05       0
Bank Sta=5008.7,5019.5
XS Rating Curve= 0 ,0
Exp/Cntr=0.3,0.1

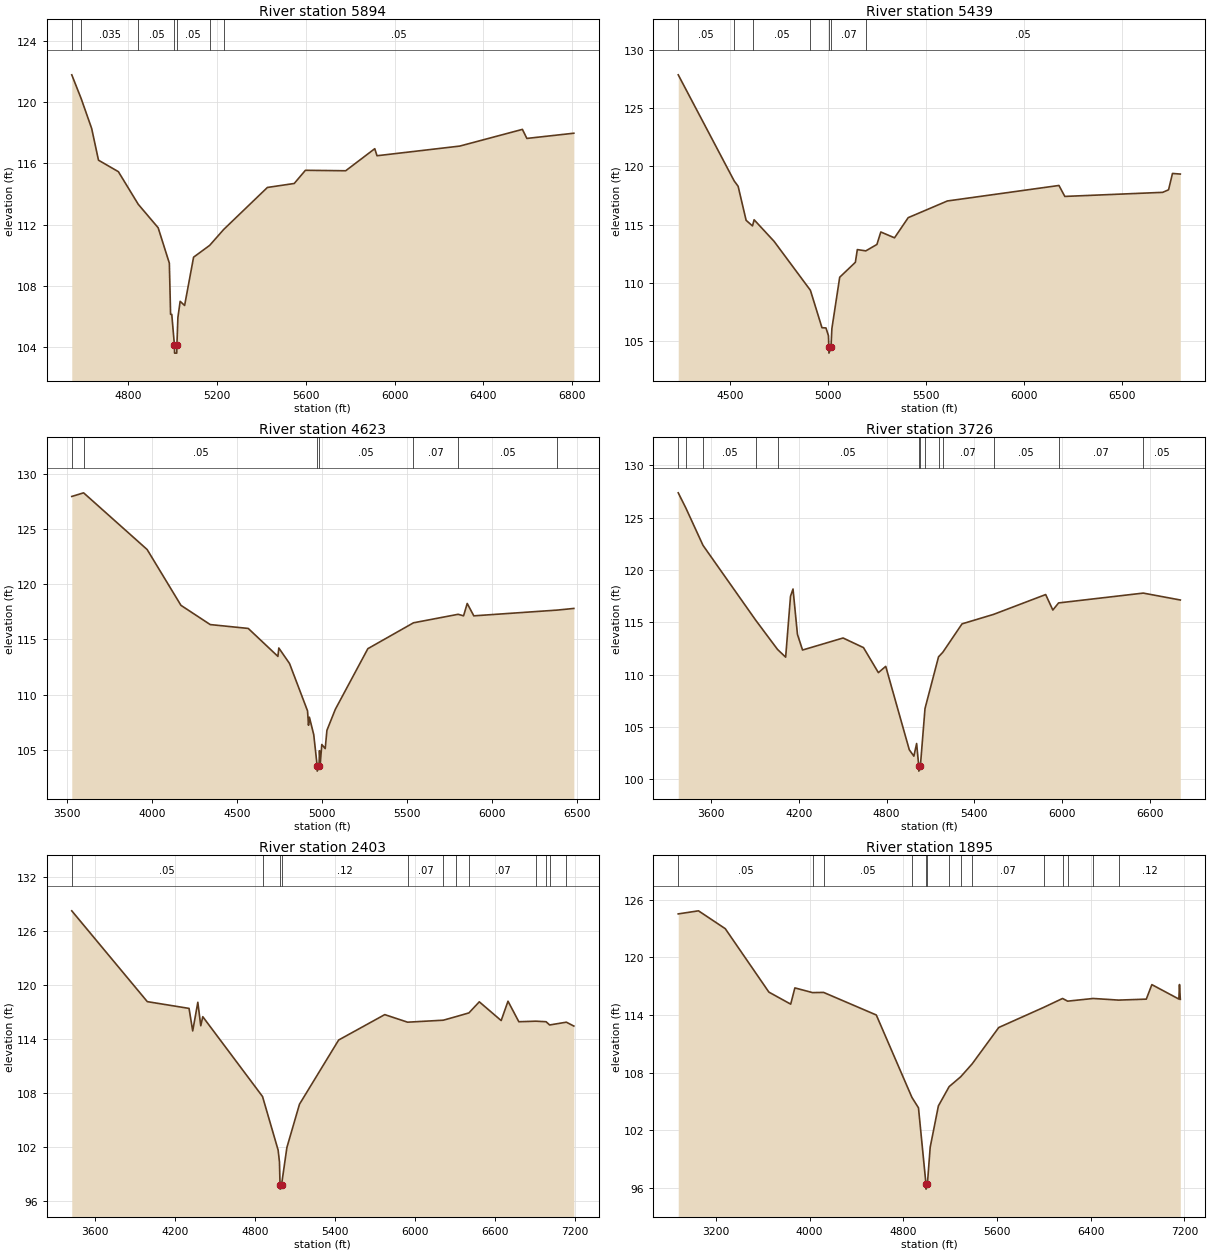
Type RM Length L Ch R = 1 ,5894    ,455,455,455
BEGIN DESCRIPTION:
TRIB 6 TO SPRING CREEK 10.0
END DESCRIPTION:
XS GIS Cut Line= 3
      2593675.04     13517274.98        2593275.       13517475.
      2591475.03       13517275.
#Sta/Elev= 30
  4548.2  121.77  4590.2  120.23  4637.7  118.27  4668.4   116.2  4757.9  115.45
  4847.3  113.32  4936.8  111.79  4987.1  109.48  4992.7  106.14    4998  106.14
  5010.1  104.11  5010.6  103.61  5020.5  103.61    5021  104.11  5025.6  105.94
  5035.7  106.99  5055.8  106.72  5096.1  109.87  5168.4  110.64  5231.6  111.68
  5428.1  114.42  5548.8  114.68  5599.1  115.54  5780.3  115.51  5911.1  116.95
  5921.1  116.49  6293.4  117.12  6575.1  118.21  6595.2  117.62  6806.5  117.96
#Mann= 7 ,-1 , 0
  4548.2     .05       0  4590.2    .035       0  4847.3     .05       0
  5010.1     .05       0    5021     .05       0  5168.4     .07       0
  5231.6     .05       0
Bank Sta=5010.1,5021
XS Rating Curve= 0 ,0
Exp/Cntr=0.3,0.1

Type RM Length L Ch R = 1 ,5439    ,816,816,816
BEGIN DESCRIPTION:
TRIB 6 TO SPRING CREEK 9.0
END DESCRIPTION:
XS GIS Cut Line= 3
      2593875.05     13517225.01        2593125.       13517075.
        2591325.       13517075.
#Sta/Elev= 30
  4234.6  127.86  4520.4  118.76  4540.6   118.3  4581.4  115.38  4614.1   114.9
  4622.2  115.43  4724.2  113.58  4909.8  109.38  4968.9  106.17  4989.3  106.15
    5002  105.49    5004  104.49  5004.5  103.99    5015  104.49  5019.5  106.09
  5059.5   110.5  5139.5  111.78  5149.5  112.87  5192.8  112.76  5249.5  113.31
  5269.5  114.38  5339.5  113.88  5409.5  115.61  5609.5  117.04  6179.5  118.37
  6209.5  117.43  6709.5  117.78  6739.5     118  6759.5   119.4  6799.5  119.35
#Mann= 7 ,-1 , 0
  4234.6     .05       0  4520.4    .035       0  4614.1     .05       0
  4909.8     .07       0    5004     .05       0    5015     .07       0
  5192.8     .05       0
Bank Sta=5004,5015
XS Rating Curve= 0 ,0
Exp/Cntr=0.3,0.1

Type RM Length L Ch R = 1 ,4623    ,897,897,897
BEGIN DESCRIPTION:
Mapping XS 11dc55db
END DESCRIPTION:
XS GIS Cut Line= 3
      2594423.23     13516865.65      2593051.67     13516379.53
      2591559.28     13516535.71
#Sta/Elev= 30
  3526.5  127.94  3596.1  128.27  3970.2  123.14  4169.3  118.09  4341.6  116.35
  4565.4     116  4740.1  113.47  4745.4  114.23  4808.4  112.83  4914.5  108.54
  4920.1  107.24  4925.4  107.97    4951  106.39    4971  103.59  4971.5  103.09
  4982.1  103.59  4984.8  104.94  4989.8  103.82  4998.4   105.5  5018.5  105.13
  5028.6  106.78    5078  108.68  5269.6  114.17  5538.2  116.51  5801.2  117.28
    5833  117.14  5854.5  118.26  5893.3  117.14  6384.1  117.66  6482.2  117.81
#Mann= 7 ,-1 , 0
  3526.5    .035       0  3596.1     .05       0    4971     .05       0
  4982.1     .05       0  5538.2     .07       0  5801.2     .05       0
  6384.1     .07       0
Bank Sta=4971,4982.1
XS Rating Curve= 0 ,0
Exp/Cntr=0.3,0.1

Type RM Length L Ch R = 1 ,3726    ,1323,1323,1323
BEGIN DESCRIPTION:
Mapping XS e9fe5421
END DESCRIPTION:
XS GIS Cut Line= 3
      2595124.89     13515980.95      2593527.65     13515789.98
      2591704.71     13515668.45
#Sta/Elev= 30
  3374.7  127.37  3427.1  125.91  3544.3  122.35  3904.9   115.2    4054  112.41
  4109.8  111.67  4142.9  117.48  4160.1  118.18  4190.4  113.85  4225.3  112.35
  4502.6   113.5  4642.4  112.58  4744.3  110.19  4794.6  110.79  4955.8  102.82
  4987.1  102.21    5006  103.42  5020.4  101.28  5020.9  100.78  5031.7  101.28
  5063.3  106.76  5155.9   111.7  5185.4  112.14  5316.7  114.85  5533.3  115.76
    5889  117.65  5938.1  116.17  5977.3  116.85  6556.8  117.79  6810.3  117.13
#Mann= 13 ,-1 , 0
  3374.7     .05       0  3427.1     .07       0  3544.3     .05       0
  3904.9     .07       0    4054     .05       0  5020.4     .05       0
  5031.7     .05       0  5063.3     .07       0  5155.9     .05       0
  5185.4     .07       0  5533.3     .05       0  5977.3     .07       0
  6556.8     .05       0
Bank Sta=5020.4,5031.7
XS Rating Curve= 0 ,0
Exp/Cntr=0.3,0.1

Type RM Length L Ch R = 1 ,2403    ,508,508,508
BEGIN DESCRIPTION:
Mapping XS bd154008
END DESCRIPTION:
XS GIS Cut Line= 4
      2595194.35     13515373.33      2593979.04     13514730.95
       2593597.1     13514713.59      2591618.96     13515077.98
#Sta/Elev= 30
  3424.4  128.22  3991.4  118.14  4304.6  117.39  4332.2  114.89  4370.6  118.07
  4392.6  115.46  4407.7  116.47  4856.2  107.61  4973.3  101.66  4983.3  100.35
  4987.5   97.83    4988   97.33  4999.1   97.83  5039.2  101.96  5133.4  106.75
  5427.5  113.88  5773.6   116.7  5944.7  115.86  6212.8  116.08  6304.8  116.46
  6405.3  116.89  6483.2  118.12  6647.3  116.04  6698.6  118.19  6779.9  115.91
  6907.7  115.97  6984.4  115.91  7011.3  115.55  7136.4  115.86  7192.8  115.43
#Mann= 12 ,-1 , 0
  3424.4     .05       0  4856.2     .12       0  4987.5     .05       0
  4999.1     .12       0  5944.7     .07       0  6212.8     .05       0
  6304.8     .12       0  6405.3     .07       0  6907.7     .12       0
  6984.4     .05       0  7011.3     .07       0  7136.4     .05       0
Bank Sta=4987.5,4999.1
XS Rating Curve= 0 ,0
Exp/Cntr=0.3,0.1

Type RM Length L Ch R = 1 ,1895    ,897,897,897
BEGIN DESCRIPTION:
Mapping XS 75f48f53
END DESCRIPTION:
XS GIS Cut Line= 4
       2595525.7     13515163.98       2594293.1     13514287.27
      2593138.58     13514278.59      2591645.56     13514903.57
#Sta/Elev= 30
  2878.7  124.53  3051.4  124.85  3280.4  122.99  3652.7  116.39  3838.7  115.14
  3874.3  116.83  4025.3  116.34  4119.5  116.36  4569.4  114.01  4873.3  105.44
  4929.4  104.35  4993.6   96.39  4994.1   95.89  5005.3   96.39  5029.4  100.25
  5099.4  104.55  5191.4  106.56  5289.7  107.58    5388  108.93  5614.8  112.71
  5997.8   114.8  6159.4  115.73  6202.7  115.45  6420.9  115.73  6637.2  115.56
    6874  115.66  6921.6  117.17  7151.9  115.67  7157.4  117.18  7164.4  115.64
#Mann= 14 ,-1 , 0
  2878.7     .05       0  4025.3     .07       0  4119.5     .05       0
  4873.3     .12       0  4993.6     .05       0  5005.3     .12       0
  5191.4     .07       0  5289.7     .12       0    5388     .07       0
  5997.8     .12       0  6159.4     .07       0  6202.7     .12       0
  6420.9     .07       0  6637.2     .12       0
Bank Sta=4993.6,5005.3
XS Rating Curve= 0 ,0
Exp/Cntr=0.3,0.1

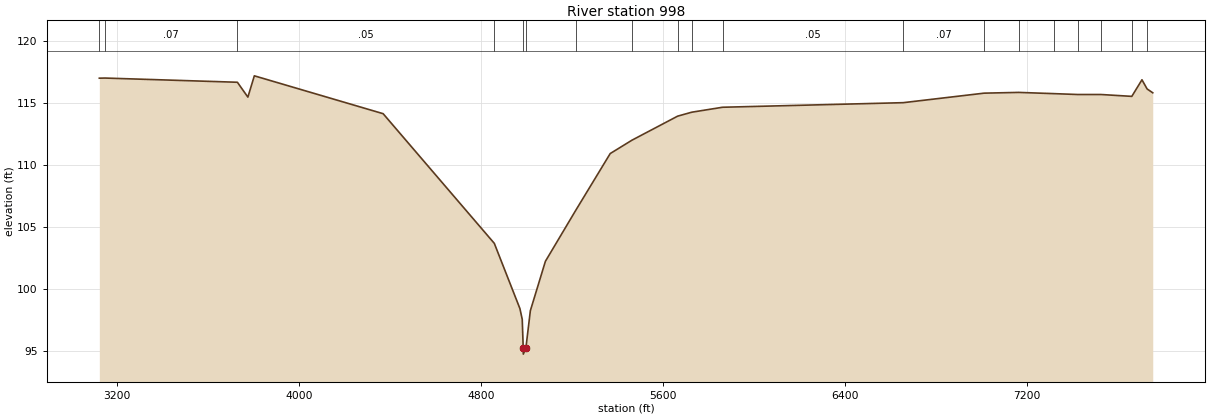
Type RM Length L Ch R = 1 ,998     ,0,0,0
BEGIN DESCRIPTION:
Mapping XS d70643a3
END DESCRIPTION:
XS GIS Cut Line= 4
      2595569.17     13514703.96      2594440.67     13513644.91
       2593711.5     13513506.02      2591706.32      13514712.6
#Sta/Elev= 30
  3122.9  117.03  3147.9  117.04  3729.7   116.7  3775.8   115.5  3804.2  117.22
  4370.3  114.16    4859  103.68  4971.5   98.41  4981.7   97.54    4986   95.23
  4986.5   94.73  4997.8   95.23  5017.4   98.24  5083.5  102.23  5215.9  106.32
  5368.5  110.94  5464.1  112.02  5664.6  113.96  5726.7  114.28  5862.1  114.68
  6656.3  115.05  7012.1  115.82  7163.5  115.88  7318.8  115.78  7424.2  115.71
  7525.6  115.71    7661  115.56  7705.6   116.9  7728.2  116.16    7753  115.85
#Mann= 19 ,-1 , 0
  3122.9     .05       0  3147.9     .07       0  3729.7     .05       0
    4859     .12       0    4986     .05       0  4997.8     .12       0
  5215.9     .05       0  5464.1    .035       0  5664.6     .05       0
  5726.7    .035       0  5862.1     .05       0  6656.3     .07       0
  7012.1     .12       0  7163.5     .07       0  7318.8     .12       0
  7424.2     .07       0  7525.6     .12       0    7661     .07       0
  7728.2     .12       0
Bank Sta=4986,4997.8
XS Rating Curve= 0 ,0
Exp/Cntr=0.3,0.1

Chan Stop Cuts=-1
Use User Specified Reach Order=0
Composite Channel Slope=5