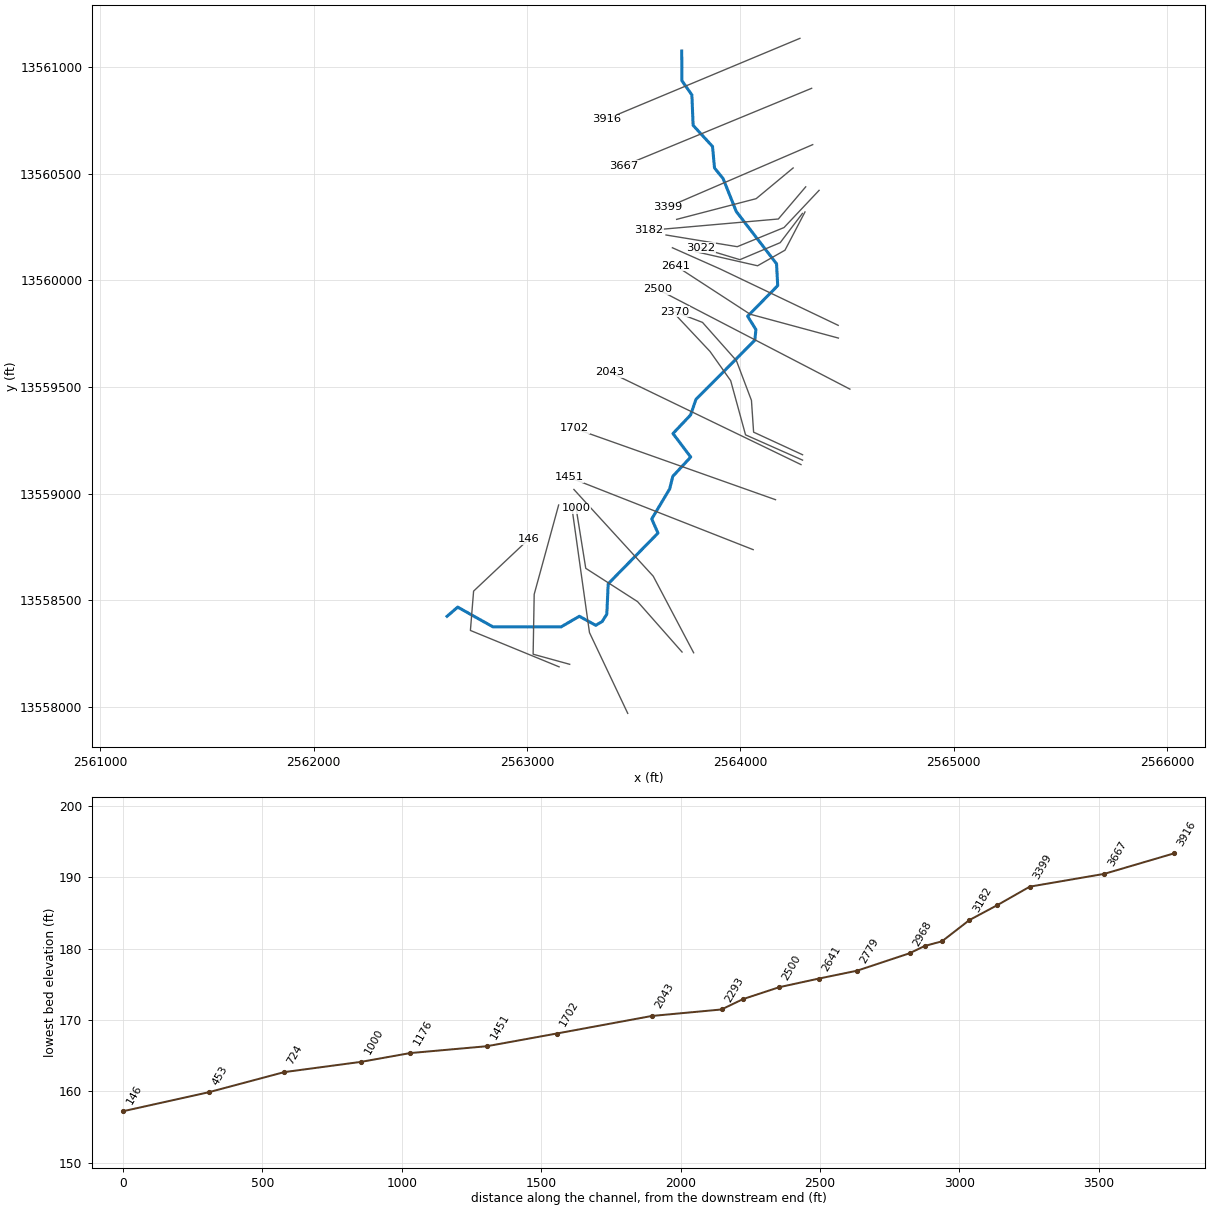
--- TRIB 6_1 TO PRICE CREEK.prj (project) ---

Proj Title=TRIB 6_1 TO PRICE CREEK Base Level Engineering
Current Plan=p01
Default Exp/Contr=0.3,0.1
English Units
Geom File=g01
Flow File=f01
Plan File=p01
BEGIN DESCRIPTION:
TRIB 6_1 TO PRICE CREEK
END DESCRIPTION:

--- TRIB 6_1 TO PRICE CREEK.p01 (plan) ---

Plan Title=Multiple Run
Short Identifier=Multiple
Geom File=g01
Flow File=f01
Subcritical Flow
K Sum by GR= 0
Std Step Tol= 0.01
Critical Tol= 0.01
Num of Std Step Trials= 20
Max Error Tol= 0.3
Flow Tol Ratio= 0.001
Split Flow NTrial= 30
Split Flow Tol= 0.02
Split Flow Ratio= 0.02
Log Output Level= 0
Friction Slope Method= 1
Unsteady Friction Slope Method= 2
Unsteady Bridges Friction Slope Method= 1
Parabolic Critical Depth
Global Vel Dist=  1 , 1 , 1
Global Log Level= 0
CheckData=True
Encroach Param= -1, 0, 0, 0
BEGIN DESCRIPTION:
Multiple Run
END DESCRIPTION:

--- TRIB 6_1 TO PRICE CREEK.f01 (steady flow) ---

Flow Title=Multiple
Number of Profiles=7
Profile Names=10-year,25-year,50-year,1pct_min,100-year,1pct_plu,500-year
River Rch & RM= TRIB 6_1 TO PRIC,Reach-1,3916
     149     216     269     165     328     655     479
River Rch & RM= TRIB 6_1 TO PRIC,Reach-1,2779
     428     668     878     562    1120    2235    1800
Boundary for River Rch & Prof#=TRIB 6_1 TO PRIC,Reach-1,1
Up Type=0
Dn Type=3
Dn Slope=0.005
Boundary for River Rch & Prof#=TRIB 6_1 TO PRIC,Reach-1,2
Up Type=0
Dn Type=3
Dn Slope=0.005
Boundary for River Rch & Prof#=TRIB 6_1 TO PRIC,Reach-1,3
Up Type=0
Dn Type=3
Dn Slope=0.005
Boundary for River Rch & Prof#=TRIB 6_1 TO PRIC,Reach-1,4
Up Type=0
Dn Type=3
Dn Slope=0.005
Boundary for River Rch & Prof#=TRIB 6_1 TO PRIC,Reach-1,5
Up Type=0
Dn Type=3
Dn Slope=0.005
Boundary for River Rch & Prof#=TRIB 6_1 TO PRIC,Reach-1,6
Up Type=0
Dn Type=3
Dn Slope=0.005
Boundary for River Rch & Prof#=TRIB 6_1 TO PRIC,Reach-1,7
Up Type=0
Dn Type=3
Dn Slope=0.005

--- TRIB 6_1 TO PRICE CREEK.g01 (geometry) ---

Geom Title=Existing Conditions

River Reach=TRIB 6_1 TO PRIC,Reach-1
Reach XY= 30
      2563725.00     13561075.00      2563726.17     13560935.48
      2563772.73     13560869.06      2563778.56     13560726.47
      2563869.46     13560627.42      2563878.83     13560526.59
      2563918.88     13560477.18      2563980.85     13560322.71
      2564169.64     13560077.49      2564175.00     13559975.00
      2564034.14     13559831.73      2564073.01     13559768.95
      2564067.50     13559718.95      2563791.65     13559441.67
      2563766.80     13559368.95      2563683.99     13559281.66
      2563767.38     13559171.67      2563683.18     13559081.06
      2563668.90     13559022.81      2563584.59     13558881.55
      2563613.76     13558815.00      2563380.47     13558577.45
      2563373.94     13558435.11      2563352.16     13558400.53
      2563321.98     13558382.83      2563245.21     13558425.21
      2563159.79     13558375.54      2562840.21     13558375.51
      2562674.88     13558468.13      2562625.00     13558425.00

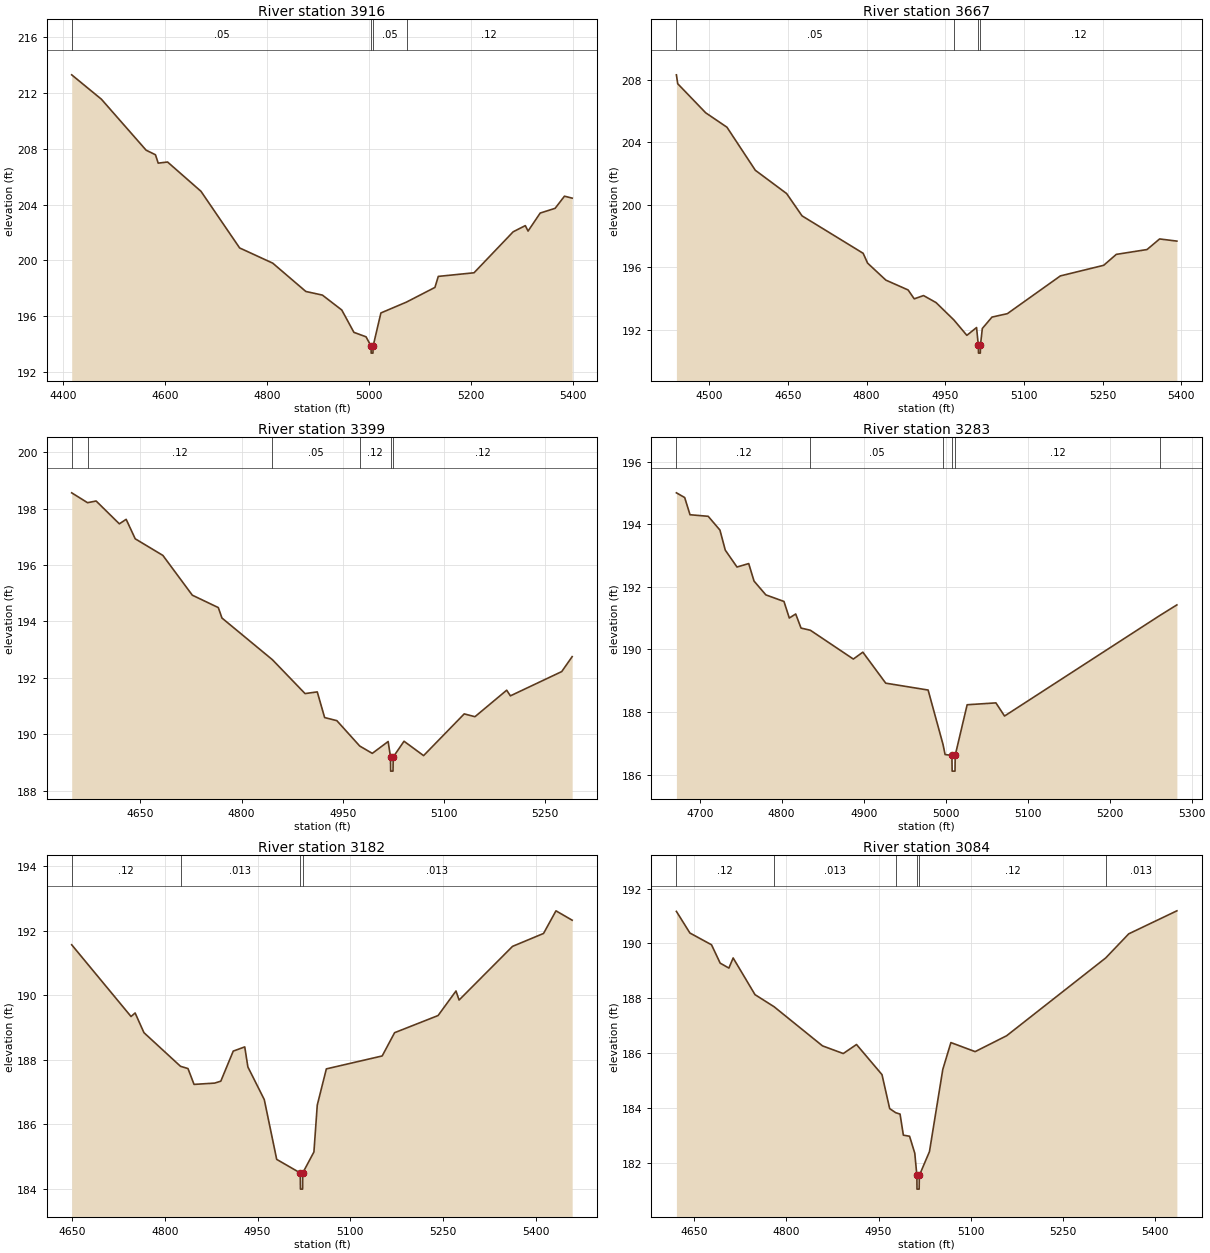
Type RM Length L Ch R = 1,3916,249,249,249
BEGIN DESCRIPTION:
LGII3145
END DESCRIPTION:
XS GIS Cut Line= 2
      2564279.32     13561134.39      2563372.42     13560755.69
#Sta/Elev= 30
  4416.5  213.30  4474.9  211.55  4562.6  207.90  4581.0  207.57  4586.4  206.97
  4604.8  207.05  4670.4  204.95  4746.3  200.89  4811.3  199.80  4876.3  197.77
  4908.8  197.51  4946.9  196.44  4970.7  194.84  4994.5  194.52  5004.4  193.85
  5004.6  193.35  5008.1  193.35  5008.4  193.85  5023.7  196.23  5074.0  197.01
  5129.8  198.06  5136.4  198.85  5206.6  199.11  5283.5  202.05  5307.3  202.49
  5312.7  202.10  5336.5  203.39  5365.8  203.73  5384.2  204.60  5399.3  204.46
#Mann=4,-1,0
  4416.5    0.05       0  5004.4    0.05       0  5008.4    0.05       0
  5074.0    0.12       0
Bank Sta=5004.4,5008.4
Exp/Cntr=0.3,0.1

Type RM Length L Ch R = 1,3667,268,268,268
BEGIN DESCRIPTION:
LGII3144
END DESCRIPTION:
XS GIS Cut Line= 2
      2564334.13     13560900.17      2563452.10     13560536.40
#Sta/Elev= 30
  4437.4  208.33  4439.9  207.76  4493.1  205.90  4533.8  204.97  4587.9  202.21
  4647.5  200.72  4676.9  199.29  4793.4  196.89  4801.9  196.26  4836.7  195.17
  4879.1  194.54  4890.8  193.97  4908.5  194.18  4932.4  193.73  4966.3  192.62
  4991.1  191.63  5009.6  192.13  5013.0  190.99  5013.3  190.49  5016.8  190.49
  5017.0  190.99  5020.6  192.07  5039.0  192.80  5068.3  193.02  5169.4  195.44
  5252.0  196.12  5276.0  196.82  5334.6  197.13  5358.6  197.81  5391.5  197.67
#Mann=4,-1,0
  4437.4    0.05       0  4966.3    0.12       0  5013.0    0.05       0
  5017.0    0.12       0
Bank Sta=5013,5017
Exp/Cntr=0.3,0.1

Type RM Length L Ch R = 1,3399,116,116,116
BEGIN DESCRIPTION:
LGII3143
END DESCRIPTION:
XS GIS Cut Line= 2
      2564339.12     13560636.07      2563658.19     13560342.82
#Sta/Elev= 30
  4548.3  198.56  4571.8  198.21  4584.5  198.27  4618.9  197.46  4629.0  197.62
  4642.4  196.93  4683.4  196.34  4727.0  194.93  4765.5  194.49  4770.9  194.12
  4845.7  192.64  4894.0  191.44  4912.1  191.50  4923.0  190.59  4941.1  190.48
  4975.0  189.58  4993.6  189.32  5017.1  189.74  5020.6  189.19  5020.8  188.69
  5024.3  188.69  5024.6  189.19  5040.6  189.75  5069.6  189.24  5129.8  190.72
  5145.7  190.62  5192.7  191.56  5198.2  191.36  5274.2  192.22  5289.7  192.75
#Mann=6,-1,0
  4548.3    0.05       0  4571.8    0.12       0  4845.7    0.05       0
  4975.0    0.12       0  5020.6    0.05       0  5024.6    0.12       0
Bank Sta=5020.6,5024.6
Exp/Cntr=0.3,0.1

Type RM Length L Ch R = 1,3283,101,101,101
BEGIN DESCRIPTION:
4869
END DESCRIPTION:
XS GIS Cut Line= 3
      2564247.43     13560526.73      2564074.08     13560382.85
      2563701.40     13560285.78
#Sta/Elev= 30
  4671.6  195.00  4681.7  194.85  4688.2  194.30  4710.4  194.25  4724.7  193.81
  4731.2  193.17  4745.5  192.63  4759.8  192.74  4766.3  192.18  4780.7  191.74
  4802.8  191.53  4809.3  191.00  4817.1  191.13  4823.6  190.68  4835.0  190.61
  4887.4  189.69  4899.0  189.91  4926.9  188.92  4978.6  188.70  4996.8  186.96
  4999.3  186.64  5007.6  186.61  5007.9  186.11  5011.4  186.11  5011.6  186.61
  5026.2  188.23  5061.3  188.29  5071.8  187.87  5261.1  191.08  5282.0  191.42
#Mann=6,-1,0
  4671.6    0.12       0  4835.0    0.05       0  4996.8    0.12       0
  5007.6    0.05       0  5011.6    0.12       0  5261.1   0.013       0
Bank Sta=5007.6,5011.6
Exp/Cntr=0.3,0.1

Type RM Length L Ch R = 1,3182,98,98,98
BEGIN DESCRIPTION:
4868
END DESCRIPTION:
XS GIS Cut Line= 3
      2564306.35     13560438.29      2564178.09     13560287.51
      2563568.90     13560233.86
#Sta/Elev= 30
  4649.3  191.56  4745.3  189.34  4751.9  189.45  4766.2  188.84  4825.3  187.80
  4837.4  187.73  4847.2  187.24  4880.5  187.28  4890.5  187.34  4910.6  188.27
  4929.2  188.40  4934.3  187.78  4960.8  186.77  4980.9  184.92  5019.0  184.50
  5019.3  184.00  5022.8  184.00  5023.0  184.50  5041.1  185.15  5046.5  186.60
  5061.2  187.72  5151.5  188.12  5171.6  188.84  5241.9  189.37  5270.9  190.13
  5275.9  189.85  5362.3  191.51  5412.5  191.91  5432.6  192.61  5458.8  192.32
#Mann=4,-1,0
  4649.3    0.12       0  4825.3   0.013       0  5019.0    0.03       0
  5023.0   0.013       0
Bank Sta=5019,5023
Exp/Cntr=0.3,0.1

Type RM Length L Ch R = 1,3084,62,62,62
BEGIN DESCRIPTION:
LGII3142
END DESCRIPTION:
XS GIS Cut Line= 4
      2564369.04     13560421.79      2564204.61     13560247.38
      2563985.34     13560157.68      2563651.42     13560212.51
#Sta/Elev= 30
  4620.8  191.17  4642.8  190.38  4678.0  189.95  4692.1  189.28  4706.3  189.10
  4713.2  189.47  4748.8  188.13  4779.8  187.69  4858.7  186.26  4892.5  185.98
  4914.1  186.31  4955.6  185.21  4968.1  183.97  4977.9  183.82  4985.0  183.77
  4990.4  183.00  5000.5  182.96  5009.0  182.34  5012.4  181.53  5012.6  181.03
  5016.1  181.03  5016.4  181.53  5032.9  182.40  5054.6  185.40  5067.8  186.38
  5107.3  186.05  5158.6  186.63  5319.9  189.47  5357.4  190.35  5435.8  191.19
#Mann=6,-1,0
  4620.8    0.12       0  4779.8   0.013       0  4977.9    0.12       0
  5012.4    0.05       0  5016.4    0.12       0  5319.9   0.013       0
Bank Sta=5012.4,5016.4
Exp/Cntr=0.3,0.1

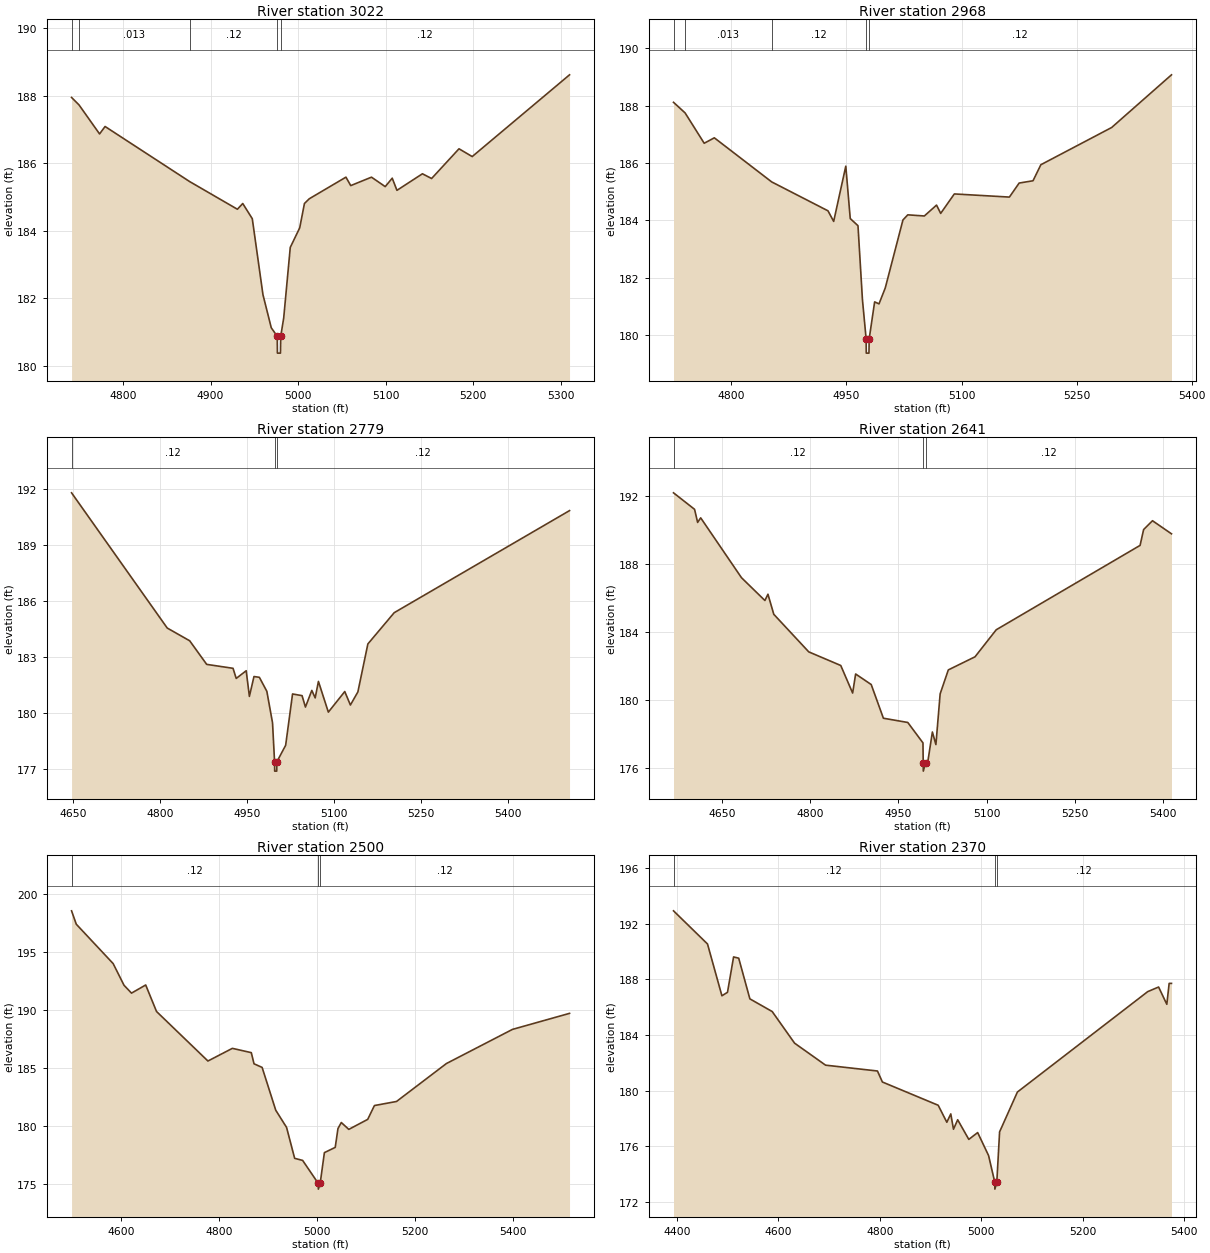
Type RM Length L Ch R = 1,3022,54,54,54
BEGIN DESCRIPTION:
4867
END DESCRIPTION:
XS GIS Cut Line= 4
      2564290.80     13560313.54      2564186.76     13560176.56
      2563997.81     13560096.82      2563814.10     13560152.28
#Sta/Elev= 30
  4741.2  187.95  4749.7  187.73  4773.2  186.87  4779.5  187.09  4876.1  185.46
  4930.7  184.64  4936.8  184.81  4947.7  184.36  4959.9  182.11  4969.4  181.13
  4976.2  180.88  4976.4  180.38  4979.9  180.38  4980.2  180.88  4983.6  181.42
  4991.1  183.51  5001.9  184.09  5007.3  184.81  5012.8  184.95  5054.7  185.59
  5060.2  185.34  5083.9  185.59  5099.6  185.31  5107.6  185.56  5113.0  185.20
  5142.1  185.69  5152.6  185.55  5183.9  186.43  5199.0  186.20  5310.2  188.62
#Mann=5,-1,0
  4741.2    0.12       0  4749.7   0.013       0  4876.1    0.12       0
  4976.2    0.05       0  4980.2    0.12       0
Bank Sta=4976.2,4980.2
Exp/Cntr=0.3,0.1

Type RM Length L Ch R = 1,2968,189,189,189
BEGIN DESCRIPTION:
4866
END DESCRIPTION:
XS GIS Cut Line= 4
      2564302.91     13560320.46      2564209.13     13560141.18
      2564080.66     13560068.26      2563788.99     13560134.74
#Sta/Elev= 30
  4724.5  188.12  4739.6  187.75  4764.5  186.69  4777.7  186.88  4852.5  185.34
  4925.9  184.33  4933.3  183.96  4949.1  185.89  4954.9  184.06  4965.0  183.81
  4970.8  181.23  4975.6  179.86  4975.8  179.36  4979.3  179.36  4979.6  179.86
  4986.7  181.15  4992.4  181.08  5000.6  181.64  5023.6  184.01  5029.9  184.19
  5051.5  184.15  5067.4  184.53  5072.8  184.24  5090.6  184.92  5162.4  184.81
  5175.1  185.30  5193.2  185.38  5203.4  185.94  5295.7  187.24  5373.7  189.08
#Mann=5,-1,0
  4724.5    0.12       0  4739.6   0.013       0  4852.5    0.12       0
  4975.6    0.05       0  4979.6    0.12       0
Bank Sta=4975.6,4979.6
Exp/Cntr=0.3,0.1

Type RM Length L Ch R = 1,2779,138,138,138
BEGIN DESCRIPTION:
LGII3141
END DESCRIPTION:
XS GIS Cut Line= 3
      2564458.72     13559788.94      2563905.61     13560053.04
      2563681.39     13560152.69
#Sta/Elev= 30
  4647.6  191.77  4812.5  184.55  4851.2  183.87  4880.5  182.61  4925.9  182.40
  4931.4  181.86  4948.6  182.27  4954.1  180.90  4962.0  181.96  4971.3  181.92
  4984.2  181.17  4994.0  179.49  4997.5  177.41  4997.7  176.91  5001.2  176.91
  5001.5  177.41  5016.6  178.29  5028.5  181.03  5044.9  180.94  5050.7  180.33
  5061.7  181.22  5067.5  180.82  5073.1  181.70  5090.2  180.06  5118.5  181.16
  5128.2  180.44  5141.1  181.14  5158.3  183.70  5203.7  185.37  5505.9  190.82
#Mann=3,-1,0
  4647.6    0.12       0  4997.5    0.05       0  5001.5    0.12       0
Bank Sta=4997.5,5001.5
Exp/Cntr=0.3,0.1

Type RM Length L Ch R = 1,2641,141,141,141
BEGIN DESCRIPTION:
Mapping XS 3af40791
END DESCRIPTION:
XS GIS Cut Line= 3
      2564459.56     13559729.29      2564045.50     13559841.26
      2563695.23     13560069.14
#Sta/Elev= 30
  4567.6  192.16  4603.4  191.19  4608.6  190.42  4613.8  190.69  4683.2  187.17
  4723.0  185.83  4728.2  186.20  4738.1  185.02  4797.6  182.81  4852.0  182.01
  4872.2  180.39  4877.3  181.51  4903.8  180.89  4924.5  178.91  4966.0  178.66
  4991.8  177.46  4992.2  176.30  4992.4  175.80  4996.2  176.30  4999.8  176.30
  5007.8  178.10  5013.8  177.36  5021.0  180.34  5034.9  181.75  5080.3  182.52
  5116.4  184.11  5361.0  189.07  5367.0  190.00  5382.1  190.52  5414.4  189.75
#Mann=3,-1,0
  4567.6    0.12       0  4992.2    0.05       0  4996.2    0.12       0
Bank Sta=4992.2,4996.2
Exp/Cntr=0.3,0.1

Type RM Length L Ch R = 1,2500,130,130,130
BEGIN DESCRIPTION:
LGII3140
END DESCRIPTION:
XS GIS Cut Line= 2
      2564513.55     13559489.94      2563611.63     13559958.34
#Sta/Elev= 30
  4498.8  198.54  4508.4  197.39  4583.7  194.00  4605.8  192.14  4621.1  191.46
  4650.1  192.16  4672.2  189.88  4777.1  185.62  4827.0  186.71  4865.6  186.34
  4871.2  185.38  4887.7  185.07  4915.5  181.39  4937.6  179.91  4954.1  177.25
  4970.4  177.07  5002.2  175.10  5002.5  174.60  5006.2  175.10  5014.8  177.74
  5036.9  178.19  5042.5  179.81  5049.3  180.33  5064.6  179.74  5103.2  180.60
  5116.9  181.79  5162.0  182.14  5263.7  185.40  5398.6  188.34  5515.1  189.72
#Mann=3,-1,0
  4498.8    0.12       0  5002.2    0.05       0  5006.2    0.12       0
Bank Sta=5002.2,5006.2
Exp/Cntr=0.3,0.1

Type RM Length L Ch R = 1,2370,77,77,77
BEGIN DESCRIPTION:
4870
END DESCRIPTION:
XS GIS Cut Line= 6
      2564291.63     13559182.33      2564062.08     13559288.27
      2564051.99     13559437.08      2563981.37     13559623.73
      2563822.47     13559802.80      2563691.28     13559853.26
#Sta/Elev= 30
  4393.1  192.91  4460.1  190.53  4488.5  186.81  4499.5  187.06  4511.5  189.60
  4521.6  189.51  4543.6  186.59  4587.6  185.68  4631.7  183.41  4692.8  181.83
  4795.1  181.41  4804.8  180.62  4914.8  178.95  4931.8  177.73  4939.6  178.33
  4944.9  177.23  4953.2  177.91  4975.1  176.50  4992.6  176.99  5014.1  175.34
  5026.3  173.43  5026.5  172.93  5030.3  173.43  5035.8  177.04  5070.9  179.90
  5327.8  187.11  5349.2  187.44  5365.4  186.20  5370.0  187.70  5374.6  187.70
#Mann=3,-1,0
  4393.1    0.12       0  5026.3    0.05       0  5030.3    0.12       0
Bank Sta=5026.3,5030.3
Exp/Cntr=0.3,0.1

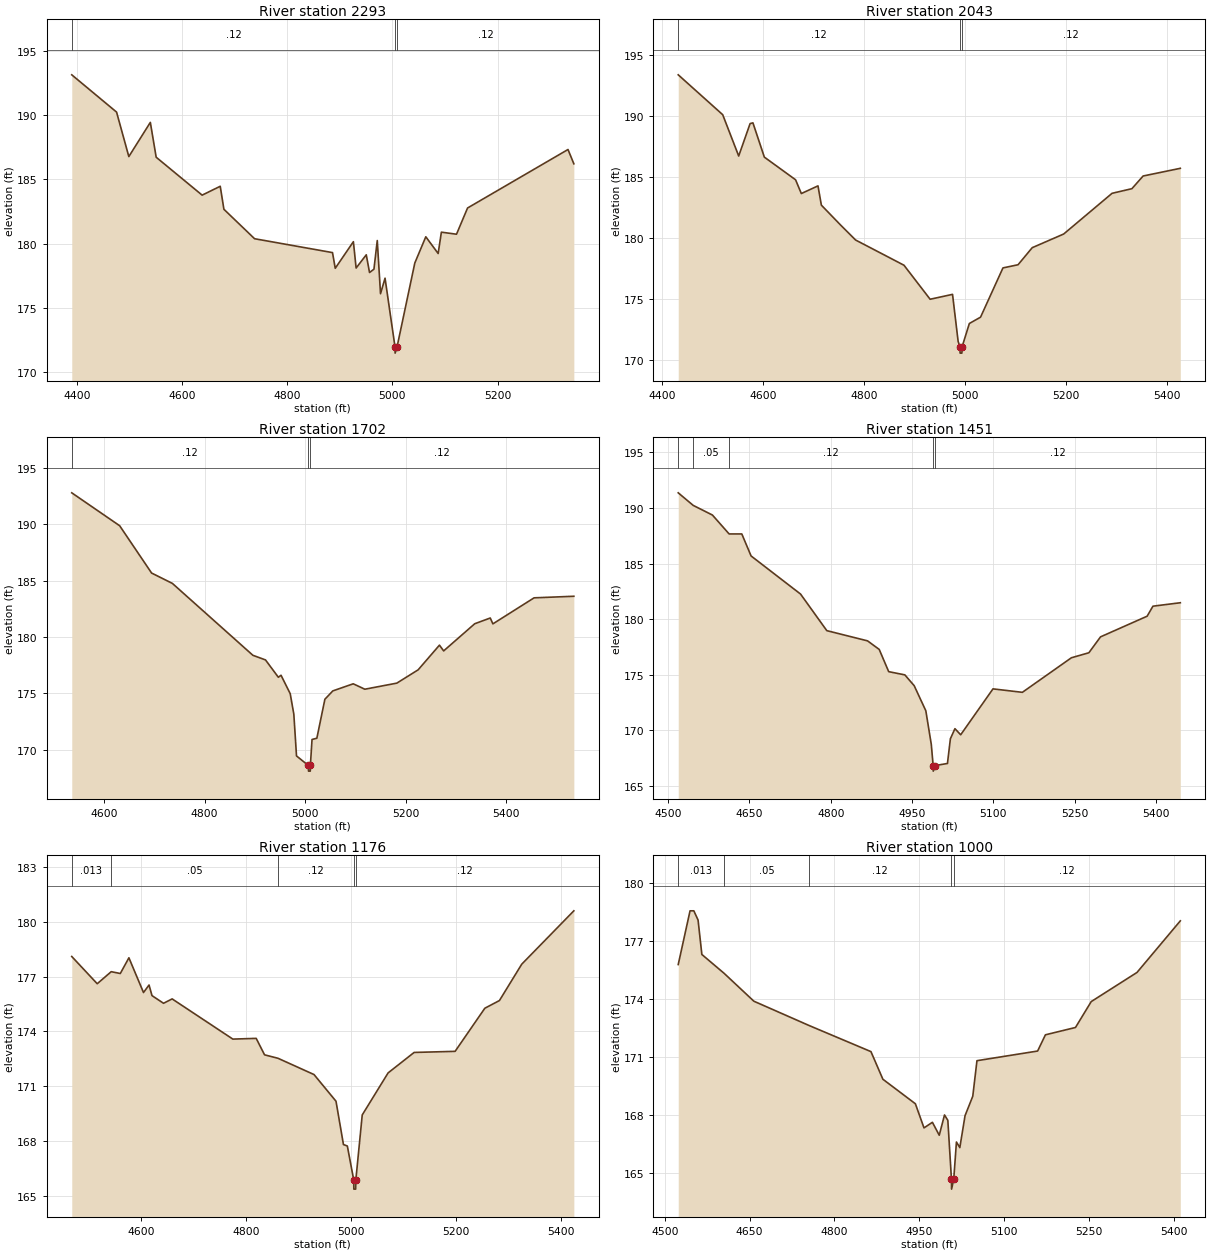
Type RM Length L Ch R = 1,2293,250,250,250
BEGIN DESCRIPTION:
LGII3139
END DESCRIPTION:
XS GIS Cut Line= 5
      2564291.60     13559157.11      2564024.25     13559275.66
      2563954.66     13559529.56      2563857.78     13559666.60
      2563699.44     13559835.00
#Sta/Elev= 30
  4390.4  193.13  4475.6  190.23  4498.9  186.77  4539.8  189.43  4550.9  186.72
  4638.3  183.77  4672.7  184.46  4679.7  182.67  4738.0  180.38  4886.2  179.30
  4891.4  178.08  4925.9  180.15  4931.1  178.10  4950.4  179.13  4956.6  177.75
  4965.0  178.01  4971.3  180.24  4977.5  176.10  4986.1  177.31  5005.0  171.98
  5005.3  171.48  5009.0  171.98  5042.7  178.49  5063.6  180.53  5087.1  179.23
  5093.2  180.89  5122.0  180.73  5143.0  182.77  5334.0  187.32  5345.1  186.21
#Mann=3,-1,0
  4390.4    0.12       0  5005.0    0.05       0  5009.0    0.12       0
Bank Sta=5005,5009
Exp/Cntr=0.3,0.1

Type RM Length L Ch R = 1,2043,341,341,341
BEGIN DESCRIPTION:
LGII3138
END DESCRIPTION:
XS GIS Cut Line= 2
      2564284.33     13559136.12      2563388.66     13559569.02
#Sta/Elev= 30
  4432.0  193.40  4520.1  190.13  4551.8  186.74  4574.4  189.40  4580.0  189.46
  4602.6  186.65  4664.5  184.79  4675.9  183.66  4708.9  184.29  4715.6  182.71
  4753.4  181.09  4783.4  179.85  4879.3  177.78  4931.1  174.99  4975.5  175.39
  4986.6  171.53  4990.3  171.07  4990.5  170.57  4994.0  170.57  4994.3  171.07
  5008.8  173.00  5031.0  173.52  5075.4  177.56  5105.3  177.82  5133.4  179.22
  5195.7  180.34  5291.6  183.68  5330.9  184.06  5353.1  185.10  5426.8  185.73
#Mann=3,-1,0
  4432.0    0.12       0  4990.3    0.05       0  4994.3    0.12       0
Bank Sta=4990.3,4994.3
Exp/Cntr=0.3,0.1

Type RM Length L Ch R = 1,1702,251,251,251
BEGIN DESCRIPTION:
LGII3137
END DESCRIPTION:
XS GIS Cut Line= 2
      2564164.78     13558971.65      2563222.91     13559305.54
#Sta/Elev= 30
  4535.6  192.81  4630.9  189.89  4694.5  185.69  4735.9  184.77  4896.1  178.39
  4921.2  177.98  4946.8  176.44  4952.1  176.62  4970.4  174.98  4977.6  173.16
  4982.9  169.46  5006.5  168.61  5006.8  168.11  5010.3  168.11  5010.5  168.61
  5013.8  170.92  5023.4  171.03  5039.4  174.49  5055.2  175.23  5095.8  175.86
  5118.9  175.38  5182.6  175.92  5225.0  177.10  5267.4  179.29  5275.8  178.78
  5337.6  181.19  5368.5  181.70  5373.8  181.18  5455.8  183.49  5534.9  183.63
#Mann=3,-1,0
  4535.6    0.12       0  5006.5    0.05       0  5010.5    0.12       0
Bank Sta=5006.5,5010.5
Exp/Cntr=0.3,0.1

Type RM Length L Ch R = 1,1451,275,275,275
BEGIN DESCRIPTION:
LGII3136
END DESCRIPTION:
XS GIS Cut Line= 2
      2564060.09     13558737.45      2563198.00     13559076.31
#Sta/Elev= 30
  4518.6  191.37  4546.2  190.24  4581.7  189.37  4612.5  187.67  4635.9  187.67
  4653.0  185.69  4744.3  182.26  4792.7  178.97  4867.9  178.05  4889.4  177.28
  4906.9  175.28  4936.7  174.99  4953.9  174.02  4975.4  171.76  4985.5  168.73
  4988.9  166.83  4989.1  166.33  4992.9  166.83  5015.3  167.02  5020.7  169.24
  5029.1  170.15  5039.7  169.60  5099.3  173.73  5153.5  173.42  5244.0  176.53
  5276.2  176.98  5297.7  178.41  5383.7  180.27  5394.4  181.17  5444.9  181.48
#Mann=5,-1,0
  4518.6    0.12       0  4546.2    0.05       0  4612.5    0.12       0
  4988.9    0.05       0  4992.9    0.12       0
Bank Sta=4988.9,4992.9
Exp/Cntr=0.3,0.1

Type RM Length L Ch R = 1,1176,176,176,176
BEGIN DESCRIPTION:
LGII3135
END DESCRIPTION:
XS GIS Cut Line= 3
      2563781.01     13558254.10      2563591.66     13558612.87
      2563219.63     13559019.62
#Sta/Elev= 30
  4467.8  178.10  4516.3  176.61  4543.0  177.27  4560.3  177.17  4576.7  178.03
  4604.5  176.13  4615.1  176.54  4620.7  175.96  4642.7  175.54  4659.1  175.78
  4774.8  173.58  4819.3  173.62  4835.2  172.72  4860.9  172.53  4929.5  171.64
  4971.4  170.18  4985.6  167.81  4993.0  167.73  5005.2  165.87  5005.4  165.37
  5008.9  165.37  5009.2  165.87  5021.4  169.43  5070.7  171.73  5120.3  172.85
  5198.4  172.91  5255.1  175.27  5282.9  175.69  5325.4  177.68  5424.7  180.60
#Mann=5,-1,0
  4467.8   0.013       0  4543.0    0.05       0  4860.9    0.12       0
  5005.2    0.05       0  5009.2    0.12       0
Bank Sta=5005.2,5009.2
Exp/Cntr=0.3,0.1

Type RM Length L Ch R = 1,1000,276,276,276
BEGIN DESCRIPTION:
4871
END DESCRIPTION:
XS GIS Cut Line= 4
      2563726.67     13558257.57      2563518.31     13558493.71
      2563275.26     13558649.96      2563230.21     13558930.60
#Sta/Elev= 30
  4523.8  175.77  4544.7  178.55  4551.4  178.55  4558.9  178.07  4565.6  176.29
  4605.1  175.31  4657.6  173.87  4755.4  172.61  4864.7  171.26  4885.8  169.83
  4943.3  168.56  4958.5  167.31  4973.4  167.60  4985.5  166.93  4994.8  167.98
  5000.7  167.70  5007.1  164.64  5007.3  164.14  5011.1  164.64  5015.9  166.58
  5021.9  166.29  5031.1  167.94  5044.8  168.95  5052.2  170.79  5159.5  171.29
  5173.3  172.13  5226.5  172.51  5254.3  173.85  5335.3  175.36  5411.9  178.03
#Mann=5,-1,0
  4523.8   0.013       0  4605.1    0.05       0  4755.4    0.12       0
  5007.1    0.05       0  5011.1    0.12       0
Bank Sta=5007.1,5011.1
Exp/Cntr=0.3,0.1

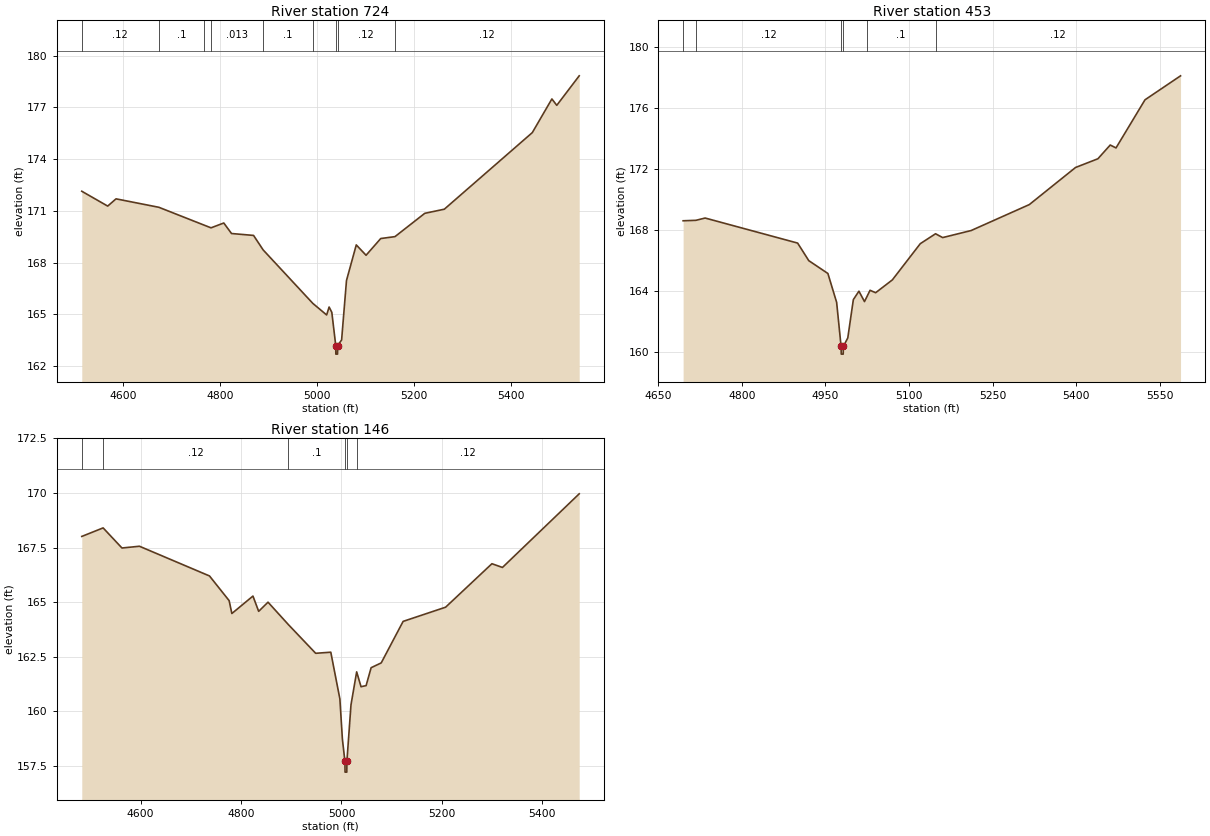
Type RM Length L Ch R = 1,724,271,271,271
BEGIN DESCRIPTION:
LGII3134
END DESCRIPTION:
XS GIS Cut Line= 3
      2563472.08     13557969.99      2563292.67     13558348.75
      2563208.07     13558950.84
#Sta/Elev= 30
  4513.9  172.14  4567.4  171.28  4584.6  171.70  4673.1  171.21  4767.1  170.17
  4780.8  170.02  4807.1  170.30  4823.1  169.69  4868.6  169.58  4888.4  168.74
  4991.0  165.64  5019.5  164.97  5024.6  165.43  5030.2  165.12  5038.3  163.20
  5038.5  162.70  5042.0  162.70  5042.3  163.20  5050.4  163.52  5060.5  166.97
  5080.7  169.03  5100.9  168.43  5131.2  169.40  5160.6  169.51  5222.1  170.86
  5262.5  171.10  5444.2  175.54  5484.6  177.49  5494.7  177.12  5541.0  178.83
#Mann=9,-1,0
  4513.9    0.12       0  4673.1     0.1       0  4767.1    0.12       0
  4780.8   0.013       0  4888.4     0.1       0  4991.0    0.12       0
  5038.3    0.05       0  5042.3    0.12       0  5160.6    0.12       0
Bank Sta=5038.3,5042.3
Exp/Cntr=0.3,0.1

Type RM Length L Ch R = 1,453,307,307,307
BEGIN DESCRIPTION:
LGII3133
END DESCRIPTION:
XS GIS Cut Line= 4
      2563199.98     13558200.00      2563028.56     13558247.31
      2563033.53     13558528.15      2563148.15     13558946.73
#Sta/Elev= 30
  4694.5  168.61  4717.5  168.64  4734.0  168.79  4900.0  167.15  4920.0  166.00
  4954.3  165.16  4970.0  163.27  4978.0  160.38  4978.3  159.88  4981.8  159.88
  4982.0  160.38  4990.0  160.94  5000.0  163.45  5010.0  164.00  5020.0  163.32
  5024.2  163.63  5030.0  164.06  5040.0  163.90  5070.0  164.74  5120.1  167.11
  5147.5  167.76  5160.3  167.51  5211.3  167.97  5315.8  169.67  5398.8  172.10
  5438.9  172.67  5461.0  173.57  5471.4  173.38  5523.4  176.53  5587.2  178.10
#Mann=6,-1,0
  4694.5   0.013       0  4717.5    0.12       0  4978.0    0.05       0
  4982.0    0.12       0  5024.2     0.1       0  5147.5    0.12       0
Bank Sta=4978,4982
Exp/Cntr=0.3,0.1

Type RM Length L Ch R = 1,146,0,0,0
BEGIN DESCRIPTION:
LGII3132
END DESCRIPTION:
XS GIS Cut Line= 4
      2563150.30     13558188.14      2562734.54     13558358.72
      2562749.49     13558543.10      2563008.59     13558787.26
#Sta/Elev= 30
  4483.0  168.01  4525.5  168.40  4563.0  167.48  4597.8  167.56  4737.3  166.20
  4776.4  165.07  4781.8  164.48  4823.8  165.28  4835.2  164.58  4853.8  165.00
  4894.5  163.97  4948.7  162.66  4978.8  162.71  4996.9  160.57  5001.9  158.73
  5006.9  157.72  5007.2  157.22  5010.7  157.22  5010.9  157.72  5019.0  160.30
  5030.3  161.81  5039.0  161.13  5049.1  161.18  5059.1  162.00  5079.2  162.22
  5122.8  164.12  5207.4  164.77  5299.6  166.76  5320.6  166.59  5473.4  169.96
#Mann=6,-1,0
  4483.0   0.013       0  4525.5    0.12       0  4894.5     0.1       0
  5006.9    0.05       0  5010.9     0.1       0  5030.3    0.12       0
Bank Sta=5006.9,5010.9
Exp/Cntr=0.3,0.1

Chan Stop Cuts=-1