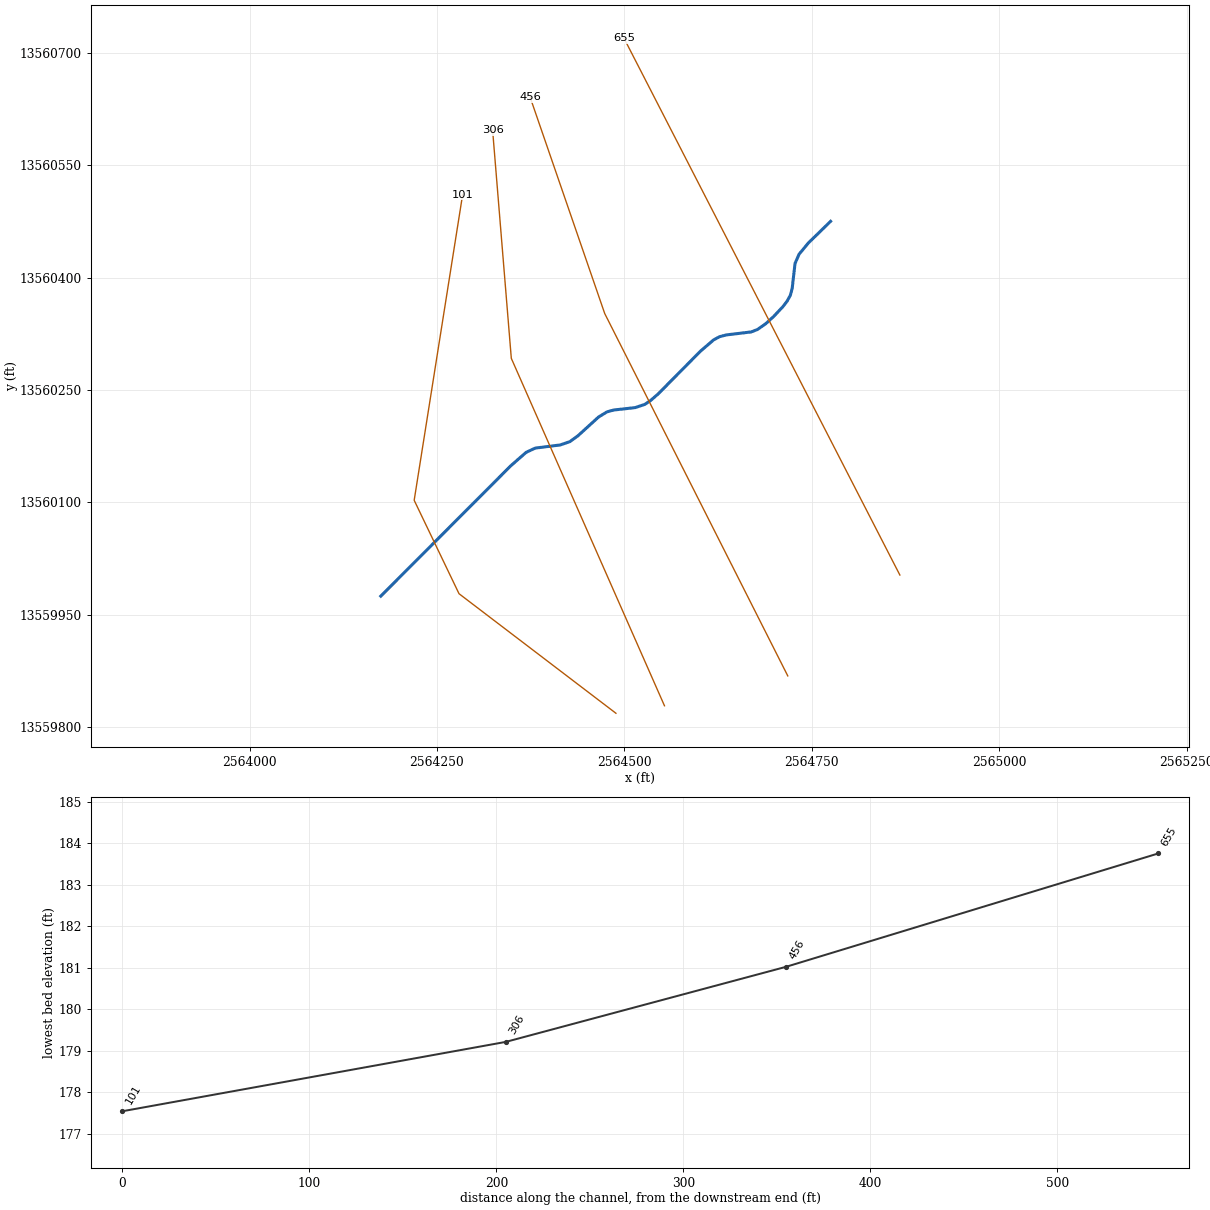
--- TRIB 6_1_1 TO PRICE CREEK.prj (project) ---

Proj Title=TRIB 6_1_1 TO PRICE CREEK Base Level Engineering
Current Plan=p01
Default Exp/Contr=0.3,0.1
English Units
Geom File=g01
Flow File=f01
Plan File=p01
BEGIN DESCRIPTION:
TRIB 6_1_1 TO PRICE CREEK
END DESCRIPTION:

--- TRIB 6_1_1 TO PRICE CREEK.p01 (plan) ---

Plan Title=Multiple Run
Short Identifier=Multiple
Geom File=g01
Flow File=f01
Subcritical Flow
K Sum by GR= 0
Std Step Tol= 0.01
Critical Tol= 0.01
Num of Std Step Trials= 20
Max Error Tol= 0.3
Flow Tol Ratio= 0.001
Split Flow NTrial= 30
Split Flow Tol= 0.02
Split Flow Ratio= 0.02
Log Output Level= 0
Friction Slope Method= 1
Unsteady Friction Slope Method= 2
Unsteady Bridges Friction Slope Method= 1
Parabolic Critical Depth
Global Vel Dist=  1 , 1 , 1
Global Log Level= 0
CheckData=True
Encroach Param= -1, 0, 0, 0
BEGIN DESCRIPTION:
Multiple Run
END DESCRIPTION:

--- TRIB 6_1_1 TO PRICE CREEK.f01 (steady flow) ---

Flow Title=Multiple
Number of Profiles=7
Profile Names=10-year,25-year,50-year,1pct_min,100-year,1pct_plu,500-year
River Rch & RM= TRIB 6_1_1 TO PR,Reach-1,655
     257     388     499     313     624    1245     961
Boundary for River Rch & Prof#=TRIB 6_1_1 TO PR,Reach-1,1
Up Type=0
Dn Type=3
Dn Slope=0.005
Boundary for River Rch & Prof#=TRIB 6_1_1 TO PR,Reach-1,2
Up Type=0
Dn Type=3
Dn Slope=0.005
Boundary for River Rch & Prof#=TRIB 6_1_1 TO PR,Reach-1,3
Up Type=0
Dn Type=3
Dn Slope=0.005
Boundary for River Rch & Prof#=TRIB 6_1_1 TO PR,Reach-1,4
Up Type=0
Dn Type=3
Dn Slope=0.005
Boundary for River Rch & Prof#=TRIB 6_1_1 TO PR,Reach-1,5
Up Type=0
Dn Type=3
Dn Slope=0.005
Boundary for River Rch & Prof#=TRIB 6_1_1 TO PR,Reach-1,6
Up Type=0
Dn Type=3
Dn Slope=0.005
Boundary for River Rch & Prof#=TRIB 6_1_1 TO PR,Reach-1,7
Up Type=0
Dn Type=3
Dn Slope=0.005

--- TRIB 6_1_1 TO PRICE CREEK.g01 (geometry) ---

Geom Title=Existing Conditions

River Reach=TRIB 6_1_1 TO PR,Reach-1
Reach XY= 30
      2564775.00     13560475.00      2564745.16     13560445.90
      2564732.95     13560431.11      2564727.58     13560418.89
      2564723.75     13560385.38      2564721.29     13560376.34
      2564717.07     13560368.60      2564711.58     13560361.40
      2564698.86     13560347.84      2564688.57     13560338.47
      2564677.54     13560330.75      2564669.13     13560327.46
      2564635.69     13560323.43      2564626.68     13560321.00
      2564618.98     13560316.82      2564601.56     13560301.93
      2564545.07     13560244.82      2564534.67     13560235.79
      2564527.29     13560230.85      2564514.37     13560226.51
      2564485.70     13560223.30      2564476.73     13560220.81
      2564465.45     13560213.90      2564438.06     13560188.98
      2564427.19     13560181.10      2564414.30     13560176.70
      2564381.03     13560172.50      2564368.94     13560166.86
      2564348.18     13560148.71      2564175.00     13559975.00

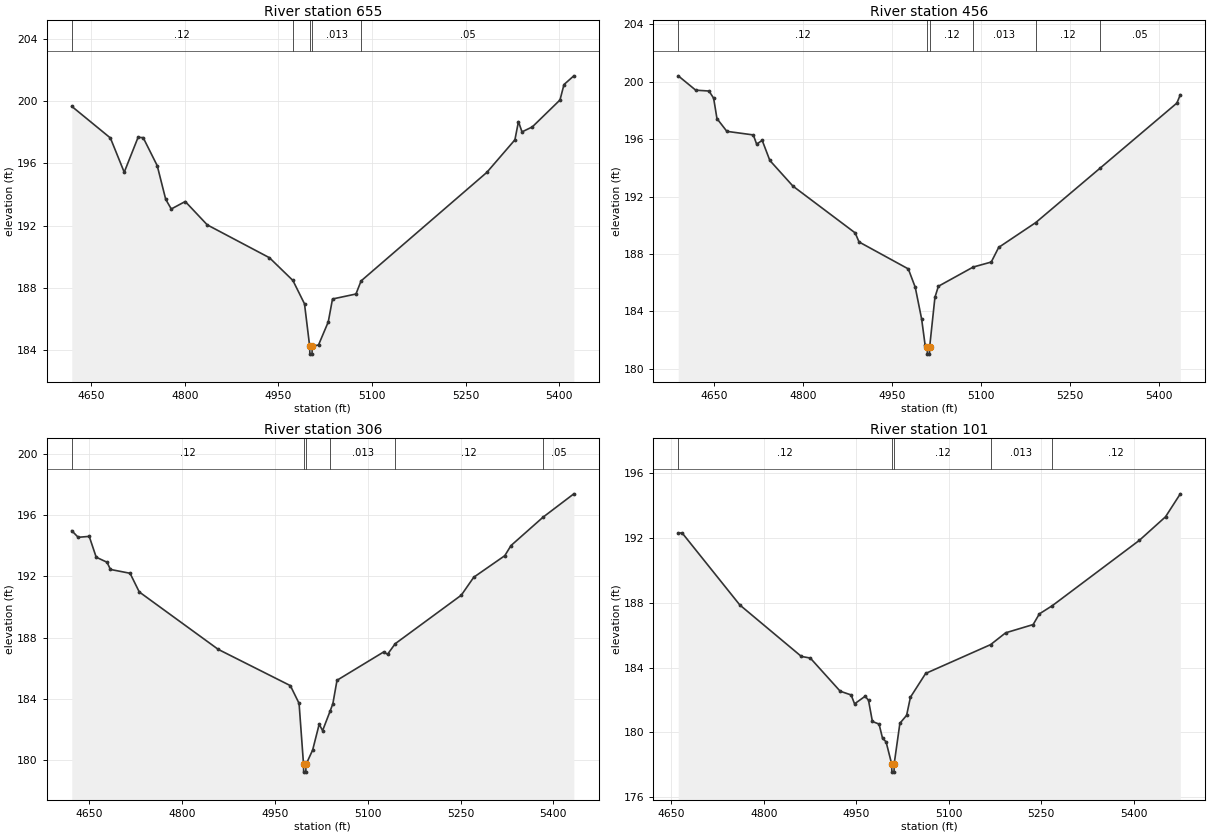
Type RM Length L Ch R = 1,655,199,199,199
BEGIN DESCRIPTION:
LGII3149
END DESCRIPTION:
XS GIS Cut Line= 2
      2564867.40     13560003.17      2564499.50     13560719.08
#Sta/Elev= 30
  4618.6  199.66  4680.5  197.63  4702.7  195.43  4724.9  197.67  4733.1  197.65
  4755.6  195.85  4769.2  193.69  4778.1  193.07  4800.5  193.55  4835.8  192.05
  4935.5  189.94  4973.1  188.48  4991.7  186.98  5000.0  184.25  5000.3  183.75
  5003.8  183.75  5004.0  184.25  5014.2  184.34  5029.8  185.82  5036.6  187.29
  5074.2  187.61  5082.4  188.45  5284.0  195.42  5329.0  197.51  5334.7  198.68
  5340.4  198.02  5356.9  198.34  5401.3  200.07  5407.7  201.06  5423.5  201.62
#Mann=5,-1,0
  4618.6    0.12       0  4973.1   0.013       0  5000.0    0.03       0
  5004.0   0.013       0  5082.4    0.05       0
Bank Sta=5000,5004
Exp/Cntr=0.3,0.1

Type RM Length L Ch R = 1,456,150,150,150
BEGIN DESCRIPTION:
LGII3148
END DESCRIPTION:
XS GIS Cut Line= 3
      2564717.89     13559868.64      2564473.70     13560352.03
      2564374.23     13560640.49
#Sta/Elev= 30
  4590.0  200.42  4619.5  199.42  4641.9  199.36  4649.7  198.86  4655.3  197.44
  4672.0  196.55  4716.6  196.30  4722.2  195.66  4731.6  195.92  4744.5  194.52
  4783.5  192.73  4888.4  189.47  4894.9  188.84  4978.0  186.96  4989.7  185.68
  5000.5  183.46  5006.4  181.63  5010.0  181.52  5010.2  181.02  5013.7  181.02
  5014.0  181.52  5022.9  184.98  5028.7  185.75  5087.4  187.09  5117.9  187.44
  5130.4  188.46  5192.9  190.19  5301.3  193.98  5430.9  198.52  5436.7  199.10
#Mann=6,-1,0
  4590.0    0.12       0  5010.0    0.05       0  5014.0    0.12       0
  5087.4   0.013       0  5192.9    0.12       0  5301.3    0.05       0
Bank Sta=5010,5014
Exp/Cntr=0.3,0.1

Type RM Length L Ch R = 1,306,205,205,205
BEGIN DESCRIPTION:
LGII3147
END DESCRIPTION:
XS GIS Cut Line= 3
      2564553.42     13559828.81      2564349.12     13560292.23
      2564324.20     13560596.26
#Sta/Elev= 30
  4621.5  194.98  4631.9  194.55  4649.7  194.61  4661.0  193.25  4678.5  192.92
  4684.0  192.45  4715.7  192.20  4730.6  190.98  4858.2  187.23  4974.8  184.86
  4988.9  183.70  4996.1  179.71  4996.3  179.21  4999.8  179.21  5000.1  179.71
  5010.8  180.65  5021.4  182.34  5026.9  181.92  5039.2  183.21  5043.5  183.68
  5050.2  185.21  5125.6  187.06  5131.9  186.91  5144.3  187.60  5251.1  190.77
  5271.2  191.94  5321.4  193.35  5331.4  194.01  5383.1  195.86  5433.0  197.39
#Mann=6,-1,0
  4621.5    0.12       0  4996.1    0.05       0  5000.1    0.12       0
  5039.2   0.013       0  5144.3    0.12       0  5383.1    0.05       0
Bank Sta=4996.1,5000.1
Exp/Cntr=0.3,0.1

Type RM Length L Ch R = 1,101,0,0,0
BEGIN DESCRIPTION:
LGII3146
END DESCRIPTION:
XS GIS Cut Line= 4
      2564488.66     13559818.82      2564279.36     13559978.29
      2564219.56     13560102.87      2564284.22     13560510.75
#Sta/Elev= 30
  4661.1  192.32  4667.5  192.32  4761.0  187.87  4860.8  184.69  4875.3  184.59
  4923.8  182.54  4941.5  182.31  4947.1  181.76  4964.2  182.23  4969.7  181.98
  4976.0  180.67  4986.8  180.51  4992.4  179.64  4998.2  179.41  5007.3  178.04
  5007.6  177.54  5011.1  177.54  5011.3  178.04  5020.6  180.56  5031.5  181.05
  5037.7  182.17  5062.4  183.64  5167.7  185.42  5192.1  186.15  5236.7  186.66
  5246.8  187.32  5267.9  187.83  5408.8  191.86  5451.4  193.32  5475.4  194.74
#Mann=5,-1,0
  4661.1    0.12       0  5007.3    0.05       0  5011.3    0.12       0
  5167.7   0.013       0  5267.9    0.12       0
Bank Sta=5007.3,5011.3
Exp/Cntr=0.3,0.1

Chan Stop Cuts=-1