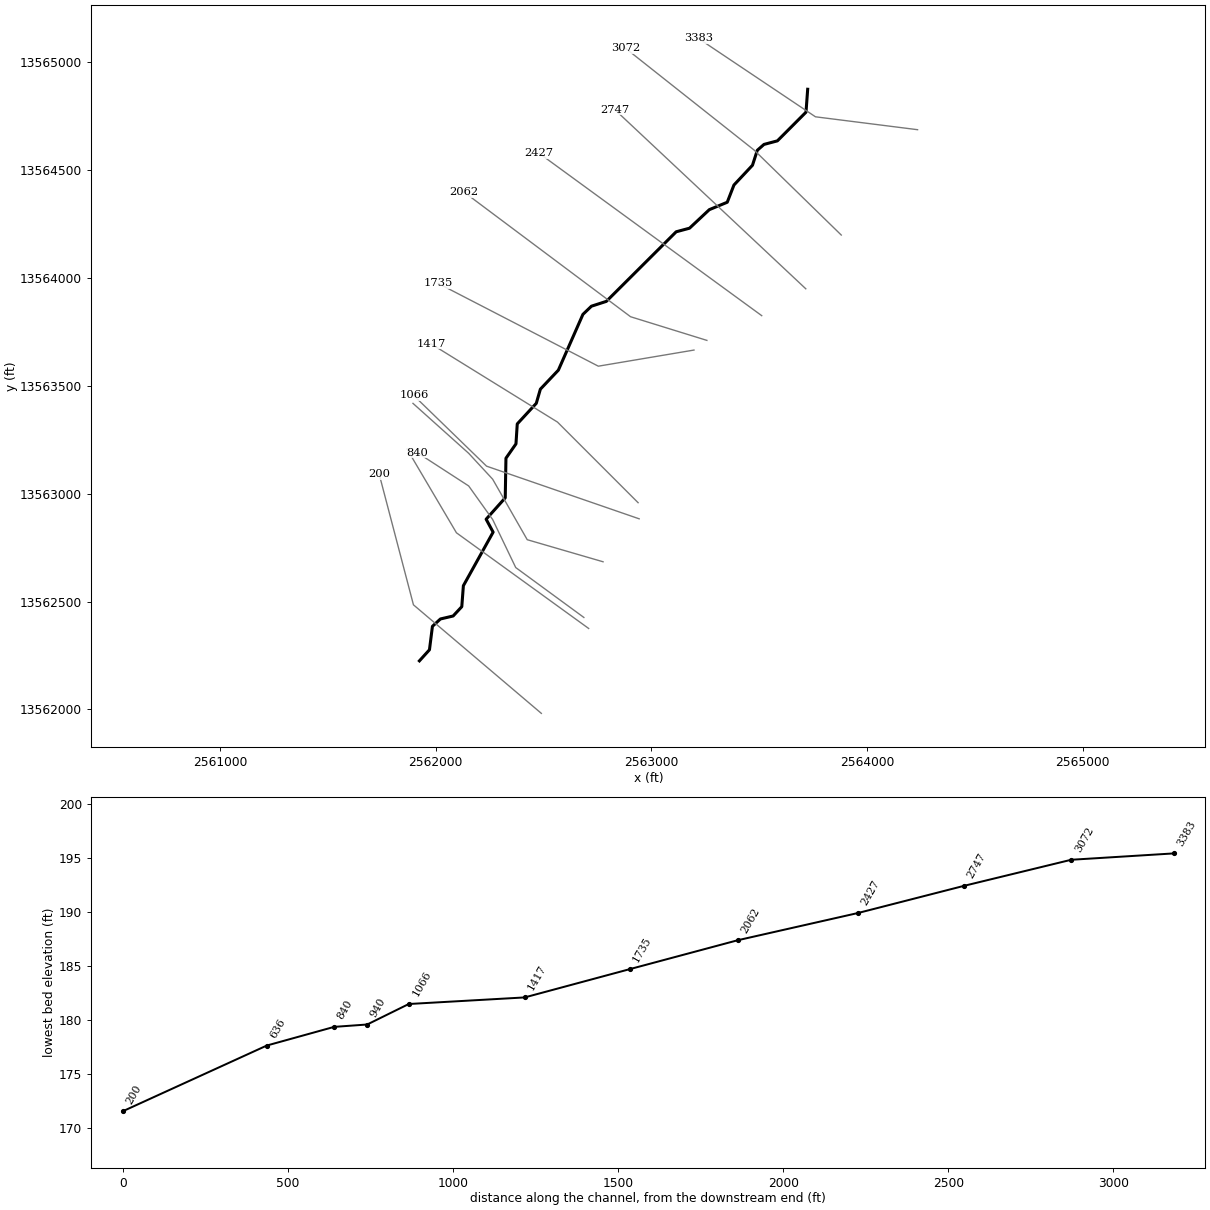
--- TRIB 6_2 TO PRICE CREEK.prj (project) ---

Proj Title=TRIB 6_2 TO PRICE CREEK Base Level Engineering
Current Plan=p01
Default Exp/Contr=0.3,0.1
English Units
Geom File=g01
Flow File=f01
Plan File=p01
BEGIN DESCRIPTION:
TRIB 6_2 TO PRICE CREEK
END DESCRIPTION:

--- TRIB 6_2 TO PRICE CREEK.p01 (plan) ---

Plan Title=Multiple Run
Short Identifier=Multiple
Geom File=g01
Flow File=f01
Subcritical Flow
K Sum by GR= 0
Std Step Tol= 0.01
Critical Tol= 0.01
Num of Std Step Trials= 20
Max Error Tol= 0.3
Flow Tol Ratio= 0.001
Split Flow NTrial= 30
Split Flow Tol= 0.02
Split Flow Ratio= 0.02
Log Output Level= 0
Friction Slope Method= 1
Unsteady Friction Slope Method= 2
Unsteady Bridges Friction Slope Method= 1
Parabolic Critical Depth
Global Vel Dist=  1 , 1 , 1
Global Log Level= 0
CheckData=True
Encroach Param= -1, 0, 0, 0
BEGIN DESCRIPTION:
Multiple Run
END DESCRIPTION:

--- TRIB 6_2 TO PRICE CREEK.f01 (steady flow) ---

Flow Title=Multiple
Number of Profiles=7
Profile Names=10-year,25-year,50-year,1pct_min,100-year,1pct_plu,500-year
River Rch & RM= TRIB 6_2 TO PRIC,Reach-1,3383
     455     712     937     599    1196    2386    1922
River Rch & RM= TRIB 6_2 TO PRIC,Reach-1,1066
     485     762    1006     645    1287    2568    2080
Boundary for River Rch & Prof#=TRIB 6_2 TO PRIC,Reach-1,1
Up Type=0
Dn Type=3
Dn Slope=0.005
Boundary for River Rch & Prof#=TRIB 6_2 TO PRIC,Reach-1,2
Up Type=0
Dn Type=3
Dn Slope=0.005
Boundary for River Rch & Prof#=TRIB 6_2 TO PRIC,Reach-1,3
Up Type=0
Dn Type=3
Dn Slope=0.005
Boundary for River Rch & Prof#=TRIB 6_2 TO PRIC,Reach-1,4
Up Type=0
Dn Type=3
Dn Slope=0.005
Boundary for River Rch & Prof#=TRIB 6_2 TO PRIC,Reach-1,5
Up Type=0
Dn Type=3
Dn Slope=0.005
Boundary for River Rch & Prof#=TRIB 6_2 TO PRIC,Reach-1,6
Up Type=0
Dn Type=3
Dn Slope=0.005
Boundary for River Rch & Prof#=TRIB 6_2 TO PRIC,Reach-1,7
Up Type=0
Dn Type=3
Dn Slope=0.005

--- TRIB 6_2 TO PRICE CREEK.g01 (geometry) ---

Geom Title=Existing Conditions

River Reach=TRIB 6_2 TO PRIC,Reach-1
Reach XY= 30
      2563725.00     13564875.00      2563717.26     13564768.78
      2563584.66     13564635.79      2563522.46     13564619.25
      2563491.50     13564592.05      2563469.12     13564522.74
      2563383.18     13564431.02      2563352.14     13564351.16
      2563268.98     13564316.82      2563177.28     13564230.87
      2563115.32     13564214.22      2562791.66     13563891.66
      2562722.46     13563869.25      2562683.02     13563831.34
      2562569.15     13563572.71      2562485.80     13563484.67
      2562466.82     13563418.96      2562378.62     13563323.50
      2562372.64     13563230.98      2562326.22     13563164.50
      2562322.92     13562980.85      2562234.32     13562881.66
      2562266.75     13562821.77      2562128.83     13562573.41
      2562121.48     13562476.28      2562081.35     13562433.03
      2562022.45     13562419.25      2561985.37     13562385.11
      2561971.61     13562276.41      2561925.00     13562225.00

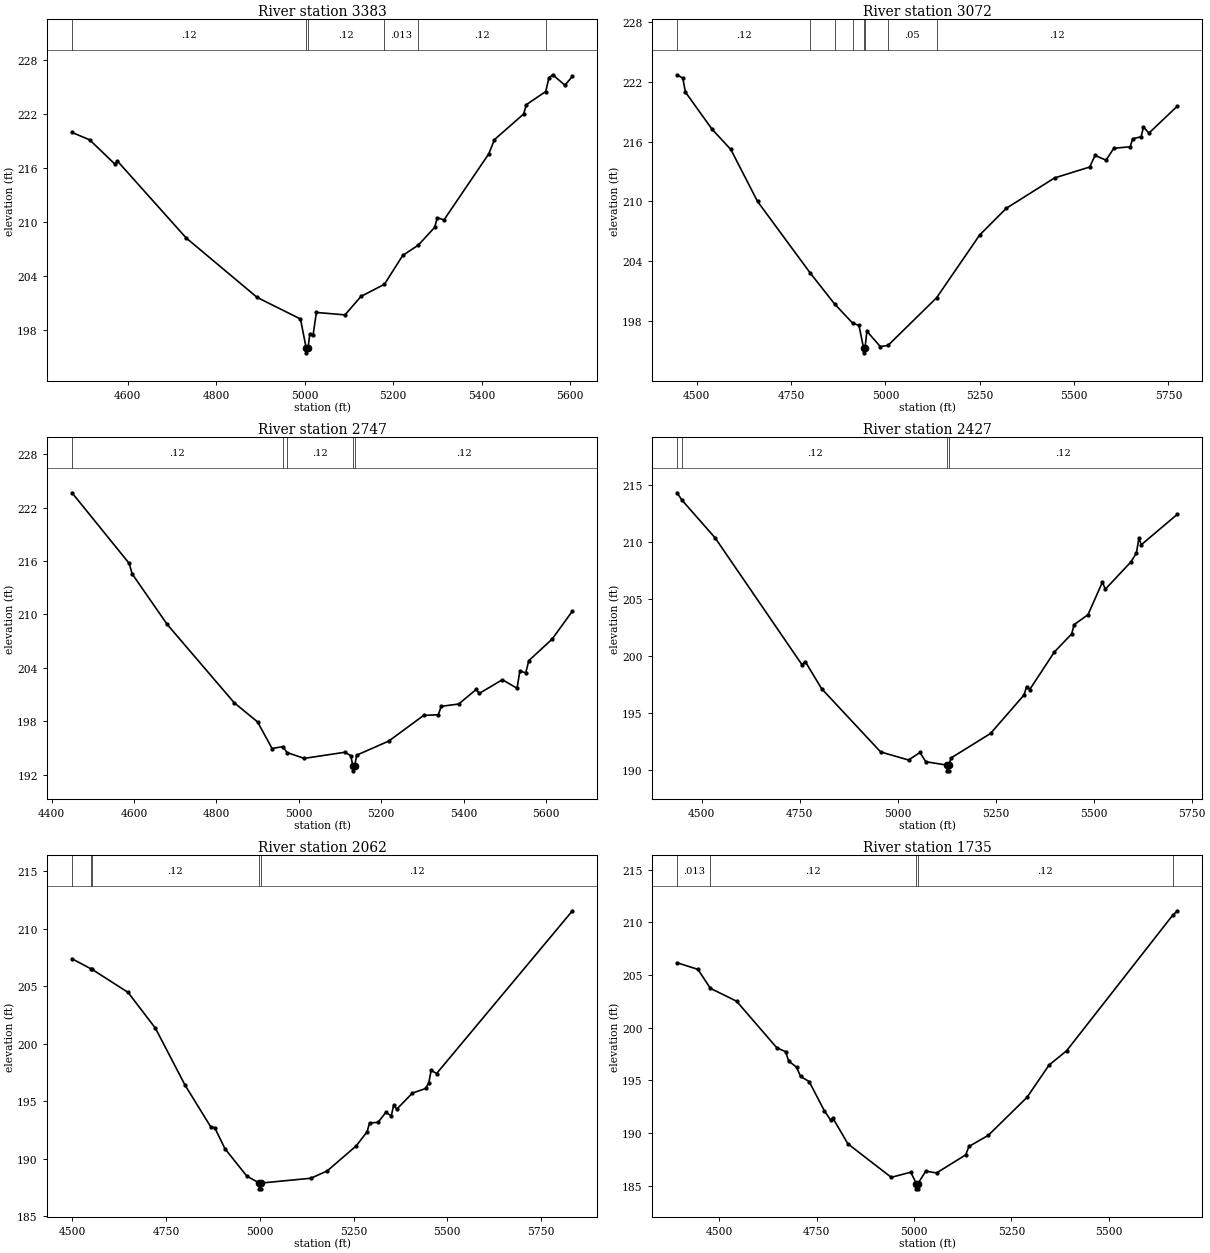
Type RM Length L Ch R = 1,3383,311,311,311
BEGIN DESCRIPTION:
LGII3131
END DESCRIPTION:
XS GIS Cut Line= 3
      2564234.51     13564687.49      2563761.09     13564747.29
      2563217.93     13565111.06
#Sta/Elev= 30
  4474.1  219.93  4513.9  219.11  4571.7  216.38  4576.7  216.75  4732.1  208.20
  4892.5  201.59  4990.4  199.19  5003.4  195.93  5003.7  195.43  5007.4  195.93
  5011.4  197.51  5018.8  197.40  5026.4  199.92  5091.0  199.65  5127.1  201.70
  5180.1  203.05  5221.5  206.26  5256.6  207.40  5293.6  209.38  5299.6  210.45
  5314.6  210.20  5416.0  217.56  5428.7  219.13  5494.7  221.98  5500.8  223.02
  5544.7  224.48  5551.8  226.01  5560.4  226.34  5587.8  225.19  5605.0  226.16
#Mann=6,-1,0
  4474.1    0.12       0  5003.4    0.05       0  5007.4    0.12       0
  5180.1   0.013       0  5256.6    0.12       0  5544.7    0.05       0
Bank Sta=5003.4,5007.4
Exp/Cntr=0.3,0.1

Type RM Length L Ch R = 1,3072,325,325,325
BEGIN DESCRIPTION:
LGII3130
END DESCRIPTION:
XS GIS Cut Line= 3
      2563880.72     13564199.10      2563477.05     13564592.81
      2562879.51     13565065.86
#Sta/Elev= 30
  4447.8  222.69  4463.1  222.36  4470.1  220.96  4540.8  217.23  4590.4  215.21
  4661.1  210.01  4800.7  202.84  4865.5  199.73  4913.3  197.81  4929.9  197.59
  4942.0  195.34  4942.3  194.84  4946.0  195.34  4951.0  197.00  4986.5  195.47
  5006.8  195.58  5135.5  200.35  5249.5  206.63  5320.4  209.32  5448.2  212.36
  5541.2  213.45  5555.6  214.61  5584.5  214.14  5605.3  215.33  5648.6  215.48
  5655.0  216.28  5677.5  216.48  5683.8  217.47  5698.3  216.85  5773.8  219.56
#Mann=8,-1,0
  4447.8    0.12       0  4800.7    0.05       0  4865.5    0.12       0
  4913.3   0.013       0  4942.0    0.03       0  4946.0   0.013       0
  5006.8    0.05       0  5135.5    0.12       0
Bank Sta=4942,4946
Exp/Cntr=0.3,0.1

Type RM Length L Ch R = 1,2747,320,320,320
BEGIN DESCRIPTION:
LGII3129
END DESCRIPTION:
XS GIS Cut Line= 2
      2563716.24     13563949.96      2562830.75     13564780.74
#Sta/Elev= 30
  4449.6  223.67  4588.4  215.73  4595.5  214.56  4680.5  208.88  4843.2  200.07
  4899.8  197.92  4935.0  194.93  4960.7  195.14  4971.6  194.47  5013.1  193.82
  5111.8  194.51  5126.0  194.12  5131.3  192.92  5131.6  192.42  5135.3  192.92
  5140.2  194.18  5218.3  195.77  5302.8  198.65  5338.5  198.72  5345.3  199.67
  5387.8  199.93  5430.3  201.57  5437.6  201.12  5493.8  202.66  5529.4  201.70
  5536.3  203.66  5550.5  203.42  5557.8  204.80  5614.4  207.22  5663.8  210.38
#Mann=5,-1,0
  4449.6    0.12       0  4960.7    0.05       0  4971.6    0.12       0
  5131.3    0.05       0  5135.3    0.12       0
Bank Sta=5131.3,5135.3
Exp/Cntr=0.3,0.1

Type RM Length L Ch R = 1,2427,365,365,365
BEGIN DESCRIPTION:
LGII3128
END DESCRIPTION:
XS GIS Cut Line= 2
      2563511.96     13563825.36      2562480.36     13564577.88
#Sta/Elev= 30
  4436.9  214.32  4449.7  213.67  4534.0  210.37  4755.7  199.23  4764.2  199.50
  4805.9  197.12  4956.5  191.57  5027.6  190.86  5056.9  191.52  5071.6  190.71
  5126.0  190.41  5126.2  189.91  5129.7  189.91  5130.0  190.41  5136.5  191.05
  5236.9  193.19  5322.6  196.58  5328.8  197.31  5336.7  197.04  5399.9  200.35
  5443.9  201.93  5450.1  202.74  5485.6  203.62  5522.4  206.48  5529.7  205.85
  5594.5  208.23  5609.0  209.02  5615.4  210.31  5621.6  209.76  5713.8  212.44
#Mann=4,-1,0
  4436.9   0.013       0  4449.7    0.12       0  5126.0    0.05       0
  5130.0    0.12       0
Bank Sta=5126,5130
Exp/Cntr=0.3,0.1

Type RM Length L Ch R = 1,2062,327,327,327
BEGIN DESCRIPTION:
LGII3127
END DESCRIPTION:
XS GIS Cut Line= 3
      2563257.76     13563710.77      2562903.97     13563820.40
      2562131.60     13564398.43
#Sta/Elev= 30
  4498.8  207.37  4549.2  206.50  4550.9  206.48  4648.3  204.45  4721.5  201.33
  4800.2  196.40  4868.5  192.79  4879.7  192.68  4906.8  190.87  4965.1  188.49
  4998.5  187.88  4998.8  187.38  5002.3  187.38  5002.5  187.88  5136.0  188.30
  5179.8  188.94  5256.9  191.11  5286.0  192.33  5292.6  193.11  5315.2  193.15
  5336.1  194.03  5350.6  193.72  5356.9  194.65  5365.2  194.30  5406.9  195.70
  5442.4  196.10  5450.7  196.61  5456.9  197.67  5471.5  197.40  5833.9  211.54
#Mann=5,-1,0
  4498.8    0.12       0  4549.2   0.013       0  4550.9    0.12       0
  4998.5    0.05       0  5002.5    0.12       0
Bank Sta=4998.5,5002.5
Exp/Cntr=0.3,0.1

Type RM Length L Ch R = 1,1735,318,318,318
BEGIN DESCRIPTION:
LGII3126
END DESCRIPTION:
XS GIS Cut Line= 3
      2563197.94     13563665.91      2562754.47     13563591.17
      2562011.98     13563974.87
#Sta/Elev= 30
  4391.0  206.16  4444.7  205.53  4476.8  203.73  4544.0  202.51  4647.5  198.08
  4670.0  197.72  4677.9  196.82  4698.2  196.25  4708.3  195.37  4730.5  194.88
  4769.2  192.13  4786.0  191.19  4791.1  191.43  4830.0  188.97  4941.4  185.79
  4991.4  186.28  5005.9  185.20  5006.1  184.70  5009.6  184.70  5009.9  185.20
  5030.0  186.38  5057.8  186.21  5132.8  187.93  5140.8  188.72  5190.7  189.78
  5290.2  193.39  5346.7  196.45  5391.7  197.80  5664.5  210.68  5676.5  211.09
#Mann=5,-1,0
  4391.0   0.013       0  4476.8    0.12       0  5005.9    0.05       0
  5009.9    0.12       0  5664.5    0.05       0
Bank Sta=5005.9,5009.9
Exp/Cntr=0.3,0.1

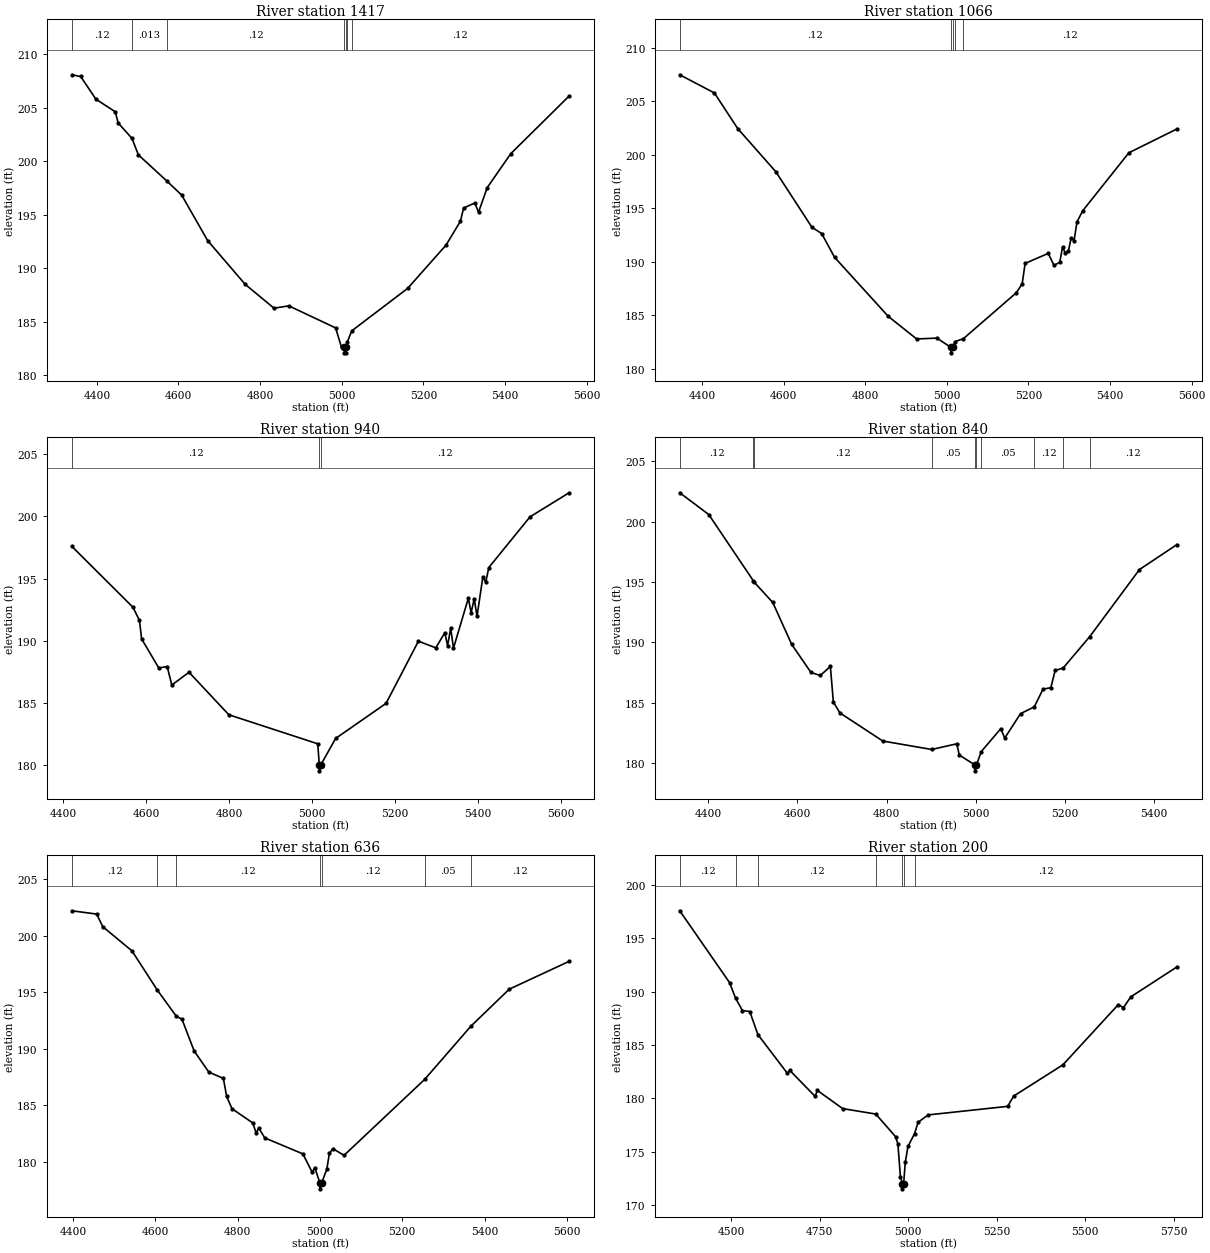
Type RM Length L Ch R = 1,1417,351,351,351
BEGIN DESCRIPTION:
LGII3125
END DESCRIPTION:
XS GIS Cut Line= 3
      2562938.86     13562958.28      2562565.11     13563332.04
      2561978.54     13563694.91
#Sta/Elev= 30
  4338.7  208.06  4360.3  207.90  4397.7  205.78  4445.2  204.60  4452.2  203.56
  4486.0  202.12  4501.7  200.58  4571.3  198.14  4607.8  196.82  4671.4  192.57
  4763.4  188.48  4834.1  186.25  4870.3  186.47  4985.0  184.41  4999.5  182.59
  5006.5  182.58  5006.7  182.08  5010.2  182.08  5010.5  182.58  5013.7  183.10
  5024.4  184.13  5161.4  188.10  5255.4  192.14  5290.7  194.37  5298.6  195.61
  5326.0  196.08  5335.2  195.22  5356.5  197.52  5414.4  200.70  5557.0  206.07
#Mann=7,-1,0
  4338.7    0.12       0  4486.0   0.013       0  4571.3    0.12       0
  5006.5    0.05       0  5010.5    0.12       0  5013.7     0.1       0
  5024.4    0.12       0
Bank Sta=5006.5,5010.5
Exp/Cntr=0.3,0.1

Type RM Length L Ch R = 1,1066,126,126,126
BEGIN DESCRIPTION:
LGII3124
END DESCRIPTION:
XS GIS Cut Line= 3
      2562943.81     13562883.55      2562236.21     13563127.72
      2561898.70     13563455.31
#Sta/Elev= 30
  4345.2  207.50  4430.1  205.80  4487.2  202.47  4580.8  198.42  4669.1  193.23
  4693.0  192.64  4724.8  190.41  4856.2  184.89  4925.8  182.77  4975.7  182.85
  5010.2  181.97  5010.5  181.47  5014.2  181.97  5019.8  182.52  5040.3  182.79
  5170.4  187.10  5184.6  187.93  5191.8  189.84  5248.4  190.78  5262.5  189.67
  5276.6  189.93  5283.6  191.37  5290.6  190.79  5297.8  190.99  5304.7  192.22
  5311.9  191.98  5318.9  193.72  5333.0  194.77  5446.2  200.20  5564.1  202.43
#Mann=5,-1,0
  4345.2    0.12       0  5010.2    0.05       0  5014.2    0.12       0
  5019.8     0.1       0  5040.3    0.12       0
Bank Sta=5010.2,5014.2
Exp/Cntr=0.3,0.1

Type RM Length L Ch R = 1,940,100,100,100
BEGIN DESCRIPTION:
4906
END DESCRIPTION:
XS GIS Cut Line= 5
      2562776.46     13562684.40      2562424.86     13562786.76
      2562264.65     13563067.13      2562153.39     13563187.29
      2561895.23     13563418.75
#Sta/Elev= 30
  4420.6  197.58  4567.9  192.70  4583.7  191.65  4588.9  190.16  4630.4  187.82
  4650.7  187.94  4661.7  186.45  4703.3  187.48  4799.3  184.07  5013.8  181.74
  5017.6  180.07  5017.8  179.57  5021.6  180.07  5057.0  182.17  5178.6  184.98
  5256.7  189.97  5298.7  189.44  5320.4  190.65  5327.1  189.61  5334.6  191.01
  5341.3  189.41  5377.2  193.42  5383.9  192.25  5391.4  193.38  5398.1  191.96
  5412.3  195.15  5419.1  194.69  5426.5  195.88  5526.0  199.95  5620.2  201.88
#Mann=3,-1,0
  4420.6    0.12       0  5017.6    0.05       0  5021.6    0.12       0
Bank Sta=5017.6,5021.6
Exp/Cntr=0.3,0.1

Type RM Length L Ch R = 1,840,204,204,204
BEGIN DESCRIPTION:
4907
END DESCRIPTION:
XS GIS Cut Line= 5
      2562687.44     13562426.28      2562371.46     13562657.70
      2562264.65     13562880.22      2562153.39     13563035.98
      2561914.41     13563190.88
#Sta/Elev= 30
  4336.3  202.39  4401.3  200.59  4501.6  195.08  4503.7  194.96  4544.8  193.30
  4587.2  189.83  4630.5  187.50  4651.3  187.25  4674.0  188.00  4680.6  185.06
  4695.3  184.15  4791.5  181.82  4901.0  181.12  4957.4  181.59  4962.9  180.66
  4997.5  179.85  4997.8  179.35  5001.5  179.85  5012.3  180.95  5056.1  182.85
  5064.7  182.06  5100.3  184.09  5131.1  184.65  5150.7  186.12  5168.2  186.24
  5177.9  187.67  5195.6  187.86  5255.6  190.48  5366.9  196.03  5451.0  198.10
#Mann=10,-1,0
  4336.3    0.12       0  4501.6   0.013       0  4503.7    0.12       0
  4901.0    0.05       0  4997.5    0.05       0  5001.5    0.12       0
  5012.3    0.05       0  5131.1    0.12       0  5195.6    0.05       0
  5255.6    0.12       0
Bank Sta=4997.5,5001.5
Exp/Cntr=0.3,0.1

Type RM Length L Ch R = 1,636,436,436,436
BEGIN DESCRIPTION:
LGII3123
END DESCRIPTION:
XS GIS Cut Line= 3
      2562709.66     13562375.22      2562096.68     13562818.76
      2561867.43     13563207.47
#Sta/Elev= 30
  4397.4  202.19  4457.7  201.90  4472.4  200.79  4543.6  198.64  4604.9  195.19
  4651.0  192.88  4665.0  192.60  4694.4  189.81  4730.0  187.94  4765.5  187.38
  4773.5  185.78  4786.4  184.70  4836.7  183.45  4845.2  182.55  4851.4  183.00
  4866.1  182.12  4958.6  180.71  4981.3  179.08  4987.5  179.50  5000.2  178.12
  5000.5  177.62  5004.2  178.12  5016.9  179.38  5023.1  180.77  5031.6  181.17
  5058.7  180.58  5254.5  187.29  5367.0  192.00  5459.9  195.26  5605.3  197.72
#Mann=7,-1,0
  4397.4    0.12       0  4604.9   0.013       0  4651.0    0.12       0
  5000.2    0.05       0  5004.2    0.12       0  5254.5    0.05       0
  5367.0    0.12       0
Bank Sta=5000.2,5004.2
Exp/Cntr=0.3,0.1

Type RM Length L Ch R = 1,200,0,0,0
BEGIN DESCRIPTION:
LGII3122
END DESCRIPTION:
XS GIS Cut Line= 3
      2562490.32     13561981.60      2561897.35     13562484.88
      2561738.26     13563091.40
#Sta/Elev= 30
  4354.5  197.59  4495.2  190.86  4512.0  189.41  4531.5  188.24  4552.3  188.15
  4575.4  185.98  4658.9  182.34  4665.4  182.63  4736.8  180.20  4743.4  180.75
  4814.8  179.05  4908.3  178.54  4964.2  176.42  4970.8  175.74  4977.9  172.67
  4983.1  172.03  4983.3  171.53  4987.1  172.03  4991.6  174.01  4999.4  175.51
  5017.8  176.70  5027.9  177.77  5056.5  178.46  5280.9  179.26  5297.8  180.22
  5437.2  183.16  5593.6  188.80  5607.9  188.50  5628.6  189.52  5759.3  192.33
#Mann=7,-1,0
  4354.5    0.12       0  4512.0   0.013       0  4575.4    0.12       0
  4908.3   0.013       0  4983.1    0.03       0  4987.1   0.013       0
  5017.8    0.12       0
Bank Sta=4983.1,4987.1
Exp/Cntr=0.3,0.1

Chan Stop Cuts=-1