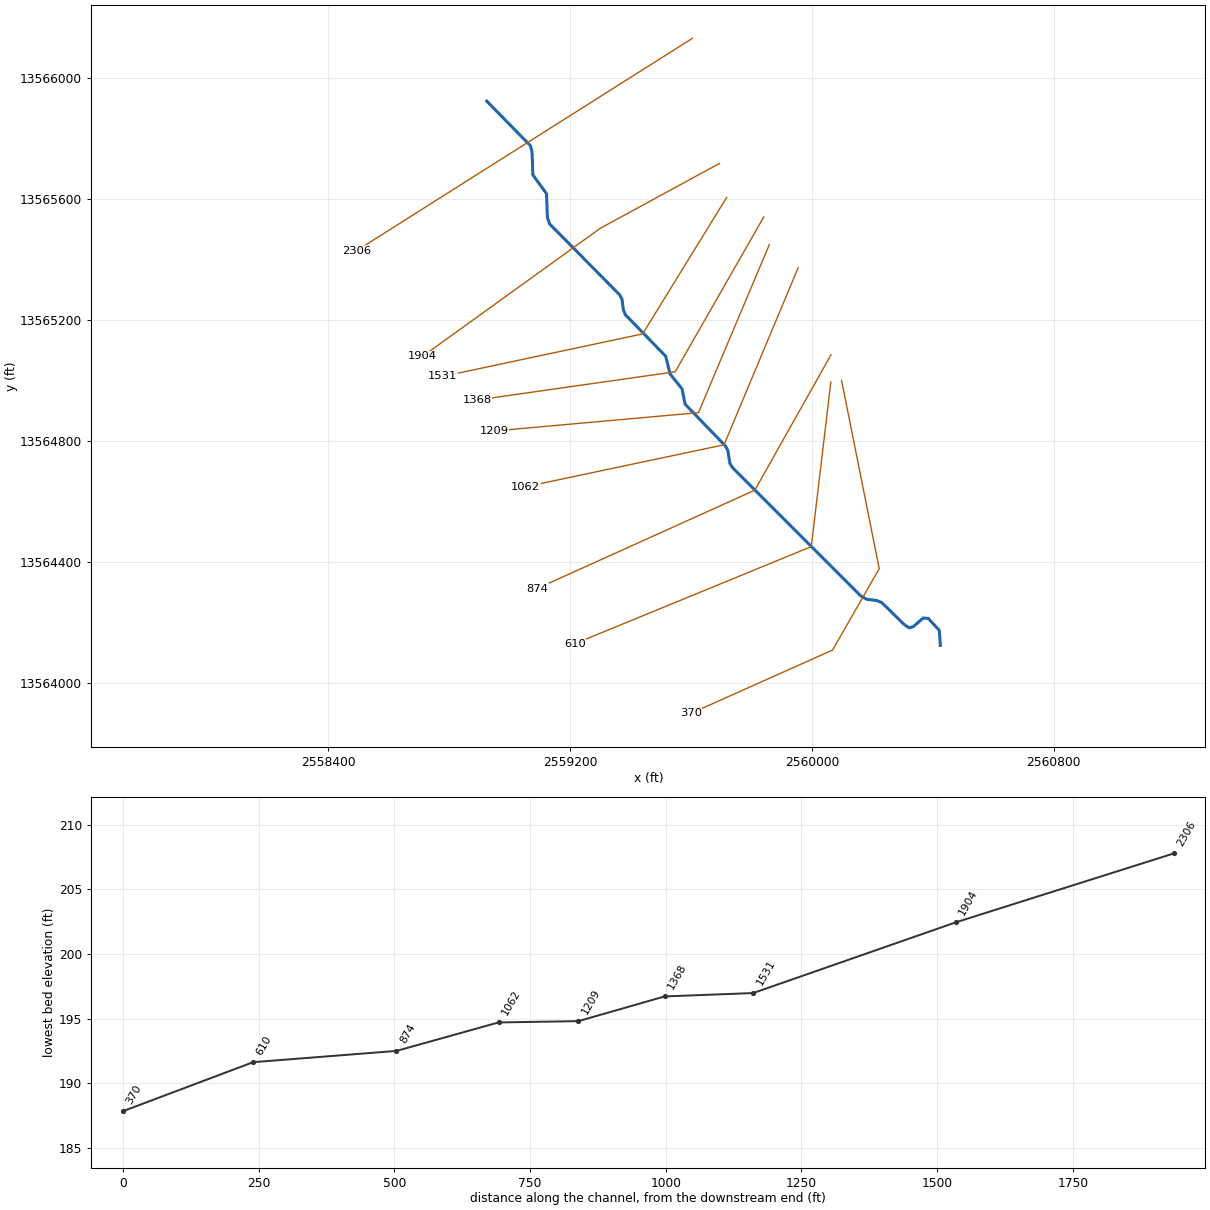
--- TRIB 6_3 TO PRICE CREEK.prj (project) ---

Proj Title=TRIB 6_3 TO PRICE CREEK Base Level Engineering
Current Plan=p01
Default Exp/Contr=0.3,0.1
English Units
Geom File=g01
Flow File=f01
Plan File=p01
Y Axis Title=Elevation
X Axis Title(PF)=Main Channel Distance
X Axis Title(XS)=Station
BEGIN DESCRIPTION:
TRIB 6_3 TO PRICE CREEK
END DESCRIPTION:
DSS Export Rating Curves= 0
DSS Export Rating Curve Sorted= 0
DSS Export Volume Flow Curves= 0
DXF OffsetX= 0
DXF OffsetY= 0
DXF ScaleX= 1
DXF ScaleY= 10

--- TRIB 6_3 TO PRICE CREEK.p01 (plan) ---

Plan Title=Multiple Run
Program Version=4.10
Short Identifier=Multiple
Geom File=g01
Flow File=f01
Subcritical Flow
K Sum by GR= 0
Std Step Tol= 0.01
Critical Tol= 0.01
Num of Std Step Trials= 20
Max Error Tol= 0.3
Flow Tol Ratio= 0.001
Split Flow NTrial= 30
Split Flow Tol= 0.02
Split Flow Ratio= 0.02
Log Output Level= 0
Friction Slope Method= 1
Unsteady Friction Slope Method= 2
Unsteady Bridges Friction Slope Method= 1
Parabolic Critical Depth
Global Vel Dist= 1 , 1 , 1
Global Log Level= 0
CheckData=True
Encroach Param=-1 ,0,0, 0
BEGIN DESCRIPTION:
Multiple Run
END DESCRIPTION:
Computation Interval=1HOUR
Output Interval=1HOUR
Run HTab= 0
Run UNet= 0
Run PostProcess= 0
Run WQNet= 0
UNET Theta= 1
UNET Theta Warmup= 1
UNET ZTol= 0.02
UNET ZSATol= 0.05
UNET MxIter= 20
UNET MaxInSteps= 0
UNET DtIC= 0
UNET DtMin= 0
UNET MaxCRTS= 20
UNET WFStab= 2
UNET SFStab= 1
UNET WFX= 1
UNET SFX= 1
UNET DSS MLevel= 4
UNET DZMax Abort= 100
UNET Convert EG Bridges= 0
UNET Use Existing IB Tables=-1
UNET Froude Reduction=False
UNET Froude Limit= 1
UNET Froude Power= 10
UNET Time Slicing=0,0, 5
UNET Junction Losses=0
Instantaneous Interval=1HOUR
Write IC File= 0
Write IC File at Sim End=0
Echo Input=False
Echo Parameters=False
Echo Output=False
Write Detailed= 0
WQ AD Non Conservative
WQ ULTIMATE=-1
WQ Max Comp Step=1HOUR
WQ Output Interval=15MIN
WQ Output Selected Increments= 0
WQ Output face flow=0
WQ Output face velocity=0
WQ Output face area=0
WQ Output face dispersion=0
WQ Output cell volume=0
WQ Output cell surface area=0
WQ Output cell continuity=0
WQ Output cumulative cell continuity=0
WQ Output face conc=0
WQ Output face dconc_dx=0
WQ Output face courant=0
WQ Output face peclet=0
WQ Output face adv mass=0
WQ Output face disp mass=0
WQ Output cell mass=0
WQ Output cell source sink temp=0
WQ Output cell source sink nsm=0
WQ Output MaxMinRange=-1
WQ Daily Max Min Mean=-1
WQ Daily Range=0
WQ Daily Time=0
WQ Create Restart=0
WQ Fixed Restart=0
WQ System Summary=0
WQ Use Fixed Temperature=0
Sorting and Armoring Iterations= 10
XS Update Threshold= 0.02
Hydraulics Update Threshold= 0.02
Energy Slope Method= 1
Volume Change Method= 0
XS Weighting Method= 0
Number of US Weighted Cross Sections= 1
Number of DS Weighted Cross Sections= 1
Upstream XS Weight=0.25
Main XS Weight=0.5
Downstream XS Weight=0.25
Number of DS XS's Weighted with US Boundary= 1
Upstream Boundary Weight= 1
Weight of XSs Associated with US Boundary= 0
Number of US XS's Weighted with DS Boundary= 1
Downstream Boundary Weight= 0.5
Weight of XSs Associated with DS Boundary= 0.5
Sediment Output Level= 4
Mass or Volume Output= 0
Output Increment Type= 1
Profile and TS Output Increment= 10
XS Output Flag= 0
XS Output Increment= 10
Disregard all LS=0
Disregard all Conn=0
Disregard all Breaches=0
Disregard all Pumps=0

--- TRIB 6_3 TO PRICE CREEK.f01 (steady flow) ---

Flow Title=Multiple
Number of Profiles=7
Profile Names=10-year,25-year,50-year,1pct_min,100-year,1pct_plu,500-year
River Rch & RM= TRIB 6_3 TO PRIC,Reach-1,2306
     276     417     536     335     668    1333    1026
Boundary for River Rch & Prof#=TRIB 6_3 TO PRIC,Reach-1,1
Up Type=0
Dn Type=3
Dn Slope=0.005
Boundary for River Rch & Prof#=TRIB 6_3 TO PRIC,Reach-1,2
Up Type=0
Dn Type=3
Dn Slope=0.005
Boundary for River Rch & Prof#=TRIB 6_3 TO PRIC,Reach-1,3
Up Type=0
Dn Type=3
Dn Slope=0.005
Boundary for River Rch & Prof#=TRIB 6_3 TO PRIC,Reach-1,4
Up Type=0
Dn Type=3
Dn Slope=0.005
Boundary for River Rch & Prof#=TRIB 6_3 TO PRIC,Reach-1,5
Up Type=0
Dn Type=3
Dn Slope=0.005
Boundary for River Rch & Prof#=TRIB 6_3 TO PRIC,Reach-1,6
Up Type=0
Dn Type=3
Dn Slope=0.005
Boundary for River Rch & Prof#=TRIB 6_3 TO PRIC,Reach-1,7
Up Type=0
Dn Type=3
Dn Slope=0.005

--- TRIB 6_3 TO PRICE CREEK.g01 (geometry) ---

Geom Title=Existing Conditions
Program Version=4.10

River Reach=TRIB 6_3 TO PRIC,Reach-1
Reach XY= 30
        2558925.       13565925.      2559069.48     13565777.43
      2559074.88     13565754.95      2559077.36     13565680.98
      2559122.64     13565619.02      2559125.52     13565540.22
      2559132.86     13565518.83      2559364.22     13565284.68
      2559372.47     13565268.95      2559376.55     13565235.64
      2559383.16     13565218.95      2559516.86     13565081.06
       2559531.1     13565022.81      2559570.81     13564973.26
      2559580.83      13564922.7      2559714.22     13564784.68
      2559722.46     13564768.95      2559728.98     13564726.65
      2559738.63     13564711.79      2560161.79     13564288.63
      2560181.05     13564277.53      2560214.36     13564273.44
      2560231.05      13564266.8      2560305.02     13564194.41
      2560321.68       13564183.      2560335.02     13564186.67
      2560368.45     13564215.48      2560385.25     13564214.13
      2560421.73     13564174.36        2560425.       13564125.

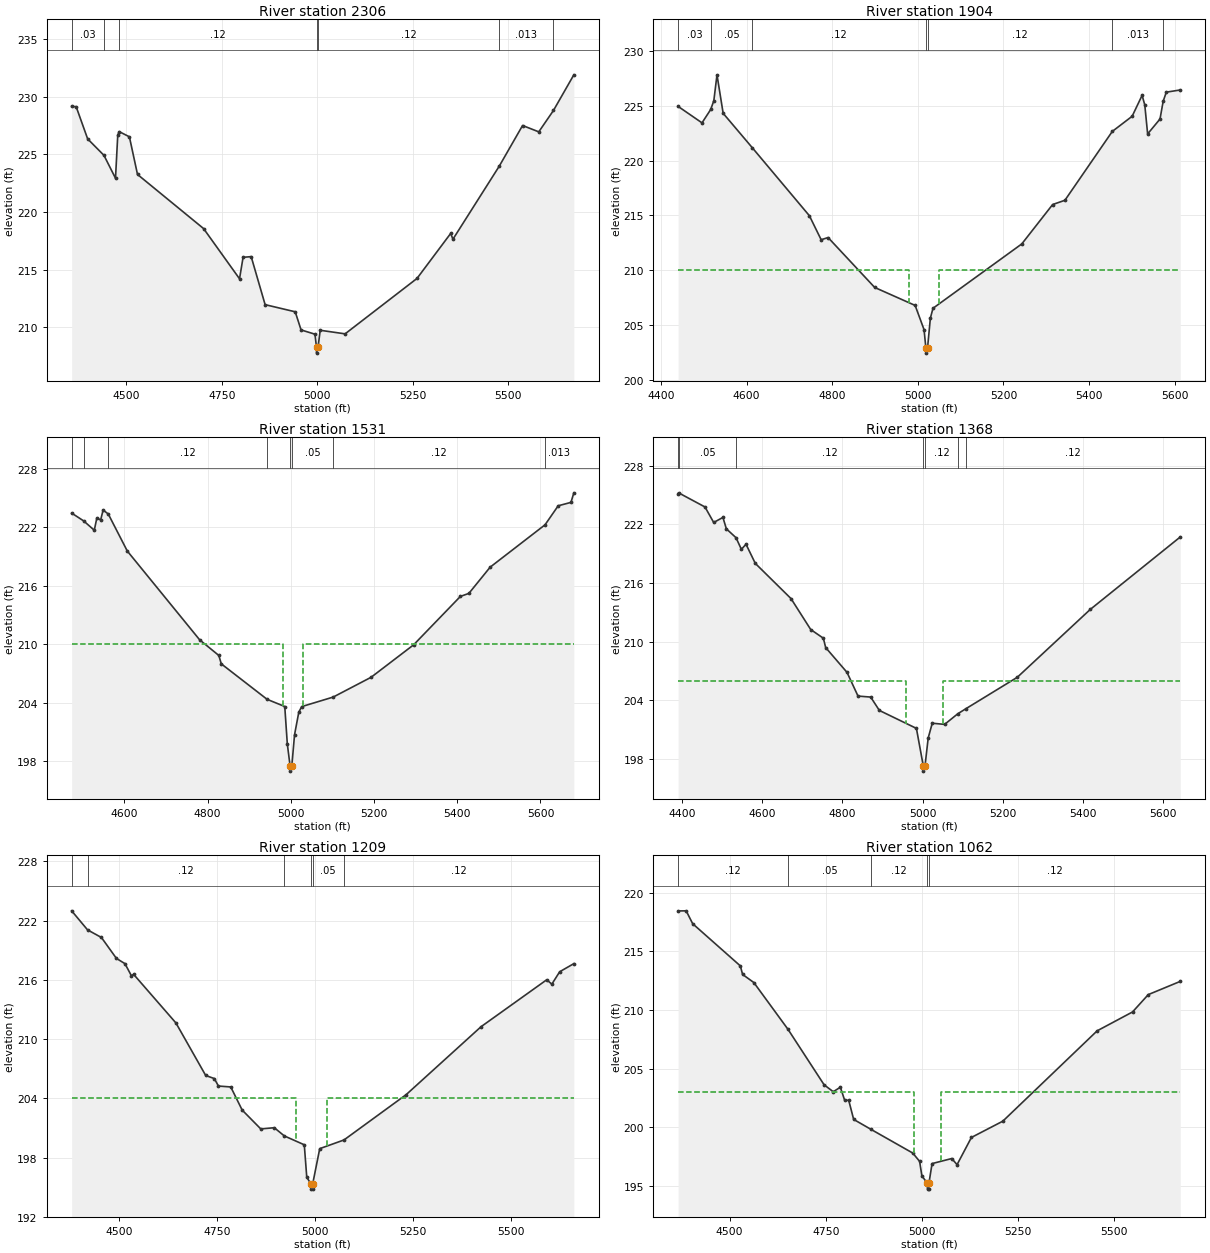
Type RM Length L Ch R = 1 ,2306    ,402,402,402
BEGIN DESCRIPTION:
LGII3121
END DESCRIPTION:
XS GIS Cut Line= 2
      2559605.01     13566132.62       2558493.8     13565430.02
#Sta/Elev= 30
  4356.6  229.14  4368.4  229.12  4398.5  226.33  4441.3   224.9  4471.4  222.92
  4477.3  226.65  4481.1  226.96  4507.8  226.51    4529  223.25    4702  218.56
  4796.1  214.21  4805.4  216.07  4826.6  216.13  4863.1  211.97  4941.9  211.35
  4957.2  209.78  4993.6  209.41  4997.6  208.27  4997.8  207.77  5001.6  208.27
  5007.3  209.75  5072.5  209.44  5260.7  214.24  5348.9  218.14  5354.8  217.64
  5475.9  223.96  5537.1  227.49  5579.5  226.94  5617.9  228.79  5671.3  231.88
#Mann= 7 ,-1 , 0
  4356.6     .03       0  4441.3     .05       0  4481.1     .12       0
  4997.6     .05       0  5001.6     .12       0  5475.9    .013       0
  5617.9     .05       0
Bank Sta=4997.6,5001.6
XS Rating Curve= 0 ,0
Exp/Cntr=0.3,0.1

Type RM Length L Ch R = 1 ,1904    ,373,373,373
BEGIN DESCRIPTION:
LGII3120
END DESCRIPTION:
XS GIS Cut Line= 3
      2559694.74     13565719.03      2559301.06     13565504.75
      2558713.05     13565081.18
#Sta/Elev= 30
  4440.1  224.94  4495.9  223.44  4516.2  224.66  4523.5  225.46  4530.9  227.82
  4545.3  224.31  4613.6  221.16  4746.7  214.97  4774.2  212.78  4790.4  212.98
  4899.2  208.43  4993.7  206.79  5014.5  204.58  5018.7  202.94  5018.9  202.44
  5022.7  202.94  5029.3  205.64  5035.4  206.53  5242.8   212.4  5314.8  215.99
  5343.5  216.38  5454.2  222.66  5500.5  224.04  5523.8  225.95    5530  225.08
  5536.7  222.43  5565.6  223.79    5573  225.41  5580.3  226.24    5613  226.44
#Mann= 7 ,-1 , 0
  4440.1     .03       0  4516.2     .05       0  4613.6     .12       0
  5018.7     .05       0  5022.7     .12       0  5454.2    .013       0
    5573     .12       0
#XS Ineff= 2 , 0
       0    4980     210    5050       0     210
Permanent Ineff=
       F       F
Bank Sta=5018.7,5022.7
XS Rating Curve= 0 ,0
Exp/Cntr=0.3,0.1

Type RM Length L Ch R = 1 ,1531    ,163,163,163
BEGIN DESCRIPTION:
Mapping XS b96dd975
END DESCRIPTION:
XS GIS Cut Line= 3
      2559718.41     13565606.52      2559440.62     13565155.11
      2558778.24      13565014.4
#Sta/Elev= 30
    4473  223.46  4501.8  222.66  4527.4   221.7  4533.5  222.94  4542.8  222.77
  4548.7  223.78  4561.1  223.36  4606.7  219.57  4780.6  210.46  4826.8  208.85
  4832.7  207.99  4942.8  204.35  4985.3  203.61  4991.4  199.78  4998.2  197.48
  4998.4  196.98  5002.2  197.48  5008.8  200.71    5019  203.02  5025.9   203.6
  5101.7  204.58  5192.8  206.61    5295  209.94  5407.5  214.91  5427.9  215.22
    5479  217.91    5611  222.26  5642.6  224.21  5673.3  224.56  5680.2  225.54
#Mann= 8 ,-1 , 0
    4473     .03       0  4501.8     .05       0  4561.1     .12       0
  4942.8     .05       0  4998.2     .04       0  5002.2     .05       0
  5101.7     .12       0    5611    .013       0
#XS Ineff= 2 , 0
       0    4980     210    5030       0     210
Permanent Ineff=
       F       F
Bank Sta=4998.2,5002.2
XS Rating Curve= 0 ,0
Exp/Cntr=0.3,0.1

Type RM Length L Ch R = 1 ,1368    ,159,159,159
BEGIN DESCRIPTION:
Mapping XS 7db38ddd
END DESCRIPTION:
XS GIS Cut Line= 3
      2559841.12     13565541.98      2559548.16     13565029.85
      2558892.77     13564936.54
#Sta/Elev= 30
  4390.7  225.15  4391.9  225.24  4457.7  223.79  4479.4   222.2  4502.4  222.72
    4511  221.55  4535.1  220.64  4548.4  219.45    4560  219.97  4583.1  218.01
  4672.2   214.4  4721.3  211.23  4752.8  210.34  4758.6  209.38  4811.8  206.84
  4839.2  204.41  4870.8  204.31  4892.4  202.94  4984.8   201.1  5002.1  197.22
  5002.3  196.72  5006.1  197.22  5014.2  200.12  5024.3  201.63  5055.1  201.51
    5088   202.6  5108.7  203.13  5236.4  206.34  5418.2  213.29  5642.7  220.72
#Mann= 7 ,-1 , 0
  4390.7     .03       0  4391.9     .05       0  4535.1     .12       0
  5002.1     .04       0  5006.1     .12       0    5088     .05       0
  5108.7     .12       0
#XS Ineff= 2 , 0
       0    4960     206    5050       0     206
Permanent Ineff=
       F       F
Bank Sta=5002.1,5006.1
XS Rating Curve= 0 ,0
Exp/Cntr=0.3,0.1

Type RM Length L Ch R = 1 ,1209    ,147,147,147
BEGIN DESCRIPTION:
Mapping XS b976c1cd
END DESCRIPTION:
XS GIS Cut Line= 3
      2559859.47     13565450.28      2559625.08     13564894.69
      2558949.01     13564834.02
#Sta/Elev= 30
  4378.3     223  4418.9  221.07  4454.3   220.3  4492.6  218.18  4514.3  217.65
  4530.9  216.42  4536.4  216.57  4644.5  211.64  4720.5  206.32  4742.4  206.01
    4753  205.25  4784.4  205.16  4813.5  202.82    4861  200.91  4895.5  201.03
  4921.1   200.2  4972.1   199.3  4978.4  196.02  4989.4  195.31  4989.7  194.81
  4993.2  194.81  4993.4  195.31  5011.5  198.91  5073.4  199.79  5232.4  204.39
  5423.2  211.26    5591  216.02  5603.9  215.57    5624  216.83  5660.1  217.65
#Mann= 6 ,-1 , 0
  4378.3     .05       0  4418.9     .12       0  4921.1     .05       0
  4989.4     .05       0  4993.4     .05       0  5073.4     .12       0
#XS Ineff= 2 , 0
       0    4950     204    5030       0     204
Permanent Ineff=
       F       F
Bank Sta=4989.4,4993.4
XS Rating Curve= 0 ,0
Exp/Cntr=0.3,0.1

Type RM Length L Ch R = 1 ,1062    ,188,188,188
BEGIN DESCRIPTION:
Mapping XS 238c71e2
END DESCRIPTION:
XS GIS Cut Line= 3
      2559954.94     13565374.29      2559709.72     13564788.35
      2559053.48     13564649.74
#Sta/Elev= 30
  4366.1  218.45    4387  218.46    4404  217.36  4527.9  213.76  4533.8  213.03
    4563  212.34    4652  208.34  4745.8  203.61  4769.6  203.02    4788  203.41
  4798.9  202.32  4809.8  202.28  4822.6  200.66  4868.2   199.8  4976.2  197.79
  4994.1  197.08    5000  195.84  5014.3  195.21  5014.6  194.71  5018.1  194.71
  5018.3  195.21  5026.5  196.89  5077.6  197.32  5091.5   196.8  5128.8  199.12
  5210.5  200.51  5455.8  208.22  5547.8  209.83  5588.7  211.31    5672  212.44
#Mann= 5 ,-1 , 0
  4366.1     .12       0    4652     .05       0  4868.2     .12       0
  5014.3     .05       0  5018.3     .12       0
#XS Ineff= 2 , 0
       0    4980     203    5050       0     203
Permanent Ineff=
       F       F
Bank Sta=5014.3,5018.3
XS Rating Curve= 0 ,0
Exp/Cntr=0.3,0.1

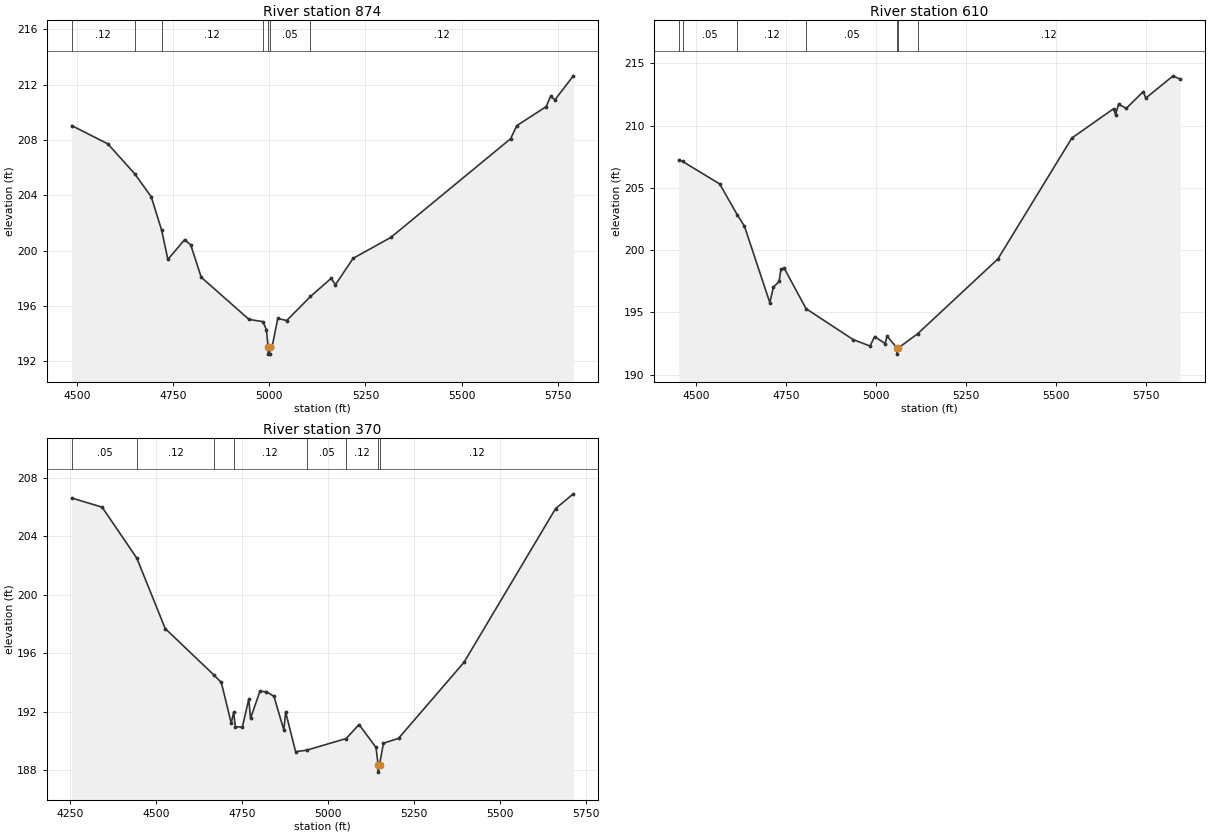
Type RM Length L Ch R = 1 ,874     ,264,264,264
BEGIN DESCRIPTION:
LGII3117
END DESCRIPTION:
XS GIS Cut Line= 3
       2560063.5     13565086.16      2559811.64     13564638.32
      2559091.14     13564312.85
#Sta/Elev= 30
  4486.2  209.04    4580  207.72  4649.5  205.57  4692.8   203.9  4719.9  201.48
  4736.2  199.36  4779.5  200.78  4795.5  200.42  4822.9  198.07  4947.2  195.02
  4983.3  194.86  4992.3  194.29    4997  193.01  4997.3  192.51  5000.8  192.51
    5001  193.01  5007.3  193.06    5022  195.09  5045.1  194.94    5107  196.68
  5160.7  197.99  5171.9  197.53  5217.9  199.44  5315.9  200.95  5627.4  208.09
  5643.7  209.04  5719.8  210.41  5731.5  211.16  5742.5   210.9  5790.6  212.64
#Mann= 7 ,-1 , 0
  4486.2     .12       0  4649.5     .05       0  4719.9     .12       0
  4983.3     .05       0    4997     .05       0    5001     .05       0
    5107     .12       0
Bank Sta=4997,5001
XS Rating Curve= 0 ,0
Exp/Cntr=0.3,0.1

Type RM Length L Ch R = 1 ,610     ,240,240,240
BEGIN DESCRIPTION:
4873
END DESCRIPTION:
XS GIS Cut Line= 3
        2560063.      13564996.3      2559998.26     13564451.73
      2559216.14     13564130.55
#Sta/Elev= 30
  4451.6  207.25  4462.4  207.12  4565.2  205.32    4614  202.85  4634.2  201.92
  4704.7  195.78  4714.7  197.02  4730.5  197.48  4735.5  198.45  4744.9  198.53
  4805.5  195.29  4936.3  192.81  4983.4  192.29  4995.8  193.05  5025.1  192.49
  5030.7  193.08  5058.1  192.14  5058.3  191.64  5062.1  192.14  5115.3  193.27
  5338.6  199.29    5544     209  5660.1  211.36  5665.5  210.88  5673.8  211.71
  5695.4  211.39  5742.8  212.74  5749.4  212.21  5825.6     214  5845.5  213.72
#Mann= 7 ,-1 , 0
  4451.6     .12       0  4462.4     .05       0    4614     .12       0
  4805.5     .05       0  5058.1     .05       0  5062.1     .05       0
  5115.3     .12       0
Bank Sta=5058.1,5062.1
XS Rating Curve= 0 ,0
Exp/Cntr=0.3,0.1

Type RM Length L Ch R = 1 ,370     ,0,0,0
BEGIN DESCRIPTION:
LGII3116
END DESCRIPTION:
XS GIS Cut Line= 4
      2560098.38     13565001.46      2560222.96     13564378.52
      2560068.48     13564109.43      2559600.07     13563900.14
#Sta/Elev= 30
  4255.2  206.61  4343.4  205.99  4444.6  202.49  4526.9  197.68    4669  194.49
  4690.1  193.99    4719   191.2    4726  191.95  4730.9  190.96  4751.3  190.93
    4770  192.85  4775.1  191.53  4802.3  193.38    4821  193.36  4843.1  193.04
    4872  190.73  4877.1  191.97  4906.1  189.25  4938.1  189.35  5053.3  190.15
  5090.6  191.11  5139.9  189.54  5146.2  188.35  5146.5  187.85  5150.2  188.35
  5161.5  189.83  5205.4  190.16  5395.9  195.37  5662.1  205.89  5713.8   206.9
#Mann= 8 ,-1 , 0
  4255.2     .05       0  4444.6     .12       0    4669     .05       0
    4726     .12       0  4938.1     .05       0  5053.3     .12       0
  5146.2     .05       0  5150.2     .12       0
Bank Sta=5146.2,5150.2
XS Rating Curve= 0 ,0
Exp/Cntr=0.3,0.1

Chan Stop Cuts=-1
Use User Specified Reach Order=0
Composite Channel Slope=5