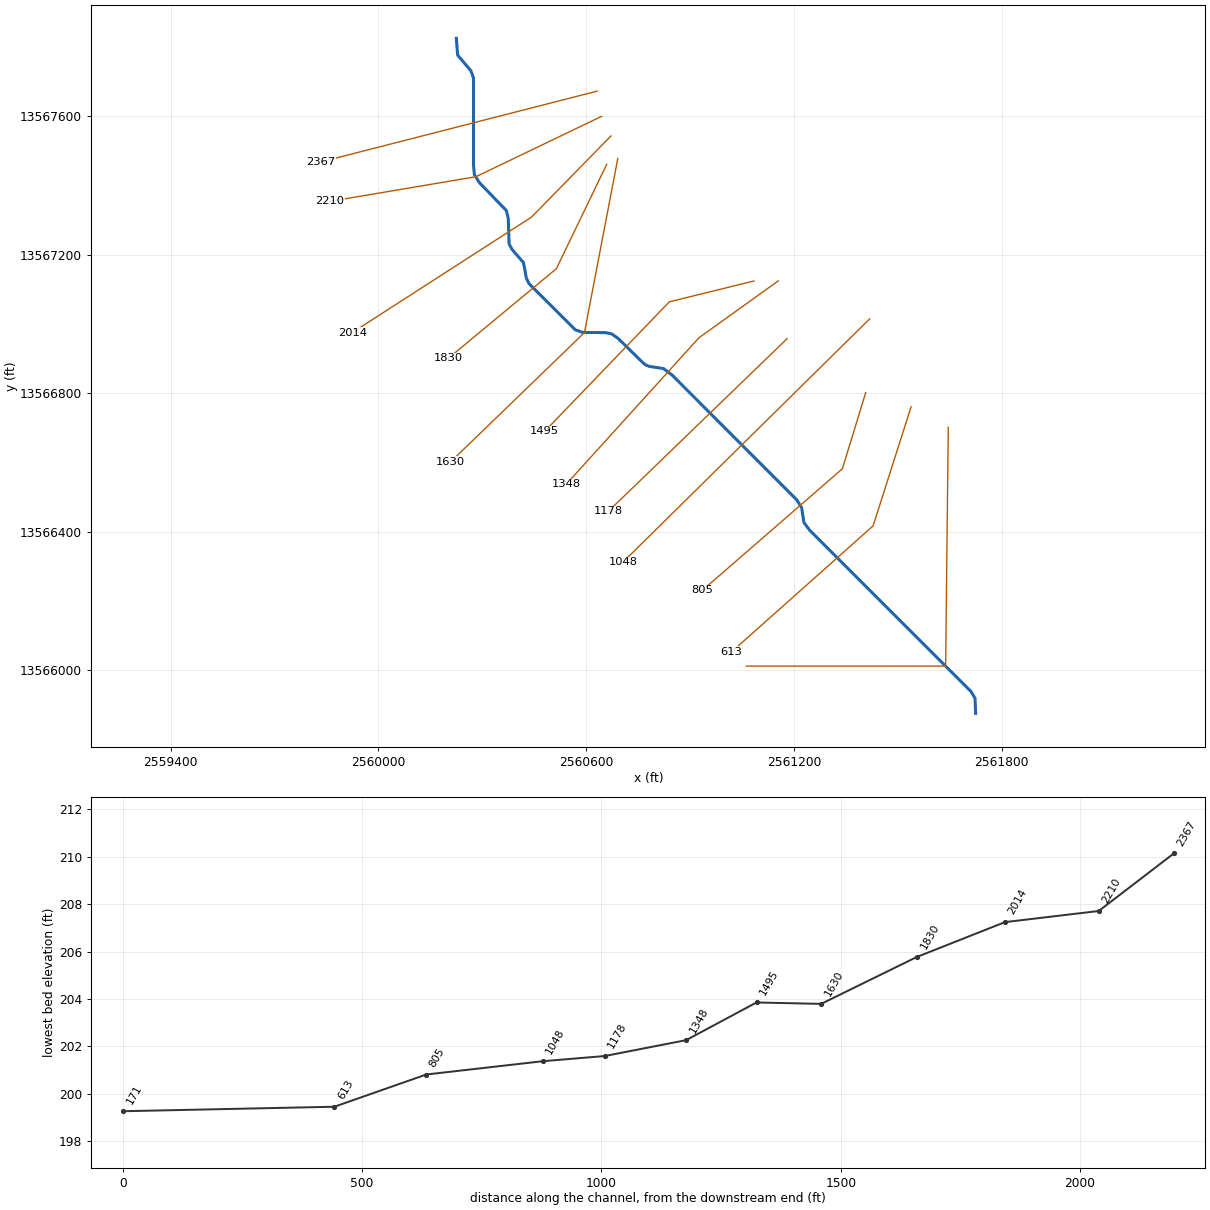
--- TRIB 6_4 TO PRICE CREEK.prj (project) ---

Proj Title=TRIB 6_4 TO PRICE CREEK Base Level Engineering
Current Plan=p01
Default Exp/Contr=0.3,0.1
English Units
Geom File=g01
Flow File=f01
Plan File=p01
Y Axis Title=Elevation
X Axis Title(PF)=Main Channel Distance
X Axis Title(XS)=Station
BEGIN DESCRIPTION:
TRIB 6_4 TO PRICE CREEK
END DESCRIPTION:
DSS Export Rating Curves= 0
DSS Export Rating Curve Sorted= 0
DSS Export Volume Flow Curves= 0
DXF OffsetX= 0
DXF OffsetY= 0
DXF ScaleX= 1
DXF ScaleY= 10

--- TRIB 6_4 TO PRICE CREEK.p01 (plan) ---

Plan Title=Multiple Run
Program Version=4.10
Short Identifier=Multiple
Geom File=g01
Flow File=f01
Subcritical Flow
K Sum by GR= 0
Std Step Tol= 0.01
Critical Tol= 0.01
Num of Std Step Trials= 20
Max Error Tol= 0.3
Flow Tol Ratio= 0.001
Split Flow NTrial= 30
Split Flow Tol= 0.02
Split Flow Ratio= 0.02
Log Output Level= 0
Friction Slope Method= 1
Unsteady Friction Slope Method= 2
Unsteady Bridges Friction Slope Method= 1
Parabolic Critical Depth
Global Vel Dist= 1 , 1 , 1
Global Log Level= 0
CheckData=True
Encroach Param=-1 ,0,0, 0
BEGIN DESCRIPTION:
Multiple Run
END DESCRIPTION:
Computation Interval=1HOUR
Output Interval=1HOUR
Run HTab= 0
Run UNet= 0
Run PostProcess= 0
Run WQNet= 0
UNET Theta= 1
UNET Theta Warmup= 1
UNET ZTol= 0.02
UNET ZSATol= 0.05
UNET MxIter= 20
UNET MaxInSteps= 0
UNET DtIC= 0
UNET DtMin= 0
UNET MaxCRTS= 20
UNET WFStab= 2
UNET SFStab= 1
UNET WFX= 1
UNET SFX= 1
UNET DSS MLevel= 4
UNET DZMax Abort= 100
UNET Convert EG Bridges= 0
UNET Use Existing IB Tables=-1
UNET Froude Reduction=False
UNET Froude Limit= 1
UNET Froude Power= 10
UNET Time Slicing=0,0, 5
UNET Junction Losses=0
Instantaneous Interval=1HOUR
Write IC File= 0
Write IC File at Sim End=0
Echo Input=False
Echo Parameters=False
Echo Output=False
Write Detailed= 0
WQ AD Non Conservative
WQ ULTIMATE=-1
WQ Max Comp Step=1HOUR
WQ Output Interval=15MIN
WQ Output Selected Increments= 0
WQ Output face flow=0
WQ Output face velocity=0
WQ Output face area=0
WQ Output face dispersion=0
WQ Output cell volume=0
WQ Output cell surface area=0
WQ Output cell continuity=0
WQ Output cumulative cell continuity=0
WQ Output face conc=0
WQ Output face dconc_dx=0
WQ Output face courant=0
WQ Output face peclet=0
WQ Output face adv mass=0
WQ Output face disp mass=0
WQ Output cell mass=0
WQ Output cell source sink temp=0
WQ Output cell source sink nsm=0
WQ Output MaxMinRange=-1
WQ Daily Max Min Mean=-1
WQ Daily Range=0
WQ Daily Time=0
WQ Create Restart=0
WQ Fixed Restart=0
WQ System Summary=0
WQ Use Fixed Temperature=0
Sorting and Armoring Iterations= 10
XS Update Threshold= 0.02
Hydraulics Update Threshold= 0.02
Energy Slope Method= 1
Volume Change Method= 0
XS Weighting Method= 0
Number of US Weighted Cross Sections= 1
Number of DS Weighted Cross Sections= 1
Upstream XS Weight=0.25
Main XS Weight=0.5
Downstream XS Weight=0.25
Number of DS XS's Weighted with US Boundary= 1
Upstream Boundary Weight= 1
Weight of XSs Associated with US Boundary= 0
Number of US XS's Weighted with DS Boundary= 1
Downstream Boundary Weight= 0.5
Weight of XSs Associated with DS Boundary= 0.5
Sediment Output Level= 4
Mass or Volume Output= 0
Output Increment Type= 1
Profile and TS Output Increment= 10
XS Output Flag= 0
XS Output Increment= 10
Disregard all LS=0
Disregard all Conn=0
Disregard all Breaches=0
Disregard all Pumps=0

--- TRIB 6_4 TO PRICE CREEK.f01 (steady flow) ---

Flow Title=Multiple
Number of Profiles=7
Profile Names=10-year,25-year,50-year,1pct_min,100-year,1pct_plu,500-year
River Rch & RM= TRIB 6_4 TO PRIC,Reach-1,2367
     262     392     501     311     621    1239     941
Boundary for River Rch & Prof#=TRIB 6_4 TO PRIC,Reach-1,1
Up Type=0
Dn Type=3
Dn Slope=0.005
Boundary for River Rch & Prof#=TRIB 6_4 TO PRIC,Reach-1,2
Up Type=0
Dn Type=3
Dn Slope=0.005
Boundary for River Rch & Prof#=TRIB 6_4 TO PRIC,Reach-1,3
Up Type=0
Dn Type=3
Dn Slope=0.005
Boundary for River Rch & Prof#=TRIB 6_4 TO PRIC,Reach-1,4
Up Type=0
Dn Type=3
Dn Slope=0.005
Boundary for River Rch & Prof#=TRIB 6_4 TO PRIC,Reach-1,5
Up Type=0
Dn Type=3
Dn Slope=0.005
Boundary for River Rch & Prof#=TRIB 6_4 TO PRIC,Reach-1,6
Up Type=0
Dn Type=3
Dn Slope=0.005
Boundary for River Rch & Prof#=TRIB 6_4 TO PRIC,Reach-1,7
Up Type=0
Dn Type=3
Dn Slope=0.005

--- TRIB 6_4 TO PRICE CREEK.g01 (geometry) ---

Geom Title=Existing Conditions
Program Version=4.10

River Reach=TRIB 6_4 TO PRIC,Reach-1
Reach XY= 30
        2560225.       13567825.      2560228.65     13567776.51
      2560267.11     13567731.16      2560274.55     13567709.81
      2560274.51      13567459.8      2560277.07     13567430.86
      2560291.47     13567408.25      2560369.46     13567327.42
      2560374.87     13567304.95      2560377.33     13567230.97
      2560385.84     13567215.35      2560418.86     13567177.17
       2560427.5     13567131.03      2560435.76     13567115.32
      2560568.83     13566982.86      2560590.22     13566975.53
      2560654.94     13566974.86       2560673.5     13566971.37
      2560691.74     13566958.51      2560768.96     13566883.18
      2560781.05     13566877.54      2560823.35     13566871.03
      2560848.47     13566851.99      2561208.35     13566491.67
      2561222.47     13566468.95      2561228.98     13566426.65
      2561244.79     13566404.91      2561711.53     13565938.27
      2561723.32     13565918.86        2561725.       13565875.

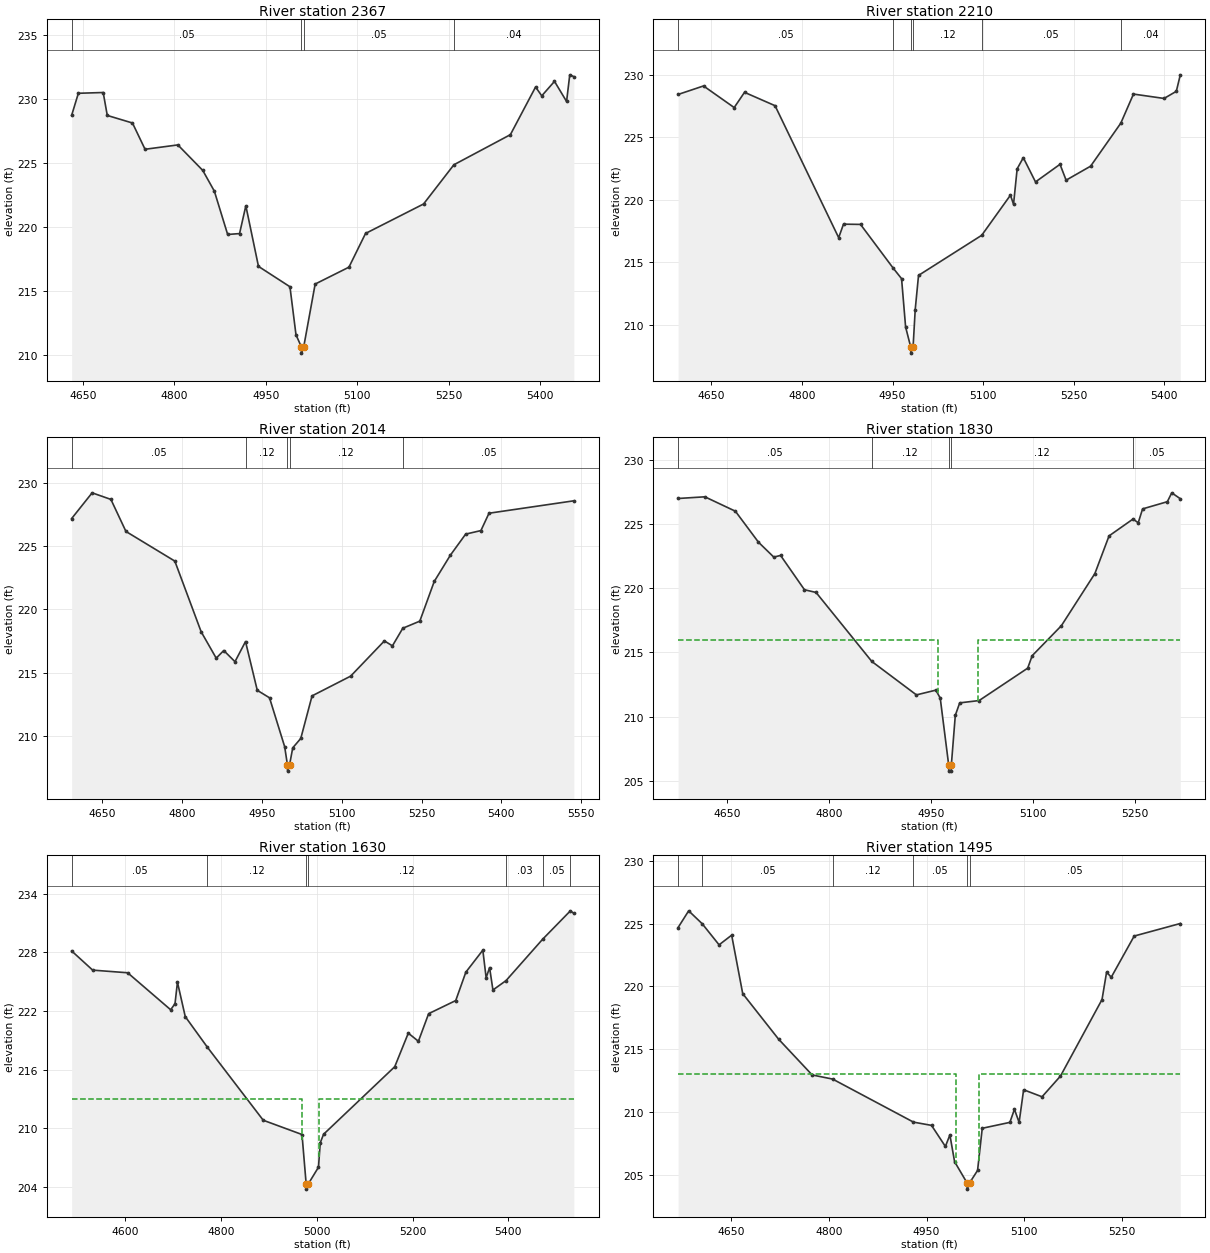
Type RM Length L Ch R = 1 ,2367    ,157,157,157
BEGIN DESCRIPTION:
LGII3115
END DESCRIPTION:
XS GIS Cut Line= 2
      2560631.58     13567672.47      2559834.24     13567468.15
#Sta/Elev= 30
  4631.9   228.7  4642.9  230.42  4683.6  230.48  4690.3  228.69  4731.6   228.1
  4752.2  226.05    4806  226.39  4846.8   224.4  4865.8  222.78  4887.6   219.4
  4907.1  219.47  4917.4  221.64  4938.1  216.91  4989.7  215.32  4999.6  211.57
  5008.3  210.64  5008.6  210.14  5012.3  210.64    5031  215.53  5086.4  216.85
  5113.6  219.48  5208.7  221.78  5258.4  224.84    5351  227.19  5392.3  230.91
  5402.4  230.22  5423.3  231.35  5443.1  229.78  5448.3  231.86    5455  231.72
#Mann= 4 ,-1 , 0
  4631.9     .05       0  5008.3     .05       0  5012.3     .05       0
  5258.4     .04       0
Bank Sta=5008.3,5012.3
XS Rating Curve= 0 ,0
Exp/Cntr=0.3,0.1

Type RM Length L Ch R = 1 ,2210    ,196,196,196
BEGIN DESCRIPTION:
Mapping XS 398a5b2c
END DESCRIPTION:
XS GIS Cut Line= 3
      2560644.77     13567599.73      2560281.46     13567425.23
      2559858.48     13567353.87
#Sta/Elev= 30
  4594.8  228.41  4636.9  229.09  4687.7  227.36  4704.8  228.58  4755.4  227.51
  4860.8  216.95  4868.8  218.03    4897  218.01  4951.3   214.5    4965  213.67
  4971.7   209.8  4980.1  208.21  4980.3  207.71  4984.1  208.21  4987.6  211.19
  4993.1  213.93  5097.8  217.14  5145.4  220.35  5150.5  219.62  5156.5  222.46
  5166.7  223.35  5186.9  221.41  5227.5  222.82  5237.6  221.55  5278.2  222.67
  5328.2  226.11  5349.2  228.44  5399.9  228.09  5420.2  228.66  5426.8  229.98
#Mann= 6 ,-1 , 0
  4594.8     .05       0  4951.3     .12       0  4980.1     .05       0
  4984.1     .12       0  5097.8     .05       0  5328.2     .04       0
Bank Sta=4980.1,4984.1
XS Rating Curve= 0 ,0
Exp/Cntr=0.3,0.1

Type RM Length L Ch R = 1 ,2014    ,184,184,184
BEGIN DESCRIPTION:
LGII3114
END DESCRIPTION:
XS GIS Cut Line= 3
      2560671.47     13567542.92      2560442.23     13567308.69
        2559924.     13566974.83
#Sta/Elev= 30
  4592.2  227.18  4630.7  229.21    4666  228.69  4694.3  226.16  4786.2  223.82
  4835.7  218.24    4864  216.16  4878.2  216.76  4899.3  215.88  4919.1  217.47
  4941.2  213.62  4964.2  213.03  4992.7  209.17  4997.9  207.74  4998.2  207.24
  5001.9  207.74  5007.9  209.08    5023  209.82  5044.2  213.18  5116.8  214.74
  5180.2  217.52  5195.3  217.13  5214.8  218.52  5246.8  219.08  5273.9  222.21
  5304.3  224.29    5333  225.95  5361.7  226.23  5376.9   227.6  5536.4  228.58
#Mann= 5 ,-1 , 0
  4592.2     .05       0  4919.1     .12       0  4997.9     .05       0
  5001.9     .12       0  5214.8     .05       0
Bank Sta=4997.9,5001.9
XS Rating Curve= 0 ,0
Exp/Cntr=0.3,0.1

Type RM Length L Ch R = 1 ,1830    ,200,200,200
BEGIN DESCRIPTION:
4875
END DESCRIPTION:
XS GIS Cut Line= 3
      2560659.31     13567460.98      2560513.92     13567159.56
      2560201.87      13566900.7
#Sta/Elev= 30
  4577.4  226.98  4616.8  227.11  4661.8  225.99  4695.8  223.58  4718.4  222.42
  4728.4  222.55  4763.6  219.88  4780.7  219.67  4862.9   214.3  4928.6   211.7
  4957.2  212.07  4963.7  211.45  4976.1  206.27  4976.3  205.77  4979.8  205.77
  4980.1  206.27  4985.9  210.11  4992.4  211.08    5021  211.26  5092.6  213.78
  5099.2  214.75  5142.2  217.08  5191.6  221.14  5212.5  224.07  5247.8  225.38
  5255.5  225.09  5261.9  226.17  5298.4  226.73  5304.9  227.42  5317.5  226.96
#Mann= 5 ,-1 , 0
  4577.4     .05       0  4862.9     .12       0  4976.1     .05       0
  4980.1     .12       0  5247.8     .05       0
#XS Ineff= 2 , 0
       0    4960     216    5020       0     216
Permanent Ineff=
       F       F
Bank Sta=4976.1,4980.1
XS Rating Curve= 0 ,0
Exp/Cntr=0.3,0.1

Type RM Length L Ch R = 1 ,1630    ,135,135,135
BEGIN DESCRIPTION:
LGII3113
END DESCRIPTION:
XS GIS Cut Line= 3
      2560691.39     13567478.09      2560595.05     13566975.13
      2560208.99     13566602.01
#Sta/Elev= 30
  4487.9  228.13  4531.8  226.17  4604.9   225.9  4694.7  222.12  4703.8  222.74
  4708.9  224.94  4725.2  221.42  4771.3   218.3  4888.1  210.83  4969.1  209.37
  4977.8  204.29    4978  203.79  4981.8  204.29  5003.5  206.03  5007.2  208.53
  5014.2   209.4  5162.8   216.3  5191.1  219.73  5212.2   218.9  5233.6  221.72
  5290.2  223.06  5311.3  225.96  5346.8  228.21  5353.7  225.39  5360.9  226.43
  5367.9  224.14  5395.3   225.1  5471.6  229.32  5529.7  232.23  5536.9  231.97
#Mann= 7 ,-1 , 0
  4487.9     .05       0  4771.3     .12       0  4977.8     .05       0
  4981.8     .12       0  5395.3     .03       0  5471.6     .05       0
  5529.7     .03       0
#XS Ineff= 2 , 0
       0    4970     213    5005       0     213
Permanent Ineff=
       F       F
Bank Sta=4977.8,4981.8
XS Rating Curve= 0 ,0
Exp/Cntr=0.3,0.1

Type RM Length L Ch R = 1 ,1495    ,147,147,147
BEGIN DESCRIPTION:
4874
END DESCRIPTION:
XS GIS Cut Line= 3
      2561084.81     13567124.11      2560840.14     13567063.83
       2560480.2     13566689.77
#Sta/Elev= 30
  4568.6   224.7  4584.8  226.03  4605.6     225  4631.5  223.32  4650.8  224.09
  4667.8  219.43  4722.9   215.8  4774.4  212.95  4805.9  212.62    4930  209.19
  4957.7  208.93    4979  207.25  4985.9  208.17  4993.1  206.04  5012.2  204.35
  5012.5  203.85  5016.2  204.35  5028.4  205.34  5035.6   208.7    5078  209.17
    5085  210.21  5092.2  209.17  5099.1  211.77  5127.4  211.21  5155.7  212.86
  5219.5  218.96  5226.5  221.14  5233.7  220.74  5268.9  224.02  5339.7  225.02
#Mann= 6 ,-1 , 0
  4568.6     .12       0  4605.6     .05       0  4805.9     .12       0
    4930     .05       0  5012.2     .05       0  5016.2     .05       0
#XS Ineff= 2 , 0
       0    4995     213    5030       0     213
Permanent Ineff=
       F       F
Bank Sta=5012.2,5016.2
XS Rating Curve= 0 ,0
Exp/Cntr=0.3,0.1

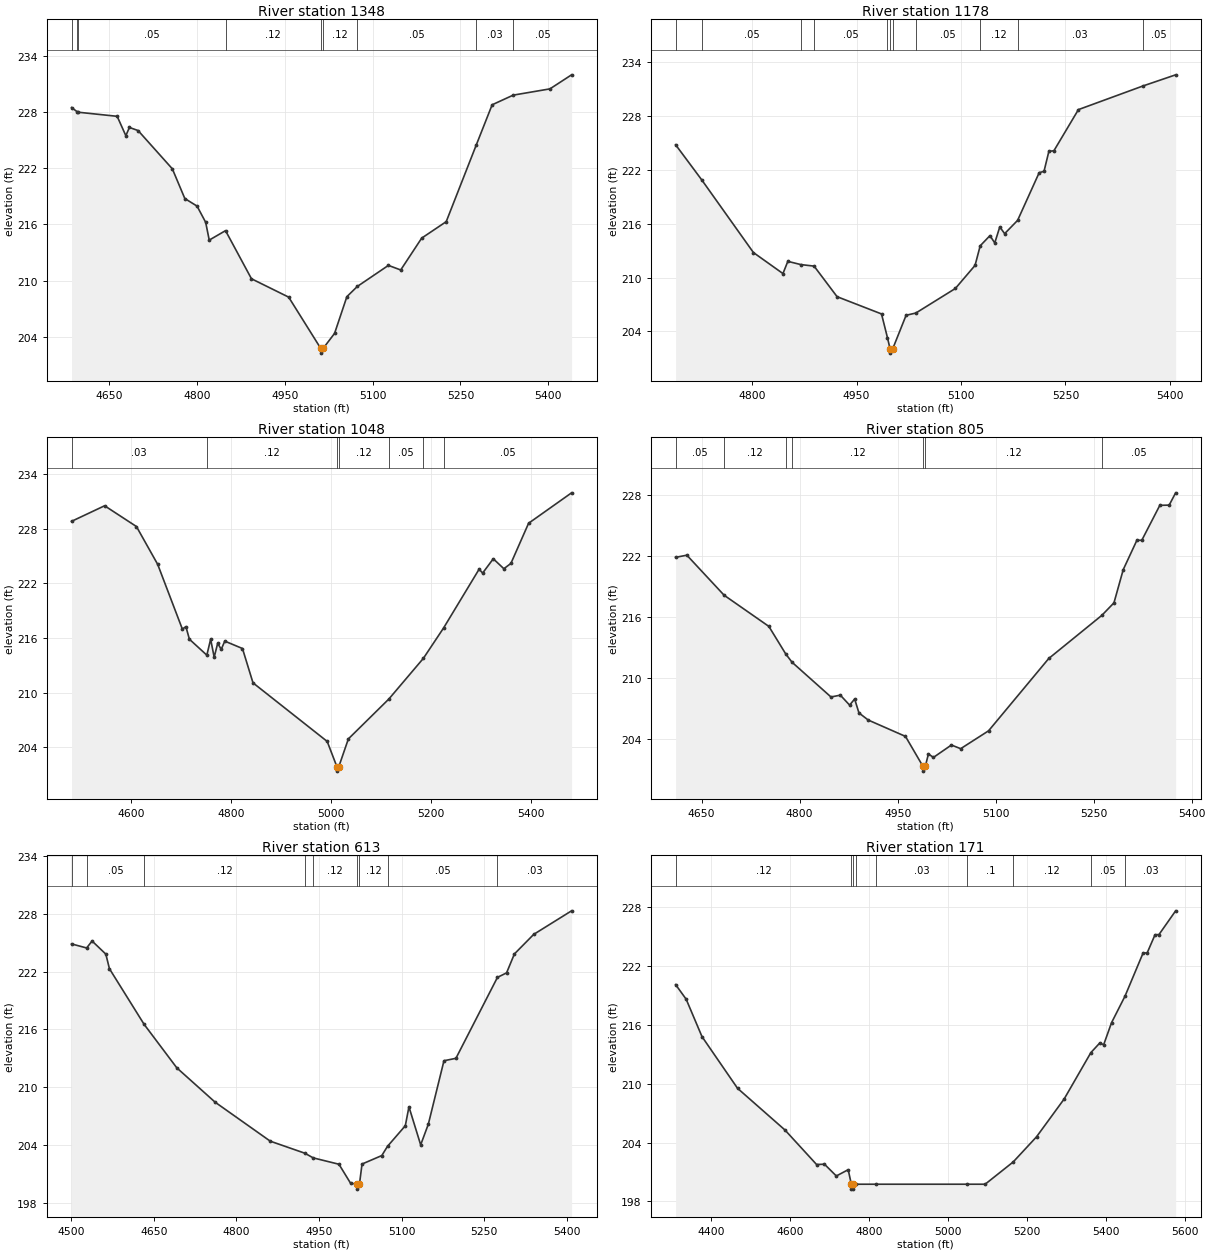
Type RM Length L Ch R = 1 ,1348    ,170,170,170
BEGIN DESCRIPTION:
LGII3112
END DESCRIPTION:
XS GIS Cut Line= 3
      2561154.86     13567124.33      2560925.61     13566959.86
      2560541.89     13566536.28
#Sta/Elev= 30
  4586.1  228.49  4595.2  228.06    4597  227.99    4664  227.55  4678.8  225.48
  4684.9  226.36  4699.7  226.03  4758.2  221.94  4779.5  218.77  4800.4  217.96
  4815.1  216.23  4821.2  214.33    4849  215.34  4893.3   210.2  4956.8  208.24
  5011.6  202.76  5011.8  202.26  5015.6  202.76  5035.2  204.37  5056.2  208.29
    5074  209.38  5127.1  211.63  5148.1  211.14  5183.9  214.54  5225.8   216.3
  5276.8  224.44  5304.2  228.78  5340.1  229.81  5402.9  230.48  5439.8  231.98
#Mann= 9 ,-1 , 0
  4586.1     .03       0  4595.2     .12       0    4597     .05       0
    4849     .12       0  5011.6     .05       0  5015.6     .12       0
    5074     .05       0  5276.8     .03       0  5340.1     .05       0
Bank Sta=5011.6,5015.6
XS Rating Curve= 0 ,0
Exp/Cntr=0.3,0.1

Type RM Length L Ch R = 1 ,1178    ,130,130,130
BEGIN DESCRIPTION:
4876
END DESCRIPTION:
XS GIS Cut Line= 2
      2561180.51     13566957.42      2560664.12     13566458.71
#Sta/Elev= 30
  4690.3  224.77  4728.2  220.82    4802  212.78  4844.4  210.44  4851.4   211.8
  4870.1  211.44  4889.1  211.27  4922.1  207.87  4985.9  205.95  4994.5  203.29
  4998.1  202.09  4998.3  201.59  5002.1  202.09  5021.2   205.8  5035.2  206.05
  5091.9  208.78  5120.2  211.35  5127.6  213.53  5141.6  214.66  5148.5  213.85
  5155.7  215.63  5162.7  214.88  5181.3  216.36  5212.3  221.67  5219.2  221.81
  5226.2  224.04  5233.4   224.1  5268.6  228.68  5360.9   231.3  5408.2  232.55
#Mann= 11 ,-1 , 0
  4690.3     .03       0  4728.2     .05       0  4870.1     .12       0
  4889.1     .05       0  4994.5     .12       0  4998.1     .05       0
  5002.1     .12       0  5035.2     .05       0  5127.6     .12       0
  5181.3     .03       0  5360.9     .05       0
Bank Sta=4998.1,5002.1
XS Rating Curve= 0 ,0
Exp/Cntr=0.3,0.1

Type RM Length L Ch R = 1 ,1048    ,243,243,243
BEGIN DESCRIPTION:
LGII3111
END DESCRIPTION:
XS GIS Cut Line= 2
      2561418.98     13567014.71      2560706.34     13566312.04
#Sta/Elev= 30
  4481.2  228.79  4547.4   230.5  4611.1  228.22  4653.6  224.07    4703  216.96
  4710.1  217.23  4717.1  215.85    4752   214.1  4759.6  215.85  4766.7  213.88
  4773.7   215.4  4780.8  214.74  4787.9  215.64  4823.3  214.83  4844.4  211.06
  4992.9  204.63  5012.2  201.87  5012.4  201.37  5016.2  201.87  5035.3  204.91
  5116.4  209.29  5185.4  213.75  5225.8  217.08    5297  223.54    5304  223.11
  5325.3  224.68  5346.5  223.59  5360.6  224.17    5396  228.58    5482  231.92
#Mann= 7 ,-1 , 0
  4481.2     .03       0    4752     .12       0  5012.2     .05       0
  5016.2     .12       0  5116.4     .05       0  5185.4     .12       0
  5225.8     .05       0
Bank Sta=5012.2,5016.2
XS Rating Curve= 0 ,0
Exp/Cntr=0.3,0.1

Type RM Length L Ch R = 1 ,805     ,192,192,192
BEGIN DESCRIPTION:
4877
END DESCRIPTION:
XS GIS Cut Line= 3
      2561407.47     13566801.42      2561340.11     13566581.59
      2560935.88     13566230.55
#Sta/Elev= 30
  4610.2  221.86  4627.4  222.07  4684.4  218.13  4752.9  215.06  4778.8  212.34
  4788.4  211.53    4848  208.11  4862.3  208.29  4876.5  207.31  4884.2  207.91
  4890.8  206.54    4905  205.84    4962  204.23  4988.5  201.31  4988.8  200.81
  4992.5  201.31  4997.1   202.5  5004.8  202.16  5032.3  203.38  5046.5  203.02
  5089.2  204.78  5181.3   211.9  5262.6  216.15  5281.1  217.38  5295.3  220.65
  5316.2  223.54  5323.7  223.54  5351.3  226.98  5365.6     227  5375.5  228.21
#Mann= 7 ,-1 , 0
  4610.2     .05       0  4684.4     .12       0  4778.8     .05       0
  4788.4     .12       0  4988.5     .05       0  4992.5     .12       0
  5262.6     .05       0
Bank Sta=4988.5,4992.5
XS Rating Curve= 0 ,0
Exp/Cntr=0.3,0.1

Type RM Length L Ch R = 1 ,613     ,442,442,442
BEGIN DESCRIPTION:
LGII3110
END DESCRIPTION:
XS GIS Cut Line= 3
      2561538.56     13566760.57      2561428.92     13566416.69
      2561020.31     13566052.93
#Sta/Elev= 30
  4500.5  224.87  4527.9  224.45  4537.8  225.17  4562.8  223.81  4569.3   222.3
  4632.2  216.54  4691.7  212.02  4761.3  208.46  4861.4  204.42  4924.3  203.17
  4939.3  202.69  4986.1  202.03  5007.1  200.07  5019.3  199.95  5019.5  199.45
  5023.3  199.95    5028  202.05  5063.9  202.93  5074.3  203.89  5106.6  206.02
  5113.2  207.98  5134.5  204.04  5148.4  206.18  5176.8  212.76  5198.5  213.01
  5273.9   221.4  5290.5  221.87  5304.7  223.83  5339.8  225.86  5408.5   228.3
#Mann= 9 ,-1 , 0
  4500.5     .03       0  4527.9     .05       0  4632.2     .12       0
  4924.3     .05       0  4939.3     .12       0  5019.3     .05       0
  5023.3     .12       0  5074.3     .05       0  5273.9     .03       0
Bank Sta=5019.3,5023.3
XS Rating Curve= 0 ,0
Exp/Cntr=0.3,0.1

Type RM Length L Ch R = 1 ,171     ,0,0,0
BEGIN DESCRIPTION:
LGII3109
END DESCRIPTION:
XS GIS Cut Line= 3
      2561646.04     13566701.73      2561638.35     13566011.68
      2561062.75      13566011.6
#Sta/Elev= 30
  4309.9  220.11  4336.6  218.62  4376.6  214.81  4466.6  209.54  4586.6  205.29
  4666.7  201.77  4686.7   201.8  4716.7   200.6  4746.7  201.24  4754.7  199.76
  4754.9  199.26  4758.4  199.26  4758.7  199.76  4766.8  199.76  4817.6  199.76
  5048.5  199.76  5093.4  199.76  5164.4  202.03  5223.4  204.59  5293.4  208.45
  5361.1  213.18  5383.4  214.15  5393.4  213.98  5413.4  216.23  5447.4  218.93
  5493.4  223.35  5503.4  223.33  5523.4  225.19  5533.4  225.21  5575.6  227.63
#Mann= 9 ,-1 , 0
  4309.9     .12       0  4754.7     .03       0  4758.7     .12       0
  4766.8      .1       0  4817.6     .03       0  5048.5      .1       0
  5164.4     .12       0  5361.1     .05       0  5447.4     .03       0
Bank Sta=4754.7,4758.7
XS Rating Curve= 0 ,0
Exp/Cntr=0.3,0.1

Chan Stop Cuts=-1
Use User Specified Reach Order=0
Composite Channel Slope=5