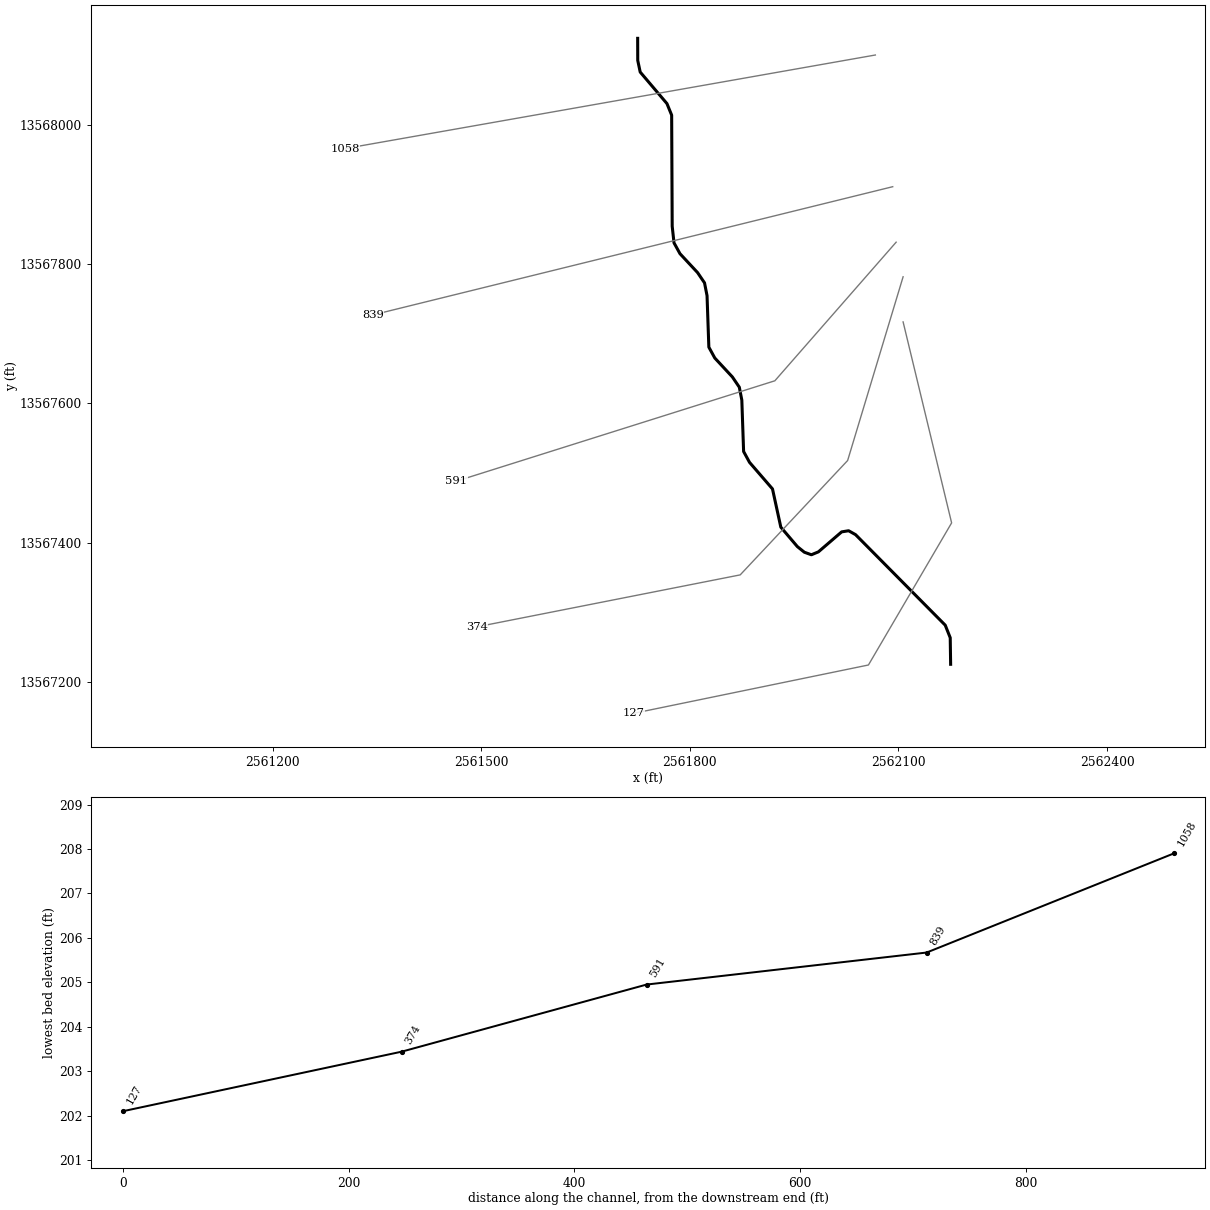
--- TRIB 6_5 TO PRICE CREEK.prj (project) ---

Proj Title=TRIB 6_5 TO PRICE CREEK Base Level Engineering
Current Plan=p01
Default Exp/Contr=0.3,0.1
English Units
Geom File=g01
Flow File=f01
Plan File=p01
BEGIN DESCRIPTION:
TRIB 6_5 TO PRICE CREEK
END DESCRIPTION:

--- TRIB 6_5 TO PRICE CREEK.p01 (plan) ---

Plan Title=Multiple Run
Short Identifier=Multiple
Geom File=g01
Flow File=f01
Subcritical Flow
K Sum by GR= 0
Std Step Tol= 0.01
Critical Tol= 0.01
Num of Std Step Trials= 20
Max Error Tol= 0.3
Flow Tol Ratio= 0.001
Split Flow NTrial= 30
Split Flow Tol= 0.02
Split Flow Ratio= 0.02
Log Output Level= 0
Friction Slope Method= 1
Unsteady Friction Slope Method= 2
Unsteady Bridges Friction Slope Method= 1
Parabolic Critical Depth
Global Vel Dist=  1 , 1 , 1
Global Log Level= 0
CheckData=True
Encroach Param= -1, 0, 0, 0
BEGIN DESCRIPTION:
Multiple Run
END DESCRIPTION:

--- TRIB 6_5 TO PRICE CREEK.f01 (steady flow) ---

Flow Title=Multiple
Number of Profiles=7
Profile Names=10-year,25-year,50-year,1pct_min,100-year,1pct_plu,500-year
River Rch & RM= TRIB 6_5 TO PRIC,Reach-1,1058
     218     322     409     253     504    1006     755
Boundary for River Rch & Prof#=TRIB 6_5 TO PRIC,Reach-1,1
Up Type=0
Dn Type=3
Dn Slope=0.005
Boundary for River Rch & Prof#=TRIB 6_5 TO PRIC,Reach-1,2
Up Type=0
Dn Type=3
Dn Slope=0.005
Boundary for River Rch & Prof#=TRIB 6_5 TO PRIC,Reach-1,3
Up Type=0
Dn Type=3
Dn Slope=0.005
Boundary for River Rch & Prof#=TRIB 6_5 TO PRIC,Reach-1,4
Up Type=0
Dn Type=3
Dn Slope=0.005
Boundary for River Rch & Prof#=TRIB 6_5 TO PRIC,Reach-1,5
Up Type=0
Dn Type=3
Dn Slope=0.005
Boundary for River Rch & Prof#=TRIB 6_5 TO PRIC,Reach-1,6
Up Type=0
Dn Type=3
Dn Slope=0.005
Boundary for River Rch & Prof#=TRIB 6_5 TO PRIC,Reach-1,7
Up Type=0
Dn Type=3
Dn Slope=0.005

--- TRIB 6_5 TO PRICE CREEK.g01 (geometry) ---

Geom Title=Existing Conditions

River Reach=TRIB 6_5 TO PRIC,Reach-1
Reach XY= 30
      2561725.00     13568125.00      2561725.12     13568093.20
      2561728.65     13568076.51      2561767.11     13568031.16
      2561773.88     13568014.54      2561774.65     13567854.85
      2561777.26     13567830.94      2561785.85     13567815.35
      2561811.17     13567788.13      2561821.14     13567773.40
      2561824.76     13567754.90      2561827.35     13567680.97
      2561835.89     13567665.37      2561861.18     13567638.13
      2561871.15     13567623.40      2561874.76     13567604.90
      2561877.33     13567530.96      2561885.84     13567515.34
      2561918.86     13567477.12      2561930.83     13567422.16
      2561954.61     13567394.21      2561964.68     13567386.11
      2561974.79     13567382.47      2561984.87     13567386.65
      2562018.32     13567415.38      2562028.32     13567417.00
      2562038.33     13567411.35      2562167.24     13567281.21
      2562174.41     13567263.16      2562175.00     13567225.00

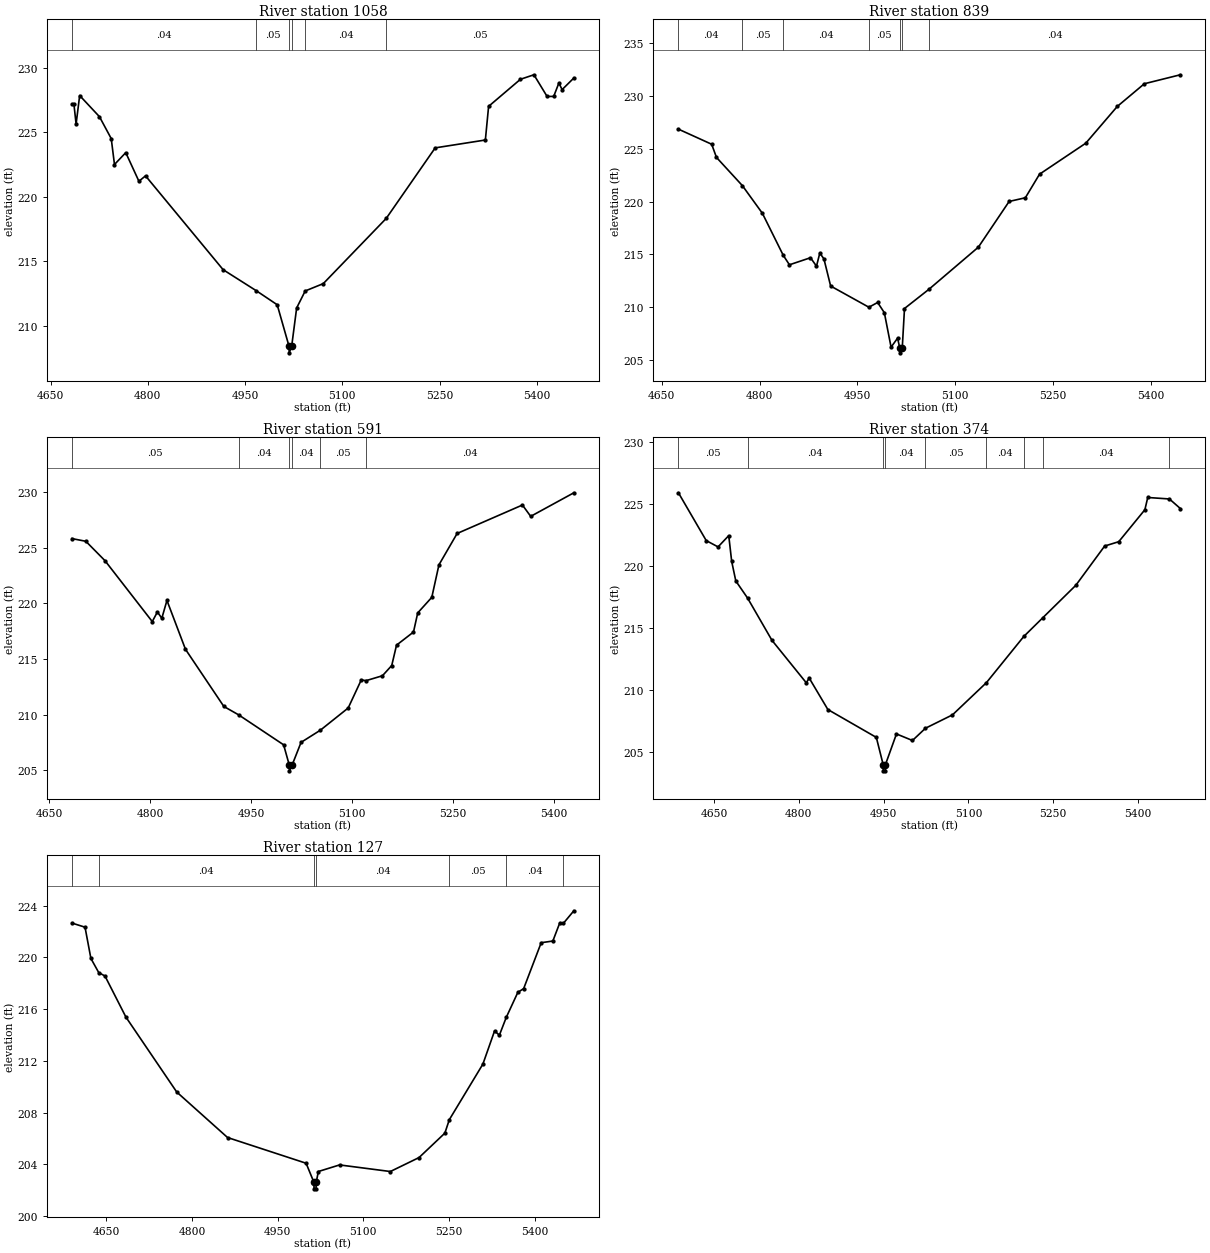
Type RM Length L Ch R = 1,1058,219,219,219
BEGIN DESCRIPTION:
LGII3108
END DESCRIPTION:
XS GIS Cut Line= 2
      2562066.75     13568101.03      2561304.33     13567966.49
#Sta/Elev= 30
  4682.9  227.21  4685.9  227.21  4689.3  225.65  4694.8  227.86  4725.3  226.22
  4743.5  224.52  4748.5  222.51  4765.9  223.43  4786.2  221.21  4796.4  221.63
  4916.1  214.35  4967.2  212.72  4999.5  211.63  5017.8  208.40  5018.0  207.90
  5021.8  208.40  5029.5  211.38  5042.7  212.70  5070.6  213.27  5167.7  218.33
  5243.2  223.80  5320.6  224.41  5325.6  227.02  5374.7  229.12  5395.5  229.47
  5415.8  227.79  5426.0  227.79  5434.0  228.83  5439.0  228.32  5457.1  229.22
#Mann=6,-1,0
  4682.9    0.04       0  4967.2    0.05       0  5017.8    0.05       0
  5021.8    0.05       0  5042.7    0.04       0  5167.7    0.05       0
Bank Sta=5017.8,5021.8
Exp/Cntr=0.3,0.1

Type RM Length L Ch R = 1,839,248,248,248
BEGIN DESCRIPTION:
LGII3107
END DESCRIPTION:
XS GIS Cut Line= 2
      2562091.73     13567911.68      2561344.23     13567727.30
#Sta/Elev= 30
  4675.4  226.86  4726.4  225.43  4733.8  224.18  4773.5  221.51  4804.2  218.89
  4836.2  214.91  4845.7  214.01  4878.0  214.68  4887.2  213.88  4892.3  215.12
  4898.6  214.57  4908.9  212.00  4967.6  209.99  4981.0  210.44  4991.3  209.47
  5001.6  206.21  5011.6  207.06  5014.8  206.17  5015.0  205.67  5018.8  206.17
  5022.2  209.87  5059.7  211.69  5135.5  215.68  5182.7  220.01  5207.6  220.36
  5229.3  222.59  5300.3  225.53  5348.6  229.01  5390.1  231.16  5445.3  232.01
#Mann=7,-1,0
  4675.4    0.04       0  4773.5    0.05       0  4836.2    0.04       0
  4967.6    0.05       0  5014.8    0.05       0  5018.8    0.05       0
  5059.7    0.04       0
Bank Sta=5014.8,5018.8
Exp/Cntr=0.3,0.1

Type RM Length L Ch R = 1,591,217,217,217
BEGIN DESCRIPTION:
LGII3106
END DESCRIPTION:
XS GIS Cut Line= 3
      2562096.65     13567831.91      2561922.26     13567632.61
      2561463.83     13567488.10
#Sta/Elev= 30
  4683.6  225.83  4704.2  225.59  4732.6  223.85  4802.9  218.37  4810.5  219.23
  4817.1  218.67  4824.7  220.27  4852.2  215.88  4909.2  210.74  4931.3  209.98
  4998.0  207.29  5006.5  205.45  5006.7  204.95  5010.5  205.45  5023.9  207.51
  5052.5  208.60  5093.9  210.60  5113.3  213.12  5120.5  213.06  5144.8  213.50
  5158.6  214.42  5165.7  216.25  5190.9  217.43  5197.2  219.15  5218.1  220.55
  5228.7  223.47  5255.7  226.29  5352.7  228.85  5365.0  227.83  5429.1  229.95
#Mann=6,-1,0
  4683.6    0.05       0  4931.3    0.04       0  5006.5    0.04       0
  5010.5    0.04       0  5052.5    0.05       0  5120.5    0.04       0
Bank Sta=5006.5,5010.5
Exp/Cntr=0.3,0.1

Type RM Length L Ch R = 1,374,247,247,247
BEGIN DESCRIPTION:
LGII3105
END DESCRIPTION:
XS GIS Cut Line= 4
      2562106.66     13567782.15      2562026.91     13567517.99
      2561872.43     13567353.54      2561493.69     13567278.79
#Sta/Elev= 30
  4587.2  225.89  4636.4  222.03  4657.3  221.52  4676.2  222.43  4681.4  220.35
  4688.7  218.77  4709.5  217.39  4752.6  213.98  4813.3  210.55  4818.5  210.93
  4851.5  208.39  4937.2  206.14  4949.3  203.94  4949.6  203.44  4953.1  203.44
  4953.3  203.94  4972.8  206.42  5001.1  205.89  5024.1  206.88  5071.9  207.96
  5131.9  210.56  5198.0  214.29  5231.6  215.80  5290.0  218.42  5341.0  221.59
  5365.9  221.94  5412.1  224.52  5417.2  225.51  5455.5  225.39  5474.8  224.62
#Mann=9,-1,0
  4587.2    0.05       0  4709.5    0.04       0  4949.3    0.04       0
  4953.3    0.04       0  5024.1    0.05       0  5131.9    0.04       0
  5198.0    0.05       0  5231.6    0.04       0  5455.5    0.03       0
Bank Sta=4949.3,4953.3
Exp/Cntr=0.3,0.1

Type RM Length L Ch R = 1,127,0,0,0
BEGIN DESCRIPTION:
LGII3104
END DESCRIPTION:
XS GIS Cut Line= 4
      2562106.66     13567717.28      2562176.41     13567428.29
      2562056.81     13567223.98      2561718.93     13567154.41
#Sta/Elev= 30
  4589.8  222.66  4612.7  222.34  4623.0  219.92  4636.7  218.83  4647.7  218.56
  4684.4  215.38  4773.3  209.59  4862.3  206.07  4999.9  204.08  5013.6  202.60
  5013.8  202.10  5017.3  202.10  5017.6  202.60  5021.3  203.44  5058.5  203.95
  5147.4  203.44  5197.7  204.52  5242.9  206.41  5250.7  207.45  5309.5  211.75
  5329.9  214.31  5338.4  213.99  5350.5  215.37  5370.7  217.30  5380.9  217.59
  5411.6  221.14  5432.0  221.27  5444.2  222.68  5450.3  222.63  5468.8  223.61
#Mann=7,-1,0
  4589.8    0.05       0  4636.7    0.04       0  5013.6    0.04       0
  5017.6    0.04       0  5250.7    0.05       0  5350.5    0.04       0
  5450.3    0.03       0
Bank Sta=5013.6,5017.6
Exp/Cntr=0.3,0.1

Chan Stop Cuts=-1