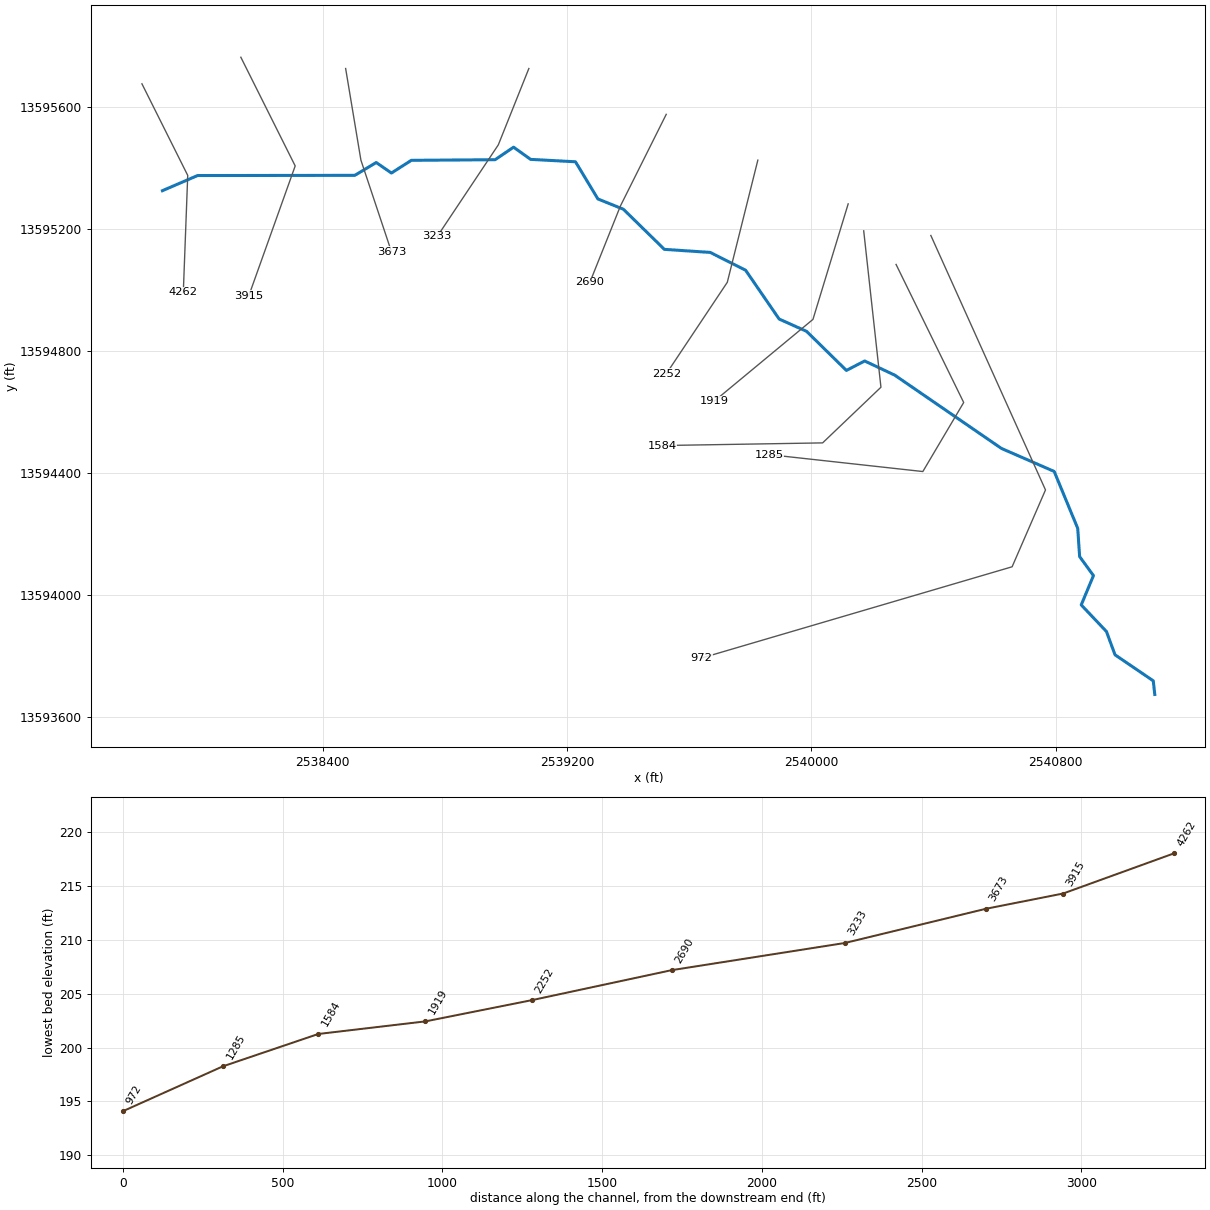
--- TRIB 7 TO IRISH CREEK.prj (project) ---

Proj Title=TRIB 7 TO IRISH CREEK Base Level Engineering
Current Plan=p01
Default Exp/Contr=0.3,0.1
English Units
Geom File=g01
Flow File=f01
Plan File=p01
BEGIN DESCRIPTION:
TRIB 7 TO IRISH CREEK
END DESCRIPTION:

--- TRIB 7 TO IRISH CREEK.p01 (plan) ---

Plan Title=Multiple Run
Short Identifier=Multiple
Geom File=g01
Flow File=f01
Subcritical Flow
K Sum by GR= 0
Std Step Tol= 0.01
Critical Tol= 0.01
Num of Std Step Trials= 20
Max Error Tol= 0.3
Flow Tol Ratio= 0.001
Split Flow NTrial= 30
Split Flow Tol= 0.02
Split Flow Ratio= 0.02
Log Output Level= 0
Friction Slope Method= 1
Unsteady Friction Slope Method= 2
Unsteady Bridges Friction Slope Method= 1
Parabolic Critical Depth
Global Vel Dist=  1 , 1 , 1
Global Log Level= 0
CheckData=True
Encroach Param= -1, 0, 0, 0
BEGIN DESCRIPTION:
Multiple Run
END DESCRIPTION:

--- TRIB 7 TO IRISH CREEK.f01 (steady flow) ---

Flow Title=Multiple
Number of Profiles=7
Profile Names=10-year,25-year,50-year,1pct_min,100-year,1pct_plu,500-year
River Rch & RM= TRIB 7 TO IRISH ,Reach-1,4262
     393     616     812     521    1040    2074    1681
Boundary for River Rch & Prof#=TRIB 7 TO IRISH ,Reach-1,1
Up Type=0
Dn Type=3
Dn Slope=0.005
Boundary for River Rch & Prof#=TRIB 7 TO IRISH ,Reach-1,2
Up Type=0
Dn Type=3
Dn Slope=0.005
Boundary for River Rch & Prof#=TRIB 7 TO IRISH ,Reach-1,3
Up Type=0
Dn Type=3
Dn Slope=0.005
Boundary for River Rch & Prof#=TRIB 7 TO IRISH ,Reach-1,4
Up Type=0
Dn Type=3
Dn Slope=0.005
Boundary for River Rch & Prof#=TRIB 7 TO IRISH ,Reach-1,5
Up Type=0
Dn Type=3
Dn Slope=0.005
Boundary for River Rch & Prof#=TRIB 7 TO IRISH ,Reach-1,6
Up Type=0
Dn Type=3
Dn Slope=0.005
Boundary for River Rch & Prof#=TRIB 7 TO IRISH ,Reach-1,7
Up Type=0
Dn Type=3
Dn Slope=0.005

--- TRIB 7 TO IRISH CREEK.g01 (geometry) ---

Geom Title=Existing Conditions

River Reach=TRIB 7 TO IRISH ,Reach-1
Reach XY= 30
      2537875.00     13595325.00      2537990.19     13595374.55
      2538505.02     13595375.18      2538575.10     13595417.21
      2538624.90     13595382.79      2538690.16     13595424.35
      2538964.56     13595426.38      2539025.00     13595467.44
      2539080.86     13595427.47      2539227.70     13595419.64
      2539301.17     13595297.87      2539384.66     13595264.21
      2539518.81     13595132.82      2539669.07     13595122.75
      2539785.00     13595064.37      2539894.77     13594904.58
      2539984.68     13594864.22      2540115.00     13594736.24
      2540174.91     13594767.22      2540273.26     13594720.87
      2540622.71     13594480.85      2540795.57     13594405.42
      2540872.65     13594219.03      2540878.89     13594126.58
      2540924.18     13594064.29      2540884.17     13593968.28
      2540966.80     13593881.05      2540994.78     13593804.87
      2541120.08     13593719.67      2541125.00     13593675.00

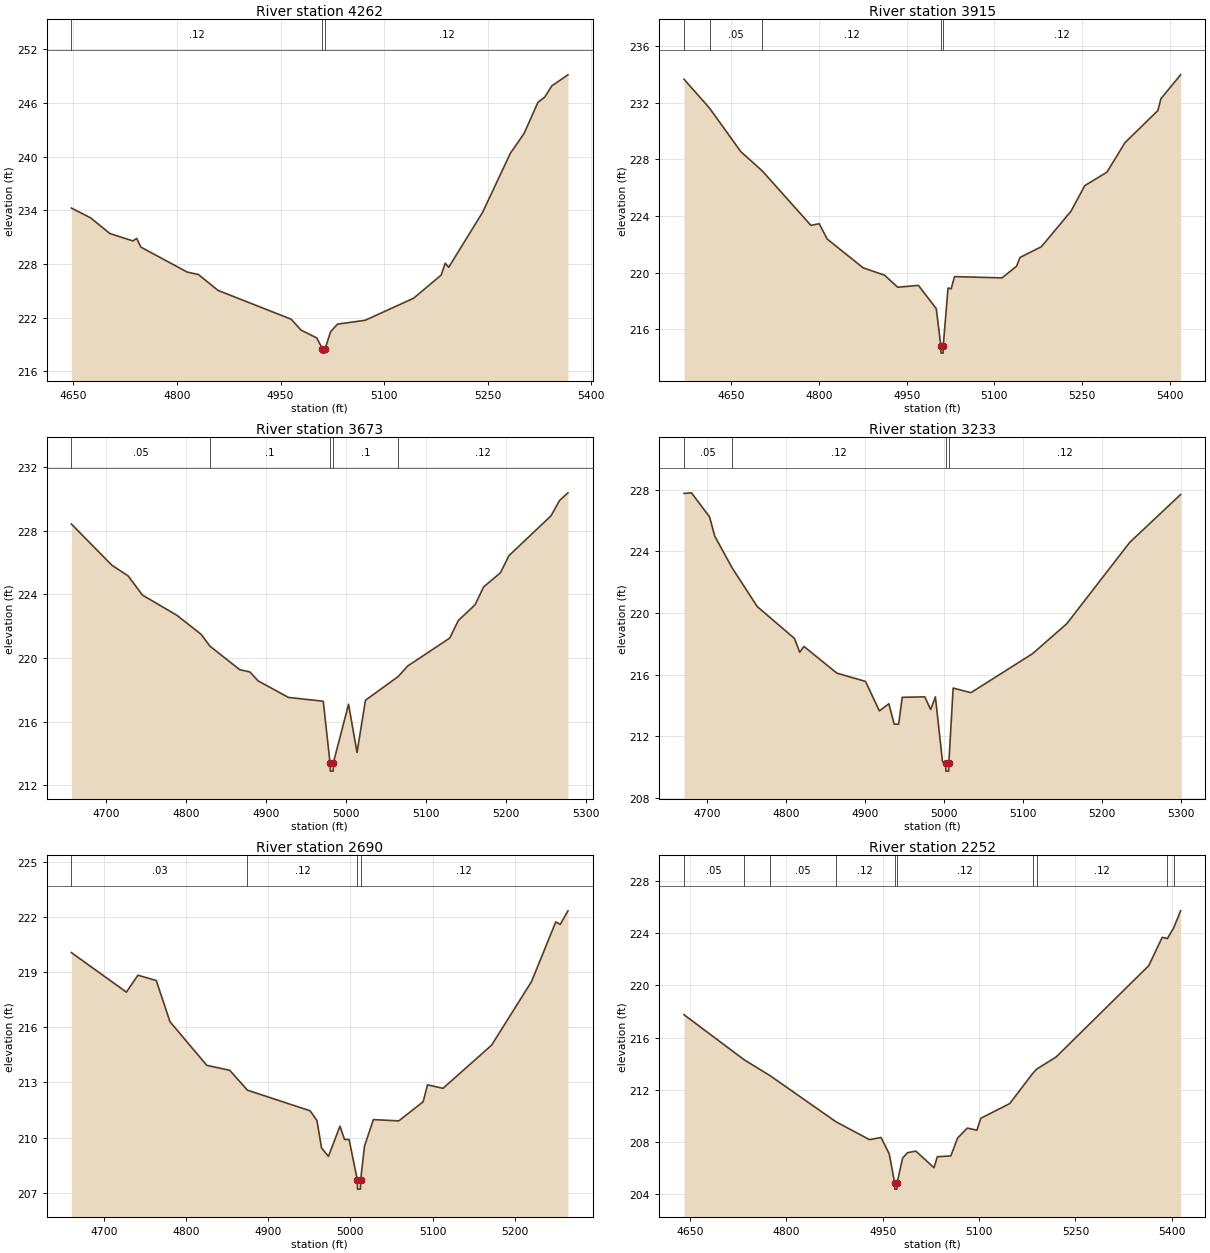
Type RM Length L Ch R = 1,4262,347,347,347
BEGIN DESCRIPTION:
TRIB 7 TO IRISH CREEK 6.0
END DESCRIPTION:
XS GIS Cut Line= 3
      2537807.83     13595674.97      2537957.81     13595375.00
      2537943.32     13594991.55
#Sta/Elev= 30
  4647.0  234.26  4674.6  233.18  4702.9  231.41  4736.1  230.59  4741.6  230.87
  4747.6  229.90  4814.7  227.11  4831.1  226.83  4859.4  225.06  4965.3  221.84
  4979.6  220.62  5002.4  219.75  5010.4  218.55  5010.6  218.05  5014.1  218.05
  5014.4  218.55  5022.4  220.44  5032.4  221.29  5072.4  221.72  5142.5  224.18
  5182.5  226.77  5188.4  228.10  5193.4  227.64  5242.6  233.80  5282.6  240.37
  5302.6  242.60  5322.6  246.07  5332.6  246.67  5342.6  247.91  5366.1  249.15
#Mann=3,-1,0
  4647.0    0.12       0  5010.4    0.05       0  5014.4    0.12       0
Bank Sta=5010.4,5014.4
Exp/Cntr=0.3,0.1

Type RM Length L Ch R = 1,3915,242,242,242
BEGIN DESCRIPTION:
Mapping XS 5d5d299c
END DESCRIPTION:
XS GIS Cut Line= 3
      2538131.80     13595761.97      2538309.76     13595406.05
      2538157.84     13594980.69
#Sta/Elev= 30
  4569.1  233.65  4612.8  231.61  4666.3  228.54  4703.0  227.18  4786.2  223.34
  4800.5  223.45  4814.1  222.37  4875.6  220.34  4912.3  219.82  4934.7  218.97
  4970.2  219.10  5000.7  217.46  5008.6  214.82  5008.9  214.32  5012.4  214.32
  5012.6  214.82  5020.8  218.91  5026.2  218.86  5031.9  219.72  5113.2  219.63
  5138.0  220.45  5144.0  221.07  5180.5  221.83  5231.1  224.33  5254.8  226.14
  5292.7  227.09  5323.5  229.17  5379.8  231.44  5385.1  232.28  5418.7  233.96
#Mann=5,-1,0
  4569.1    0.12       0  4612.8    0.05       0  4703.0    0.12       0
  5008.6    0.05       0  5012.6    0.12       0
Bank Sta=5008.6,5012.6
Exp/Cntr=0.3,0.1

Type RM Length L Ch R = 1,3673,440,440,440
BEGIN DESCRIPTION:
TRIB 7 TO IRISH CREEK 5.0
END DESCRIPTION:
XS GIS Cut Line= 3
      2538475.00     13595725.03      2538525.00     13595425.00
      2538625.00     13595124.99
#Sta/Elev= 30
  4657.1  228.42  4707.8  225.83  4728.1  225.16  4745.8  223.96  4788.9  222.69
  4819.3  221.49  4830.2  220.75  4867.5  219.27  4880.2  219.13  4890.3  218.57
  4928.3  217.53  4971.8  217.29  4980.3  213.40  4980.6  212.90  4984.1  212.90
  4984.3  213.40  5003.4  217.10  5014.0  214.07  5024.5  217.35  5065.4  218.84
  5077.2  219.50  5129.9  221.26  5140.5  222.36  5161.5  223.35  5172.1  224.47
  5193.2  225.36  5203.7  226.43  5256.4  228.94  5267.0  229.90  5277.5  230.38
#Mann=5,-1,0
  4657.1    0.05       0  4830.2     0.1       0  4980.3    0.05       0
  4984.3     0.1       0  5065.4    0.12       0
Bank Sta=4980.3,4984.3
Exp/Cntr=0.3,0.1

Type RM Length L Ch R = 1,3233,543,543,543
BEGIN DESCRIPTION:
TRIB 7 TO IRISH CREEK 4.0
END DESCRIPTION:
XS GIS Cut Line= 3
      2539075.02     13595725.04      2538975.00     13595475.00
      2538774.98     13595174.96
#Sta/Elev= 30
  4670.2  227.75  4679.7  227.79  4702.6  226.23  4709.3  224.97  4731.4  222.91
  4763.1  220.41  4810.3  218.34  4817.0  217.45  4822.4  217.82  4864.1  216.09
  4900.5  215.55  4918.0  213.64  4930.1  214.10  4936.8  212.78  4942.5  212.78
  4947.0  214.52  4975.6  214.55  4983.1  213.73  4989.1  214.55  4998.1  210.35
  5002.1  210.23  5002.4  209.73  5005.9  209.73  5006.1  210.23  5011.6  215.12
  5034.1  214.82  5112.3  217.35  5155.8  219.30  5235.5  224.57  5300.1  227.68
#Mann=4,-1,0
  4670.2    0.05       0  4731.4    0.12       0  5002.1    0.05       0
  5006.1    0.12       0
Bank Sta=5002.1,5006.1
Exp/Cntr=0.3,0.1

Type RM Length L Ch R = 1,2690,438,438,438
BEGIN DESCRIPTION:
TRIB 7 TO IRISH CREEK 3.0
END DESCRIPTION:
XS GIS Cut Line= 3
      2539524.98     13595574.96      2539375.00     13595275.00
      2539275.01     13595025.03
#Sta/Elev= 30
  4660.3  220.06  4727.3  217.91  4741.3  218.83  4763.7  218.54  4780.4  216.30
  4825.2  213.93  4853.1  213.66  4874.7  212.58  4950.9  211.46  4959.3  210.93
  4964.9  209.44  4973.3  208.98  4987.3  210.62  4992.9  209.90  4998.4  209.90
  5008.5  207.70  5008.7  207.20  5012.2  207.20  5012.5  207.70  5017.2  209.54
  5028.0  210.98  5058.9  210.91  5088.6  211.95  5093.9  212.87  5112.8  212.68
  5172.0  215.03  5220.5  218.48  5250.1  221.73  5255.5  221.59  5264.9  222.33
#Mann=4,-1,0
  4660.3    0.03       0  4874.7    0.12       0  5008.5    0.05       0
  5012.5    0.12       0
Bank Sta=5008.5,5012.5
Exp/Cntr=0.3,0.1

Type RM Length L Ch R = 1,2252,333,333,333
BEGIN DESCRIPTION:
TRIB 7 TO IRISH CREEK 2.0
END DESCRIPTION:
XS GIS Cut Line= 3
      2539825.00     13595425.00      2539725.00     13595025.00
      2539524.98     13594724.97
#Sta/Elev= 30
  4640.7  217.76  4734.1  214.32  4774.8  213.09  4877.1  209.57  4929.3  208.20
  4947.4  208.36  4960.2  207.10  4968.5  204.91  4968.8  204.41  4972.3  204.41
  4972.5  204.91  4980.9  206.78  4988.6  207.20  5001.5  207.32  5029.8  206.05
  5035.0  206.89  5056.0  206.95  5066.5  208.32  5081.6  209.08  5096.6  208.92
  5102.6  209.83  5147.7  210.96  5183.2  213.25  5189.7  213.60  5219.8  214.52
  5364.0  221.51  5385.0  223.68  5393.1  223.59  5402.9  224.41  5413.6  225.71
#Mann=10,-1,0
  4640.7    0.05       0  4734.1    0.12       0  4774.8    0.05       0
  4877.1    0.12       0  4968.5    0.05       0  4972.5    0.12       0
  5183.2    0.05       0  5189.7    0.12       0  5393.1    0.05       0
  5402.9    0.12       0
Bank Sta=4968.5,4972.5
Exp/Cntr=0.3,0.1

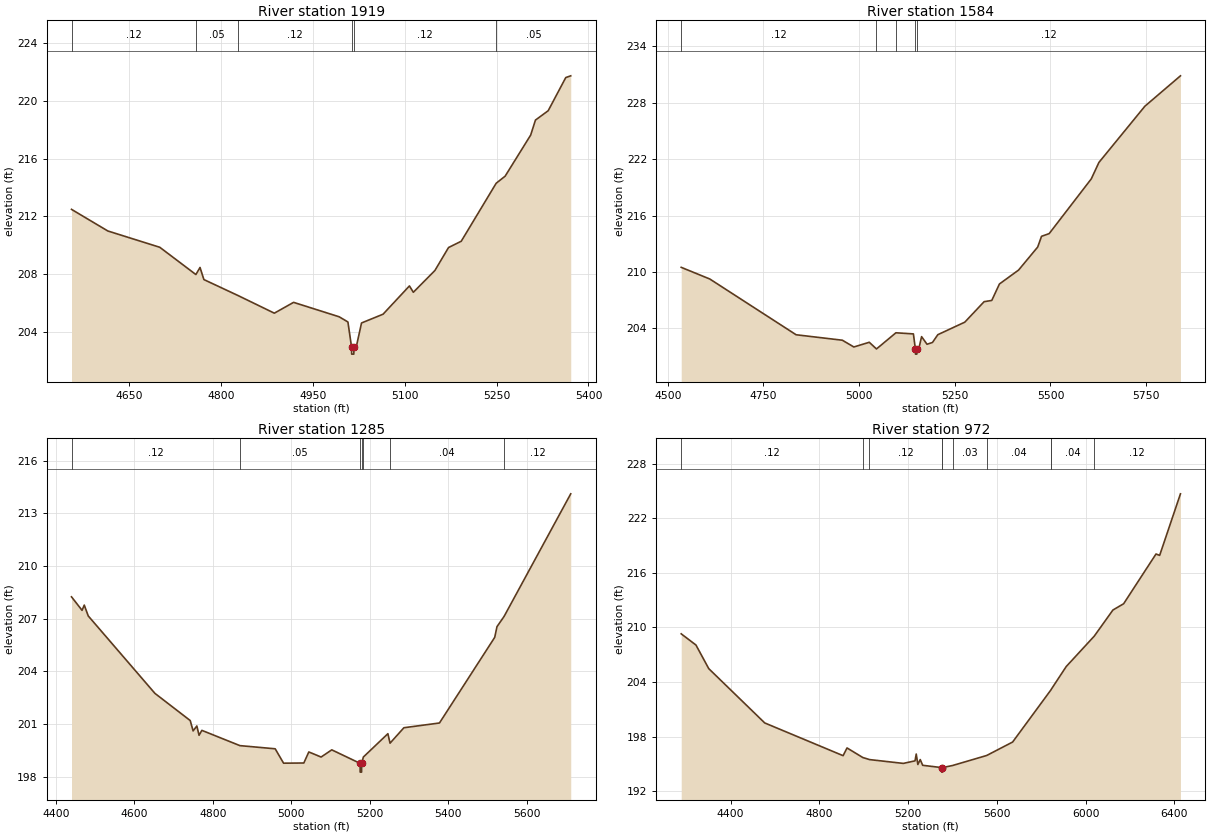
Type RM Length L Ch R = 1,1919,335,335,335
BEGIN DESCRIPTION:
4883
END DESCRIPTION:
XS GIS Cut Line= 3
      2540120.86     13595281.72      2540005.52     13594903.41
      2539682.57     13594635.83
#Sta/Elev= 30
  4556.2  212.48  4615.5  210.98  4700.3  209.85  4759.2  207.96  4766.0  208.45
  4772.3  207.61  4827.7  206.51  4887.3  205.28  4918.7  206.03  4993.1  205.03
  5007.4  204.67  5013.3  202.94  5013.5  202.44  5017.0  202.44  5017.3  202.94
  5021.8  203.09  5029.6  204.60  5064.8  205.21  5107.8  207.17  5114.2  206.73
  5149.4  208.24  5171.6  209.83  5192.4  210.27  5249.4  214.29  5264.0  214.78
  5305.7  217.63  5313.5  218.67  5334.3  219.32  5363.0  221.62  5371.1  221.74
#Mann=6,-1,0
  4556.2    0.12       0  4759.2    0.05       0  4827.7    0.12       0
  5013.3    0.05       0  5017.3    0.12       0  5249.4    0.05       0
Bank Sta=5013.3,5017.3
Exp/Cntr=0.3,0.1

Type RM Length L Ch R = 1,1584,299,299,299
BEGIN DESCRIPTION:
Mapping XS 6e6e6274
END DESCRIPTION:
XS GIS Cut Line= 4
      2540171.73     13595193.42      2540228.16     13594681.23
      2540037.19     13594498.94      2539512.07     13594490.26
#Sta/Elev= 30
  4535.2  210.50  4609.9  209.26  4835.4  203.33  4956.2  202.75  4986.3  202.03
  5026.6  202.53  5045.4  201.82  5096.2  203.54  5141.9  203.42  5147.2  201.77
  5147.4  201.27  5150.9  201.27  5151.2  201.77  5156.1  201.86  5163.3  203.13
  5177.5  202.32  5191.7  202.51  5205.8  203.34  5276.2  204.67  5326.7  206.85
  5346.7  206.98  5366.7  208.73  5416.7  210.21  5466.7  212.66  5476.7  213.80
  5496.7  214.09  5606.7  219.91  5626.7  221.66  5746.8  227.64  5839.7  230.87
#Mann=5,-1,0
  4535.2    0.12       0  5045.4    0.05       0  5096.2    0.12       0
  5147.2    0.05       0  5151.2    0.12       0
Bank Sta=5147.2,5151.2
Exp/Cntr=0.3,0.1

Type RM Length L Ch R = 1,1285,313,313,313
BEGIN DESCRIPTION:
4882
END DESCRIPTION:
XS GIS Cut Line= 4
      2540277.74     13595083.33      2540499.19     13594631.20
      2540365.39     13594405.12      2539862.48     13594460.49
#Sta/Elev= 30
  4439.8  208.25  4466.7  207.48  4472.3  207.78  4482.5  207.16  4652.3  202.75
  4742.3  201.20  4749.7  200.61  4759.2  200.89  4764.8  200.36  4772.0  200.64
  4869.0  199.77  4958.8  199.59  4980.2  198.77  5031.8  198.78  5044.5  199.41
  5075.8  199.12  5103.0  199.53  5175.2  198.76  5175.4  198.26  5178.9  198.26
  5179.2  198.76  5183.5  199.12  5246.0  200.45  5251.5  199.91  5286.8  200.79
  5377.4  201.06  5518.2  205.94  5524.0  206.55  5542.0  207.13  5711.9  214.12
#Mann=7,-1,0
  4439.8    0.12       0  4869.0    0.05       0  5175.2    0.05       0
  5179.2    0.05       0  5183.5    0.03       0  5251.5    0.04       0
  5542.0    0.12       0
Bank Sta=5175.2,5179.2
Exp/Cntr=0.3,0.1

Type RM Length L Ch R = 1,972,0,0,0
BEGIN DESCRIPTION:
Mapping XS 49dc6a2c
END DESCRIPTION:
XS GIS Cut Line= 4
      2540391.64     13595178.20      2540767.08     13594344.86
      2540657.78     13594093.18      2539639.26     13593793.83
#Sta/Elev= 30
  4177.5  209.30  4243.9  208.07  4301.7  205.47  4553.9  199.50  4907.1  195.90
  4924.8  196.75  4995.7  195.70  5025.9  195.47  5178.6  195.05  5231.2  195.33
  5236.7  196.08  5244.0  194.93  5254.7  195.47  5265.8  194.84  5351.0  194.59
  5351.3  194.09  5354.8  194.09  5355.0  194.59  5400.8  194.82  5554.2  195.92
  5671.1  197.40  5844.0  203.14  5846.3  203.24  5912.6  205.70  6039.1  209.05
  6123.2  211.92  6171.4  212.61  6317.3  218.08  6333.8  217.93  6427.5  224.70
#Mann=10,-1,0
  4177.5    0.12       0  4995.7    0.05       0  5025.9    0.12       0
  5351.0    0.05       0  5355.0    0.12       0  5400.8    0.03       0
  5554.2    0.04       0  5844.0    0.03       0  5846.3    0.04       0
  6039.1    0.12       0
Bank Sta=5351,5355
Exp/Cntr=0.3,0.1

Chan Stop Cuts=-1