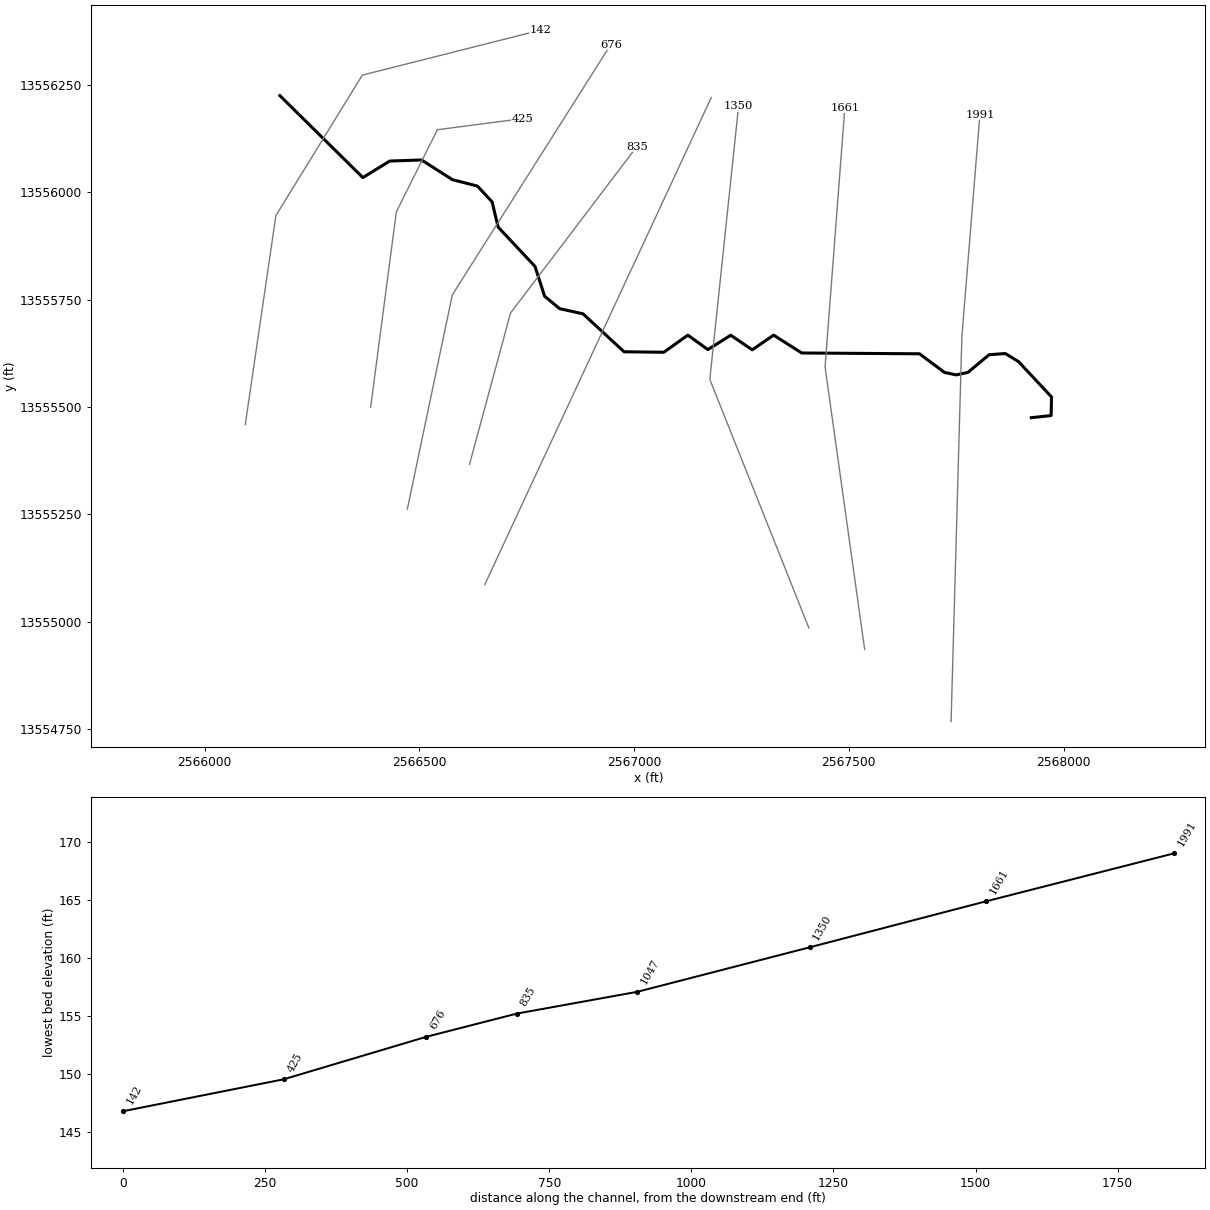
--- TRIB 7 TO PRICE CREEK.prj (project) ---

Proj Title=TRIB 7 TO PRICE CREEK Base Level Engineering
Current Plan=p01
Default Exp/Contr=0.3,0.1
English Units
Geom File=g01
Flow File=f01
Plan File=p01
BEGIN DESCRIPTION:
TRIB 7 TO PRICE CREEK
END DESCRIPTION:

--- TRIB 7 TO PRICE CREEK.p01 (plan) ---

Plan Title=Multiple Run
Short Identifier=Multiple
Geom File=g01
Flow File=f01
Subcritical Flow
K Sum by GR= 0
Std Step Tol= 0.01
Critical Tol= 0.01
Num of Std Step Trials= 20
Max Error Tol= 0.3
Flow Tol Ratio= 0.001
Split Flow NTrial= 30
Split Flow Tol= 0.02
Split Flow Ratio= 0.02
Log Output Level= 0
Friction Slope Method= 1
Unsteady Friction Slope Method= 2
Unsteady Bridges Friction Slope Method= 1
Parabolic Critical Depth
Global Vel Dist=  1 , 1 , 1
Global Log Level= 0
CheckData=True
Encroach Param= -1, 0, 0, 0
BEGIN DESCRIPTION:
Multiple Run
END DESCRIPTION:

--- TRIB 7 TO PRICE CREEK.f01 (steady flow) ---

Flow Title=Multiple
Number of Profiles=7
Profile Names=10-year,25-year,50-year,1pct_min,100-year,1pct_plu,500-year
River Rch & RM= TRIB 7 TO PRICE ,Reach-1,1991
     233     348     445     277     554    1104     842
Boundary for River Rch & Prof#=TRIB 7 TO PRICE ,Reach-1,1
Up Type=0
Dn Type=3
Dn Slope=0.005
Boundary for River Rch & Prof#=TRIB 7 TO PRICE ,Reach-1,2
Up Type=0
Dn Type=3
Dn Slope=0.005
Boundary for River Rch & Prof#=TRIB 7 TO PRICE ,Reach-1,3
Up Type=0
Dn Type=3
Dn Slope=0.005
Boundary for River Rch & Prof#=TRIB 7 TO PRICE ,Reach-1,4
Up Type=0
Dn Type=3
Dn Slope=0.005
Boundary for River Rch & Prof#=TRIB 7 TO PRICE ,Reach-1,5
Up Type=0
Dn Type=3
Dn Slope=0.005
Boundary for River Rch & Prof#=TRIB 7 TO PRICE ,Reach-1,6
Up Type=0
Dn Type=3
Dn Slope=0.005
Boundary for River Rch & Prof#=TRIB 7 TO PRICE ,Reach-1,7
Up Type=0
Dn Type=3
Dn Slope=0.005

--- TRIB 7 TO PRICE CREEK.g01 (geometry) ---

Geom Title=Existing Conditions

River Reach=TRIB 7 TO PRICE ,Reach-1
Reach XY= 30
      2567925.00     13555475.00      2567971.07     13555479.92
      2567972.03     13555523.21      2567895.14     13555605.59
      2567864.39     13555624.40      2567826.74     13555621.63
      2567777.20     13555580.42      2567750.00     13555574.61
      2567722.82     13555580.38      2567664.50     13555623.76
      2567390.16     13555625.65      2567324.90     13555667.22
      2567274.99     13555633.02      2567225.00     13555667.00
      2567171.67     13555633.54      2567125.10     13555667.21
      2567069.11     13555627.35      2566976.50     13555628.47
      2566881.02     13555716.81      2566826.43     13555728.89
      2566791.50     13555757.95      2566769.12     13555827.26
      2566683.18     13555918.98      2566669.25     13555977.54
      2566635.00     13556014.37      2566576.78     13556029.24
      2566504.90     13556075.10      2566430.89     13556072.63
      2566368.26     13556034.13      2566175.00     13556225.00

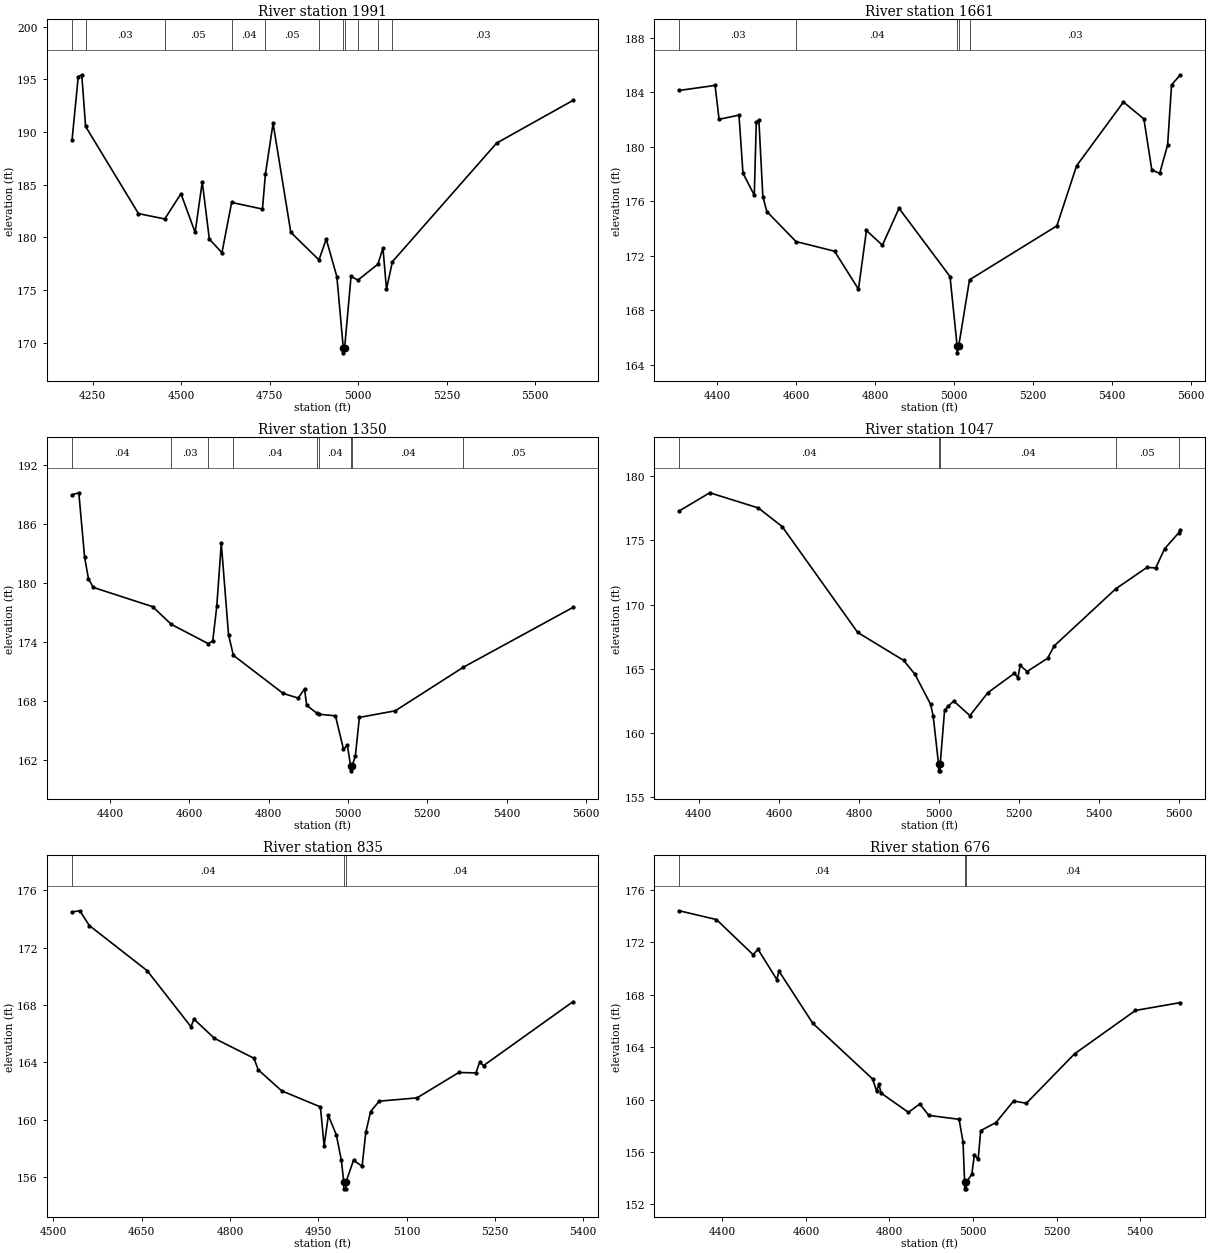
Type RM Length L Ch R = 1,1991,330,330,330
BEGIN DESCRIPTION:
LGII3155
END DESCRIPTION:
XS GIS Cut Line= 3
      2567738.12     13554767.49      2567763.28     13555664.74
      2567805.19     13556180.24
#Sta/Elev= 30
  4191.9  189.22  4209.4  195.25  4219.4  195.44  4230.2  190.53  4379.5  182.25
  4453.7  181.74  4499.5  184.14  4539.5  180.46  4559.6  185.27  4579.6  179.83
  4615.2  178.53  4642.6  183.31  4729.6  182.68  4737.8  185.98  4759.6  190.83
  4809.6  180.47  4889.2  177.85  4909.7  179.83  4939.7  176.25  4957.7  169.52
  4958.0  169.02  4961.7  169.52  4979.7  176.28  4999.1  175.93  5055.7  177.45
  5069.8  178.98  5079.8  175.07  5096.5  177.68  5390.8  188.95  5606.7  193.01
#Mann=11,-1,0
  4191.9    0.05       0  4230.2    0.03       0  4453.7    0.05       0
  4642.6    0.04       0  4737.8    0.05       0  4889.2    0.04       0
  4957.7    0.05       0  4961.7    0.04       0  4999.1    0.05       0
  5055.7    0.04       0  5096.5    0.03       0
Bank Sta=4957.7,4961.7
Exp/Cntr=0.3,0.1

Type RM Length L Ch R = 1,1661,311,311,311
BEGIN DESCRIPTION:
LGII3154
END DESCRIPTION:
XS GIS Cut Line= 3
      2567536.85     13554935.20      2567444.61     13555593.46
      2567490.73     13556197.21
#Sta/Elev= 30
  4303.9  184.15  4394.6  184.52  4404.7  182.03  4455.2  182.34  4465.3  178.08
  4494.0  176.46  4499.0  181.80  4505.6  181.98  4515.7  176.36  4525.8  175.26
  4599.7  173.06  4697.5  172.35  4758.1  169.56  4778.3  173.87  4818.7  172.79
  4860.9  175.50  4990.2  170.49  5008.2  165.39  5008.5  164.89  5012.2  165.39
  5039.6  170.25  5261.0  174.21  5311.1  178.62  5429.8  183.30  5481.6  182.06
  5501.7  178.32  5521.7  178.06  5541.8  180.15  5551.8  184.56  5574.1  185.30
#Mann=5,-1,0
  4303.9    0.03       0  4599.7    0.04       0  5008.2    0.04       0
  5012.2    0.04       0  5039.6    0.03       0
Bank Sta=5008.2,5012.2
Exp/Cntr=0.3,0.1

Type RM Length L Ch R = 1,1350,303,303,303
BEGIN DESCRIPTION:
LGII3153
END DESCRIPTION:
XS GIS Cut Line= 3
      2567406.87     13554985.51      2567176.27     13555564.11
      2567243.28     13556200.73
#Sta/Elev= 30
  4304.6  188.95  4321.7  189.16  4336.3  182.61  4345.9  180.45  4357.9  179.55
  4507.7  177.59  4554.9  175.79  4648.1  173.83  4659.3  174.11  4669.5  177.65
  4680.8  184.03  4699.1  174.74  4711.2  172.65  4836.6  168.78  4874.6  168.30
  4890.6  169.23  4896.1  167.56  4921.0  166.79  4927.2  166.66  4968.6  166.50
  4988.7  163.12  4998.7  163.49  5006.8  161.41  5007.0  160.91  5010.8  161.41
  5018.9  162.46  5028.9  166.34  5119.4  167.01  5290.7  171.43  5567.6  177.52
#Mann=9,-1,0
  4304.6    0.04       0  4554.9    0.03       0  4648.1    0.05       0
  4711.2    0.04       0  4921.0    0.05       0  4927.2    0.04       0
  5006.8    0.04       0  5010.8    0.04       0  5290.7    0.05       0
Bank Sta=5006.8,5010.8
Exp/Cntr=0.3,0.1

Type RM Length L Ch R = 1,1047,212,212,212
BEGIN DESCRIPTION:
LGII3152
END DESCRIPTION:
XS GIS Cut Line= 2
      2566652.13     13555086.08      2567179.68     13556220.73
#Sta/Elev= 30
  4351.3  177.30  4427.3  178.71  4548.6  177.53  4608.2  176.08  4796.8  167.84
  4911.3  165.67  4939.7  164.59  4978.7  162.26  4985.4  161.33  4998.8  157.57
  4999.0  157.07  5002.5  157.07  5002.8  157.57  5013.8  161.78  5022.8  162.11
  5036.7  162.50  5077.0  161.37  5122.1  163.16  5188.2  164.66  5196.9  164.31
  5202.5  165.28  5219.8  164.80  5271.1  165.83  5287.5  166.79  5441.0  171.23
  5519.1  172.90  5541.1  172.86  5563.2  174.35  5598.4  175.59  5602.6  175.84
#Mann=5,-1,0
  4351.3    0.04       0  4998.8    0.04       0  5002.8    0.04       0
  5441.0    0.05       0  5598.4    0.04       0
Bank Sta=4998.8,5002.8
Exp/Cntr=0.3,0.1

Type RM Length L Ch R = 1,835,159,159,159
BEGIN DESCRIPTION:
4885
END DESCRIPTION:
XS GIS Cut Line= 3
      2566616.70     13555366.67      2566712.17     13555718.63
      2567006.12     13556106.19
#Sta/Elev= 30
  4531.6  174.49  4544.8  174.57  4561.0  173.54  4659.1  170.40  4733.6  166.49
  4738.7  167.02  4773.4  165.68  4840.7  164.29  4847.8  163.49  4887.7  162.02
  4953.5  160.90  4959.8  158.17  4967.0  160.31  4980.6  158.94  4988.9  157.22
  4993.2  155.69  4993.4  155.19  4996.9  155.19  4997.2  155.69  5009.7  157.18
  5024.3  156.76  5030.6  159.13  5038.8  160.58  5053.4  161.30  5117.6  161.53
  5188.6  163.30  5217.7  163.27  5224.0  164.02  5230.6  163.78  5382.7  168.24
#Mann=3,-1,0
  4531.6    0.04       0  4993.2    0.04       0  4997.2    0.04       0
Bank Sta=4993.2,4997.2
Exp/Cntr=0.3,0.1

Type RM Length L Ch R = 1,676,251,251,251
BEGIN DESCRIPTION:
LGII3151
END DESCRIPTION:
XS GIS Cut Line= 3
      2566471.86     13555262.23      2566576.68     13555761.18
      2566945.64     13556343.97
#Sta/Elev= 30
  4296.9  174.39  4385.9  173.72  4473.4  171.05  4485.6  171.44  4530.3  169.15
  4535.5  169.79  4616.5  165.81  4759.6  161.57  4769.5  160.63  4774.6  161.19
  4780.0  160.49  4845.6  159.02  4872.7  159.67  4894.1  158.79  4966.8  158.49
  4976.1  156.78  4980.0  153.69  4980.3  153.19  4983.8  153.19  4984.0  153.69
  4997.3  154.31  5003.2  155.77  5012.5  155.46  5018.5  157.63  5054.9  158.24
  5097.3  159.89  5127.8  159.71  5243.1  163.48  5388.9  166.79  5496.5  167.39
#Mann=3,-1,0
  4296.9    0.04       0  4980.0    0.04       0  4984.0    0.04       0
Bank Sta=4980,4984
Exp/Cntr=0.3,0.1

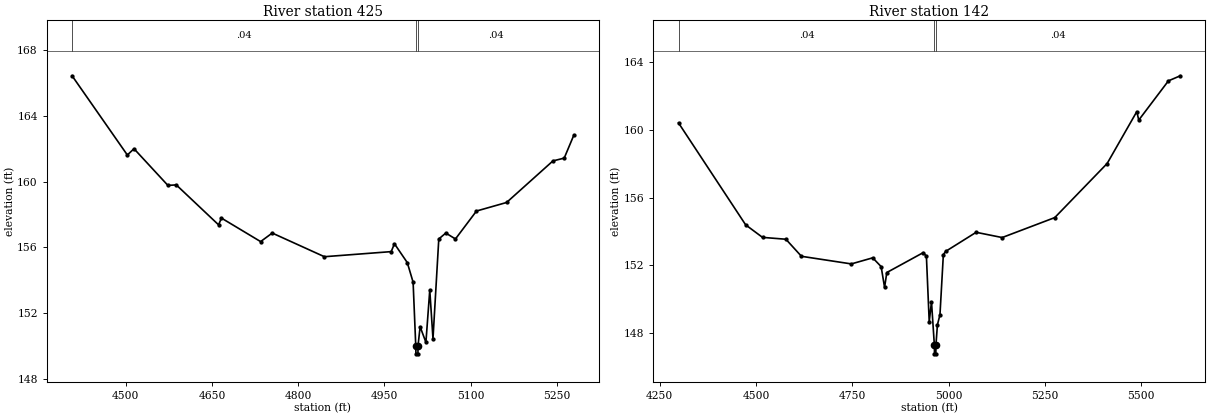
Type RM Length L Ch R = 1,425,283,283,283
BEGIN DESCRIPTION:
4886
END DESCRIPTION:
XS GIS Cut Line= 4
      2566386.40     13555499.58      2566446.31     13555954.54
      2566541.80     13556145.51      2566741.10     13556171.59
#Sta/Elev= 30
  4406.5  166.44  4502.7  161.62  4514.3  162.00  4573.3  159.77  4587.9  159.80
  4661.5  157.37  4666.5  157.78  4734.7  156.35  4754.9  156.87  4845.7  155.43
  4962.0  155.74  4967.6  156.22  4990.0  155.07  5000.1  153.88  5004.7  150.02
  5005.0  149.52  5008.5  149.52  5008.7  150.02  5012.3  151.17  5022.4  150.22
  5029.1  153.40  5034.7  150.44  5044.8  156.51  5057.0  156.87  5073.8  156.51
  5110.4  158.21  5162.8  158.73  5243.5  161.26  5263.1  161.43  5279.9  162.83
#Mann=3,-1,0
  4406.5    0.04       0  5004.7    0.04       0  5008.7    0.04       0
Bank Sta=5004.7,5008.7
Exp/Cntr=0.3,0.1

Type RM Length L Ch R = 1,142,0,0,0
BEGIN DESCRIPTION:
LGII3150
END DESCRIPTION:
XS GIS Cut Line= 4
      2566094.49     13555459.26      2566165.77     13555945.67
      2566367.03     13556272.72      2566781.11     13556377.28
#Sta/Elev= 30
  4298.7  160.42  4473.0  154.39  4516.7  153.65  4577.4  153.54  4617.8  152.53
  4747.3  152.08  4802.8  152.44  4824.7  151.92  4833.6  150.69  4839.4  151.57
  4934.1  152.75  4942.2  152.53  4949.5  148.66  4955.4  149.84  4962.9  147.26
  4963.2  146.76  4966.7  146.76  4966.9  147.26  4970.8  148.48  4977.4  149.07
  4986.2  152.63  4992.1  152.82  5071.3  153.95  5138.9  153.64  5275.4  154.82
  5411.4  158.02  5488.4  161.09  5493.5  160.59  5570.5  162.91  5601.4  163.21
#Mann=3,-1,0
  4298.7    0.04       0  4962.9    0.04       0  4966.9    0.04       0
Bank Sta=4962.9,4966.9
Exp/Cntr=0.3,0.1

Chan Stop Cuts=-1