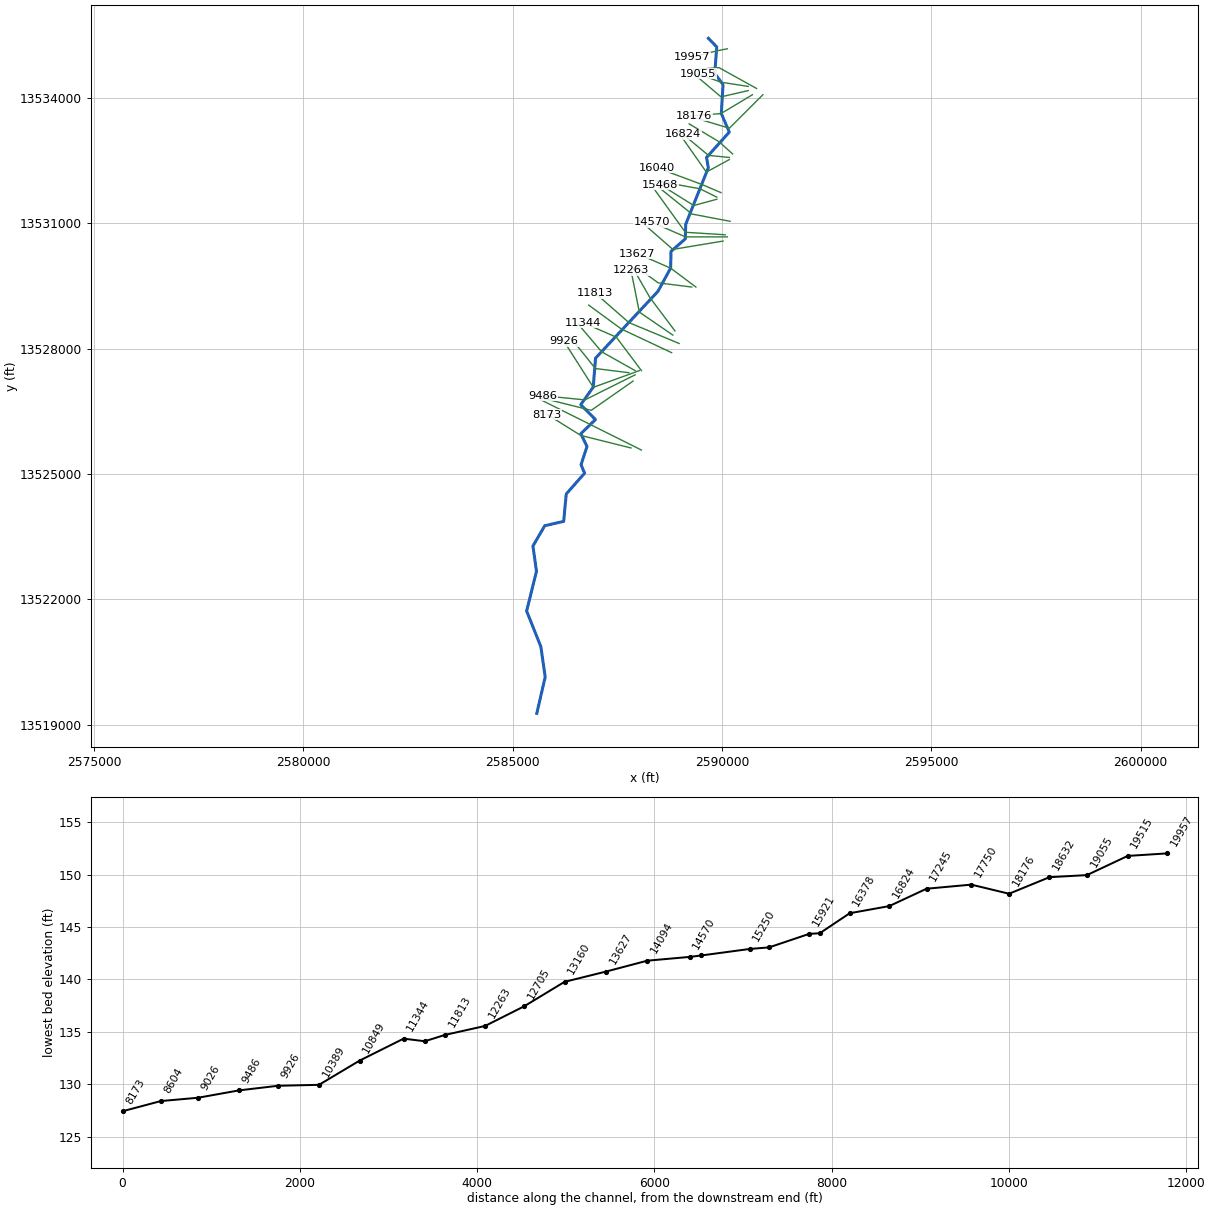
--- TRIB 7 TO SPRING CREEK.prj (project) ---

Proj Title=TRIB 7 TO SPRING CREEK Base Level Engineering
Current Plan=p01
Default Exp/Contr=0.3,0.1
English Units
Geom File=g01
Flow File=f01
Plan File=p01
Y Axis Title=Elevation
X Axis Title(PF)=Main Channel Distance
X Axis Title(XS)=Station
BEGIN DESCRIPTION:
TRIB 7 TO SPRING CREEK
END DESCRIPTION:
DSS Export Rating Curves= 0
DSS Export Rating Curve Sorted= 0
DSS Export Volume Flow Curves= 0
DXF OffsetX= 0
DXF OffsetY= 0
DXF ScaleX= 1
DXF ScaleY= 10

--- TRIB 7 TO SPRING CREEK.p01 (plan) ---

Plan Title=Multiple Run
Short Identifier=Multiple
Geom File=g01
Flow File=f01
Subcritical Flow
K Sum by GR= 0
Std Step Tol= 0.01
Critical Tol= 0.01
Num of Std Step Trials= 20
Max Error Tol= 0.3
Flow Tol Ratio= 0.001
Split Flow NTrial= 30
Split Flow Tol= 0.02
Split Flow Ratio= 0.02
Log Output Level= 0
Friction Slope Method= 1
Unsteady Friction Slope Method= 2
Unsteady Bridges Friction Slope Method= 1
Parabolic Critical Depth
Global Vel Dist=  1 , 1 , 1
Global Log Level= 0
CheckData=True
Encroach Param= -1, 0, 0, 0
BEGIN DESCRIPTION:
Multiple Run
END DESCRIPTION:

--- TRIB 7 TO SPRING CREEK.f01 (steady flow) ---

Flow Title=Multiple
Number of Profiles=7
Profile Names=10-year,25-year,50-year,1pct_min,100-year,1pct_plu,500-year
River Rch & RM= TRIB 7 TO SPRING,Reach-1,19957
     759    1189    1565     994    1984    3959    3151
River Rch & RM= TRIB 7 TO SPRING,Reach-1,17750
     877    1384    1830    1168    2330    4648    3734
River Rch & RM= TRIB 7 TO SPRING,Reach-1,15468
    1105    1764    2353    1513    3019    6023    4914
River Rch & RM= TRIB 7 TO SPRING,Reach-1,11813
    1358    2191    2941    1903    3797    7576    6259
River Rch & RM= TRIB 7 TO SPRING,Reach-1,8173
    1599    2601    3511    2283    4556    9090    7586
River Rch & RM= TRIB 7 TO SPRING,Reach-1,4095
    1848    3033    4119    2695    5377   10728    9061
Boundary for River Rch & Prof#=TRIB 7 TO SPRING,Reach-1,1
Up Type=0
Dn Type=3
Dn Slope=0.005
Boundary for River Rch & Prof#=TRIB 7 TO SPRING,Reach-1,2
Up Type=0
Dn Type=3
Dn Slope=0.005
Boundary for River Rch & Prof#=TRIB 7 TO SPRING,Reach-1,3
Up Type=0
Dn Type=3
Dn Slope=0.005
Boundary for River Rch & Prof#=TRIB 7 TO SPRING,Reach-1,4
Up Type=0
Dn Type=3
Dn Slope=0.005
Boundary for River Rch & Prof#=TRIB 7 TO SPRING,Reach-1,5
Up Type=0
Dn Type=3
Dn Slope=0.005
Boundary for River Rch & Prof#=TRIB 7 TO SPRING,Reach-1,6
Up Type=0
Dn Type=3
Dn Slope=0.005
Boundary for River Rch & Prof#=TRIB 7 TO SPRING,Reach-1,7
Up Type=0
Dn Type=3
Dn Slope=0.005

--- TRIB 7 TO SPRING CREEK.g01 (geometry) ---

Geom Title=Existing Conditions
Program Version=4.10

River Reach=TRIB 7 TO SPRING,Reach-1
Reach XY= 30
        2589675.       13535425.      2589873.02     13535219.33
      2589825.69     13534585.69      2590023.17     13534318.88
      2589982.53     13533625.01      2590172.86     13533180.97
      2589628.46      13532573.5      2589672.86     13532330.97
      2589132.89     13530978.58      2589121.85     13530626.63
      2588780.47     13530327.45      2588772.94     13529930.85
      2588469.54     13529372.55      2586978.54     13527773.54
      2586923.01     13527080.68      2586624.75     13526659.28
      2586975.37      13526304.8      2586626.03     13525964.58
      2586774.62     13525659.84      2586632.33      13525225.1
      2586716.96     13525021.68      2586278.45     13524523.75
      2586217.36     13523868.54       2585765.2     13523764.52
      2585482.81     13523278.41       2585567.9       13522675.
      2585332.34      13521724.9      2585672.75     13520869.06
      2585775.67     13520145.08        2585575.       13519275.

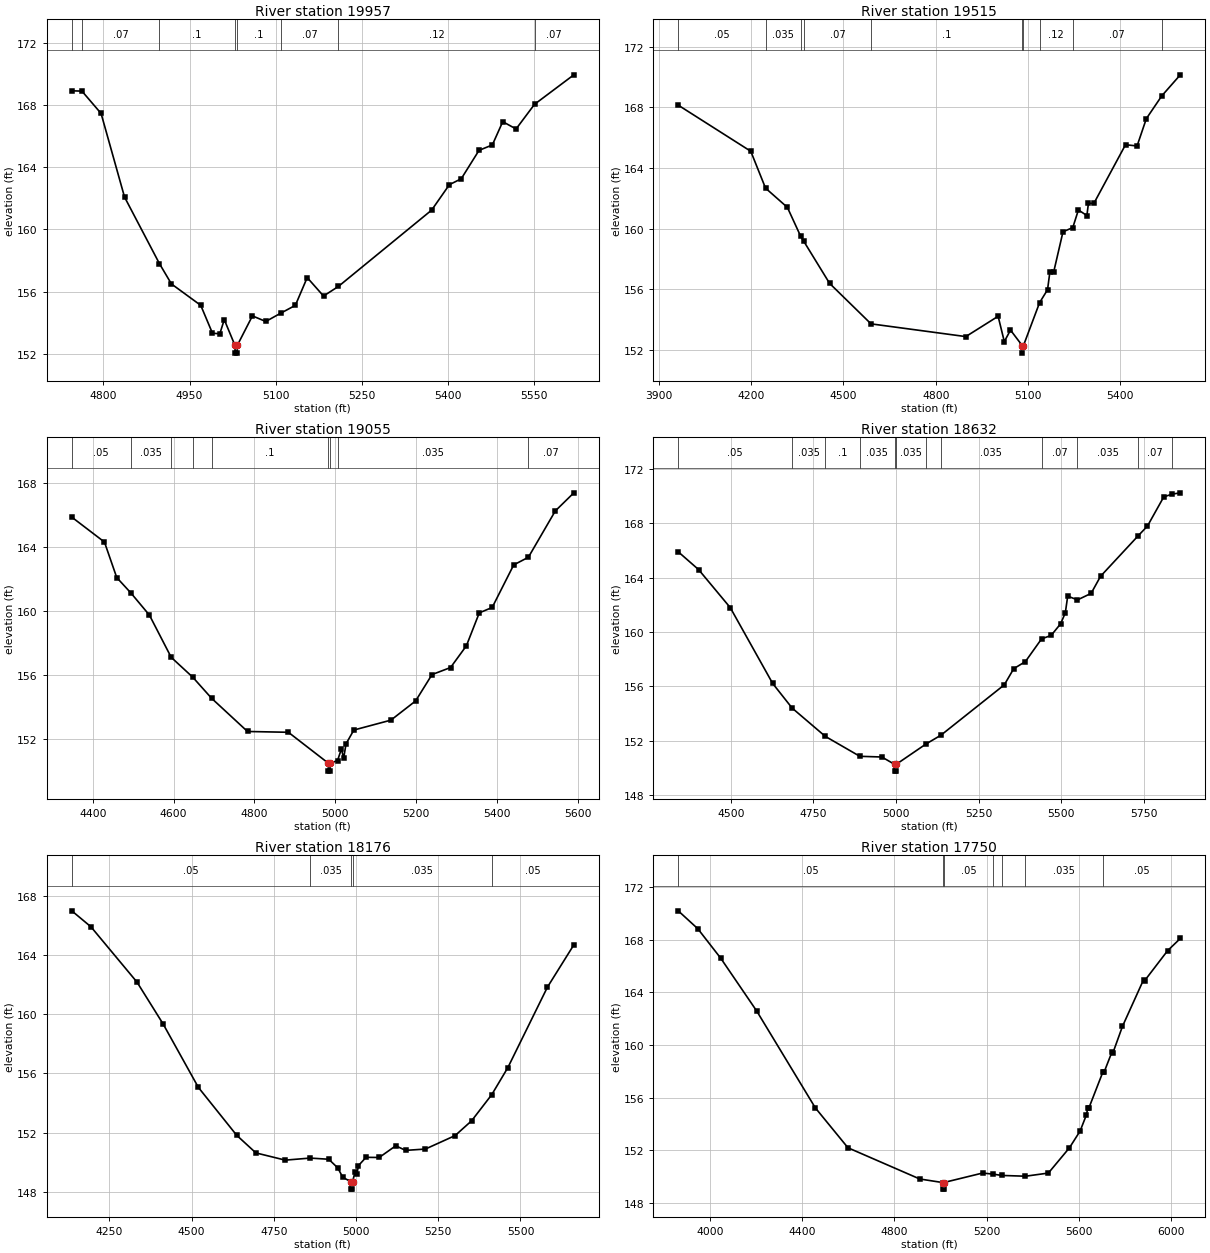
Type RM Length L Ch R = 1 ,19957   ,442,442,442
BEGIN DESCRIPTION:
TRIB 7 TO SPRING CREEK 42.0
END DESCRIPTION:
XS GIS Cut Line= 3
      2590125.05     13535175.01        2589875.       13535125.
      2589274.97     13534974.99
#Sta/Elev= 30
  4745.1  168.94  4762.8  168.92  4796.1  167.48  4836.9  162.09  4897.6   157.8
  4918.5  156.49  4969.5  155.11  4989.9  153.31  5002.7  153.28  5010.4  154.19
    5029  152.53  5029.3  152.03  5032.8  152.03  5033.1  152.53  5059.4  154.43
  5082.6  154.07  5108.4   154.6  5134.1  155.11  5154.7   156.9  5183.1  155.71
    5209  156.33  5371.2  161.25  5402.1  162.89  5422.7  163.27  5453.6   165.1
  5476.8  165.45  5494.9  166.95  5518.1  166.48  5550.2  168.07  5618.6  169.97
#Mann= 8 ,-1 , 0
  4745.1    .035       0  4762.8     .07       0  4897.6      .1       0
    5029     .05       0  5033.1      .1       0  5108.4     .07       0
    5209     .12       0  5550.2     .07       0
Bank Sta=5029,5033.1
XS Rating Curve= 0 ,0
Exp/Cntr=0.3,0.1

Type RM Length L Ch R = 1 ,19515   ,460,460,460
BEGIN DESCRIPTION:
TRIB 7 TO SPRING CREEK 41.0
END DESCRIPTION:
XS GIS Cut Line= 3
      2590825.03     13534224.98        2589925.       13534725.
      2589324.98       13534675.
#Sta/Elev= 30
    3963  168.14  4198.7   165.1  4246.7  162.67  4317.7   161.4    4361  159.49
  4370.8  159.17  4454.9  156.39  4589.5  153.72  4897.6  152.88  5002.6  154.22
  5022.7  152.55  5042.8  153.31  5080.9  152.29  5081.1  151.79    5085  152.29
  5137.4  155.12  5163.2  155.97  5170.7  157.13  5183.3  157.15  5213.4  159.79
  5245.3  160.07  5263.5  161.23  5291.1  160.86  5296.1  161.67  5313.7  161.66
  5416.6  165.53  5454.2  165.45  5484.3  167.25  5534.4  168.75  5594.7  170.14
#Mann= 10 ,-1 , 0
    3963     .05       0  4246.7    .035       0    4361     .05       0
  4370.8     .07       0  4589.5      .1       0  5080.9     .05       0
    5085      .1       0  5137.4     .12       0  5245.3     .07       0
  5534.4    .035       0
Bank Sta=5080.9,5085
XS Rating Curve= 0 ,0
Exp/Cntr=0.3,0.1

Type RM Length L Ch R = 1 ,19055   ,423,423,423
BEGIN DESCRIPTION:
TRIB 7 TO SPRING CREEK 40.0
END DESCRIPTION:
XS GIS Cut Line= 3
      2590624.96     13534275.01        2589975.       13534375.
      2589425.04     13534574.99
#Sta/Elev= 30
    4348  165.85  4428.9  164.29  4459.3  162.07  4494.2  161.11  4540.2  159.72
  4594.1  157.08  4647.7  155.83    4694  154.52    4783  152.44  4884.2  152.39
  4982.9  150.46  4983.3  149.96  4987.5  149.96  4987.8  150.46  5005.9  150.62
  5015.6  151.36  5020.9  150.75  5026.9  151.67  5046.2  152.53    5138  153.15
  5199.1  154.35  5239.7     156  5285.6  156.44  5324.8   157.8  5356.7  159.86
  5388.7   160.2  5441.9  162.86  5478.3  163.34    5545  166.24  5590.8  167.37
#Mann= 9 ,-1 , 0
    4348     .05       0  4494.2    .035       0  4594.1     .05       0
  4647.7     .07       0    4694      .1       0  4982.9     .05       0
  4987.8      .1       0  5005.9    .035       0  5478.3     .07       0
Bank Sta=4982.9,4987.8
XS Rating Curve= 0 ,0
Exp/Cntr=0.3,0.1

Type RM Length L Ch R = 1 ,18632   ,456,456,456
BEGIN DESCRIPTION:
TRIB 7 TO SPRING CREEK 39.0
END DESCRIPTION:
XS GIS Cut Line= 3
        2590625.       13534175.        2589975.       13534025.
      2589324.97     13534575.03
#Sta/Elev= 30
  4341.2   165.9  4402.8  164.59  4498.6  161.79  4626.9  156.21  4685.7   154.4
  4785.9  152.32  4890.5  150.85    4957   150.8  4995.5  150.26  4995.9  149.76
  5000.2  149.76  5000.5  150.26  5090.8  151.76  5136.1  152.41  5327.4  156.11
    5356   157.3  5391.2  157.82  5440.1  159.49  5469.2  159.75  5497.7   160.6
    5512  161.41  5519.2  162.64  5548.7  162.36    5590  162.84  5618.6   164.1
  5732.8  167.09  5760.3  167.79  5809.7  169.94  5834.4  170.14  5859.8  170.24
#Mann= 12 ,-1 , 0
  4341.2     .05       0  4685.7    .035       0  4785.9      .1       0
  4890.5    .035       0  4995.5    .035       0  5000.5    .035       0
  5090.8     .07       0  5136.1    .035       0  5440.1     .07       0
  5548.7    .035       0  5732.8     .07       0  5834.4    .035       0
Bank Sta=4995.5,5000.5
XS Rating Curve= 0 ,0
Exp/Cntr=0.3,0.1

Type RM Length L Ch R = 1 ,18176   ,426,426,426
BEGIN DESCRIPTION:
TRIB 7 TO SPRING CREEK 38.0
END DESCRIPTION:
XS GIS Cut Line= 3
      2590725.01       13534075.        2589975.       13533625.
      2589324.97       13533575.
#Sta/Elev= 30
  4135.7     167    4194  165.92    4334  162.18  4413.7  159.34  4520.6  155.06
  4637.2  151.82  4695.5  150.63  4784.9  150.14  4860.3  150.28  4917.1   150.2
  4944.3  149.62  4959.8  148.98  4984.5  148.68  4984.9  148.18  4989.2  148.18
  4989.6  148.68  4996.7  149.33  5002.6  149.21  5007.4  149.77  5030.4  150.33
  5070.5  150.32  5120.7  151.11  5150.8   150.8  5210.9  150.89  5301.2   151.8
  5351.4   152.8  5412.7  154.57  5461.7   156.4    5582  161.84  5662.3   164.7
#Mann= 5 ,-1 , 0
  4135.7     .05       0  4860.3    .035       0  4984.5    .035       0
  4989.6    .035       0  5412.7     .05       0
Bank Sta=4984.5,4989.6
XS Rating Curve= 0 ,0
Exp/Cntr=0.3,0.1

Type RM Length L Ch R = 1 ,17750   ,505,505,505
BEGIN DESCRIPTION:
TRIB 7 TO SPRING CREEK 37.0
END DESCRIPTION:
XS GIS Cut Line= 3
      2590974.99     13534074.99        2590175.       13533275.
      2589174.98       13533575.
#Sta/Elev= 30
  3863.5  170.18  3948.3  168.82  4047.3  166.59  4202.9  162.59  4457.5  155.22
  4598.9  152.19    4910  149.82  5008.8  149.55  5009.2  149.05  5013.6  149.05
    5014  149.55  5181.9  150.27    5228  150.19  5264.5  150.09    5368  150.03
  5467.3  150.27  5558.6  152.19  5604.7  153.46  5631.7  154.67  5637.8  155.18
    5643  155.22  5702.9  157.92  5709.1  157.95  5742.2  159.44  5747.4  159.42
  5788.3  161.41  5879.7  164.95  5884.9  164.89  5984.1  167.16  6038.9  168.08
#Mann= 7 ,-1 , 0
  3863.5     .05       0  5008.8     .05       0    5014     .05       0
    5228      .1       0  5264.5     .05       0    5368    .035       0
  5702.9     .05       0
Bank Sta=5008.8,5014
XS Rating Curve= 0 ,0
Exp/Cntr=0.3,0.1

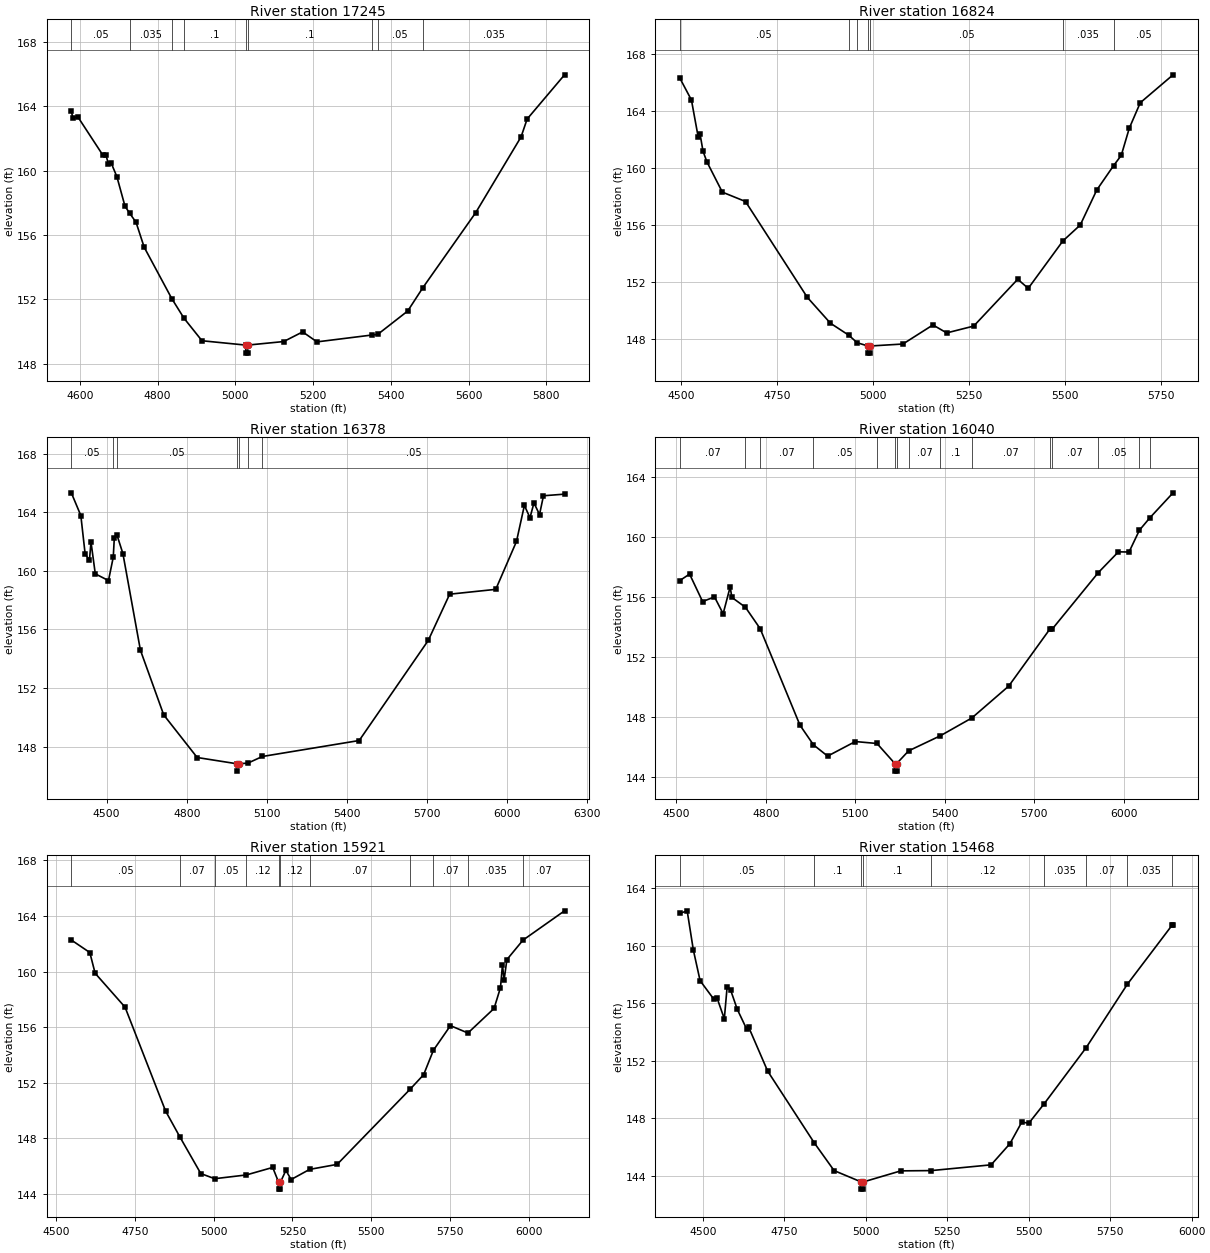
Type RM Length L Ch R = 1 ,17245   ,421,421,421
BEGIN DESCRIPTION:
Mapping XS 2d8d92af
END DESCRIPTION:
XS GIS Cut Line= 3
      2590252.92     13532657.92      2589931.72     13532948.73
      2589215.62      13533378.4
#Sta/Elev= 30
  4578.3  163.73  4581.8  163.31    4596  163.32  4659.5  160.97    4667  161.01
  4673.7  160.42  4681.2  160.46  4695.4  159.64  4716.3   157.8  4728.3  157.36
  4744.7   156.8  4765.6  155.25  4836.9  152.04  4868.1  150.83  4914.3  149.43
  5026.7  149.16  5027.1  148.66  5031.6  148.66    5032  149.16  5124.4  149.38
  5173.2  149.98  5210.1  149.36  5352.7  149.79    5366  149.82  5443.4  151.28
  5482.6  152.74  5618.3   157.4  5734.9  162.11  5750.5  163.22  5846.7  165.97
#Mann= 9 ,-1 , 0
  4578.3     .05       0  4728.3    .035       0  4836.9     .05       0
  4868.1      .1       0  5026.7     .05       0    5032      .1       0
  5352.7    .035       0    5366     .05       0  5482.6    .035       0
Bank Sta=5026.7,5032
XS Rating Curve= 0 ,0
Exp/Cntr=0.3,0.1

Type RM Length L Ch R = 1 ,16824   ,446,446,446
BEGIN DESCRIPTION:
TRIB 7 TO SPRING CREEK 35.0
END DESCRIPTION:
XS GIS Cut Line= 3
      2590175.05       13532575.        2589675.       13532625.
      2589074.98     13533125.02
#Sta/Elev= 30
  4497.2  166.32  4527.4  164.78    4545  162.18    4550  162.36  4557.5  161.19
  4567.6  160.44  4607.8  158.31  4668.1  157.65  4828.9  150.92  4889.2   149.1
  4936.8  148.26  4958.7  147.73    4987   147.5  4987.4     147  4991.9     147
  4992.3   147.5  5077.8  147.64  5155.9  148.98  5191.7  148.42    5262   148.9
  5376.6  152.19  5403.9  151.55  5494.1  154.88  5539.3     156  5582.3  158.46
  5626.3  160.18    5646  160.89  5666.9   162.8  5695.5  164.59  5780.8  166.55
#Mann= 7 ,-1 , 0
  4497.2     .05       0  4936.8      .1       0  4958.7     .05       0
    4987     .05       0  4992.3     .05       0  5494.1    .035       0
  5626.3     .05       0
Bank Sta=4987,4992.3
XS Rating Curve= 0 ,0
Exp/Cntr=0.3,0.1

Type RM Length L Ch R = 1 ,16378   ,338,338,338
BEGIN DESCRIPTION:
TRIB 7 TO SPRING CREEK 34.0
END DESCRIPTION:
XS GIS Cut Line= 3
      2590174.99       13532525.        2589625.       13532225.
      2588925.03     13533224.96
#Sta/Elev= 30
  4367.9  165.32  4403.5  163.77  4419.6  161.15  4435.8  160.71  4441.5  161.97
  4457.6  159.79    4507  159.33  4524.9  160.92  4528.8  162.22  4538.3  162.47
  4561.1  161.17  4626.6  154.58  4713.9  150.16  4839.2  147.25  4988.8  146.82
  4989.3  146.32  4994.2  146.82  5029.6  146.87  5083.3  147.32    5446  148.41
  5704.5  155.24  5784.8   158.4  5957.4  158.73    6035     162  6064.6  164.46
  6085.6  163.62  6100.4  164.63  6121.3  163.84  6136.1  165.12    6215  165.23
#Mann= 7 ,-1 , 0
  4367.9     .05       0  4524.9     .07       0  4538.3     .05       0
  4988.8     .05       0  4994.2     .05       0  5029.6     .07       0
  5083.3     .05       0
Bank Sta=4988.8,4994.2
XS Rating Curve= 0 ,0
Exp/Cntr=0.3,0.1

Type RM Length L Ch R = 1 ,16040   ,119,119,119
BEGIN DESCRIPTION:
Mapping XS 5ef024b5
END DESCRIPTION:
XS GIS Cut Line= 3
       2589975.1     13531733.47       2589519.4     13531928.77
      2588434.33     13532332.41
#Sta/Elev= 30
  4511.4   157.1  4544.1  157.53  4587.7   155.7  4627.6  156.01  4656.6  154.89
  4680.2  156.68  4685.7  155.98  4731.3  155.32  4780.6   153.9  4914.1  147.47
  4959.4  146.16  5006.9  145.41  5099.7  146.38  5172.4  146.25  5232.5  144.91
  5232.9  144.41  5237.8  144.41  5238.3  144.91  5278.4  145.76  5384.4  146.76
  5490.4  147.95  5613.9  150.07  5752.4  153.88  5759.5  153.86  5914.4  157.63
  5981.7  159.01  6017.4     159  6052.1  160.45  6087.3  161.28  6164.9  162.94
#Mann= 15 ,-1 , 0
  4511.4     .07       0  4731.3     .05       0  4780.6     .07       0
  4959.4     .05       0  5172.4     .12       0  5232.5     .05       0
  5238.3     .12       0  5278.4     .07       0  5384.4      .1       0
  5490.4     .07       0  5752.4    .035       0  5759.5     .07       0
  5914.4     .05       0  6052.1     .07       0  6087.3     .05       0
Bank Sta=5232.5,5238.3
XS Rating Curve= 0 ,0
Exp/Cntr=0.3,0.1

Type RM Length L Ch R = 1 ,15921   ,453,453,453
BEGIN DESCRIPTION:
TRIB 7 TO SPRING CREEK 33.0
END DESCRIPTION:
XS GIS Cut Line= 3
      2589875.02     13531624.99        2589475.       13531825.
      2588374.97     13532025.01
#Sta/Elev= 30
  4548.3  162.27    4607  161.37  4623.8  159.88  4718.8  157.44  4847.4  149.97
  4892.7  148.11  4959.2  145.47  5003.3   145.1  5103.7  145.37  5187.4  145.91
  5206.1  144.85  5206.5  144.35  5211.4  144.35  5211.9  144.85  5229.3   145.7
  5245.8  145.04  5304.6  145.77  5391.9  146.13  5623.6  151.54  5666.4  152.58
  5697.4  154.34  5751.5  156.11    5807  155.58    5890  157.35  5910.3  158.85
  5916.6  160.49  5921.7  159.38  5930.6  160.86  5981.6  162.26  6113.6  164.37
#Mann= 11 ,-1 , 0
  4548.3     .05       0  4892.7     .07       0  5003.3     .05       0
  5103.7     .12       0  5206.1     .05       0  5211.9     .12       0
  5304.6     .07       0  5623.6    .035       0  5697.4     .07       0
    5807    .035       0  5981.6     .07       0
Bank Sta=5206.1,5211.9
XS Rating Curve= 0 ,0
Exp/Cntr=0.3,0.1

Type RM Length L Ch R = 1 ,15468   ,218,218,218
BEGIN DESCRIPTION:
TRIB 7 TO SPRING CREEK 32.0
END DESCRIPTION:
XS GIS Cut Line= 3
      2589875.04     13531575.01        2589325.       13531425.
      2588525.02     13531924.99
#Sta/Elev= 30
  4429.4  162.24  4451.9  162.42  4470.9  159.69  4491.6  157.56  4533.1  156.29
  4543.5  156.36  4565.9  154.91  4574.6  157.14  4584.9  156.93  4605.6  155.57
    4635  154.17  4640.2  154.35  4698.9  151.27  4841.6  146.29  4902.8  144.35
    4986  143.56  4986.5  143.06  4991.8  143.06  4992.3  143.56  5107.4  144.33
  5201.2  144.35  5384.6  144.75  5442.3  146.22  5478.9  147.73  5500.1  147.64
  5547.5     149  5676.2   152.9  5802.9  157.32  5940.6  161.44  5942.9  161.44
#Mann= 9 ,-1 , 0
  4429.4     .05       0  4841.6      .1       0    4986     .05       0
  4992.3      .1       0  5201.2     .12       0  5547.5    .035       0
  5676.2     .07       0  5802.9    .035       0  5940.6     .07       0
Bank Sta=4986,4992.3
XS Rating Curve= 0 ,0
Exp/Cntr=0.3,0.1

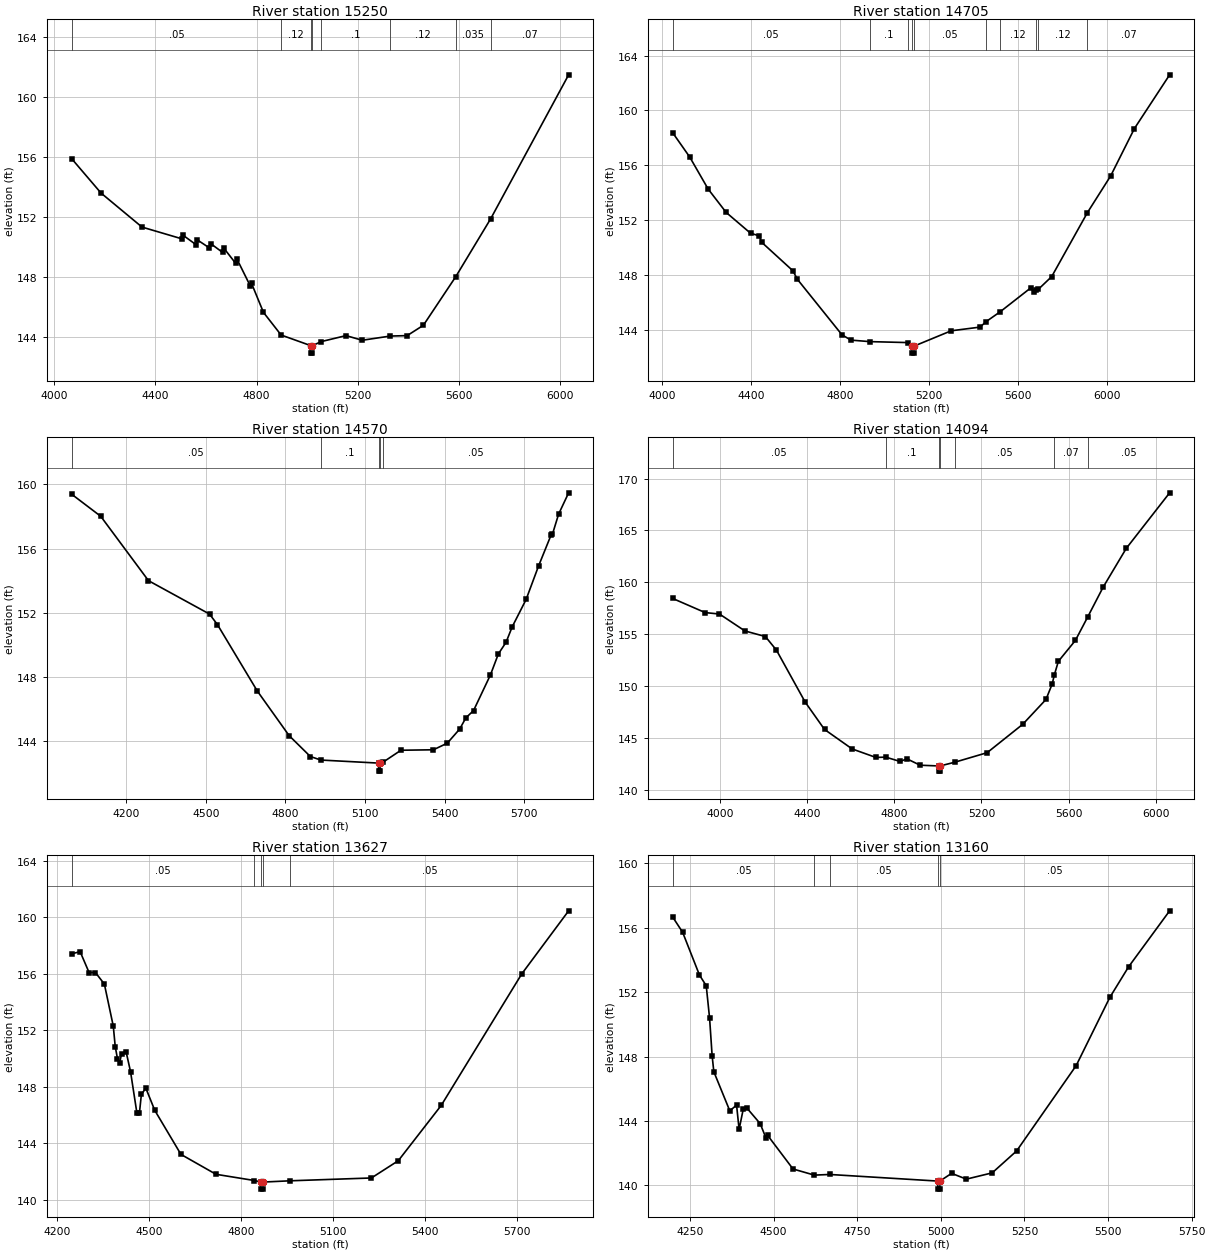
Type RM Length L Ch R = 1 ,15250   ,545,545,545
BEGIN DESCRIPTION:
Mapping XS 544a2413
END DESCRIPTION:
XS GIS Cut Line= 3
      2590192.15     13531047.69      2589280.68      13531221.3
      2588474.84     13531871.18
#Sta/Elev= 30
  4069.5  155.91  4186.2   153.6  4347.8  151.33  4504.3  150.55  4509.4  150.79
  4561.6  150.15  4566.7  150.47  4613.8  149.94  4618.8  150.23  4665.9  149.64
    4671  149.92  4718.1   148.9  4723.2  149.18  4775.4   147.4  4780.4  147.57
  4827.5  145.63  4897.2  144.12  5014.4  143.41  5014.9  142.91  5020.3  142.91
  5020.8  143.41  5055.6  143.68  5153.5  144.08  5217.5  143.77  5328.1  144.05
    5395  144.08    5459  144.77    5587  148.02  5725.3   151.9  6032.6   161.5
#Mann= 8 ,-1 , 0
  4069.5     .05       0  4897.2     .12       0  5014.4     .05       0
  5020.8     .12       0  5055.6      .1       0  5328.1     .12       0
    5587    .035       0  5725.3     .07       0
Bank Sta=5014.4,5020.8
XS Rating Curve= 0 ,0
Exp/Cntr=0.3,0.1

Type RM Length L Ch R = 1 ,14705   ,135,135,135
BEGIN DESCRIPTION:
TRIB 7 TO SPRING CREEK 31.0
END DESCRIPTION:
XS GIS Cut Line= 3
      2590074.99       13530725.      2589123.51     13530785.49
      2588374.98     13531825.03
#Sta/Elev= 30
  4046.6  158.39  4123.6  156.61  4206.9  154.26  4287.6  152.56  4397.3  151.04
  4436.5  150.85  4447.4  150.38  4587.7   148.3  4607.7  147.68  4808.1  143.63
  4848.2  143.24  4933.2  143.13  5103.1  143.06    5124  142.79  5124.5  142.29
    5130  142.29  5130.5  142.79  5299.1  143.92  5429.2  144.19  5455.4  144.58
  5520.4  145.32  5657.5  147.06  5672.2  146.77  5679.9  146.91  5691.1  146.95
  5751.1  147.88  5911.7  152.55  6015.9  155.22  6122.7  158.68    6281   162.6
#Mann= 10 ,-1 , 0
  4046.6     .05       0  4933.2      .1       0  5103.1     .05       0
    5124     .05       0  5130.5     .05       0  5455.4      .1       0
  5520.4     .12       0  5679.9     .05       0  5691.1     .12       0
  5911.7     .07       0
Bank Sta=5124,5130.5
XS Rating Curve= 0 ,0
Exp/Cntr=0.3,0.1

Type RM Length L Ch R = 1 ,14570   ,476,476,476
BEGIN DESCRIPTION:
TRIB 7 TO SPRING CREEK 30.0
END DESCRIPTION:
XS GIS Cut Line= 3
      2590124.98       13530675.        2589125.       13530675.
        2588325.       13531025.
#Sta/Elev= 30
  3993.7   159.4  4103.7  158.02  4283.7  154.01  4513.7  151.93  4543.7  151.27
  4693.7  147.14  4813.7  144.36  4893.7  143.06  4933.2  142.84  5150.6  142.65
  5151.1  142.15  5156.7  142.15  5157.2  142.65  5167.8  142.71    5235  143.45
  5357.4  143.48  5409.6  143.89  5456.4  144.77  5479.8  145.47  5508.6  145.92
  5572.2  148.14  5602.2  149.45    5631  150.17  5654.4  151.14  5706.7  152.84
  5753.5  154.92  5800.2  156.83  5805.7  156.89  5829.1  158.15  5866.9  159.48
#Mann= 5 ,-1 , 0
  3993.7     .05       0  4933.2      .1       0  5150.6     .05       0
  5157.2      .1       0  5167.8     .05       0
Bank Sta=5150.6,5157.2
XS Rating Curve= 0 ,0
Exp/Cntr=0.3,0.1

Type RM Length L Ch R = 1 ,14094   ,467,467,467
BEGIN DESCRIPTION:
TRIB 7 TO SPRING CREEK 29.0
END DESCRIPTION:
XS GIS Cut Line= 3
      2590025.02       13530575.        2588825.       13530375.
      2588024.99     13531075.01
#Sta/Elev= 30
  3783.4  158.45    3933  157.08  3998.8  156.94  4115.4  155.31  4209.2  154.77
  4259.9  153.46  4391.7  148.45  4480.4  145.81  4607.1  143.93  4716.1  143.11
    4761  143.14  4827.6  142.72    4858  142.98  4918.9  142.36  5003.8  142.29
  5004.3  141.79  5009.9  141.79  5010.4  142.29  5077.9  142.65  5226.3  143.57
  5389.6  146.31  5495.9   148.7  5524.4  150.19  5534.5  151.08  5552.8  152.38
  5630.7  154.39  5686.9  156.64  5757.8  159.52  5864.1  163.27    6063  168.63
#Mann= 7 ,-1 , 0
  3783.4     .05       0    4761      .1       0  5003.8     .05       0
  5010.4      .1       0  5077.9     .05       0  5534.5     .07       0
  5686.9     .05       0
Bank Sta=5003.8,5010.4
XS Rating Curve= 0 ,0
Exp/Cntr=0.3,0.1

Type RM Length L Ch R = 1 ,13627   ,467,467,467
BEGIN DESCRIPTION:
TRIB 7 TO SPRING CREEK 28.0
END DESCRIPTION:
XS GIS Cut Line= 3
      2589374.97     13529475.02        2588775.       13529925.
      2587974.98     13530275.01
#Sta/Elev= 30
  4246.2  157.41  4274.3  157.57  4303.5  156.09  4324.3  156.09  4353.5  155.27
  4382.6  152.29  4388.9  150.85  4396.2  149.99  4403.5  149.71  4409.7  150.35
  4424.3  150.49  4438.9  149.07  4459.7  146.14    4468  146.15  4474.3  147.46
  4488.9   147.9    4518  146.33  4603.5  143.21    4718   141.8  4843.3  141.36
  4864.7  141.25  4865.2  140.75  4870.9  140.75  4871.4  141.25  4960.4  141.34
  5225.4  141.54  5313.1  142.76  5453.4  146.68  5716.6     156  5869.4  160.46
#Mann= 5 ,-1 , 0
  4246.2     .05       0  4843.3      .1       0  4864.7     .05       0
  4871.4      .1       0  4960.4     .05       0
Bank Sta=4864.7,4871.4
XS Rating Curve= 0 ,0
Exp/Cntr=0.3,0.1

Type RM Length L Ch R = 1 ,13160   ,455,455,455
BEGIN DESCRIPTION:
TRIB 7 TO SPRING CREEK 27.0
END DESCRIPTION:
XS GIS Cut Line= 3
      2589275.02       13529475.        2588475.       13529575.
      2587925.01     13529974.99
#Sta/Elev= 30
  4197.8  156.68    4228  155.72  4278.4  153.06  4298.6   152.4  4308.7  150.37
  4316.2  148.06  4321.3  147.06  4369.1  144.63  4389.3  144.99  4396.9  143.48
  4409.4  144.75  4419.5  144.82  4459.8  143.84  4477.5  142.93  4482.5   143.1
  4558.1  141.02  4621.9  140.64  4667.9  140.68  4990.6  140.27  4991.1  139.77
  4996.8  139.77  4997.3  140.27  5032.2  140.75  5076.3  140.39  5153.6  140.78
  5226.6  142.14  5404.7  147.44  5505.2  151.67  5561.6  153.58  5684.1  157.05
#Mann= 5 ,-1 , 0
  4197.8     .05       0  4621.9      .1       0  4667.9     .05       0
  4990.6     .05       0  4997.3     .05       0
Bank Sta=4990.6,4997.3
XS Rating Curve= 0 ,0
Exp/Cntr=0.3,0.1

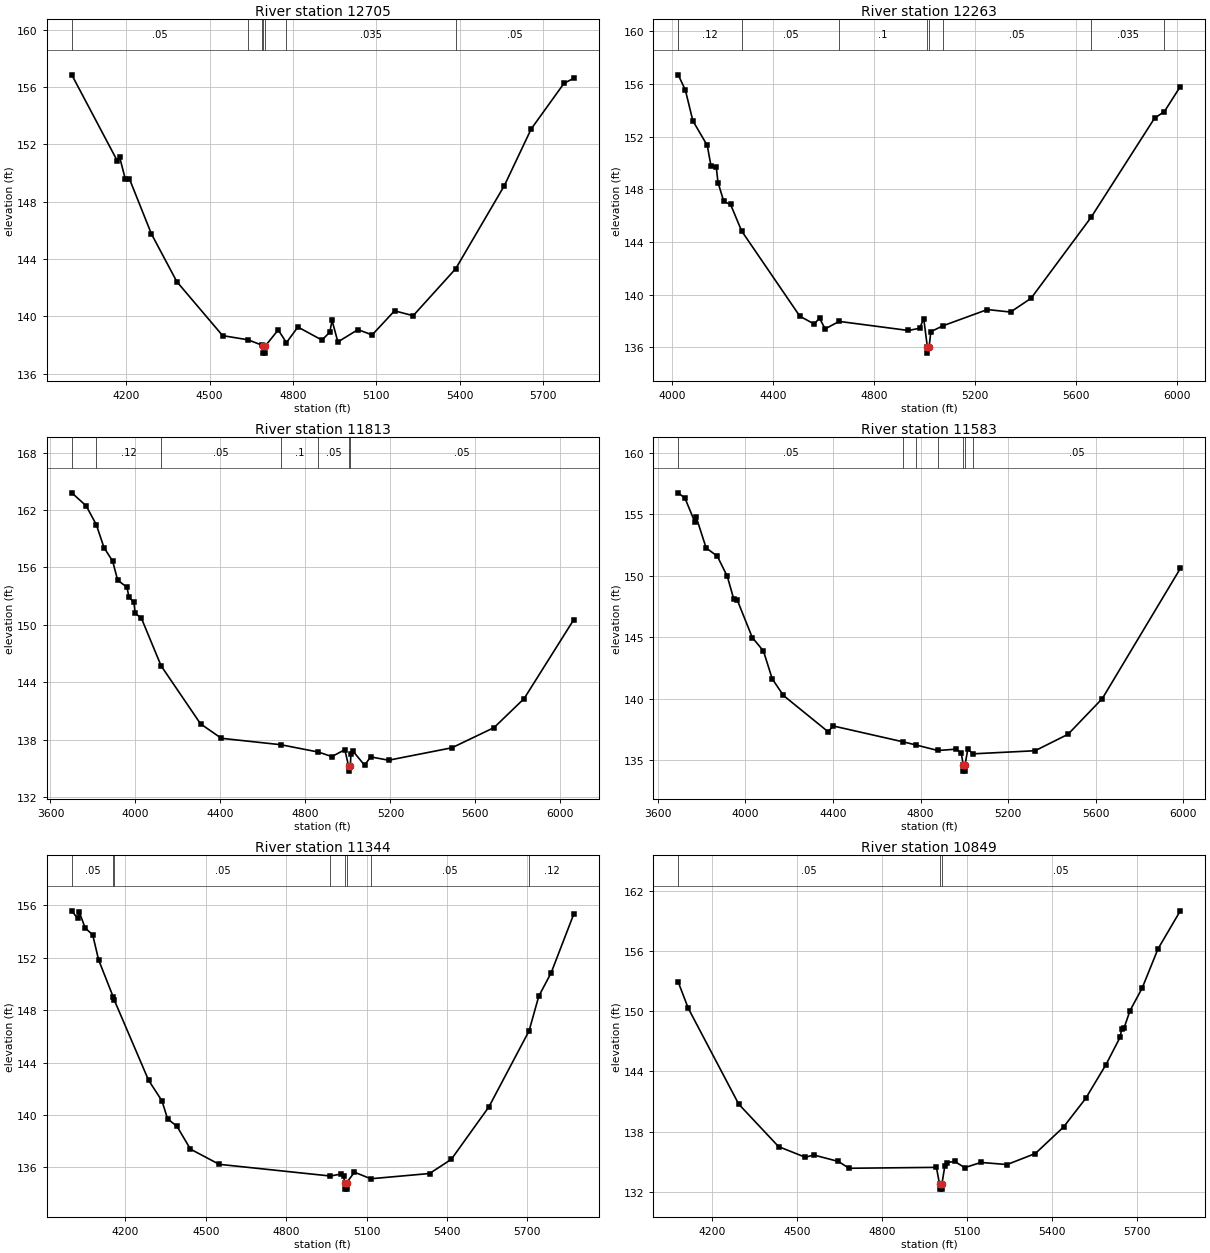
Type RM Length L Ch R = 1 ,12705   ,442,442,442
BEGIN DESCRIPTION:
TRIB 7 TO SPRING CREEK 26.0
END DESCRIPTION:
XS GIS Cut Line= 3
      2588874.99     13528425.02        2588275.       13529225.
        2587875.       13529925.
#Sta/Elev= 30
  4004.4  156.85  4167.9  150.86  4176.3  151.13  4197.1  149.57  4211.7   149.6
  4290.8  145.76  4382.5  142.42  4547.1  138.66  4638.5  138.37  4687.9     138
  4693.5  137.94    4694  137.44  4700.2  137.44  4700.7  137.94  4747.1  139.06
  4776.6  138.17  4817.9  139.26  4904.4  138.35  4932.5   138.9  4940.8  139.72
  4961.7  138.22  5033.9  139.08    5085  138.71  5165.6  140.39  5232.6  140.05
  5385.7  143.33  5560.8  149.13  5657.3  153.08  5775.3  156.26  5810.6  156.61
#Mann= 7 ,-1 , 0
  4004.4     .05       0  4638.5    .035       0  4687.9     .05       0
  4693.5    .035       0  4700.7     .05       0  4776.6    .035       0
  5385.7     .05       0
Bank Sta=4693.5,4700.7
XS Rating Curve= 0 ,0
Exp/Cntr=0.3,0.1

Type RM Length L Ch R = 1 ,12263   ,450,450,450
BEGIN DESCRIPTION:
TRIB 7 TO SPRING CREEK 25.0
END DESCRIPTION:
XS GIS Cut Line= 3
      2588824.96     13528325.03        2588025.       13528875.
        2587825.     13529875.02
#Sta/Elev= 30
  4024.5   156.7  4052.9  155.53  4082.6   153.2  4139.5  151.34  4154.4  149.78
  4175.3  149.69  4182.2  148.52  4205.1  147.08  4232.1  146.85  4275.8  144.84
  4506.8  138.36  4563.6  137.77  4584.6  138.22  4606.9   137.4  4662.4  137.97
  4937.1  137.28  4981.8  137.45  4997.8  138.19    5012  136.06  5012.5  135.56
  5019.4  136.06  5025.9  137.19  5074.5  137.64  5250.2  138.87    5342  138.68
  5423.6  139.73  5661.5  145.88  5913.1  153.41    5952  153.91  6015.1  155.81
#Mann= 8 ,-1 , 0
  4024.5     .12       0  4275.8     .05       0  4662.4      .1       0
    5012     .05       0  5019.4      .1       0  5074.5     .05       0
  5661.5    .035       0    5952     .05       0
Bank Sta=5012,5019.4
XS Rating Curve= 0 ,0
Exp/Cntr=0.3,0.1

Type RM Length L Ch R = 1 ,11813   ,230,230,230
BEGIN DESCRIPTION:
TRIB 7 TO SPRING CREEK 24.0
END DESCRIPTION:
XS GIS Cut Line= 3
      2588974.96     13528125.02        2587775.       13528625.
      2586974.98     13529325.02
#Sta/Elev= 30
  3700.4  163.79  3768.1  162.43    3816  160.46    3852  158.07  3892.7  156.65
  3916.5  154.66  3960.4  153.92  3969.6  152.88  3992.9  152.36  3998.8   151.2
  4028.1  150.69  4120.7  145.72  4306.5  139.65  4404.5  138.14  4684.1  137.47
  4861.6   136.7  4924.5  136.23  4985.7  136.95  5003.4  135.21  5003.9  134.71
  5011.5  135.21  5014.1  136.52  5021.7  136.86  5078.7  135.32  5106.7   136.2
  5191.6  135.85  5489.6  137.15    5688  139.26  5829.4  142.29  6063.4  150.55
#Mann= 7 ,-1 , 0
  3700.4     .05       0    3816     .12       0  4120.7     .05       0
  4684.1      .1       0  4861.6     .05       0  5003.4     .05       0
  5011.5     .05       0
Bank Sta=5003.4,5011.5
XS Rating Curve= 0 ,0
Exp/Cntr=0.3,0.1

Type RM Length L Ch R = 1 ,11583   ,239,239,239
BEGIN DESCRIPTION:
Mapping XS 1f02a692
END DESCRIPTION:
XS GIS Cut Line= 3
       2588794.6     13527905.32      2587596.66     13528469.57
      2586815.39     13529042.49
#Sta/Elev= 30
    3693  156.76  3723.8  156.32  3769.4  154.36  3774.9  154.79  3820.5  152.27
  3871.6   151.6  3917.2  149.95  3946.8  148.09  3962.8  148.02  4031.1  144.98
  4082.2  143.88  4122.3  141.61  4173.4  140.26  4377.9   137.3    4400  137.78
    4721  136.48  4781.1  136.22  4878.4  135.78  4963.7  135.89  4985.8  135.56
  4994.5   134.6    4995   134.1  5002.2   134.1  5002.7   134.6  5015.3  135.87
  5041.4  135.51  5322.7  135.76  5473.2   137.1  5629.9  140.01    5986   150.6
#Mann= 7 ,-1 , 0
    3693     .05       0    4721      .1       0  4781.1     .05       0
  4878.4      .1       0  4994.5     .05       0  5002.7      .1       0
  5041.4     .05       0
Bank Sta=4994.5,5002.7
XS Rating Curve= 0 ,0
Exp/Cntr=0.3,0.1

Type RM Length L Ch R = 1 ,11344   ,495,495,495
BEGIN DESCRIPTION:
TRIB 7 TO SPRING CREEK 23.0
END DESCRIPTION:
XS GIS Cut Line= 3
      2588075.01     13527474.98        2587475.       13528275.
      2586675.03     13528624.99
#Sta/Elev= 30
  4000.2  155.56  4022.1  154.98  4028.3  155.46  4050.2  154.25  4078.3  153.73
  4100.2  151.83  4154.2  149.03  4159.4  148.73  4286.7  142.65  4336.7  141.08
  4357.5  139.71  4392.9  139.13  4442.9   137.4  4550.2  136.24  4964.6  135.35
  5002.9  135.49  5014.6  135.37    5018  134.85  5018.5  134.35  5025.7  134.35
  5026.2  134.85  5054.8  135.64  5115.7  135.14  5335.1  135.54  5416.2  136.62
  5556.5  140.62  5706.3  146.41  5742.5  149.05  5788.8  150.84  5873.4  155.33
#Mann= 8 ,-1 , 0
  4000.2     .05       0  4154.2     .07       0  4159.4     .05       0
  4964.6      .1       0    5018     .05       0  5026.2      .1       0
  5115.7     .05       0  5706.3     .12       0
Bank Sta=5018,5026.2
XS Rating Curve= 0 ,0
Exp/Cntr=0.3,0.1

Type RM Length L Ch R = 1 ,10849   ,460,460,460
BEGIN DESCRIPTION:
TRIB 7 TO SPRING CREEK 22.0
END DESCRIPTION:
XS GIS Cut Line= 3
        2587925.       13527475.        2587125.       13527925.
      2586574.97     13528575.04
#Sta/Elev= 30
  4082.1   152.9  4117.5  150.28  4295.3  140.73  4435.6   136.5  4529.6  135.44
  4559.8  135.66  4646.5  135.02  4684.1  134.34    4992  134.43    5003  132.76
  5003.5  132.26  5010.8  132.26  5011.3  132.76  5021.4  134.53    5028  134.91
  5056.5  135.02  5091.7   134.4  5148.8  134.92  5241.1  134.71  5340.6  135.81
    5440  138.45    5518   141.3  5589.5  144.67  5638.9  147.38  5645.4  148.25
  5653.2  148.31    5674  150.04  5716.9  152.29  5772.9  156.21  5851.5     160
#Mann= 3 ,-1 , 0
  4082.1     .05       0    5003     .05       0  5011.3     .05       0
Bank Sta=5003,5011.3
XS Rating Curve= 0 ,0
Exp/Cntr=0.3,0.1

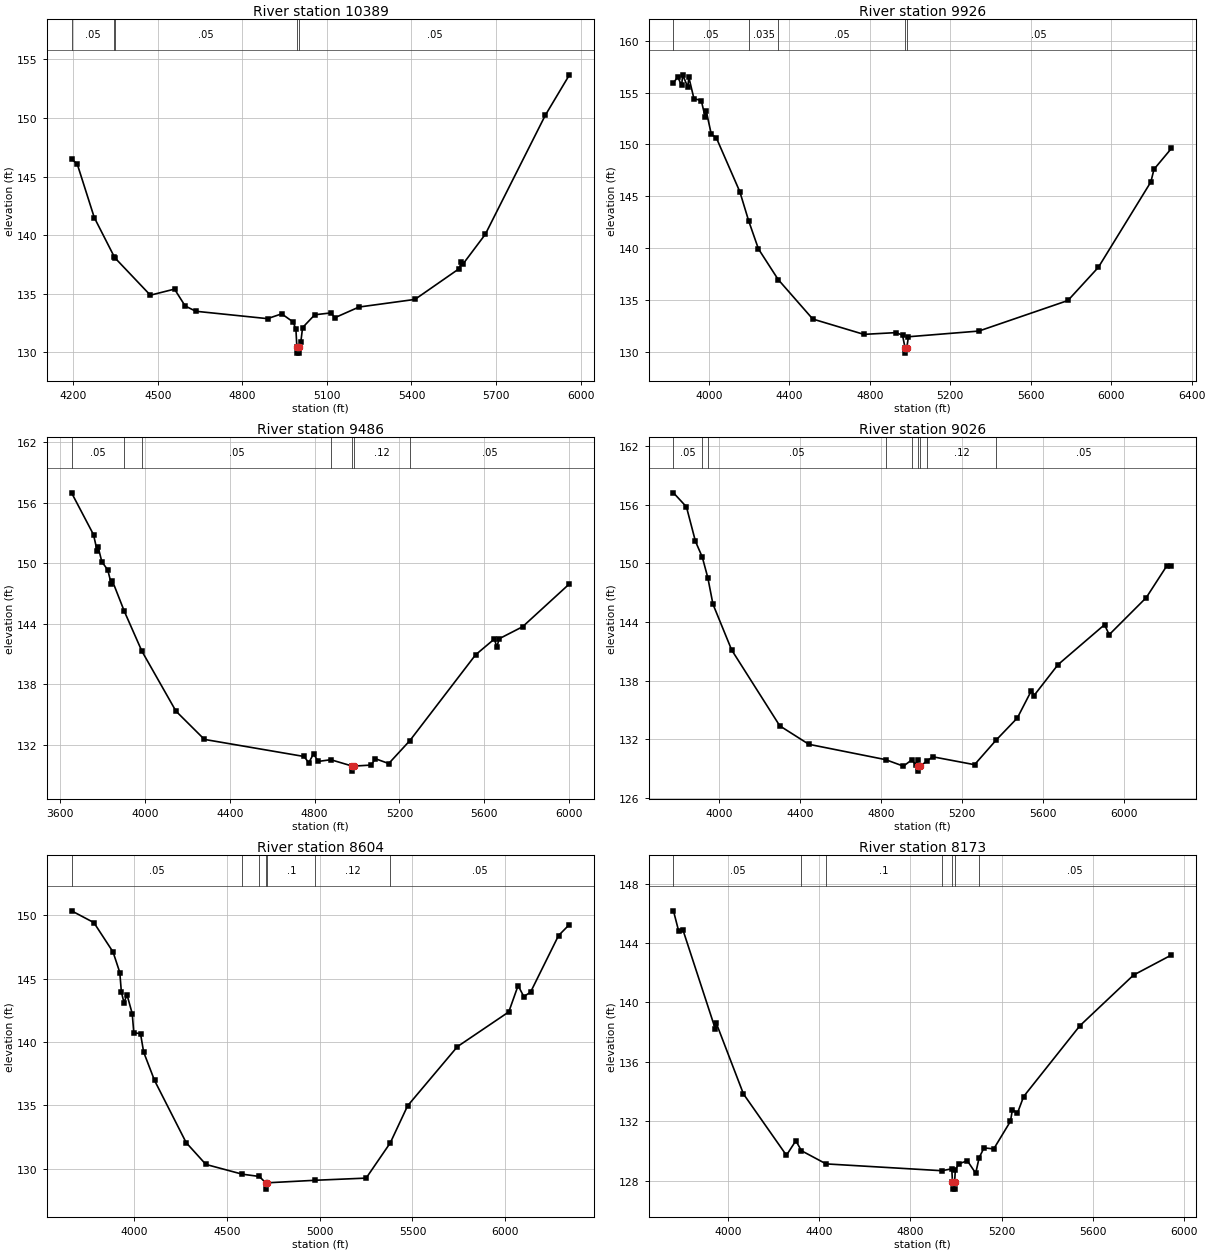
Type RM Length L Ch R = 1 ,10389   ,463,463,463
BEGIN DESCRIPTION:
TRIB 7 TO SPRING CREEK 21.0
END DESCRIPTION:
XS GIS Cut Line= 3
      2587774.96       13527425.        2586975.       13527525.
      2586374.97     13528275.03
#Sta/Elev= 30
  4193.8  146.49  4213.9  146.07  4274.4   141.5  4346.1  138.12  4347.4  138.07
  4473.4  134.88  4559.1   135.4  4596.9  133.96  4634.7  133.51  4889.1  132.88
  4939.5  133.29  4979.8   132.6  4989.9  131.98  4993.3  130.44  4993.8  129.94
  5001.1  129.94  5001.6  130.44  5007.2  130.87  5013.6  132.12  5056.8  133.21
  5114.4  133.37    5128  132.96  5213.7  133.87  5412.2  134.52  5569.1  137.14
  5576.3  137.71  5583.5  137.56  5661.9  140.07  5874.8  150.22  5960.5  153.67
#Mann= 5 ,-1 , 0
  4193.8     .05       0  4346.1    .035       0  4347.4     .05       0
  4993.3     .05       0  5001.6     .05       0
Bank Sta=4993.3,5001.6
XS Rating Curve= 0 ,0
Exp/Cntr=0.3,0.1

Type RM Length L Ch R = 1 ,9926    ,440,440,440
BEGIN DESCRIPTION:
TRIB 7 TO SPRING CREEK 20.0
END DESCRIPTION:
XS GIS Cut Line= 3
      2588024.99       13527475.        2586925.       13527075.
        2586225.       13528175.
#Sta/Elev= 30
  3824.8  155.94  3846.1   156.5  3865.4  155.68  3870.7  156.71  3895.9  155.52
  3901.3  156.47  3926.5  154.42  3963.1  154.22  3982.4  152.64  3987.7  153.21
    4013  150.97  4037.6  150.64  4154.6  145.43  4198.8   142.6  4247.1  139.91
  4345.3  136.95  4517.1  133.14  4771.1  131.66  4931.4  131.83  4963.3  131.57
  4975.8  130.35  4976.3  129.85  4984.1  130.35  4992.6  131.43  5342.4  131.98
  5785.2  134.93  5936.7  138.14  6197.5  146.38  6212.7  147.59  6299.1   149.6
#Mann= 5 ,-1 , 0
  3824.8     .05       0  4198.8    .035       0  4345.3     .05       0
  4975.8     .05       0  4984.1     .05       0
Bank Sta=4975.8,4984.1
XS Rating Curve= 0 ,0
Exp/Cntr=0.3,0.1

Type RM Length L Ch R = 1 ,9486    ,460,460,460
BEGIN DESCRIPTION:
TRIB 7 TO SPRING CREEK 19.0
END DESCRIPTION:
XS GIS Cut Line= 3
      2587925.03     13527375.02        2586725.       13526775.
      2585724.96       13526875.
#Sta/Elev= 30
  3654.5  156.96    3758  152.82  3774.7  151.25  3780.3  151.55  3797.1  150.14
    3825  149.33  3841.8  147.94  3847.4  148.22    3903  145.24  3985.9  141.29
  4146.5  135.35  4280.6  132.55  4750.2  130.86  4772.6  130.24  4794.9  131.12
  4817.3  130.37  4876.3  130.54  4977.5  129.91    4978  129.41  4986.9  129.91
  5066.5  130.01  5086.6  130.64  5149.4  130.16    5249  132.43    5559  140.93
  5646.9  142.48  5659.5   141.7  5669.5  142.51  5780.1   143.7  6001.2  147.95
#Mann= 7 ,-1 , 0
  3654.5     .05       0    3903    .035       0  3985.9     .05       0
  4876.3     .12       0  4977.5     .05       0  4986.9     .12       0
    5249     .05       0
Bank Sta=4977.5,4986.9
XS Rating Curve= 0 ,0
Exp/Cntr=0.3,0.1

Type RM Length L Ch R = 1 ,9026    ,422,422,422
BEGIN DESCRIPTION:
TRIB 7 TO SPRING CREEK 18.0
END DESCRIPTION:
XS GIS Cut Line= 3
      2587874.99     13527224.99        2586875.       13526525.
      2585674.97     13526825.01
#Sta/Elev= 30
  3774.1  157.24  3838.2   155.8  3882.6  152.27  3916.4  150.65  3943.8  148.53
    3969  145.83  4061.4  141.13    4299  133.35  4442.4  131.46  4820.8  129.89
  4909.3  129.22  4950.8  129.87  4972.5  129.29  4981.2  129.86  4982.6  129.21
  4983.1  128.71    4992  129.21  5024.1  129.73    5054  130.18  5260.2  129.37
  5367.6  131.91  5471.5  134.16  5541.1  136.97  5553.9  136.46  5672.5  139.63
  5901.8  143.72    5925   142.7    6108   146.5  6208.5  149.73  6231.7  149.72
#Mann= 9 ,-1 , 0
  3774.1     .05       0  3916.4    .035       0  3943.8     .05       0
  4820.8     .12       0  4950.8      .1       0  4982.6     .05       0
    4992      .1       0  5024.1     .12       0  5367.6     .05       0
Bank Sta=4982.6,4992
XS Rating Curve= 0 ,0
Exp/Cntr=0.3,0.1

Type RM Length L Ch R = 1 ,8604    ,431,431,431
BEGIN DESCRIPTION:
TRIB 7 TO SPRING CREEK 17.0
END DESCRIPTION:
XS GIS Cut Line= 3
      2588075.01     13525574.99        2586875.       13526175.
      2585674.99       13526775.
#Sta/Elev= 30
  3662.7  150.36  3782.9  149.43  3886.3  147.11  3922.7  145.49    3931  143.97
    3945  143.12  3961.8  143.72  3989.7  142.24  3998.1  140.75  4034.5  140.65
  4051.2  139.21  4109.9  136.97  4280.4  132.06  4386.6  130.34  4582.6  129.57
  4674.5  129.39  4708.9  128.89  4709.4  128.39  4718.4  128.89  4977.3  129.09
  5250.3  129.26  5380.3  132.04  5473.9  134.97  5742.3  139.64    6019  142.38
  6069.3  144.46    6100  143.59  6136.4  143.94  6287.3  148.41    6346  149.28
#Mann= 7 ,-1 , 0
  3662.7     .05       0  4582.6     .07       0  4674.5      .1       0
  4708.9     .05       0  4718.4      .1       0  4977.3     .12       0
  5380.3     .05       0
Bank Sta=4708.9,4718.4
XS Rating Curve= 0 ,0
Exp/Cntr=0.3,0.1

Type RM Length L Ch R = 1 ,8173    ,458,458,458
BEGIN DESCRIPTION:
TRIB 7 TO SPRING CREEK 16.0
END DESCRIPTION:
XS GIS Cut Line= 3
      2587824.96     13525625.01        2586625.       13525925.
      2585824.99     13526425.01
#Sta/Elev= 30
  3762.5  146.17  3785.6  144.79  3803.7   144.9  3945.4  138.23  3950.6  138.58
  4069.1  133.83  4257.2   129.7  4298.5  130.68  4322.7  130.01  4430.8  129.12
  4938.3  128.66  4981.3  128.79  4984.3  127.92  4984.8  127.42  4993.4  127.42
  4993.9  127.92  4996.8  128.73  5012.9  129.13  5049.5  129.33  5086.1  128.49
  5101.1  129.54  5122.6   130.2  5165.1  130.13  5238.2  131.99    5247  132.78
  5268.8  132.54    5296  133.66  5542.4  138.43  5777.1  141.84  5942.8  143.19
#Mann= 7 ,-1 , 0
  3762.5     .05       0  4322.7     .07       0  4430.8      .1       0
  4938.3     .12       0  4984.3     .05       0  4993.9     .12       0
  5101.1     .05       0
Bank Sta=4984.3,4993.9
XS Rating Curve= 0 ,0
Exp/Cntr=0.3,0.1