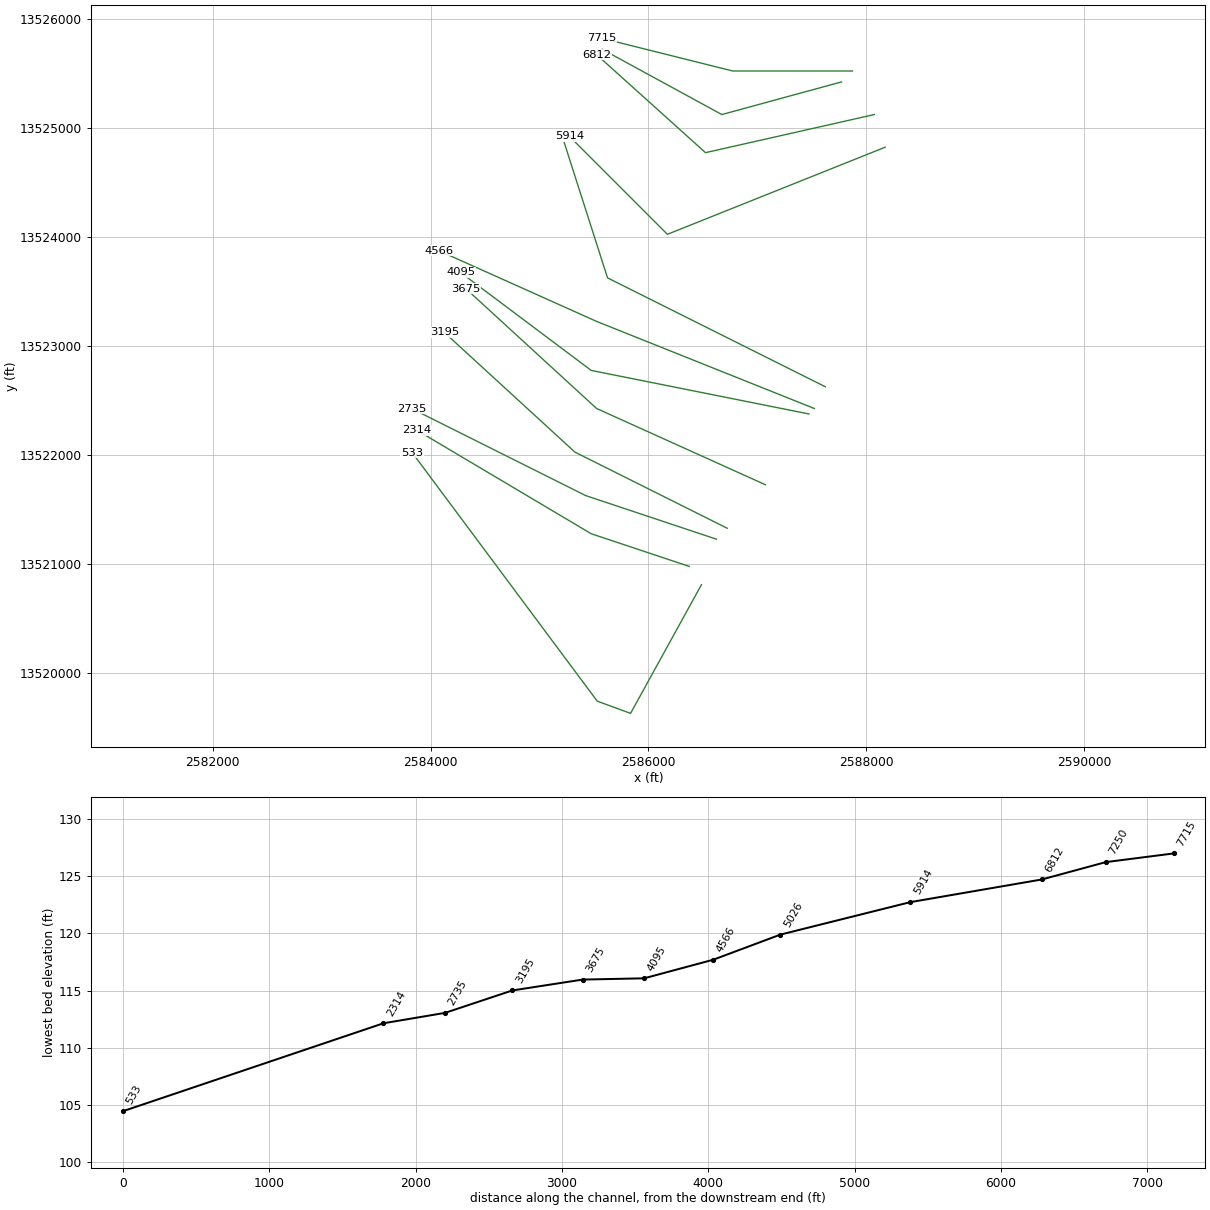
HEC-RAS study TRIB 7 TO SPRING CREEK.prj: TRIB 7 TO SPRING CREEK Base Level Engineering

--- TRIB 7 TO SPRING CREEK.g01 (geometry) --- (continued)

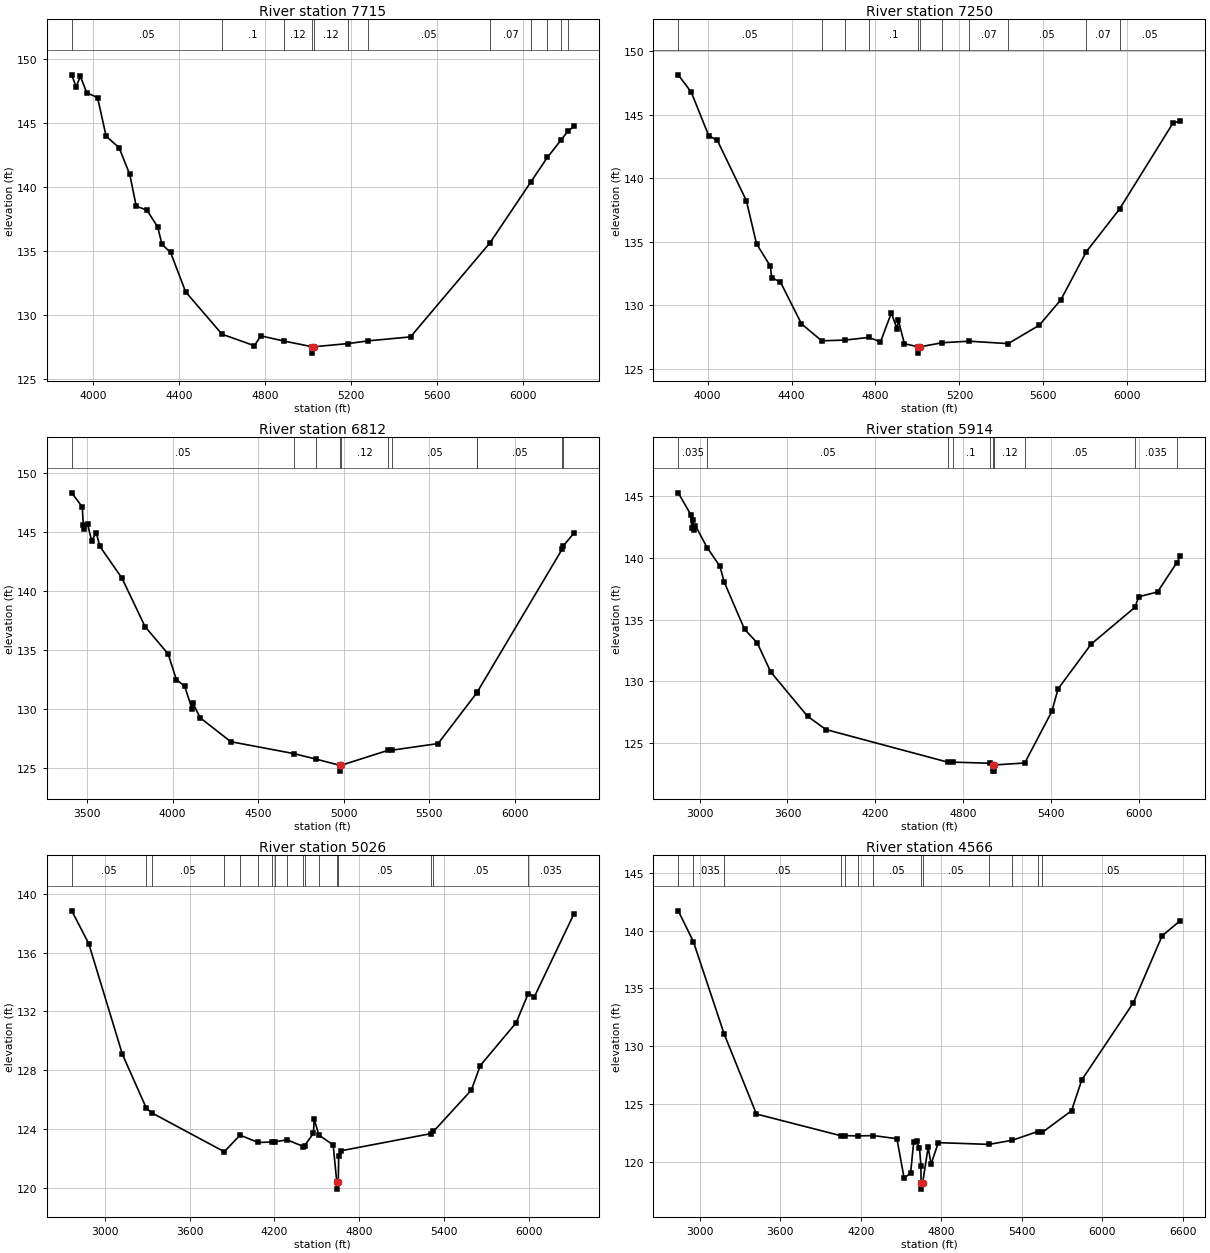
Type RM Length L Ch R = 1 ,7715    ,465,465,465
BEGIN DESCRIPTION:
TRIB 7 TO SPRING CREEK 15.0
END DESCRIPTION:
XS GIS Cut Line= 3
      2587875.01       13525525.        2586775.       13525525.
      2585575.04     13525824.99
#Sta/Elev= 30
  3900.4  148.75  3920.4  147.81  3940.4  148.62  3970.4  147.35  4020.4  146.97
  4060.4  143.95  4120.4  143.06  4170.4  140.96  4200.4  138.48  4250.4  138.17
  4300.4  136.85  4320.4  135.49  4360.4  134.86  4430.4  131.78  4599.6  128.47
  4750.4  127.57  4780.4  128.34  4886.5  127.94  5018.8  127.49  5019.3  126.99
  5028.4  127.49  5188.3  127.74  5280.6  127.95  5477.1  128.26  5847.1  135.62
  6037.5  140.38    6114  142.29  6179.6  143.69  6208.9  144.33  6237.3  144.71
#Mann= 12 ,-1 , 0
  3900.4     .05       0  4599.6      .1       0  4886.5     .12       0
  5018.8     .05       0  5028.4     .12       0  5188.3     .07       0
  5280.6     .05       0  5847.1     .07       0  6037.5     .05       0
    6114     .07       0  6179.6     .12       0  6208.9     .07       0
Bank Sta=5018.8,5028.4
XS Rating Curve= 0 ,0
Exp/Cntr=0.3,0.1

Type RM Length L Ch R = 1 ,7250    ,438,438,438
BEGIN DESCRIPTION:
TRIB 7 TO SPRING CREEK 14.0
END DESCRIPTION:
XS GIS Cut Line= 3
      2587775.02     13525425.01        2586675.       13525125.
        2585575.       13525725.
#Sta/Elev= 30
  3859.8  148.16    3922  146.79  4004.9  143.37  4046.4  142.99  4184.6  138.24
    4233  134.84  4298.6  133.09  4305.5  132.17    4347  131.83  4447.2  128.54
  4543.5   127.2  4656.9  127.26  4768.5  127.47  4823.8  127.12  4875.6  129.39
  4903.3  128.12  4908.4  128.86  4937.8  126.97  5003.3  126.73  5003.8  126.23
  5012.9  126.73  5118.2  127.05  5245.4  127.17  5432.3  126.98  5580.9  128.43
  5683.9  130.44  5804.9  134.22  5963.2  137.58  6217.4  144.34    6253  144.54
#Mann= 11 ,-1 , 0
  3859.8     .05       0  4543.5      .1       0  4656.9     .12       0
  4768.5      .1       0  5003.3     .05       0  5012.9      .1       0
  5118.2     .12       0  5245.4     .07       0  5432.3     .05       0
  5804.9     .07       0  5963.2     .05       0
Bank Sta=5003.3,5012.9
XS Rating Curve= 0 ,0
Exp/Cntr=0.3,0.1

Type RM Length L Ch R = 1 ,6812    ,898,898,898
BEGIN DESCRIPTION:
TRIB 7 TO SPRING CREEK 13.0
END DESCRIPTION:
XS GIS Cut Line= 3
      2588074.95     13525124.99        2586525.       13524775.
      2585525.03     13525674.97
#Sta/Elev= 30
    3411  148.34  3472.5  147.13  3478.3  145.57  3483.4  145.27  3503.2  145.72
  3526.6  144.28  3554.5  144.94    3575   143.8  3704.6  141.09  3839.3  136.98
  3974.1  134.66  4022.4  132.48  4070.7  131.92  4113.9  129.99  4119.1  130.46
  4162.3  129.23  4340.2  127.21  4708.2   126.2  4838.6  125.73  4975.8  125.21
  4976.3  124.71    4986  125.21  5258.2  126.47  5283.1  126.49  5551.9  127.05
  5778.8  131.37  5780.1  131.41  6277.6  143.57  6281.4  143.79  6345.3  144.91
#Mann= 11 ,-1 , 0
    3411     .05       0  4708.2      .1       0  4838.6     .12       0
  4975.8     .05       0    4986     .12       0  5258.2      .1       0
  5283.1     .05       0  5778.8    .035       0  5780.1     .05       0
  6277.6    .035       0  6281.4     .05       0
Bank Sta=4975.8,4986
XS Rating Curve= 0 ,0
Exp/Cntr=0.3,0.1

Type RM Length L Ch R = 1 ,5914    ,888,888,888
BEGIN DESCRIPTION:
TRIB 7 TO SPRING CREEK 12.0
END DESCRIPTION:
XS GIS Cut Line= 3
      2588175.02     13524825.01        2586175.       13524025.
      2585274.99     13524925.01
#Sta/Elev= 30
  2854.6  145.29  2940.8  143.51  2947.5  142.45  2952.9   143.1  2962.3  142.31
  2971.8  142.63  3051.8  140.85  3138.7  139.35  3168.3  138.06    3307  134.23
  3393.1  133.14    3486  130.77  3737.8  127.17    3863   126.1  4693.4  123.46
  4727.5  123.46  4979.8  123.37  5000.7  123.23  5001.2  122.73  5010.8  122.73
  5011.3  123.23  5219.6  123.39  5404.7  127.57  5447.1   129.4  5673.4  133.03
  5970.8     136  5998.6  136.87  6125.9  137.25  6257.4  139.63  6281.5  140.15
#Mann= 10 ,-1 , 0
  2854.6    .035       0  3051.8     .05       0  4693.4     .07       0
  4727.5      .1       0  4979.8     .12       0  5000.7     .05       0
  5011.3     .12       0  5219.6     .05       0  5970.8    .035       0
  6257.4     .05       0
Bank Sta=5000.7,5011.3
XS Rating Curve= 0 ,0
Exp/Cntr=0.3,0.1

Type RM Length L Ch R = 1 ,5026    ,460,460,460
BEGIN DESCRIPTION:
TRIB 7 TO SPRING CREEK 11.0
END DESCRIPTION:
XS GIS Cut Line= 3
        2587625.       13522625.        2585625.       13523625.
        2585225.       13524875.
#Sta/Elev= 30
  2767.8  138.86    2888  136.62  3125.6  129.08  3295.1   125.4  3333.2  125.09
  3845.5  122.44    3957  123.57  4085.4  123.07    4180   123.1  4204.6  123.12
  4291.4  123.25  4405.1  122.79  4413.5  122.86  4475.6  123.69  4481.2  124.65
  4514.4  123.57  4615.3  122.91  4640.7  120.39  4641.2  119.89  4651.5  120.39
  4654.5  122.15  4668.5   122.5  5309.5  123.68    5324  123.82  5591.8  126.64
  5654.8  128.31  5909.1  131.24  5993.7  133.22  6037.7  133.01  6316.3  138.64
#Mann= 17 ,-1 , 0
  2767.8     .05       0  3295.1    .035       0  3333.2     .05       0
  3845.5     .07       0    3957    .035       0  4085.4      .1       0
    4180     .07       0  4204.6      .1       0  4291.4     .12       0
  4405.1     .05       0  4413.5     .12       0  4514.4     .05       0
  4640.7     .05       0  4651.5     .05       0  5309.5     .07       0
    5324     .05       0  5993.7    .035       0
Bank Sta=4640.7,4651.5
XS Rating Curve= 0 ,0
Exp/Cntr=0.3,0.1

Type RM Length L Ch R = 1 ,4566    ,471,471,471
BEGIN DESCRIPTION:
TRIB 7 TO SPRING CREEK 10.0
END DESCRIPTION:
XS GIS Cut Line= 3
      2587524.97     13522425.01        2585525.       13523225.
      2584074.96     13523875.02
#Sta/Elev= 30
  2839.1   141.7  2951.8  139.05  3181.3  131.08    3422  124.17  4050.5   122.3
  4080.7  122.31  4176.8  122.28  4294.8  122.31  4469.4  122.04  4523.3  118.63
  4571.7   119.1  4594.6  121.75  4616.2  121.85  4637.7  121.24  4648.5  119.71
  4649.5  118.19    4650  117.69  4660.9  118.19  4702.3  121.32  4723.9  119.84
  4777.7   121.7  5156.1  121.55  5331.1  121.91  5519.1  122.66  5553.7  122.59
  5771.2  124.45  5847.9  127.12  6232.3  133.77  6446.4  139.54  6582.2  140.86
#Mann= 13 ,-1 , 0
  2839.1     .05       0  2951.8    .035       0  3181.3     .05       0
  4050.5     .07       0  4080.7    .035       0  4176.8     .07       0
  4294.8     .05       0  4649.5     .05       0  4660.9     .05       0
  5156.1      .1       0  5331.1     .05       0  5519.1      .1       0
  5553.7     .05       0
Bank Sta=4649.5,4660.9
XS Rating Curve= 0 ,0
Exp/Cntr=0.3,0.1

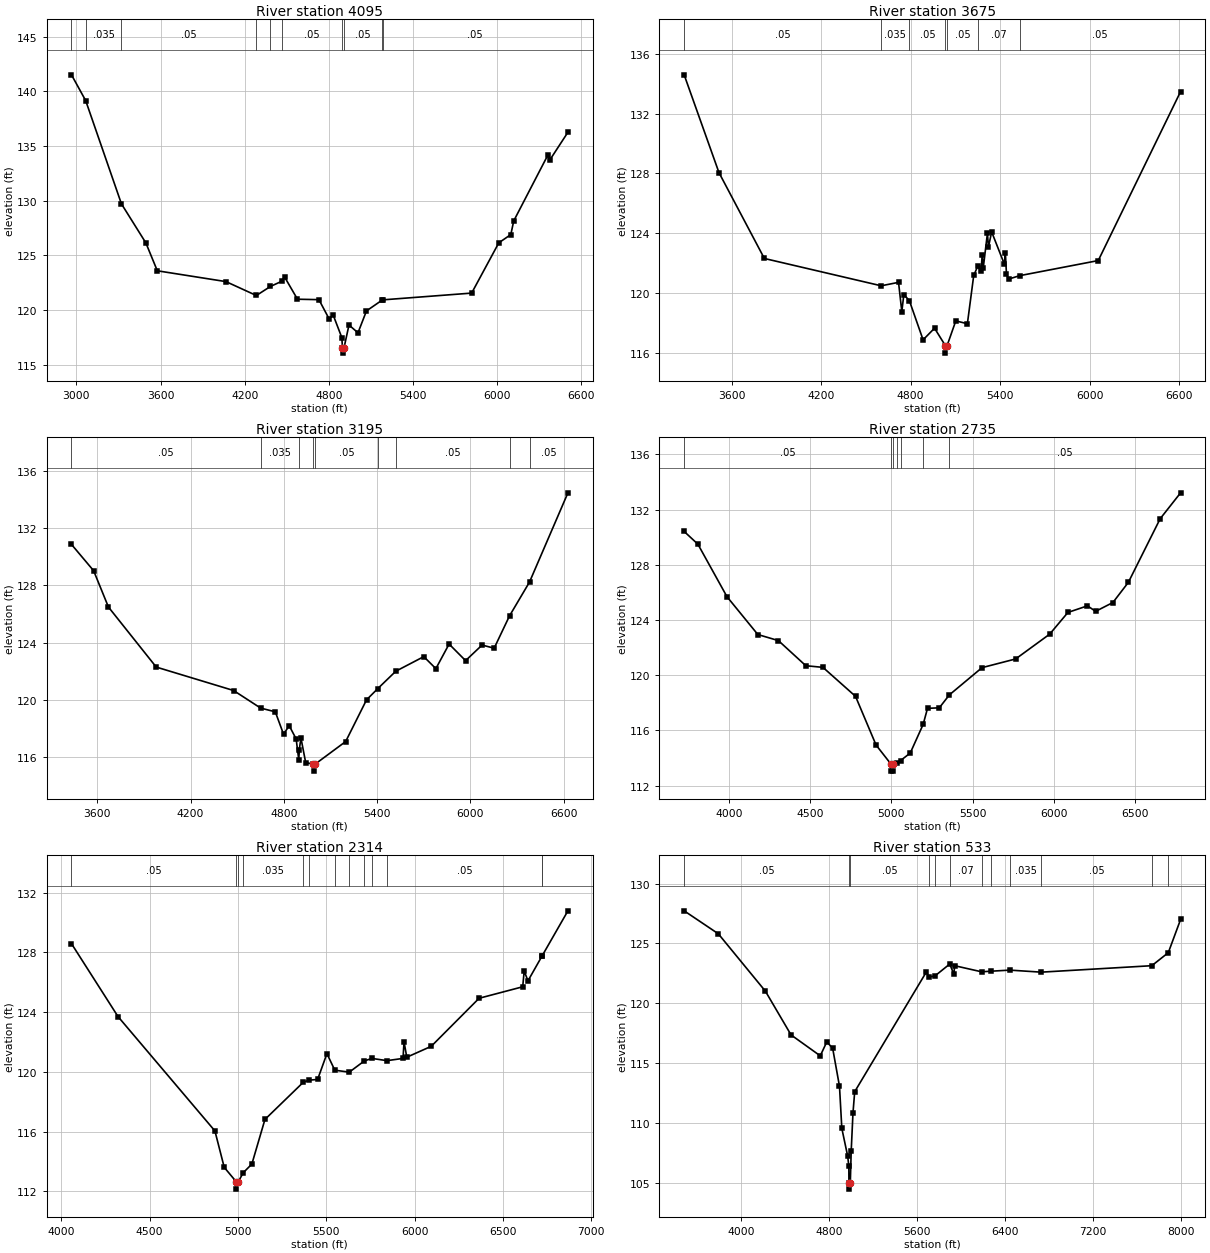
Type RM Length L Ch R = 1 ,4095    ,420,420,420
BEGIN DESCRIPTION:
TRIB 7 TO SPRING CREEK 9.0
END DESCRIPTION:
XS GIS Cut Line= 3
      2587475.03     13522374.99        2585475.       13522775.
      2584275.03     13523674.97
#Sta/Elev= 30
  2965.2  141.52  3066.5  139.16  3321.3  129.72  3495.5  126.15  3577.1   123.6
  4066.6  122.61  4283.3  121.34  4384.1  122.17  4464.1  122.64  4484.7  123.03
  4576.5     121  4729.5  120.96  4800.9  119.23  4831.5  119.54  4892.7  117.49
  4897.2  116.57  4897.7  116.07  4908.6  116.57  4943.7  118.64    5008  117.93
  5068.4  119.93  5180.3  120.92  5183.4  120.94  5818.4  121.56  6012.1  126.16
  6097.6  126.91  6118.4  128.16  6362.1  134.19  6376.7  133.75  6504.8  136.27
#Mann= 10 ,-1 , 0
  2965.2     .05       0  3066.5    .035       0  3321.3     .05       0
  4283.3     .07       0  4384.1    .035       0  4464.1     .05       0
  4897.2     .05       0  4908.6     .05       0  5180.3     .07       0
  5183.4     .05       0
Bank Sta=4897.2,4908.6
XS Rating Curve= 0 ,0
Exp/Cntr=0.3,0.1

Type RM Length L Ch R = 1 ,3675    ,480,480,480
BEGIN DESCRIPTION:
TRIB 7 TO SPRING CREEK 8.0
END DESCRIPTION:
XS GIS Cut Line= 3
      2587075.02     13521724.99        2585525.       13522425.
      2584325.03     13523524.97
#Sta/Elev= 30
  3281.7   134.6  3515.1  128.05  3819.4   122.3  4602.8  120.47  4719.1   120.7
  4741.1  118.74  4754.6  119.88  4791.6  119.48  4883.7  116.85  4960.5  117.63
  5033.2  116.46  5033.7  115.96  5044.6  116.46    5103  118.12  5180.7  117.93
  5223.2  121.16  5249.6  121.77  5272.6  121.45    5280  122.55  5286.8  121.64
  5315.1  123.98  5321.9  123.07  5343.5  124.08  5428.6  121.92  5435.4  122.67
  5442.8  121.25  5456.9  120.92  5532.2  121.15  6058.2  122.16  6610.3  133.48
#Mann= 7 ,-1 , 0
  3281.7     .05       0  4602.8    .035       0  4791.6     .05       0
  5033.2     .05       0  5044.6     .05       0  5249.6     .07       0
  5532.2     .05       0
Bank Sta=5033.2,5044.6
XS Rating Curve= 0 ,0
Exp/Cntr=0.3,0.1

Type RM Length L Ch R = 1 ,3195    ,460,460,460
BEGIN DESCRIPTION:
TRIB 7 TO SPRING CREEK 7.0
END DESCRIPTION:
XS GIS Cut Line= 3
      2586724.99       13521325.        2585325.       13522025.
      2584125.02     13523124.98
#Sta/Elev= 30
  3434.1  130.87  3576.6  129.03  3671.7  126.49  3979.1  122.29  4476.7  120.65
  4650.8  119.42    4745  119.16  4798.1  117.59  4834.4  118.19  4879.2  117.26
  4895.9  115.81  4899.7  116.52  4909.9  117.33  4940.6   115.6  4990.5  115.51
    4991  115.01  5002.6  115.51  5197.6  117.08    5332     120  5404.8  120.79
  5520.2     122  5700.1  123.02  5777.8  122.18  5862.9   123.9    5969  122.74
    6075  123.83  6152.7  123.61  6251.5  125.87  6380.2  128.24  6627.2  134.48
#Mann= 9 ,-1 , 0
  3434.1     .05       0  4650.8    .035       0  4899.7     .05       0
  4990.5     .05       0  5002.6     .05       0  5404.8     .07       0
  5520.2     .05       0  6251.5     .12       0  6380.2     .05       0
Bank Sta=4990.5,5002.6
XS Rating Curve= 0 ,0
Exp/Cntr=0.3,0.1

Type RM Length L Ch R = 1 ,2735    ,421,421,421
BEGIN DESCRIPTION:
TRIB 7 TO SPRING CREEK 6.0
END DESCRIPTION:
XS GIS Cut Line= 3
      2586624.96     13521225.01        2585425.       13521625.
      2583825.02     13522424.99
#Sta/Elev= 30
  3725.8  130.42  3810.1   129.5  3989.3  125.69    4179  122.95  4305.5  122.51
  4474.2  120.69  4579.6  120.57  4779.9  118.47  4906.3  114.94  4998.6  113.55
  4999.1  113.05  5010.2  113.05  5010.7  113.55  5035.2  113.66  5057.4  113.82
  5116.5  114.36    5196  116.44  5222.7   117.6  5295.3  117.64  5357.5  118.58
  5558.1  120.55  5764.9  121.18  5974.5  122.98  6086.3  124.55  6206.5  125.03
  6256.8  124.63  6363.1  125.27  6458.1  126.73  6653.7  131.34  6779.5  133.22
#Mann= 7 ,-1 , 0
  3725.8     .05       0  4998.6     .05       0  5010.7     .05       0
  5035.2    .035       0  5057.4     .05       0    5196    .035       0
  5357.5     .05       0
Bank Sta=4998.6,5010.7
XS Rating Curve= 0 ,0
Exp/Cntr=0.3,0.1

Type RM Length L Ch R = 1 ,2314    ,1781,1781,1781
BEGIN DESCRIPTION:
TRIB 7 TO SPRING CREEK 5.0
END DESCRIPTION:
XS GIS Cut Line= 3
      2586375.02     13520974.99        2585475.       13521275.
      2583874.99     13522225.01
#Sta/Elev= 30
  4057.6  128.59  4321.1   123.7  4869.3  116.04    4922   113.6  4989.6  112.64
  4990.1  112.14  5001.9  112.64  5029.6  113.24  5078.4  113.82  5152.4  116.81
  5369.4   119.3  5400.1  119.44  5450.5  119.49  5503.2  121.22  5547.8  120.11
  5629.9  119.98  5714.8  120.73  5757.4   120.9  5843.2  120.75  5933.8   120.9
  5939.6  122.01  5955.2  120.98  6093.5  121.71  6364.4  124.93  6611.2   125.7
  6619.6  126.75  6641.1   126.1  6720.5  127.76    6721  127.77  6867.1  130.79
#Mann= 13 ,-1 , 0
  4057.6     .05       0  4989.6     .05       0  5001.9     .05       0
  5029.6    .035       0  5369.4     .05       0  5400.1    .035       0
  5547.8     .05       0  5629.9     .07       0  5714.8     .05       0
  5757.4     .07       0  5843.2     .05       0  6720.5     .07       0
    6721     .05       0
Bank Sta=4989.6,5001.9
XS Rating Curve= 0 ,0
Exp/Cntr=0.3,0.1

Type RM Length L Ch R = 1 ,533     ,0,0,0
BEGIN DESCRIPTION:
TRIB 7 TO SPRING CREEK 1.0
END DESCRIPTION:
XS GIS Cut Line= 4
      2586487.69     13520806.76      2585836.67       13519625.
      2585530.54     13519737.36      2583830.41     13522020.59
#Sta/Elev= 30
  3478.2  127.73  3789.2  125.81  4218.1  121.01  4451.9  117.35  4717.9   115.6
  4777.6  116.77    4831  116.23  4893.1  113.05  4914.4  109.53  4967.7  107.21
  4978.3  106.36  4979.1  104.95  4979.6  104.45  4991.6  104.95  4999.6   107.6
  5015.8   110.8  5031.6   112.6  5685.3  122.63  5705.2   122.2  5760.8  122.27
  5897.5  123.28  5935.6  122.41  5941.8  123.14  6186.9  122.63  6273.8  122.68
  6444.8  122.77  6730.5   122.6  7737.9  123.14  7888.2  124.23  8000.2  127.01
#Mann= 12 ,-1 , 0
  3478.2     .05       0  4979.1     .05       0  4991.6     .05       0
  5705.2    .035       0  5760.8     .05       0  5897.5     .07       0
  6186.9     .12       0  6273.8     .07       0  6444.8    .035       0
  6730.5     .05       0  7737.9     .07       0  7888.2     .05       0
Bank Sta=4979.1,4991.6
XS Rating Curve= 0 ,0
Exp/Cntr=0.3,0.1

Chan Stop Cuts=-1
Use User Specified Reach Order=0
Composite Channel Slope=5