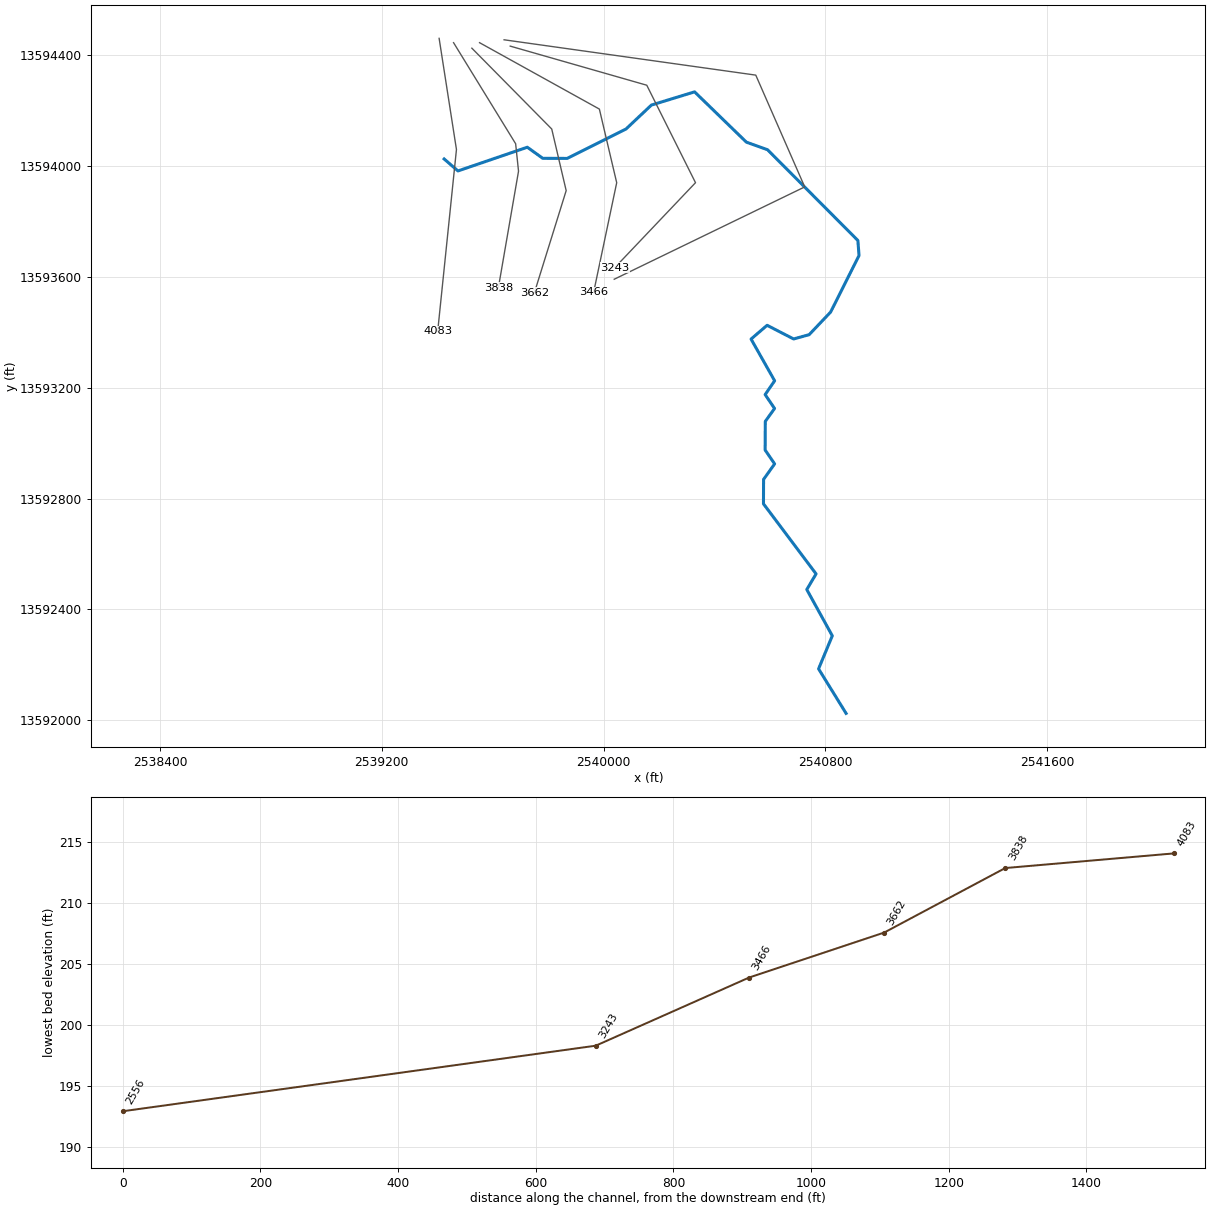
--- TRIB 7_1 TO IRISH CREEK.prj (project) ---

Proj Title=TRIB 7_1 TO IRISH CREEK Base Level Engineering
Current Plan=p01
Default Exp/Contr=0.3,0.1
English Units
Geom File=g01
Flow File=f01
Plan File=p01
BEGIN DESCRIPTION:
TRIB 7_1 TO IRISH CREEK
END DESCRIPTION:

--- TRIB 7_1 TO IRISH CREEK.p01 (plan) ---

Plan Title=Multiple Run
Short Identifier=Multiple
Geom File=g01
Flow File=f01
Subcritical Flow
K Sum by GR= 0
Std Step Tol= 0.01
Critical Tol= 0.01
Num of Std Step Trials= 20
Max Error Tol= 0.3
Flow Tol Ratio= 0.001
Split Flow NTrial= 30
Split Flow Tol= 0.02
Split Flow Ratio= 0.02
Log Output Level= 0
Friction Slope Method= 1
Unsteady Friction Slope Method= 2
Unsteady Bridges Friction Slope Method= 1
Parabolic Critical Depth
Global Vel Dist=  1 , 1 , 1
Global Log Level= 0
CheckData=True
Encroach Param= -1, 0, 0, 0
BEGIN DESCRIPTION:
Multiple Run
END DESCRIPTION:

--- TRIB 7_1 TO IRISH CREEK.f01 (steady flow) ---

Flow Title=Multiple
Number of Profiles=7
Profile Names=10-year,25-year,50-year,1pct_min,100-year,1pct_plu,500-year
River Rch & RM= TRIB 7_1 TO IRIS,Reach-1,4083
     254     386     498     314     626    1249     975
Boundary for River Rch & Prof#=TRIB 7_1 TO IRIS,Reach-1,1
Up Type=0
Dn Type=3
Dn Slope=0.005
Boundary for River Rch & Prof#=TRIB 7_1 TO IRIS,Reach-1,2
Up Type=0
Dn Type=3
Dn Slope=0.005
Boundary for River Rch & Prof#=TRIB 7_1 TO IRIS,Reach-1,3
Up Type=0
Dn Type=3
Dn Slope=0.005
Boundary for River Rch & Prof#=TRIB 7_1 TO IRIS,Reach-1,4
Up Type=0
Dn Type=3
Dn Slope=0.005
Boundary for River Rch & Prof#=TRIB 7_1 TO IRIS,Reach-1,5
Up Type=0
Dn Type=3
Dn Slope=0.005
Boundary for River Rch & Prof#=TRIB 7_1 TO IRIS,Reach-1,6
Up Type=0
Dn Type=3
Dn Slope=0.005
Boundary for River Rch & Prof#=TRIB 7_1 TO IRIS,Reach-1,7
Up Type=0
Dn Type=3
Dn Slope=0.005

--- TRIB 7_1 TO IRISH CREEK.g01 (geometry) ---

Geom Title=Existing Conditions

River Reach=TRIB 7_1 TO IRIS,Reach-1
Reach XY= 30
      2539425.00     13594025.00      2539474.86     13593981.91
      2539725.00     13594067.44      2539780.89     13594027.36
      2539869.03     13594027.15      2540081.05     13594133.16
      2540172.58     13594219.47      2540328.42     13594267.21
      2540515.32     13594085.78      2540591.67     13594058.35
      2540917.52     13593731.06      2540921.69     13593676.74
      2540819.17     13593472.69      2540741.71     13593391.21
      2540685.70     13593375.74      2540590.06     13593425.04
      2540532.20     13593375.36      2540617.25     13593224.91
      2540583.02     13593175.00      2540617.00     13593125.00
      2540583.53     13593078.33      2540583.02     13592975.01
      2540617.21     13592925.10      2540577.35     13592869.11
      2540576.97     13592780.89      2540766.76     13592528.23
      2540733.24     13592471.77      2540825.29     13592304.82
      2540775.74     13592185.68      2540875.00     13592025.00

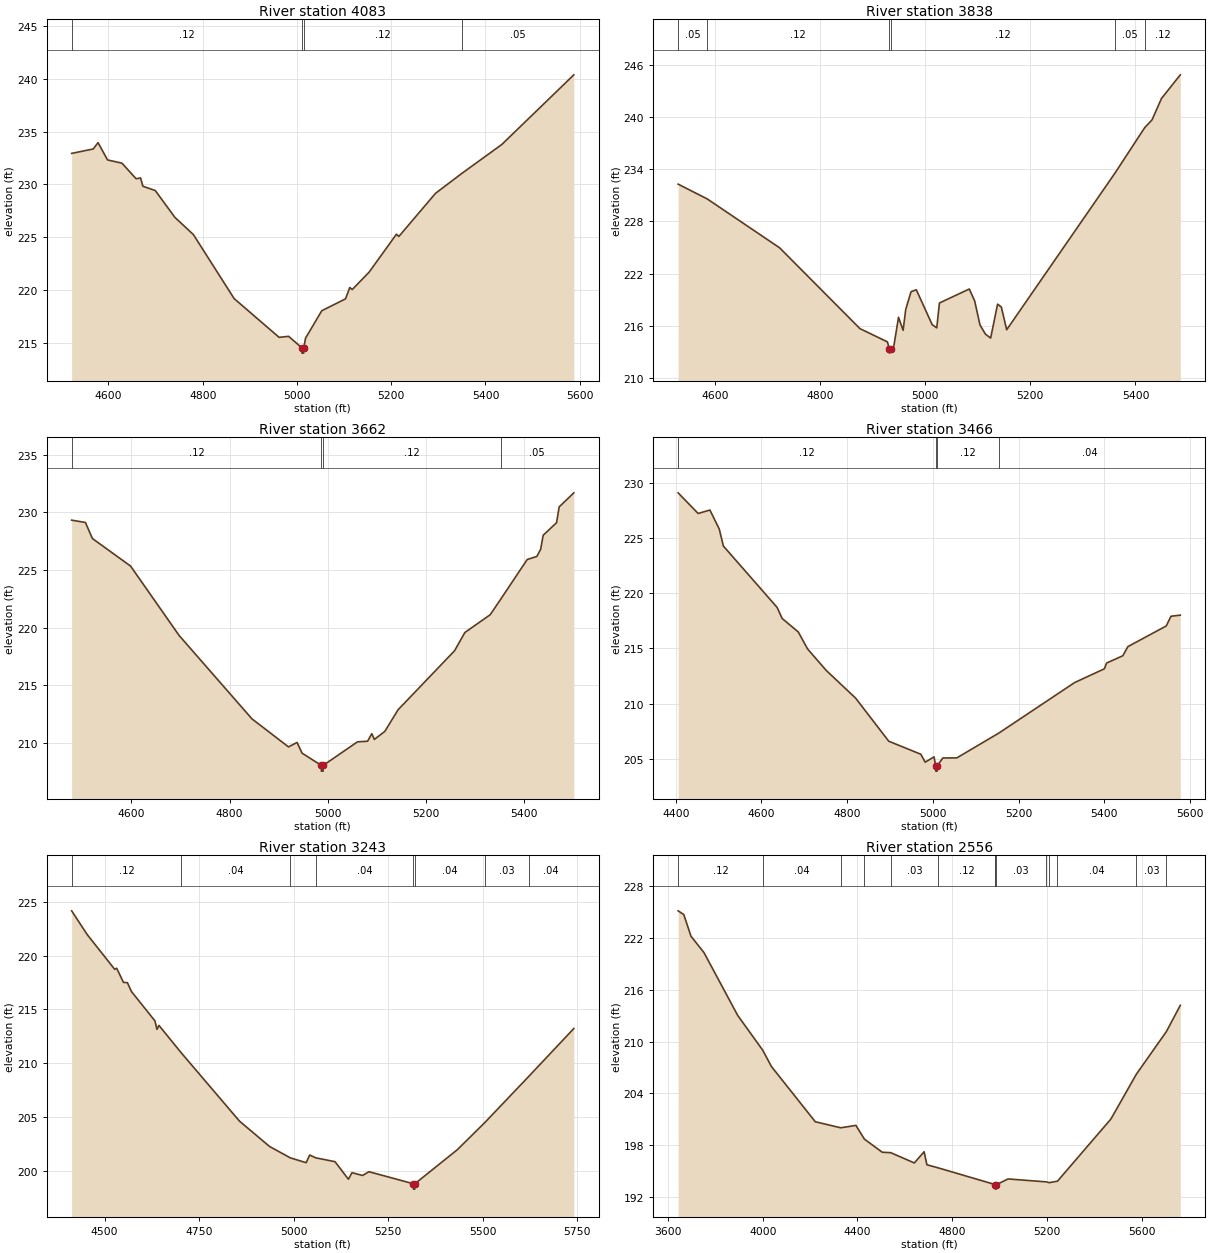
Type RM Length L Ch R = 1,4083,245,245,245
BEGIN DESCRIPTION:
LGII4079
END DESCRIPTION:
XS GIS Cut Line= 3
      2539406.85     13594460.30      2539469.36     13594059.22
      2539401.65     13593402.93
#Sta/Elev= 30
  4521.9  232.94  4567.8  233.36  4577.9  233.96  4598.1  232.32  4628.5  232.02
  4658.8  230.54  4668.1  230.62  4673.1  229.83  4699.3  229.43  4741.0  226.89
  4780.3  225.26  4866.7  219.21  4962.2  215.54  4982.3  215.64  5010.5  214.55
  5010.7  214.05  5014.2  214.05  5014.5  214.55  5018.3  215.47  5052.7  218.06
  5103.0  219.18  5112.2  220.26  5117.3  220.06  5153.2  221.71  5211.2  225.30
  5216.2  225.08  5294.0  229.16  5349.4  231.03  5434.7  233.78  5587.6  240.37
#Mann=4,-1,0
  4521.9    0.12       0  5010.5    0.05       0  5014.5    0.12       0
  5349.4    0.05       0
Bank Sta=5010.5,5014.5
Exp/Cntr=0.3,0.1

Type RM Length L Ch R = 1,3838,176,176,176
BEGIN DESCRIPTION:
LGII4078
END DESCRIPTION:
XS GIS Cut Line= 4
      2539458.96     13594444.61      2539682.90     13594080.05
      2539693.32     13593981.09      2539620.47     13593559.60
#Sta/Elev= 30
  4530.2  232.30  4585.8  230.59  4723.3  224.97  4876.0  215.67  4928.2  214.15
  4932.0  213.35  4932.3  212.85  4936.0  213.35  4940.5  213.67  4949.4  216.98
  4958.1  215.47  4963.1  217.88  4973.2  219.92  4983.2  220.14  5013.4  216.13
  5022.1  215.76  5027.2  218.62  5084.0  220.23  5094.2  218.86  5104.3  216.10
  5114.5  215.05  5124.6  214.58  5137.8  218.49  5144.9  218.16  5155.1  215.54
  5361.4  233.60  5417.7  238.81  5431.7  239.71  5449.4  242.15  5485.3  244.88
#Mann=6,-1,0
  4530.2    0.05       0  4585.8    0.12       0  4932.0    0.05       0
  4936.0    0.12       0  5361.4    0.05       0  5417.7    0.12       0
Bank Sta=4932,4936
Exp/Cntr=0.3,0.1

Type RM Length L Ch R = 1,3662,196,196,196
BEGIN DESCRIPTION:
Mapping XS 519f16f1
END DESCRIPTION:
XS GIS Cut Line= 4
      2539524.94     13594424.79      2539813.12     13594133.14
      2539865.21     13593910.91      2539750.64     13593542.90
#Sta/Elev= 30
  4478.2  229.32  4506.3  229.12  4520.5  227.73  4598.3  225.34  4697.3  219.32
  4845.8  212.09  4920.3  209.66  4937.7  210.05  4947.9  209.12  4987.0  208.06
  4987.3  207.56  4990.8  207.56  4991.0  208.06  5060.9  210.10  5081.4  210.15
  5090.1  210.81  5095.2  210.31  5116.5  211.00  5143.6  212.88  5258.8  218.00
  5279.8  219.58  5331.4  221.12  5352.7  222.46  5406.9  225.91  5426.4  226.17
  5434.2  226.79  5439.4  228.01  5466.7  229.10  5472.0  230.47  5501.9  231.69
#Mann=4,-1,0
  4478.2    0.12       0  4987.0    0.05       0  4991.0    0.12       0
  5352.7    0.05       0
Bank Sta=4987,4991
Exp/Cntr=0.3,0.1

Type RM Length L Ch R = 1,3466,223,223,223
BEGIN DESCRIPTION:
LGII4077
END DESCRIPTION:
XS GIS Cut Line= 4
      2539552.68     13594444.64      2539984.98     13594205.05
      2540047.48     13593939.42      2539964.16     13593543.64
#Sta/Elev= 30
  4405.5  229.09  4452.2  227.22  4479.7  227.53  4501.5  225.81  4511.1  224.27
  4636.5  218.71  4648.2  217.71  4685.8  216.49  4707.5  214.95  4751.1  213.00
  4819.7  210.49  4896.9  206.59  4971.7  205.41  4982.0  204.69  5002.5  205.17
  5006.3  204.38  5006.6  203.88  5010.1  203.88  5010.3  204.38  5023.1  205.07
  5055.8  205.08  5154.7  207.35  5330.4  211.90  5400.0  213.15  5405.1  213.67
  5442.9  214.33  5454.9  215.16  5544.3  217.03  5555.3  217.91  5577.1  218.01
#Mann=4,-1,0
  4405.5    0.12       0  5006.3    0.05       0  5010.3    0.12       0
  5154.7    0.04       0
Bank Sta=5006.3,5010.3
Exp/Cntr=0.3,0.1

Type RM Length L Ch R = 1,3243,687,687,687
BEGIN DESCRIPTION:
Mapping XS c1c6f3ab
END DESCRIPTION:
XS GIS Cut Line= 4
      2539663.34     13594432.19      2540156.01     13594291.12
      2540331.79     13593939.56      2540040.96     13593633.54
#Sta/Elev= 30
  4412.9  224.16  4454.1  221.95  4526.8  218.72  4532.0  218.82  4549.9  217.51
  4560.3  217.48  4571.0  216.66  4633.1  213.93  4638.5  213.14  4643.7  213.51
  4702.7  210.96  4856.7  204.61  4936.0  202.26  4990.7  201.20  5032.8  200.75
  5042.3  201.46  5058.2  201.20  5109.3  200.84  5144.6  199.21  5154.1  199.82
  5182.0  199.56  5198.8  199.91  5316.4  198.79  5316.7  198.29  5320.2  198.29
  5320.4  198.79  5432.7  201.96  5506.1  204.51  5620.9  208.75  5740.6  213.22
#Mann=8,-1,0
  4412.9    0.12       0  4702.7    0.04       0  4990.7    0.12       0
  5058.2    0.04       0  5316.4    0.05       0  5320.4    0.04       0
  5506.1    0.03       0  5620.9    0.04       0
Bank Sta=5316.4,5320.4
Exp/Cntr=0.3,0.1

Type RM Length L Ch R = 1,2556,0,0,0
BEGIN DESCRIPTION:
LGII4076
END DESCRIPTION:
XS GIS Cut Line= 4
      2539641.20     13594455.05      2540549.23     13594327.58
      2540725.78     13593924.26      2540038.54     13593591.18
#Sta/Elev= 30
  3642.8  225.14  3666.8  224.71  3697.1  222.20  3751.9  220.31  3894.5  213.03
  4000.0  209.01  4037.1  207.11  4222.2  200.72  4329.8  200.02  4393.7  200.30
  4429.5  198.71  4505.0  197.19  4540.7  197.14  4640.4  195.95  4681.8  197.25
  4693.5  195.74  4741.6  195.38  4981.3  193.45  4982.2  193.42  4982.5  192.92
  4986.0  192.92  4986.2  193.42  5036.2  194.10  5197.7  193.76  5210.0  193.67
  5245.0  193.84  5470.7  201.04  5578.2  206.23  5704.9  211.16  5763.7  214.20
#Mann=14,-1,0
  3642.8    0.12       0  4000.0    0.04       0  4329.8    0.03       0
  4429.5    0.05       0  4540.7    0.03       0  4741.6    0.12       0
  4981.3    0.03       0  4982.2    0.03       0  4986.2    0.03       0
  5197.7    0.04       0  5210.0    0.03       0  5245.0    0.04       0
  5578.2    0.03       0  5704.9    0.04       0
Bank Sta=4982.2,4986.2
Exp/Cntr=0.3,0.1

Chan Stop Cuts=-1