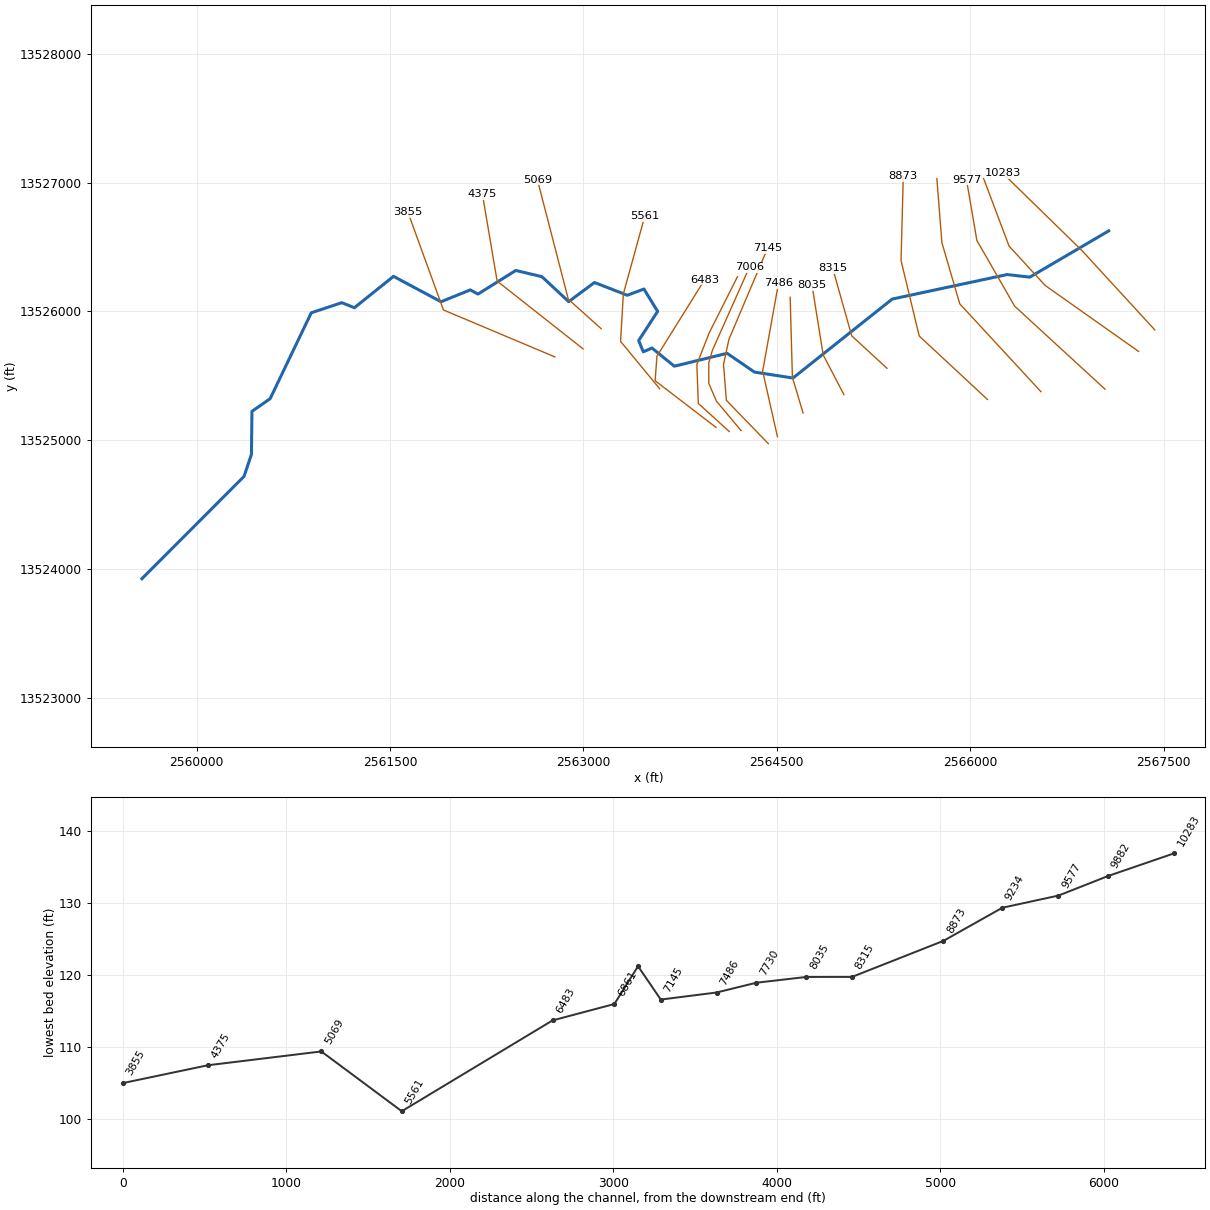
--- TRIB 8 TO GUADALUPE RIVER.prj (project) ---

Proj Title=TRIB 8 TO GUADALUPE RIVER Base Level Engineering
Current Plan=p01
Default Exp/Contr=0.3,0.1
English Units
Geom File=g01
Flow File=f01
Plan File=p01
Y Axis Title=Elevation
X Axis Title(PF)=Main Channel Distance
X Axis Title(XS)=Station
BEGIN DESCRIPTION:
TRIB 8 TO GUADALUPE RIVER
END DESCRIPTION:
DSS Export Rating Curves= 0
DSS Export Rating Curve Sorted= 0
DSS Export Volume Flow Curves= 0
DXF OffsetX= 0
DXF OffsetY= 0
DXF ScaleX= 1
DXF ScaleY= 10

--- TRIB 8 TO GUADALUPE RIVER.p01 (plan) ---

Plan Title=Multiple Run
Short Identifier=Multiple
Geom File=g01
Flow File=f01
Subcritical Flow
K Sum by GR= 0
Std Step Tol= 0.01
Critical Tol= 0.01
Num of Std Step Trials= 20
Max Error Tol= 0.3
Flow Tol Ratio= 0.001
Split Flow NTrial= 30
Split Flow Tol= 0.02
Split Flow Ratio= 0.02
Log Output Level= 0
Friction Slope Method= 1
Unsteady Friction Slope Method= 2
Unsteady Bridges Friction Slope Method= 1
Parabolic Critical Depth
Global Vel Dist=  1 , 1 , 1
Global Log Level= 0
CheckData=True
Encroach Param= -1, 0, 0, 0
BEGIN DESCRIPTION:
Multiple Run
END DESCRIPTION:

--- TRIB 8 TO GUADALUPE RIVER.f01 (steady flow) ---

Flow Title=Multiple
Number of Profiles=7
Profile Names=10-year,25-year,50-year,1pct_min,100-year,1pct_plu,500-year
River Rch & RM= TRIB 8 TO GUADAL,Reach-1,10283
     347     531     688     434     865    1726    1347
River Rch & RM= TRIB 8 TO GUADAL,Reach-1,8315
     850    1375    1852    1207    2408    4805    4025
River Rch & RM= TRIB 8 TO GUADAL,Reach-1,7486
    1330    2221    3055    2032    4054    8088    7057
Boundary for River Rch & Prof#=TRIB 8 TO GUADAL,Reach-1,1
Up Type=0
Dn Type=3
Dn Slope=0.005
Boundary for River Rch & Prof#=TRIB 8 TO GUADAL,Reach-1,2
Up Type=0
Dn Type=3
Dn Slope=0.005
Boundary for River Rch & Prof#=TRIB 8 TO GUADAL,Reach-1,3
Up Type=0
Dn Type=3
Dn Slope=0.005
Boundary for River Rch & Prof#=TRIB 8 TO GUADAL,Reach-1,4
Up Type=0
Dn Type=3
Dn Slope=0.005
Boundary for River Rch & Prof#=TRIB 8 TO GUADAL,Reach-1,5
Up Type=0
Dn Type=3
Dn Slope=0.005
Boundary for River Rch & Prof#=TRIB 8 TO GUADAL,Reach-1,6
Up Type=0
Dn Type=3
Dn Slope=0.005
Boundary for River Rch & Prof#=TRIB 8 TO GUADAL,Reach-1,7
Up Type=0
Dn Type=3
Dn Slope=0.005

--- TRIB 8 TO GUADALUPE RIVER.g01 (geometry) ---

Geom Title=Existing Conditions
Program Version=4.10

River Reach=TRIB 8 TO GUADAL,Reach-1
Reach XY= 30
        2567075.       13526625.      2566462.12      13526265.5
      2566287.27     13526285.91      2565395.46     13526095.66
      2564625.01     13525482.53      2564326.55     13525528.75
      2564114.36     13525674.35      2563704.86     13525574.32
      2563531.58     13525715.43      2563464.56     13525686.11
      2563428.31      13525773.2       2563575.5     13525999.97
      2563469.15     13526173.45      2563340.39     13526125.08
      2563085.48     13526224.07      2562885.64     13526075.55
      2562677.45     13526269.53      2562474.99     13526317.47
      2562181.66     13526134.31      2562121.78     13526166.71
      2561895.17      13526074.7      2561526.63     13526271.88
      2561223.27     13526028.37      2561125.01     13526067.41
      2560888.46     13525988.63      2560569.58     13525322.33
      2560428.45     13525223.75      2560424.48     13524890.22
      2560367.14     13524718.83        2559575.       13523925.

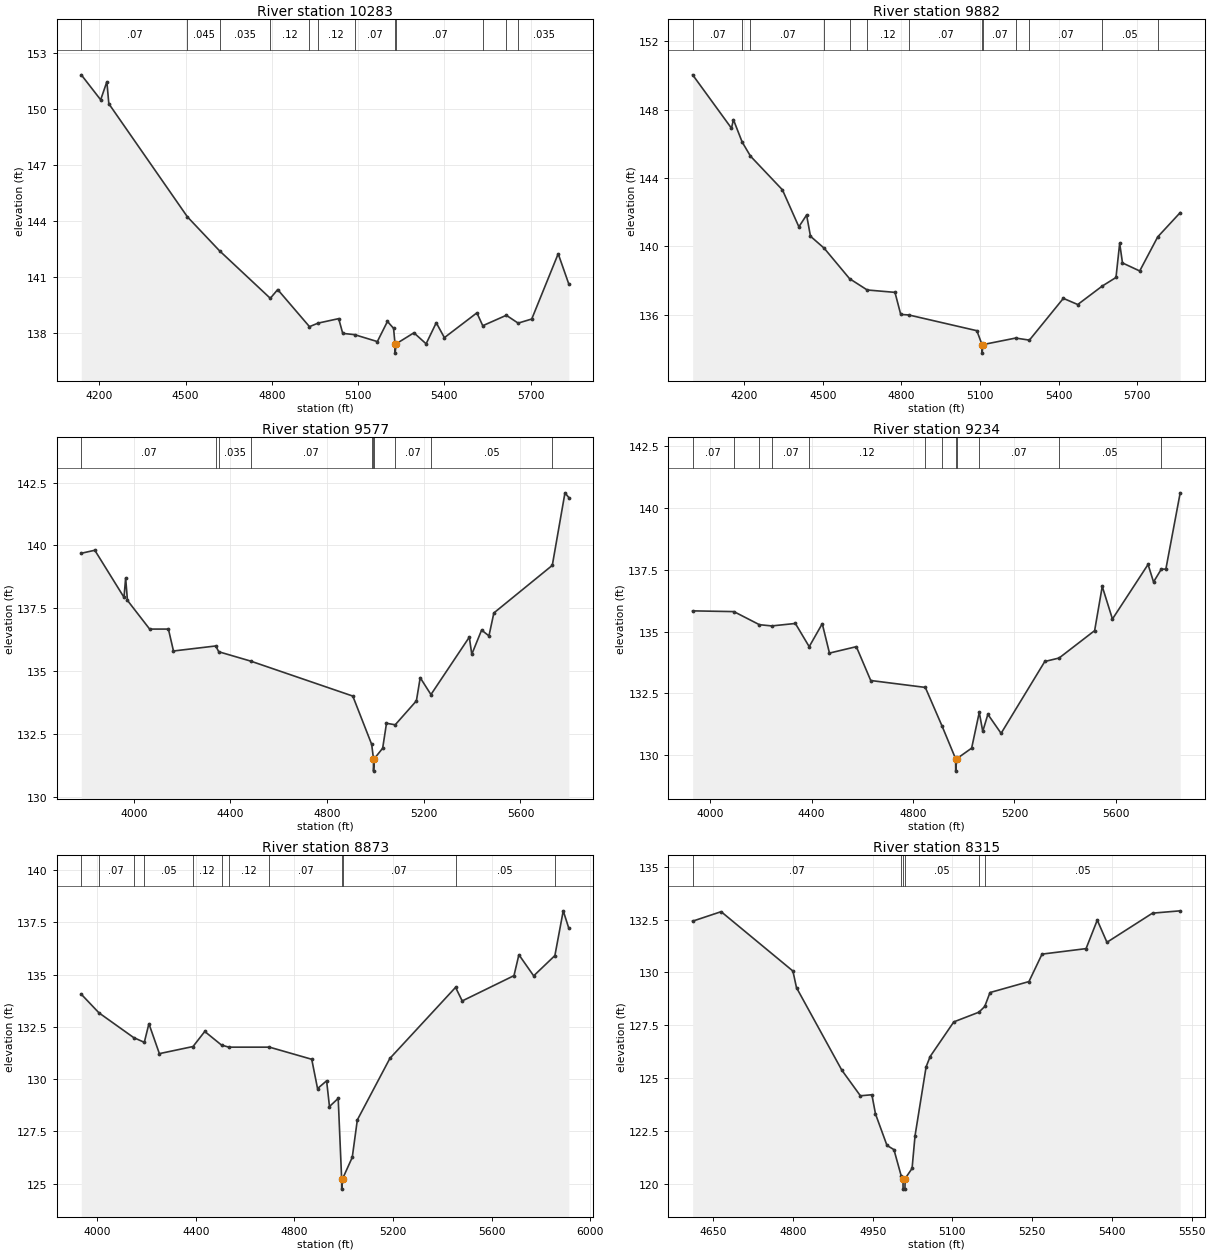
Type RM Length L Ch R = 1 ,10283   ,401,401,401
BEGIN DESCRIPTION:
Mapping XS e73baeee
END DESCRIPTION:
XS GIS Cut Line= 3
      2567431.96     13525856.38      2566869.18     13526469.74
      2566251.38     13527073.85
#Sta/Elev= 30
  4136.8  151.83  4204.2  150.49  4225.8  151.46  4232.6  150.28  4506.1  144.21
  4617.8  142.39  4794.5  139.84  4820.2  140.31  4930.8  138.32  4960.8  138.51
  5032.4  138.75  5046.5  137.96  5087.9  137.89  5166.9  137.52  5202.1   138.6
  5223.4  138.23  5228.4   137.4  5228.7   136.9  5232.4   137.4  5294.2  137.99
  5336.6   137.4  5371.9  138.53  5400.2  137.73  5513.3  139.06  5533.7  138.37
  5615.7  138.93  5656.8  138.51  5704.2  138.73  5796.2  142.23  5833.3   140.6
#Mann= 12 ,-1 , 0
  4136.8     .07       0  4506.1    .045       0  4617.8    .035       0
  4794.5     .12       0  4930.8     .07       0  4960.8     .12       0
  5087.9     .07       0  5228.4     .05       0  5232.4     .07       0
  5533.7    .035       0  5615.7     .07       0  5656.8    .035       0
Bank Sta=5228.4,5232.4
XS Rating Curve= 0 ,0
Exp/Cntr=0.3,0.1

Type RM Length L Ch R = 1 ,9882    ,305,305,305
BEGIN DESCRIPTION:
Mapping XS 2cc0ccb9
END DESCRIPTION:
XS GIS Cut Line= 4
      2567306.08     13525689.28      2566581.27     13526201.43
      2566301.32     13526507.42      2566104.33     13527031.28
#Sta/Elev= 30
  4002.4  150.03  4150.7  146.91  4158.2  147.41  4191.6   146.1  4223.3  145.28
  4345.3  143.31  4408.1  141.15  4437.6  141.84  4452.4   140.6  4504.7   139.9
  4601.7  138.12    4669  137.46  4775.1  137.32  4797.1  136.03  4827.8     136
  5087.8  135.08  5107.4  134.27  5107.7  133.77  5111.4  134.27  5235.9  134.65
  5288.5  134.53  5418.1  136.97    5473  136.61  5566.8  137.69  5619.1  138.19
  5633.2  140.19  5643.9  139.04  5709.7  138.57  5778.4  140.56  5864.3  141.98
#Mann= 13 ,-1 , 0
  4002.4     .07       0  4191.6     .05       0  4223.3     .07       0
  4504.7     .05       0  4601.7    .035       0    4669     .12       0
  4827.8     .07       0  5107.4     .05       0  5111.4     .07       0
  5235.9     .12       0  5288.5     .07       0  5566.8     .05       0
  5778.4    .035       0
Bank Sta=5107.4,5111.4
XS Rating Curve= 0 ,0
Exp/Cntr=0.3,0.1

Type RM Length L Ch R = 1 ,9577    ,343,343,343
BEGIN DESCRIPTION:
Mapping XS 08e82263
END DESCRIPTION:
XS GIS Cut Line= 4
      2567045.65     13525396.33      2566344.72     13526040.84
      2566051.76     13526550.82      2565971.61     13527020.89
#Sta/Elev= 30
  3782.9  139.69  3838.8  139.81  3959.6  137.94  3966.4  138.71  3973.8  137.82
  4065.7  136.68  4143.3  136.68  4164.3  135.81  4339.3  136.01  4351.5  135.78
  4483.2  135.41  4906.2  134.02  4984.4   132.1  4991.6  131.54  4991.9  131.04
  4995.6  131.54  5029.8  131.95  5045.6  132.94  5081.7  132.88  5169.3  133.83
  5185.1  134.75  5229.5  134.08  5388.2  136.36  5398.5  135.68  5439.1  136.64
  5469.5  136.41  5489.8  137.32  5731.6  139.21    5784  142.09  5800.1   141.9
#Mann= 10 ,-1 , 0
  3782.9     .07       0  4339.3     .05       0  4351.5    .035       0
  4483.2     .07       0  4984.4     .12       0  4991.6     .05       0
  4995.6     .12       0  5081.7     .07       0  5229.5     .05       0
  5731.6    .035       0
Bank Sta=4991.6,4995.6
XS Rating Curve= 0 ,0
Exp/Cntr=0.3,0.1

Type RM Length L Ch R = 1 ,9234    ,361,361,361
BEGIN DESCRIPTION:
Mapping XS ad3341e3
END DESCRIPTION:
XS GIS Cut Line= 4
      2566548.71     13525376.78      2565919.38      13526058.2
      2565780.49     13526533.46      2565741.53     13527031.32
#Sta/Elev= 30
  3931.4  135.84    4094  135.81  4194.6  135.28  4243.4  135.23  4336.4  135.33
  4390.9  134.39  4442.4  135.32  4470.8  134.13  4576.8  134.39  4633.5  133.02
  4848.7  132.74  4914.9  131.17  4968.2  129.85  4968.5  129.35  4972.2  129.85
  5031.3  130.28  5061.4  131.73  5075.1  130.96  5095.3  131.65  5147.4  130.88
  5319.7  133.79    5376  133.93  5516.2  135.04  5546.2  136.83  5586.4  135.51
  5726.8  137.72  5748.4  137.01  5779.1  137.53    5797  137.53  5853.5  140.62
#Mann= 12 ,-1 , 0
  3931.4     .07       0    4094     .05       0  4194.6    .035       0
  4243.4     .07       0  4390.9     .12       0  4848.7     .07       0
  4914.9     .12       0  4968.2     .05       0  4972.2     .12       0
  5061.4     .07       0    5376     .05       0  5779.1    .035       0
Bank Sta=4968.2,4972.2
XS Rating Curve= 0 ,0
Exp/Cntr=0.3,0.1

Type RM Length L Ch R = 1 ,8873    ,558,558,558
BEGIN DESCRIPTION:
Mapping XS 10a845d7
END DESCRIPTION:
XS GIS Cut Line= 4
      2566134.21     13525316.02      2565604.71     13525808.63
      2565463.65     13526394.57      2565481.01     13527047.75
#Sta/Elev= 30
  3934.6  134.06  4006.4  133.17  4146.9  131.99  4190.4  131.76  4209.1  132.65
  4251.6  131.22  4388.2  131.56  4435.8  132.28  4503.8  131.63  4533.5  131.53
  4698.6  131.53  4870.1  130.95  4893.7  129.55  4930.5  129.92  4942.1  128.69
  4977.5  129.08  4991.5  125.24  4991.8  124.74  4995.5  125.24  5034.6  126.26
  5055.2  128.05  5187.2  130.99    5454  134.39    5481  133.74  5691.1  134.95
  5711.1  135.95  5771.1  134.94  5857.2  135.91  5891.1  138.05  5913.9  137.21
#Mann= 12 ,-1 , 0
  3934.6    .035       0  4006.4     .07       0  4146.9     .12       0
  4190.4     .05       0  4388.2     .12       0  4503.8     .07       0
  4533.5     .12       0  4698.6     .07       0  4991.5     .05       0
  4995.5     .07       0    5454     .05       0  5857.2    .035       0
Bank Sta=4991.5,4995.5
XS Rating Curve= 0 ,0
Exp/Cntr=0.3,0.1

Type RM Length L Ch R = 1 ,8315    ,280,280,280
BEGIN DESCRIPTION:
Mapping XS a49b7233
END DESCRIPTION:
XS GIS Cut Line= 3
      2565354.44     13525558.26      2565080.98     13525810.02
      2564933.42     13526335.18
#Sta/Elev= 30
  4611.3  132.43  4664.9  132.88  4799.9  130.07  4806.7  129.28  4891.8  125.38
  4926.9  124.16  4948.5  124.21  4955.3   123.3  4976.9  121.81    4990  121.61
  5003.5  120.38    5007  120.24  5007.2  119.74  5010.7  119.74    5011  120.24
  5024.1  120.72  5029.7  122.27  5050.5  125.53  5058.1  126.02  5102.6  127.66
  5149.9  128.12  5160.8  128.39  5170.7  129.05    5244  129.57  5268.6  130.87
  5351.4  131.13  5372.5  132.48  5390.7  131.43  5476.4  132.81  5528.5  132.92
#Mann= 6 ,-1 , 0
  4611.3     .07       0  5003.5     .05       0    5007     .05       0
    5011     .05       0  5149.9     .07       0  5160.8     .05       0
Bank Sta=5007,5011
XS Rating Curve= 0 ,0
Exp/Cntr=0.3,0.1

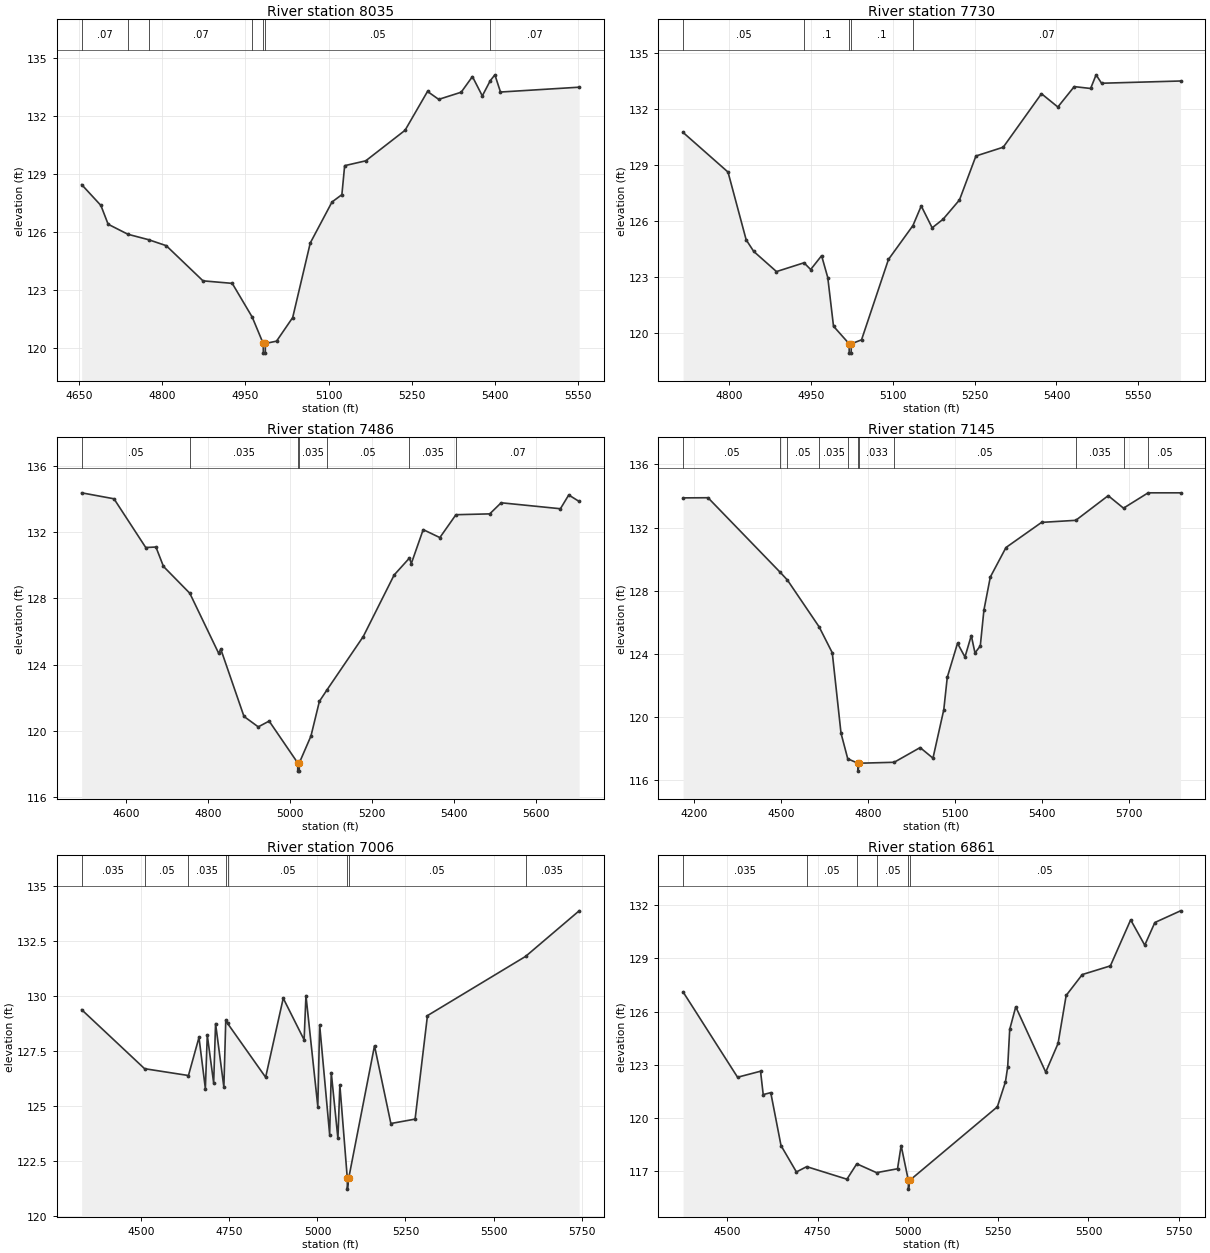
Type RM Length L Ch R = 1 ,8035    ,305,305,305
BEGIN DESCRIPTION:
Mapping XS 2519f74a
END DESCRIPTION:
XS GIS Cut Line= 3
      2565020.24     13525354.24      2564859.63     13525662.45
      2564772.82       13526205.
#Sta/Elev= 30
  4654.7  128.45  4689.4  127.37  4702.4   126.4  4738.1  125.88  4775.3   125.6
  4807.2  125.29  4873.5  123.47  4926.2  123.34  4962.3  121.59    4982  120.23
  4982.3  119.73  4985.8  119.73    4986  120.23  5006.1  120.35  5035.2  121.57
  5066.9  125.43  5106.1  127.55  5123.9  127.93  5128.9  129.43  5166.9  129.68
  5237.8  131.26  5278.3  133.27  5298.5  132.86    5339  133.23  5359.3  134.04
  5377.1  133.04  5391.5  133.83  5399.8  134.13  5409.9  133.24  5551.7  133.49
#Mann= 7 ,-1 , 0
  4654.7     .07       0  4738.1     .05       0  4775.3     .07       0
  4962.3     .05       0    4982     .05       0    4986     .05       0
  5391.5     .07       0
Bank Sta=4982,4986
XS Rating Curve= 0 ,0
Exp/Cntr=0.3,0.1

Type RM Length L Ch R = 1 ,7730    ,244,244,244
BEGIN DESCRIPTION:
Mapping XS df313b09
END DESCRIPTION:
XS GIS Cut Line= 3
      2564703.39     13525211.03      2564620.91     13525488.83
      2564603.55      13526109.5
#Sta/Elev= 30
  4716.4  130.73  4798.7  128.61  4831.9  124.99  4845.7  124.37  4887.4  123.29
  4937.8  123.76    4950   123.4    4970  124.14  4981.3  122.97  4991.8  120.37
  5020.4  119.43  5020.6  118.93  5024.1  118.93  5024.4  119.43  5043.1  119.64
  5092.4  123.94  5137.2  125.75  5152.4   126.8  5172.4  125.63  5192.4  126.09
  5222.4  127.12  5252.5  129.47  5302.5  129.94  5372.5   132.8  5402.5  132.09
  5432.5  133.18  5462.5  133.08  5472.5  133.81  5482.5  133.36  5627.1  133.48
#Mann= 5 ,-1 , 0
  4716.4     .05       0  4937.8      .1       0  5020.4     .05       0
  5024.4      .1       0  5137.2     .07       0
Bank Sta=5020.4,5024.4
XS Rating Curve= 0 ,0
Exp/Cntr=0.3,0.1

Type RM Length L Ch R = 1 ,7486    ,341,341,341
BEGIN DESCRIPTION:
Mapping XS 9426bb0d
END DESCRIPTION:
XS GIS Cut Line= 3
      2564504.57     13525027.96      2564390.19     13525536.07
      2564513.35     13526220.04
#Sta/Elev= 30
  4490.8  134.36  4569.8     134  4647.4  131.06  4672.3  131.09  4690.7  129.92
  4755.1   128.3  4825.6  124.68  4830.8  124.93  4887.5  120.87  4922.4  120.24
    4949  120.59  5018.7  118.07    5019  117.57  5022.5  117.57  5022.8  118.07
  5051.2  119.69  5071.8  121.78  5090.6  122.48    5179  125.69  5254.4   129.4
    5292  130.43  5296.4  130.09  5325.5  132.14  5366.2  131.66  5405.5  133.04
  5488.1  133.09    5516  133.76  5660.8   133.4  5681.2  134.23  5706.6  133.84
#Mann= 7 ,-1 , 0
  4490.8     .05       0  4755.1    .035       0  5018.7    .035       0
  5022.8    .035       0  5090.6     .05       0    5292    .035       0
  5405.5     .07       0
Bank Sta=5018.7,5022.8
XS Rating Curve= 0 ,0
Exp/Cntr=0.3,0.1

Type RM Length L Ch R = 1 ,7145    ,139,139,139
BEGIN DESCRIPTION:
Mapping XS bf5e3e25
END DESCRIPTION:
XS GIS Cut Line= 5
      2564434.19     13524972.94      2564108.63      13525309.5
      2564086.63     13525588.86      2564128.43     13525782.43
       2564427.6     13526488.56
#Sta/Elev= 30
  4163.1  133.88    4249  133.89  4498.2  129.16  4522.5  128.68  4631.7  125.72
    4677  124.08  4707.1  118.99  4730.3  117.37  4765.2  117.09  4765.5  116.59
  4769.3  117.09  4890.2  117.15  4979.6  118.08  5023.8  117.41  5061.1  120.48
  5073.1  122.53  5108.4  124.68    5134  123.81  5155.8  125.17  5168.5  124.07
  5186.8  124.51  5199.3  126.78  5221.3  128.87  5275.3  130.74  5397.9  132.33
  5515.7  132.46  5627.3  134.02  5680.1  133.23  5764.8   134.2  5876.5   134.2
#Mann= 11 ,-1 , 0
  4163.1     .05       0  4498.2    .035       0  4522.5     .05       0
  4631.7    .035       0  4730.3    .033       0  4765.2     .05       0
  4769.3    .033       0  4890.2     .05       0  5515.7    .035       0
  5680.1     .07       0  5764.8     .05       0
Bank Sta=4765.2,4769.3
XS Rating Curve= 0 ,0
Exp/Cntr=0.3,0.1

Type RM Length L Ch R = 1 ,7006    ,145,145,145
BEGIN DESCRIPTION:
Mapping XS 3b9f076b
END DESCRIPTION:
XS GIS Cut Line= 6
        2564223.     13525074.15      2564031.64      13525302.9
      2563972.25     13525441.48      2563972.25     13525599.86
      2564000.85     13525698.85      2564286.56     13526340.59
#Sta/Elev= 30
  4330.3  129.37    4509  126.69  4633.6  126.38  4663.5  128.11  4681.6  125.79
  4687.1  128.21  4705.2  126.04  4710.6  128.74  4734.2  125.85  4739.6  128.91
  4744.6  128.75  4852.8   126.3  4902.8  129.89  4962.1     128  4967.3  130.01
    5001  124.97  5006.2  128.68  5034.6   123.7  5039.2  126.51  5058.1  123.52
  5063.6  125.95  5084.7  121.72    5085  121.22  5088.8  121.72    5162  127.73
  5208.5   124.2  5277.3   124.4  5312.4   129.1  5591.1  131.79  5743.2  133.86
#Mann= 8 ,-1 , 0
  4330.3    .035       0    4509     .05       0  4633.6    .035       0
  4739.6    .033       0  4744.6     .05       0  5084.7     .05       0
  5088.8     .05       0  5591.1    .035       0
Bank Sta=5084.7,5088.8
XS Rating Curve= 0 ,0
Exp/Cntr=0.3,0.1

Type RM Length L Ch R = 1 ,6861    ,378,378,378
BEGIN DESCRIPTION:
Mapping XS e6003950
END DESCRIPTION:
XS GIS Cut Line= 5
      2564130.64     13525067.53      2563890.86      13525285.3
      2563879.86     13525588.86      2563974.45     13525830.83
      2564194.44      13526268.6
#Sta/Elev= 30
  4377.5  127.11  4528.4  122.29    4592  122.63  4599.4  121.31  4620.3  121.42
  4648.7  118.43  4691.3  116.94  4719.8  117.24  4831.2  116.53  4858.5   117.4
  4913.2   116.9  4971.3  117.12  4981.3  118.43  5001.2  116.47  5001.5  115.97
  5005.3  116.47  5247.7  120.62  5270.1  122.03  5276.3  122.87  5281.9  124.99
  5298.6  126.27  5381.6  122.58  5415.8   124.2  5438.2  126.91  5482.8  128.09
  5560.6  128.58  5616.8  131.18  5655.8  129.75  5683.8  131.03  5754.9  131.69
#Mann= 6 ,-1 , 0
  4377.5    .035       0  4719.8     .05       0  4858.5    .035       0
  4913.2     .05       0  5001.2     .05       0  5005.3     .05       0
Bank Sta=5001.2,5005.3
XS Rating Curve= 0 ,0
Exp/Cntr=0.3,0.1

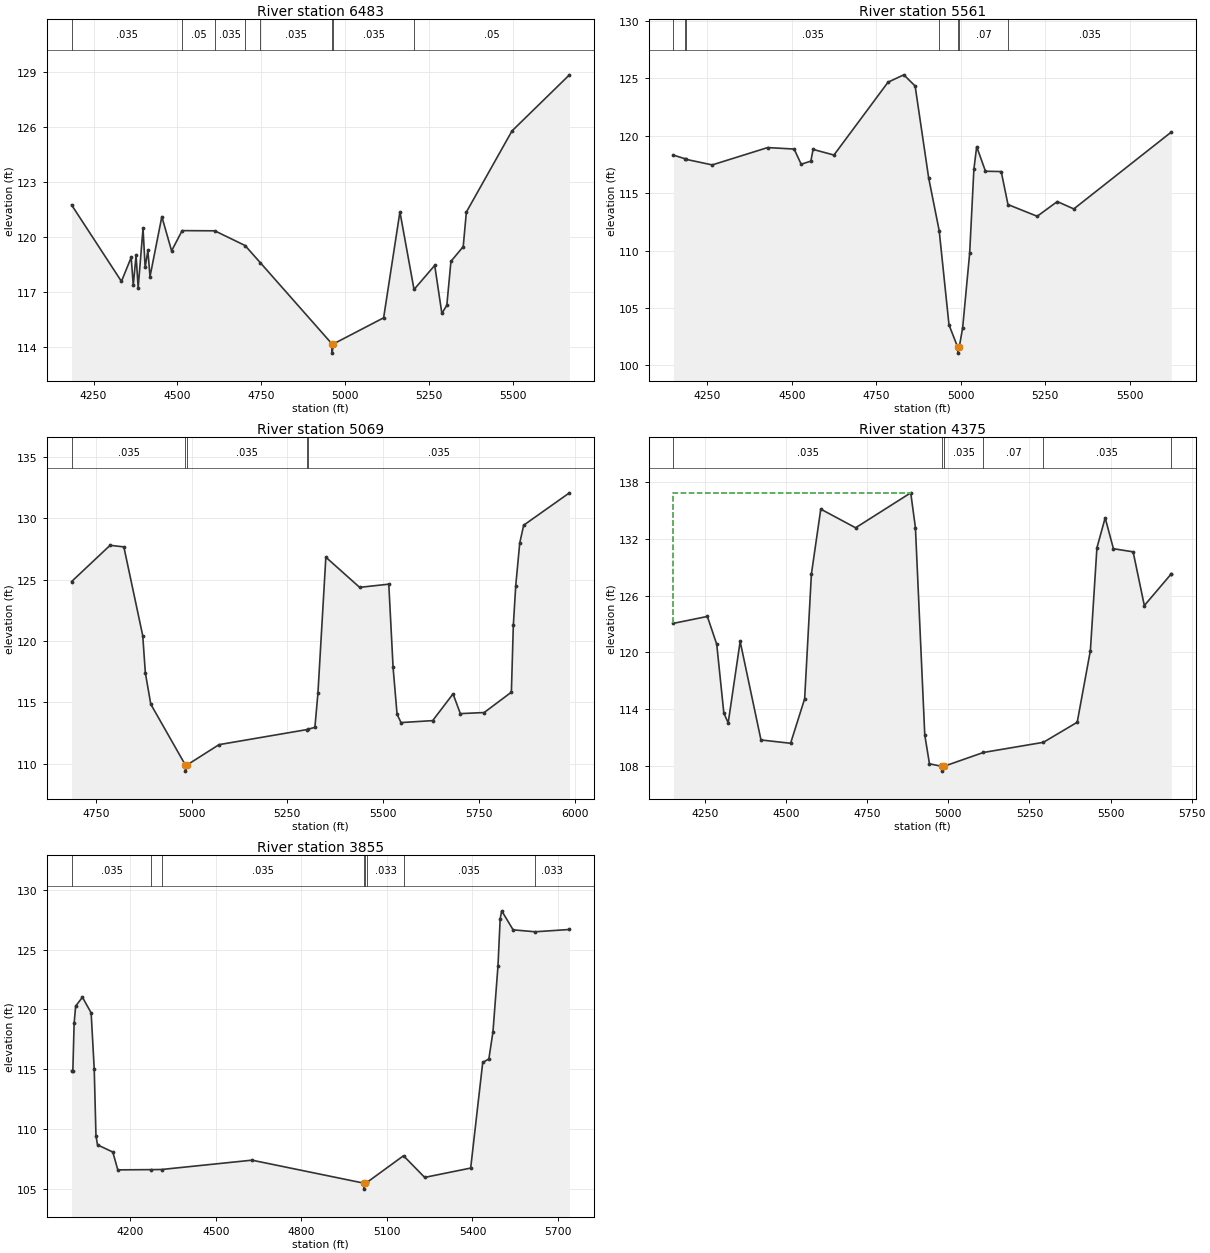
Type RM Length L Ch R = 1 ,6483    ,922,922,922
BEGIN DESCRIPTION:
Mapping XS 980e0de1
END DESCRIPTION:
XS GIS Cut Line= 4
      2564028.26     13525099.63      2563556.03     13525461.41
      2563569.95      13525651.7      2563939.75     13526245.47
#Sta/Elev= 30
  4184.4  121.75  4333.2  117.59  4362.2  118.89  4368.5  117.38  4376.8  119.01
  4383.1  117.25  4397.6  120.47  4403.9  118.35  4412.1  119.27  4418.4  117.85
  4453.7  121.11  4482.8  119.25  4514.3  120.35  4611.6  120.34    4702  119.54
  4747.3  118.61  4961.3  114.19  4961.6  113.69  4965.4  114.19  5115.3  115.61
  5163.9  121.37    5206  117.15  5267.7  118.46    5289  115.85  5303.8  116.29
  5316.1  118.68  5352.7  119.48  5362.1  121.36  5498.2  125.77  5669.6  128.82
#Mann= 8 ,-1 , 0
  4184.4    .035       0  4514.3     .05       0  4611.6    .035       0
    4702     .05       0  4747.3    .035       0  4961.3    .035       0
  4965.4    .035       0    5206     .05       0
Bank Sta=4961.3,4965.4
XS Rating Curve= 0 ,0
Exp/Cntr=0.3,0.1

Type RM Length L Ch R = 1 ,5561    ,492,492,492
BEGIN DESCRIPTION:
Mapping XS fcb1c073
END DESCRIPTION:
XS GIS Cut Line= 4
      2563591.27      13525399.4      2563287.93     13525766.97
      2563309.53     13526136.07      2563476.16     13526740.11
#Sta/Elev= 30
  4149.9   118.3  4185.2  117.98  4186.5  117.94  4264.6  117.45  4428.8  118.96
    4507  118.83  4527.8  117.51  4556.5  117.78    4563   118.8  4624.8  118.31
  4784.8  124.65  4831.4  125.29  4864.9  124.32    4905  116.31  4936.1  111.73
  4965.1  103.53  4991.1  101.57  4991.4  101.07  4995.3  101.57  5005.5  103.27
  5026.2  109.75  5038.7  117.06    5047  119.04    5073   116.9  5119.6  116.87
  5139.6     114    5226  112.98  5285.5  114.26  5334.3  113.62  5622.8  120.31
#Mann= 7 ,-1 , 0
  4149.9    .035       0  4185.2     .05       0  4186.5    .035       0
  4936.1     .07       0  4991.1     .05       0  4995.3     .07       0
  5139.6    .035       0
Bank Sta=4991.1,4995.3
XS Rating Curve= 0 ,0
Exp/Cntr=0.3,0.1

Type RM Length L Ch R = 1 ,5069    ,694,694,694
BEGIN DESCRIPTION:
Mapping XS bc5d1609
END DESCRIPTION:
XS GIS Cut Line= 3
      2563137.63     13525865.26      2562882.45     13526094.41
      2562643.07     13527020.71
#Sta/Elev= 30
  4686.8  124.84  4787.4   127.8  4823.3  127.67  4872.6  120.43  4879.4   117.4
  4893.6  114.84  4983.9  109.88  4984.2  109.38  4988.1  109.88  5071.7  111.54
  5301.5  112.77  5302.8  112.79    5322  112.95  5329.9  115.72  5350.6  126.83
  5438.8  124.37  5514.9  124.63  5526.1  117.84  5536.5  114.02  5546.8  113.34
  5629.4   113.5  5682.6  115.68  5701.7  114.07  5763.9  114.16  5834.9  115.82
    5840  121.28  5846.3  124.51  5856.7  127.98    5867  129.44  5986.5  132.08
#Mann= 5 ,-1 , 0
  4686.8    .035       0  4983.9    .035       0  4988.1    .035       0
  5301.5     .07       0  5302.8    .035       0
#XS Ineff= 2 , 0
       0                  5350.6       0  126.83
Permanent Ineff=
       F       F
Bank Sta=4983.9,4988.1
XS Rating Curve= 0 ,0
Exp/Cntr=0.3,0.1

Type RM Length L Ch R = 1 ,4375    ,520,520,520
BEGIN DESCRIPTION:
Mapping XS e6cd8973
END DESCRIPTION:
XS GIS Cut Line= 3
        2562997.     13525709.02      2562330.37     13526235.03
      2562215.96     13526911.05
#Sta/Elev= 30
  4152.5  123.06  4257.1  123.79    4286  120.85  4307.9  113.59  4321.3  112.55
  4358.2  121.15  4422.4  110.75  4513.7   110.4    4557   115.1  4577.8  128.26
  4606.7  135.12  4714.1  133.15    4884  136.84  4898.5  133.16  4927.3  111.27
  4941.8  108.23  4981.3  107.96  4981.6  107.46  4985.6  107.96  5108.1  109.43
  5292.9   110.5  5397.2  112.62  5437.8  120.19    5458  131.04  5483.4   134.2
  5508.8  130.94  5569.6  130.61  5604.1  124.94  5686.8  128.27  5687.3  128.26
#Mann= 6 ,-1 , 0
  4152.5    .035       0  4981.3    .035       0  4985.6    .035       0
  5108.1     .07       0  5292.9    .035       0  5686.8    .033       0
#XS Ineff= 2 , 0
       0    4884  136.84               0
Permanent Ineff=
       F       F
Bank Sta=4981.3,4985.6
XS Rating Curve= 0 ,0
Exp/Cntr=0.3,0.1

Type RM Length L Ch R = 1 ,3855    ,0,0,0
BEGIN DESCRIPTION:
TRIB 8 TO GUADALUPE RIVER 7.0
END DESCRIPTION:
XS GIS Cut Line= 3
      2562778.29     13525646.49       2561913.7     13526011.07
      2561637.93     13526770.75
#Sta/Elev= 30
  3993.6  114.88  3998.1  114.88  4002.6  118.83    4008  120.28  4031.8  121.02
  4062.3  119.71  4073.1  115.02  4079.2  109.45  4084.6  108.68  4138.3  108.08
  4155.8  106.59  4273.9  106.61  4309.1  106.62  4626.6   107.4  5018.6  105.48
    5019  104.98  5023.8  105.48  5031.3  105.57    5158  107.77  5232.2  105.96
  5393.6  106.74  5435.9  115.57  5457.4  115.86  5471.8  118.13  5489.3   123.6
  5497.1  127.57  5502.4  128.24  5542.5  126.65  5619.8  126.49  5740.1  126.68
#Mann= 8 ,-1 , 0
  3993.6    .035       0  4273.9    .033       0  4309.1    .035       0
  5018.6    .035       0  5023.8    .035       0  5031.3    .033       0
    5158    .035       0  5619.8    .033       0
Bank Sta=5018.6,5023.8
XS Rating Curve= 0 ,0
Exp/Cntr=0.3,0.1

Chan Stop Cuts=-1
Use User Specified Reach Order=0
Composite Channel Slope=5