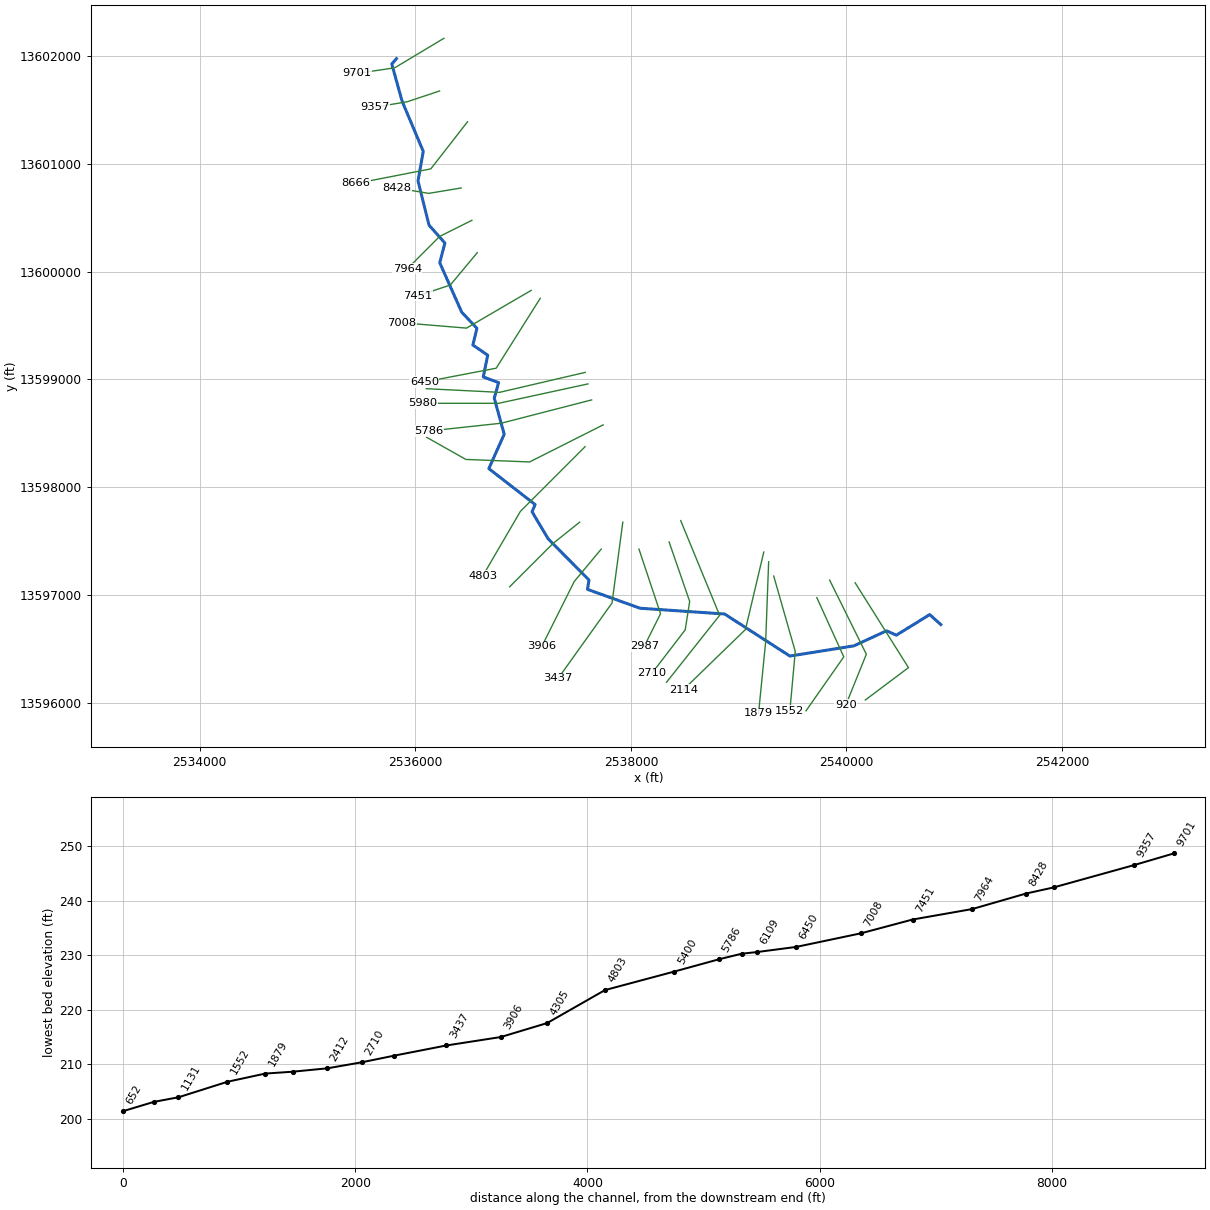
--- TRIB 8 TO IRISH CREEK.prj (project) ---

Proj Title=TRIB 8 TO IRISH CREEK Base Level Engineering
Current Plan=p01
Default Exp/Contr=0.3,0.1
English Units
Geom File=g01
Flow File=f01
Plan File=p01
BEGIN DESCRIPTION:
TRIB 8 TO IRISH CREEK
END DESCRIPTION:

--- TRIB 8 TO IRISH CREEK.p01 (plan) ---

Plan Title=Multiple Run
Short Identifier=Multiple
Geom File=g01
Flow File=f01
Subcritical Flow
K Sum by GR= 0
Std Step Tol= 0.01
Critical Tol= 0.01
Num of Std Step Trials= 20
Max Error Tol= 0.3
Flow Tol Ratio= 0.001
Split Flow NTrial= 30
Split Flow Tol= 0.02
Split Flow Ratio= 0.02
Log Output Level= 0
Friction Slope Method= 1
Unsteady Friction Slope Method= 2
Unsteady Bridges Friction Slope Method= 1
Parabolic Critical Depth
Global Vel Dist=  1 , 1 , 1
Global Log Level= 0
CheckData=True
Encroach Param= -1, 0, 0, 0
BEGIN DESCRIPTION:
Multiple Run
END DESCRIPTION:

--- TRIB 8 TO IRISH CREEK.f01 (steady flow) ---

Flow Title=Multiple
Number of Profiles=7
Profile Names=10-year,25-year,50-year,1pct_min,100-year,1pct_plu,500-year
River Rch & RM= TRIB 8 TO IRISH ,Reach-1,9701
     509     814    1088     707    1410    2814    2340
River Rch & RM= TRIB 8 TO IRISH ,Reach-1,7008
     553     887    1188     772    1541    3074    2561
River Rch & RM= TRIB 8 TO IRISH ,Reach-1,4803
     839    1381    1880    1241    2476    4939    4248
River Rch & RM= TRIB 8 TO IRISH ,Reach-1,3906
     941    1553    2118    1400    2792    5572    4805
Boundary for River Rch & Prof#=TRIB 8 TO IRISH ,Reach-1,1
Up Type=0
Dn Type=3
Dn Slope=0.005
Boundary for River Rch & Prof#=TRIB 8 TO IRISH ,Reach-1,2
Up Type=0
Dn Type=3
Dn Slope=0.005
Boundary for River Rch & Prof#=TRIB 8 TO IRISH ,Reach-1,3
Up Type=0
Dn Type=3
Dn Slope=0.005
Boundary for River Rch & Prof#=TRIB 8 TO IRISH ,Reach-1,4
Up Type=0
Dn Type=3
Dn Slope=0.005
Boundary for River Rch & Prof#=TRIB 8 TO IRISH ,Reach-1,5
Up Type=0
Dn Type=3
Dn Slope=0.005
Boundary for River Rch & Prof#=TRIB 8 TO IRISH ,Reach-1,6
Up Type=0
Dn Type=3
Dn Slope=0.005
Boundary for River Rch & Prof#=TRIB 8 TO IRISH ,Reach-1,7
Up Type=0
Dn Type=3
Dn Slope=0.005

--- TRIB 8 TO IRISH CREEK.g01 (geometry) ---

Geom Title=Existing Conditions

River Reach=TRIB 8 TO IRISH ,Reach-1
Reach XY= 30
      2535825.00     13601975.00      2535781.87     13601925.12
      2535877.24     13601580.93      2536073.78     13601114.49
      2536025.09     13600840.39      2536127.06     13600430.85
      2536274.07     13600264.52      2536226.80     13600081.11
      2536430.52     13599622.57      2536571.54     13599473.50
      2536534.02     13599317.98      2536671.96     13599223.58
      2536630.40     13599022.03      2536773.03     13598969.50
      2536732.56     13598825.00      2536824.62     13598490.27
      2536682.20     13598171.56      2537111.36     13597838.36
      2537083.02     13597771.67      2537233.14     13597518.94
      2537611.36     13597138.36      2537597.36     13597051.29
      2538085.50     13596876.22      2538869.07     13596822.76
      2539474.99     13596432.53      2540069.06     13596527.26
      2540371.72     13596666.92      2540462.96     13596626.24
      2540771.79     13596817.20      2540875.00     13596725.00

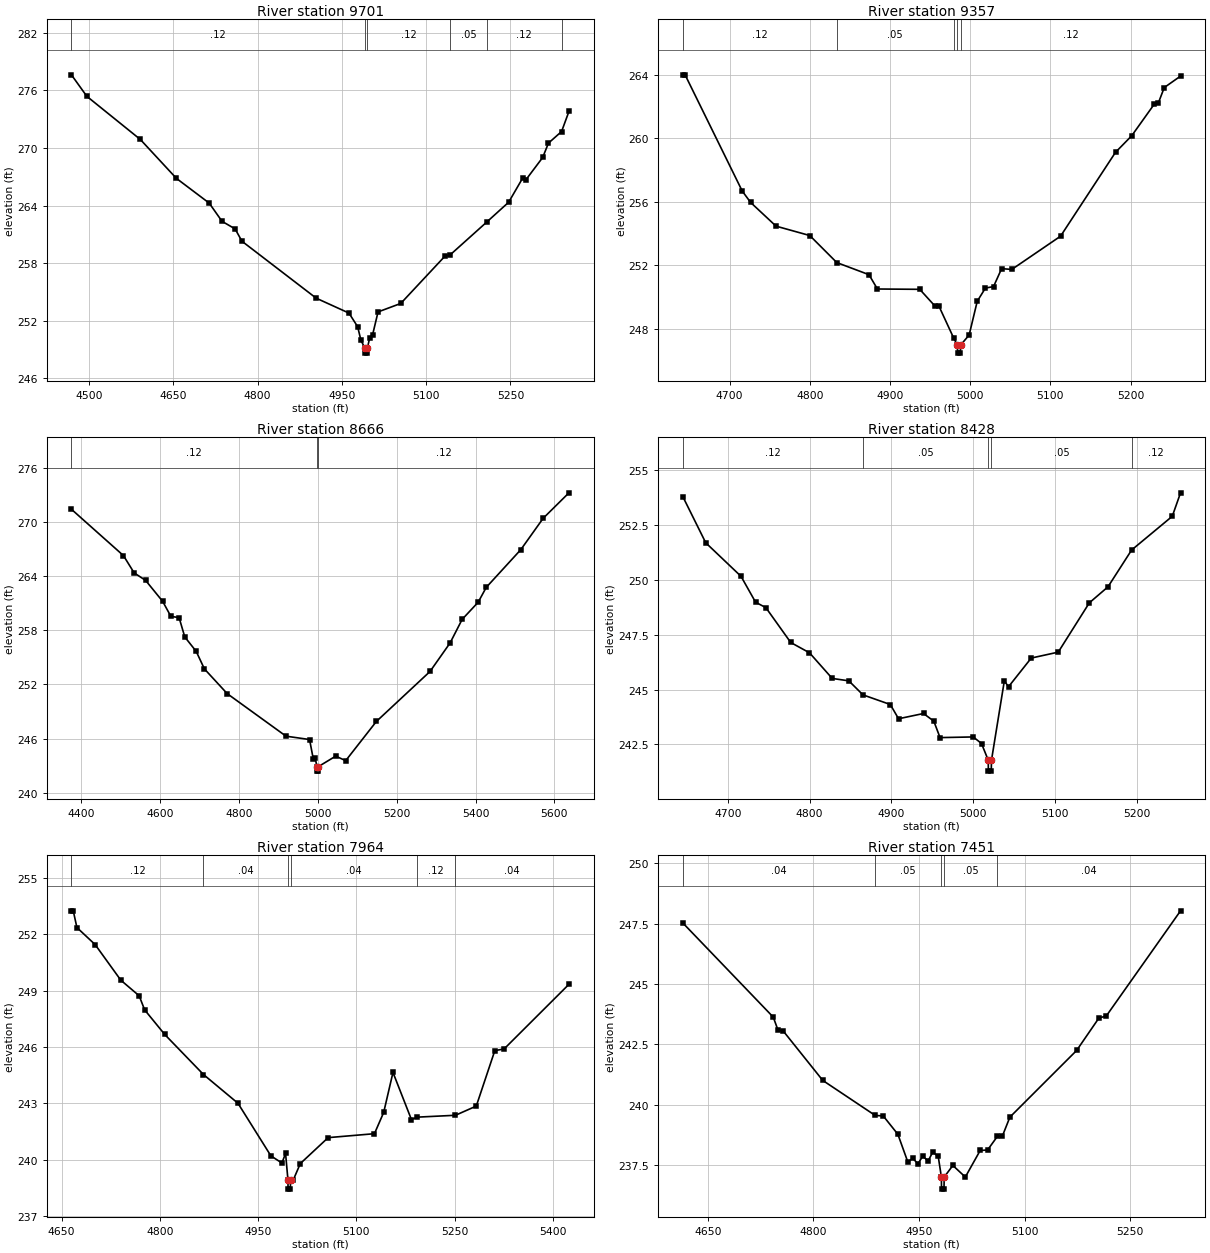
Type RM Length L Ch R = 1,9701,344,344,344
BEGIN DESCRIPTION:
TRIB 8 TO IRISH CREEK 20.0
END DESCRIPTION:
XS GIS Cut Line= 3
      2536264.90     13602163.36      2535809.20     13601889.95
      2535458.85     13601838.04
#Sta/Elev= 30
  4468.6  277.61  4496.1  275.37  4591.3  270.88  4655.5  266.83  4713.8  264.26
  4736.7  262.36  4760.0  261.57  4772.1  260.29  4904.3  254.36  4962.6  252.81
  4978.1  251.39  4984.0  249.96  4991.3  249.14  4991.5  248.64  4995.0  248.64
  4995.3  249.14  4999.5  250.22  5004.7  250.55  5014.4  252.93  5054.8  253.81
  5133.4  258.73  5142.6  258.86  5207.8  262.28  5246.9  264.35  5272.4  266.92
  5277.4  266.67  5307.5  269.01  5317.7  270.50  5341.1  271.71  5354.2  273.80
#Mann=6,-1,0
  4468.6    0.12       0  4991.3    0.05       0  4995.3    0.12       0
  5142.6    0.05       0  5207.8    0.12       0  5341.1    0.03       0
Bank Sta=4991.3,4995.3
Exp/Cntr=0.3,0.1

Type RM Length L Ch R = 1,9357,691,691,691
BEGIN DESCRIPTION:
TRIB 8 TO IRISH CREEK 19.0
END DESCRIPTION:
XS GIS Cut Line= 3
      2536225.00     13601675.00      2535925.00     13601575.00
      2535624.97     13601525.00
#Sta/Elev= 30
  4641.9  263.98  4644.5  263.98  4715.7  256.68  4726.2  255.96  4757.9  254.47
  4800.0  253.88  4833.7  252.18  4873.8  251.42  4884.3  250.52  4937.1  250.50
  4955.5  249.48  4960.7  249.48  4979.2  247.46  4984.0  246.99  4984.3  246.49
  4987.8  246.49  4988.0  246.99  4998.7  247.63  5008.8  249.75  5019.0  250.58
  5029.1  250.67  5039.2  251.80  5051.9  251.75  5112.7  253.84  5181.2  259.11
  5201.4  260.15  5229.3  262.12  5234.4  262.18  5242.0  263.18  5262.3  263.90
#Mann=5,-1,0
  4641.9    0.12       0  4833.7    0.05       0  4979.2    0.12       0
  4984.0    0.05       0  4988.0    0.12       0
Bank Sta=4984,4988
Exp/Cntr=0.3,0.1

Type RM Length L Ch R = 1,8666,238,238,238
BEGIN DESCRIPTION:
Mapping XS 914cd593
END DESCRIPTION:
XS GIS Cut Line= 3
      2536484.68     13601389.63      2536143.52     13600952.12
      2535449.07     13600816.87
#Sta/Elev= 30
  4374.6  271.40  4506.6  266.27  4533.8  264.35  4562.7  263.53  4606.1  261.20
  4626.9  259.54  4647.8  259.40  4662.2  257.26  4691.2  255.66  4712.0  253.72
  4769.9  250.98  4919.1  246.27  4978.8  245.90  4988.4  243.71  4993.5  243.83
  4997.2  242.90  4997.5  242.40  5001.0  242.40  5001.2  242.90  5045.1  244.06
  5070.5  243.56  5148.3  247.90  5284.5  253.44  5335.4  256.60  5366.0  259.21
  5406.5  261.10  5427.1  262.75  5514.8  266.93  5571.5  270.40  5636.9  273.22
#Mann=3,-1,0
  4374.6    0.12       0  4997.2    0.05       0  5001.2    0.12       0
Bank Sta=4997.2,5001.2
Exp/Cntr=0.3,0.1

Type RM Length L Ch R = 1,8428,464,464,464
BEGIN DESCRIPTION:
TRIB 8 TO IRISH CREEK 17.0
END DESCRIPTION:
XS GIS Cut Line= 3
      2536424.95     13600774.99      2536125.00     13600725.00
      2535825.03     13600775.00
#Sta/Elev= 30
  4645.3  253.79  4673.1  251.70  4716.2  250.17  4734.0  248.99  4746.6  248.74
  4777.0  247.15  4799.9  246.68  4827.7  245.51  4848.0  245.40  4865.3  244.76
  4898.7  244.32  4908.8  243.67  4939.3  243.91  4951.9  243.56  4959.5  242.81
  5000.1  242.84  5010.2  242.54  5018.4  241.78  5018.6  241.28  5022.1  241.28
  5022.4  241.78  5038.1  245.40  5043.2  245.13  5071.0  246.44  5104.0  246.71
  5142.0  248.96  5164.8  249.69  5193.7  251.37  5243.4  252.91  5253.5  253.98
#Mann=5,-1,0
  4645.3    0.12       0  4865.3    0.05       0  5018.4    0.05       0
  5022.4    0.05       0  5193.7    0.12       0
Bank Sta=5018.4,5022.4
Exp/Cntr=0.3,0.1

Type RM Length L Ch R = 1,7964,513,513,513
BEGIN DESCRIPTION:
TRIB 8 TO IRISH CREEK 16.0
END DESCRIPTION:
XS GIS Cut Line= 3
      2536524.98     13600474.99      2536225.00     13600325.00
      2535924.97     13600024.97
#Sta/Elev= 30
  4664.9  253.24  4667.7  253.24  4673.3  252.35  4701.2  251.44  4740.3  249.55
  4768.3  248.72  4776.7  247.97  4807.4  246.66  4866.5  244.53  4919.2  243.00
  4969.5  240.20  4986.3  239.82  4991.9  240.33  4995.5  238.93  4995.7  238.43
  4999.2  238.43  4999.5  238.93  5003.8  238.93  5014.4  239.79  5056.9  241.17
  5127.6  241.38  5141.7  242.51  5155.9  244.64  5184.1  242.13  5192.6  242.26
  5251.3  242.36  5283.1  242.85  5311.4  245.80  5325.6  245.89  5424.6  249.33
#Mann=6,-1,0
  4664.9    0.12       0  4866.5    0.04       0  4995.5    0.04       0
  4999.5    0.04       0  5192.6    0.12       0  5251.3    0.04       0
Bank Sta=4995.5,4999.5
Exp/Cntr=0.3,0.1

Type RM Length L Ch R = 1,7451,443,443,443
BEGIN DESCRIPTION:
TRIB 8 TO IRISH CREEK 15.0
END DESCRIPTION:
XS GIS Cut Line= 3
      2536574.97     13600174.97      2536325.00     13599875.00
      2536025.00     13599775.00
#Sta/Elev= 30
  4614.8  247.52  4743.0  243.63  4749.5  243.11  4757.3  243.05  4813.3  241.01
  4887.8  239.56  4899.2  239.54  4920.0  238.78  4934.3  237.62  4940.8  237.79
  4948.6  237.56  4955.2  237.87  4963.0  237.68  4969.5  238.04  4977.3  237.87
  4981.8  237.01  4982.0  236.51  4985.5  236.51  4985.8  237.01  4998.1  237.49
  5015.8  237.01  5036.9  238.11  5047.4  238.13  5061.5  238.70  5068.5  238.71
  5079.1  239.49  5173.9  242.25  5205.5  243.59  5216.1  243.68  5321.5  248.03
#Mann=5,-1,0
  4614.8    0.04       0  4887.8    0.05       0  4981.8    0.05       0
  4985.8    0.05       0  5061.5    0.04       0
Bank Sta=4981.8,4985.8
Exp/Cntr=0.3,0.1

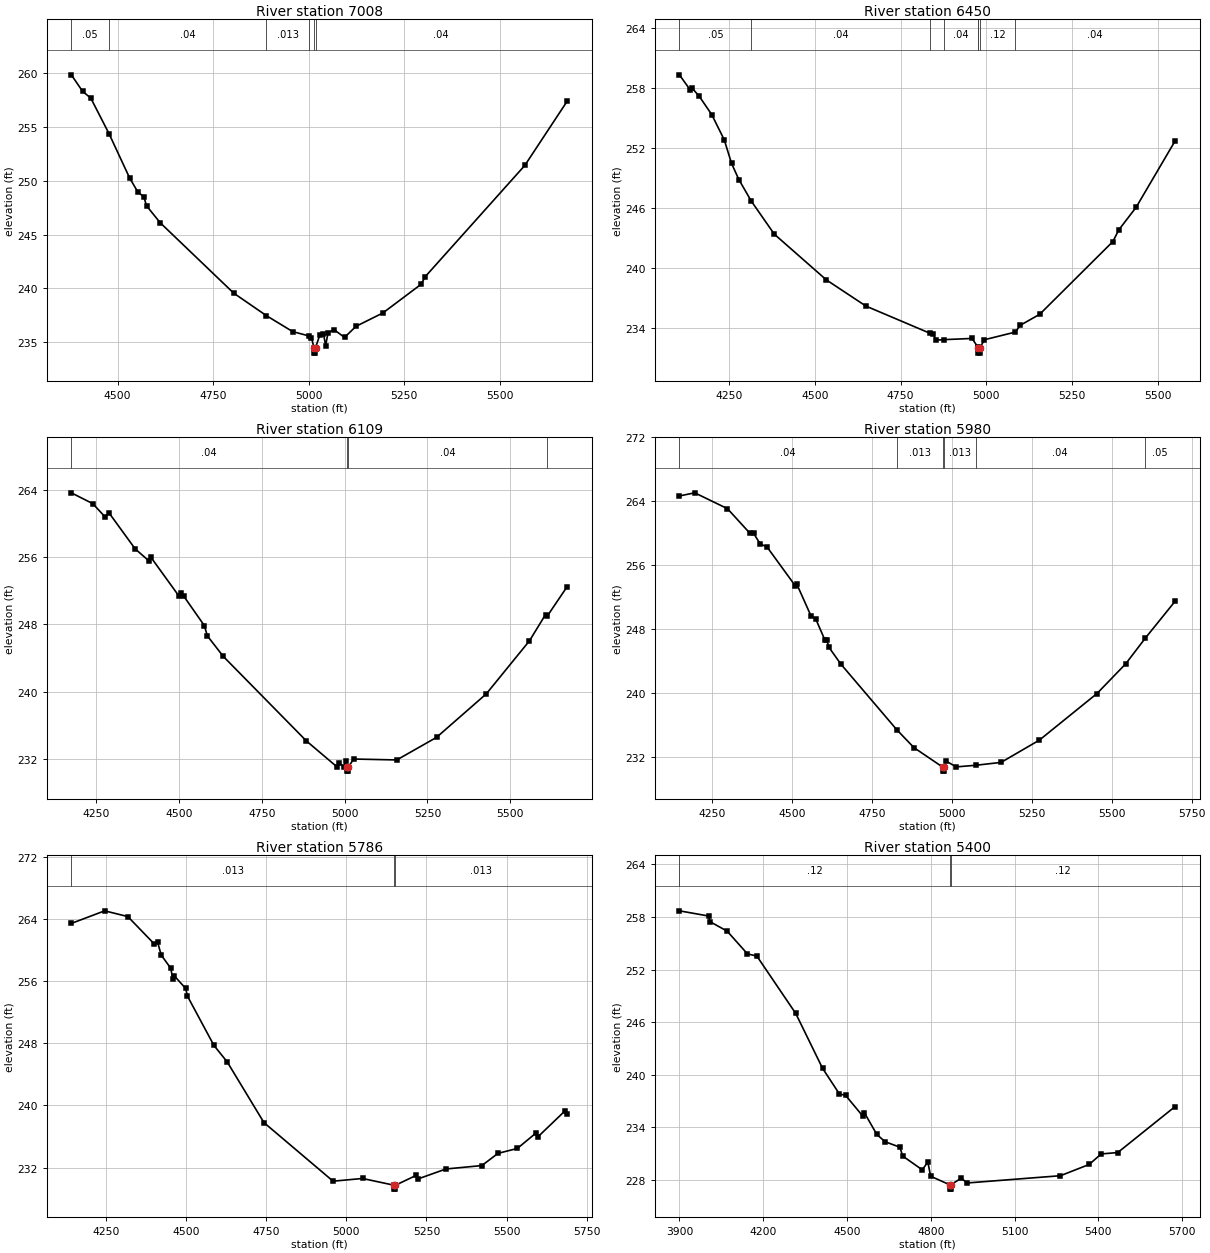
Type RM Length L Ch R = 1,7008,558,558,558
BEGIN DESCRIPTION:
TRIB 8 TO IRISH CREEK 14.0
END DESCRIPTION:
XS GIS Cut Line= 3
      2537075.03     13599825.01      2536475.00     13599475.00
      2535875.03     13599525.00
#Sta/Elev= 30
  4378.9  259.82  4408.3  258.29  4429.8  257.66  4477.5  254.36  4531.5  250.24
  4553.0  248.94  4568.7  248.49  4575.7  247.66  4611.7  246.08  4803.6  239.56
  4889.2  237.47  4957.8  235.99  5001.2  235.58  5007.0  235.44  5013.7  234.49
  5013.9  233.99  5017.4  233.99  5017.7  234.49  5028.5  235.63  5038.4  235.81
  5044.2  234.69  5050.4  235.87  5065.7  236.18  5093.6  235.45  5123.7  236.48
  5194.0  237.72  5294.3  240.39  5304.3  241.07  5565.2  251.41  5675.6  257.35
#Mann=6,-1,0
  4378.9    0.05       0  4477.5    0.04       0  4889.2   0.013       0
  5001.2    0.04       0  5013.7    0.03       0  5017.7    0.04       0
Bank Sta=5013.7,5017.7
Exp/Cntr=0.3,0.1

Type RM Length L Ch R = 1,6450,341,341,341
BEGIN DESCRIPTION:
Mapping XS 88441e98
END DESCRIPTION:
XS GIS Cut Line= 3
      2537159.17     13599751.62      2536750.30     13599103.16
      2536083.60     13598975.55
#Sta/Elev= 30
  4105.0  259.35  4135.7  257.88  4141.7  258.03  4162.9  257.20  4199.3  255.37
  4235.8  252.84  4257.0  250.49  4278.3  248.87  4314.6  246.71  4381.7  243.40
  4533.6  238.82  4648.9  236.20  4835.6  233.48  4845.8  233.38  4852.6  232.78
  4876.3  232.84  4958.4  232.96  4975.9  232.06  4976.8  231.99  4977.1  231.49
  4980.6  231.49  4980.8  231.99  4994.4  232.83  5084.9  233.60  5098.5  234.27
  5155.7  235.38  5369.0  242.66  5386.1  243.82  5437.0  246.10  5550.4  252.73
#Mann=8,-1,0
  4105.0    0.05       0  4314.6    0.04       0  4835.6   0.013       0
  4876.3    0.04       0  4975.9    0.12       0  4976.8    0.05       0
  4980.8    0.12       0  5084.9    0.04       0
Bank Sta=4976.8,4980.8
Exp/Cntr=0.3,0.1

Type RM Length L Ch R = 1,6109,129,129,129
BEGIN DESCRIPTION:
Mapping XS 8d50cbbd
END DESCRIPTION:
XS GIS Cut Line= 3
      2537575.85     13599064.10      2536781.55     13598879.20
      2536101.83     13598913.06
#Sta/Elev= 30
  4175.1  263.66  4240.0  262.37  4277.5  260.77  4288.9  261.27  4367.8  256.99
  4410.4  255.52  4415.5  255.98  4500.7  251.33  4505.8  251.78  4514.8  251.34
  4576.4  247.87  4585.8  246.63  4633.6  244.20  4884.4  234.14  4976.8  231.05
  4984.5  231.50  4997.2  231.04  5004.5  231.76  5007.5  231.04  5007.7  230.54
  5011.2  230.54  5011.5  231.04  5027.2  231.98  5157.4  231.87  5277.5  234.56
  5427.7  239.74  5557.9  246.05  5606.3  249.17  5612.1  249.02  5671.2  252.47
#Mann=4,-1,0
  4175.1    0.04       0  5007.5    0.04       0  5011.5    0.04       0
  5612.1    0.05       0
Bank Sta=5007.5,5011.5
Exp/Cntr=0.3,0.1

Type RM Length L Ch R = 1,5980,194,194,194
BEGIN DESCRIPTION:
Mapping XS 786e388b
END DESCRIPTION:
XS GIS Cut Line= 3
      2537601.88     13598957.33      2536773.73     13598777.64
      2536070.65     13598777.64
#Sta/Elev= 30
  4147.7  264.65  4195.7  265.04  4298.0  263.06  4367.7  260.01  4379.9  259.97
  4400.3  258.66  4422.0  258.26  4510.1  253.42  4515.2  253.60  4559.2  249.66
  4574.3  249.26  4603.3  246.59  4608.4  246.68  4615.2  245.74  4652.4  243.64
  4827.6  235.42  4881.3  233.18  4971.4  230.74  4971.6  230.24  4975.1  230.24
  4975.4  230.74  4981.2  231.51  5013.8  230.77  5074.0  230.97  5153.8  231.33
  5273.8  234.12  5453.8  239.94  5543.8  243.66  5604.3  246.83  5698.2  251.48
#Mann=6,-1,0
  4147.7    0.04       0  4827.6   0.013       0  4971.4    0.03       0
  4975.4   0.013       0  5074.0    0.04       0  5604.3    0.05       0
Bank Sta=4971.4,4975.4
Exp/Cntr=0.3,0.1

Type RM Length L Ch R = 1,5786,386,386,386
BEGIN DESCRIPTION:
Mapping XS 430e3c0b
END DESCRIPTION:
XS GIS Cut Line= 3
      2537635.69     13598808.88      2536797.17     13598592.74
      2536120.91     13598519.92
#Sta/Elev= 30
  4142.2  263.40  4246.2  265.02  4318.5  264.28  4401.1  260.75  4411.4  260.98
  4422.5  259.34  4452.7  257.61  4458.1  256.31  4463.2  256.66  4498.7  255.05
  4504.4  254.05  4587.0  247.71  4628.3  245.60  4742.9  237.79  4958.7  230.25
  5050.5  230.60  5149.1  229.73  5149.4  229.23  5152.9  229.23  5153.1  229.73
  5218.5  231.01  5223.5  230.54  5310.5  231.82  5422.7  232.26  5473.0  233.83
  5533.3  234.46  5591.4  236.44  5596.4  235.91  5683.3  239.34  5688.3  238.87
#Mann=3,-1,0
  4142.2   0.013       0  5149.1    0.03       0  5153.1   0.013       0
Bank Sta=5149.1,5153.1
Exp/Cntr=0.3,0.1

Type RM Length L Ch R = 1,5400,597,597,597
BEGIN DESCRIPTION:
Mapping XS c81dd5c0
END DESCRIPTION:
XS GIS Cut Line= 4
      2537742.52     13598577.14      2537060.19     13598233.37
      2536469.05     13598256.81      2536104.43     13598462.55
#Sta/Elev= 30
  3900.1  258.69  4004.3  258.10  4009.9  257.45  4071.2  256.37  4143.7  253.78
  4177.2  253.54  4316.6  246.99  4412.4  240.75  4472.8  237.82  4495.1  237.65
  4556.4  235.30  4562.0  235.69  4606.6  233.21  4636.4  232.37  4689.3  231.75
  4699.4  230.74  4769.4  229.17  4789.4  230.06  4799.4  228.44  4867.5  227.47
  4867.7  226.97  4871.2  226.97  4871.5  227.47  4909.5  228.22  4929.5  227.67
  5264.2  228.50  5366.7  229.78  5410.0  230.98  5469.3  231.14  5674.4  236.38
#Mann=3,-1,0
  3900.1    0.12       0  4867.5    0.05       0  4871.5    0.12       0
Bank Sta=4867.5,4871.5
Exp/Cntr=0.3,0.1

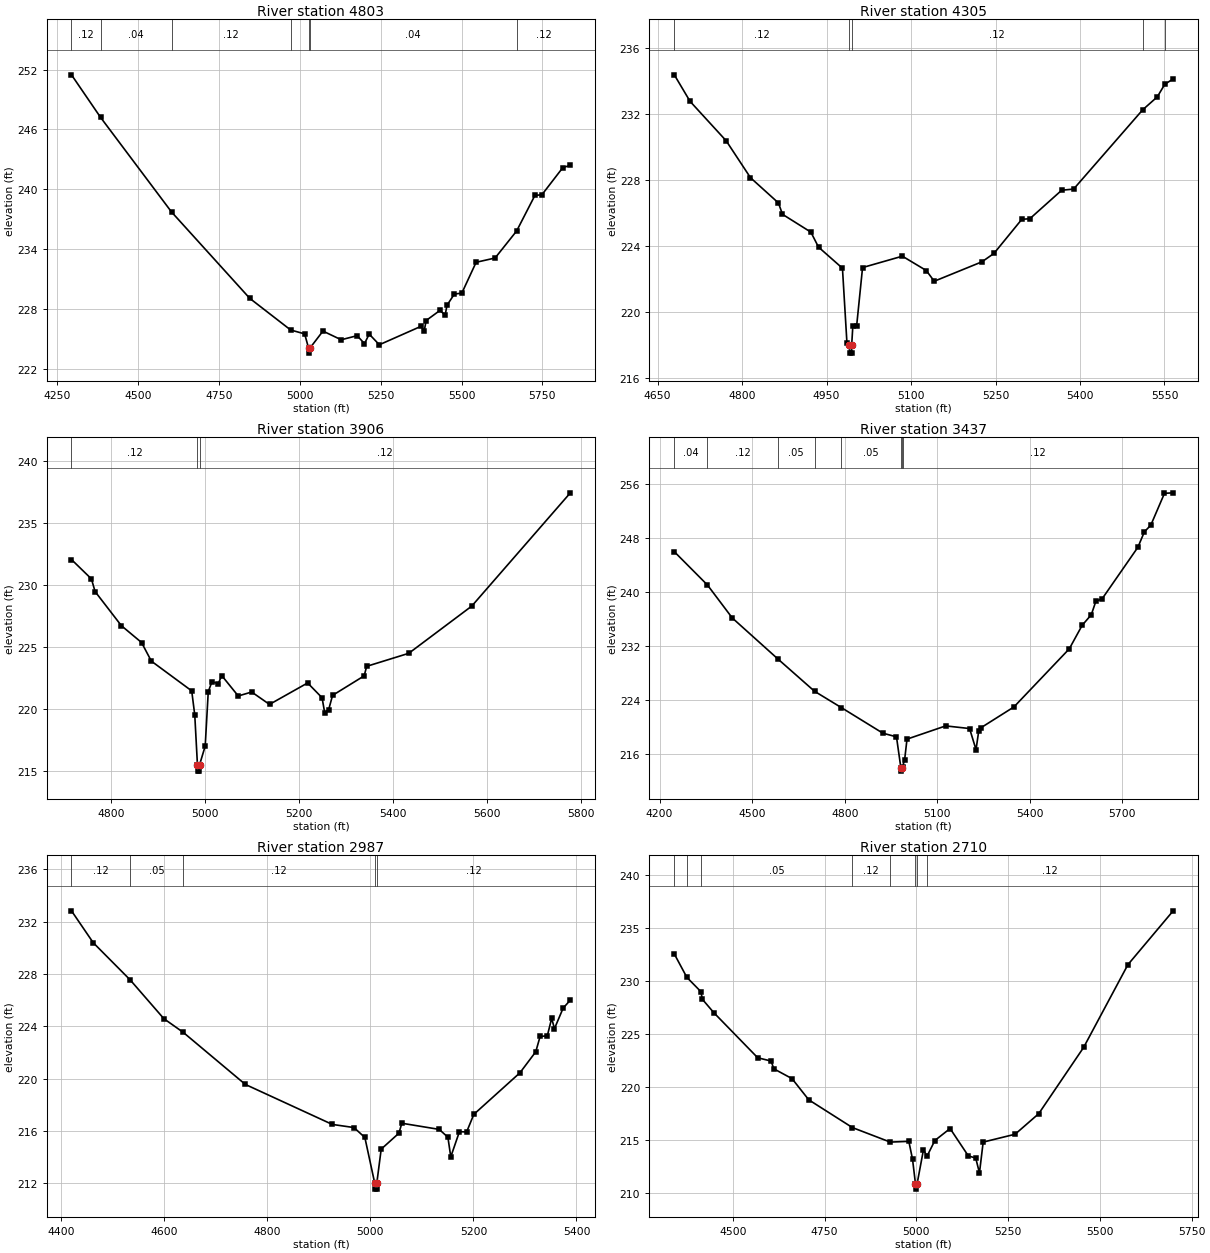
Type RM Length L Ch R = 1,4803,498,498,498
BEGIN DESCRIPTION:
TRIB 8 TO IRISH CREEK 10.0
END DESCRIPTION:
XS GIS Cut Line= 3
      2537575.03     13598375.03      2536975.00     13597775.00
      2536624.99     13597174.99
#Sta/Elev= 30
  4293.4  251.48  4383.4  247.21  4602.8  237.73  4845.0  229.06  4971.4  225.89
  5014.7  225.50  5026.8  224.07  5027.0  223.57  5030.9  224.07  5071.3  225.78
  5127.8  224.91  5177.1  225.32  5199.8  224.52  5214.3  225.48  5245.7  224.41
  5374.7  226.26  5384.7  225.82  5390.5  226.84  5433.5  227.86  5449.2  227.37
  5455.0  228.37  5477.7  229.49  5500.9  229.59  5545.1  232.68  5603.8  233.11
  5670.4  235.82  5727.0  239.39  5748.5  239.45  5813.4  242.18  5836.6  242.40
#Mann=7,-1,0
  4293.4    0.12       0  4383.4    0.04       0  4602.8    0.12       0
  4971.4    0.04       0  5026.8    0.04       0  5030.9    0.04       0
  5670.4    0.12       0
Bank Sta=5026.8,5030.9
Exp/Cntr=0.3,0.1

Type RM Length L Ch R = 1,4305,399,399,399
BEGIN DESCRIPTION:
TRIB 8 TO IRISH CREEK 9.0
END DESCRIPTION:
XS GIS Cut Line= 3
      2537525.01     13597675.01      2537275.00     13597475.00
      2536874.97     13597074.97
#Sta/Elev= 30
  4679.6  234.40  4707.6  232.79  4771.7  230.40  4814.9  228.16  4864.5  226.63
  4871.7  225.94  4922.1  224.86  4935.7  223.95  4978.2  222.67  4986.2  218.12
  4990.5  218.02  4990.8  217.52  4994.4  217.52  4994.6  218.02  4996.6  219.14
  5003.3  219.14  5013.9  222.71  5084.6  223.40  5127.1  222.53  5141.2  221.88
  5226.0  223.06  5247.3  223.57  5296.8  225.64  5310.9  225.67  5367.5  227.40
  5388.7  227.47  5511.4  232.28  5537.2  233.06  5550.7  233.83  5565.5  234.15
#Mann=5,-1,0
  4679.6    0.12       0  4990.5    0.05       0  4994.6    0.12       0
  5511.4    0.04       0  5550.7    0.12       0
Bank Sta=4990.5,4994.6
Exp/Cntr=0.3,0.1

Type RM Length L Ch R = 1,3906,469,469,469
BEGIN DESCRIPTION:
TRIB 8 TO IRISH CREEK 8.0
END DESCRIPTION:
XS GIS Cut Line= 3
      2537725.03     13597425.04      2537475.00     13597125.00
      2537174.99     13596524.98
#Sta/Elev= 30
  4716.1  232.02  4758.5  230.46  4766.3  229.44  4822.2  226.69  4865.2  225.33
  4886.0  223.83  4971.9  221.43  4978.4  219.48  4984.1  215.46  4984.4  214.96
  4988.2  214.96  4988.5  215.46  5000.6  216.98  5007.1  221.37  5014.9  222.16
  5028.6  222.02  5035.7  222.67  5070.9  221.02  5099.5  221.34  5137.4  220.34
  5218.5  222.07  5249.2  220.88  5254.8  219.68  5263.2  219.91  5271.6  221.07
  5338.7  222.64  5344.2  223.41  5433.7  224.46  5567.8  228.27  5777.5  237.40
#Mann=3,-1,0
  4716.1    0.12       0  4984.1    0.05       0  4988.5    0.12       0
Bank Sta=4984.1,4988.5
Exp/Cntr=0.3,0.1

Type RM Length L Ch R = 1,3437,450,450,450
BEGIN DESCRIPTION:
TRIB 8 TO IRISH CREEK 7.0
END DESCRIPTION:
XS GIS Cut Line= 3
      2537925.01     13597675.05      2537825.00     13596925.00
      2537325.01     13596225.01
#Sta/Elev= 30
  4247.6  245.92  4355.1  240.98  4435.5  236.10  4583.7  230.01  4702.1  225.24
  4789.4  222.81  4923.6  219.03  4967.7  218.49  4981.9  213.91  4982.2  213.41
  4986.3  213.91  4987.4  214.08  4994.2  215.12  5001.8  218.15  5127.2  220.11
  5204.6  219.72  5225.5  216.59  5234.1  219.30  5240.2  219.80  5348.4  222.92
  5527.8  231.53  5569.6  235.02  5599.1  236.58  5613.8  238.56  5634.7  238.97
  5750.2  246.58  5771.1  248.86  5792.0  249.85  5836.3  254.57  5864.5  254.64
#Mann=8,-1,0
  4247.6    0.04       0  4355.1    0.12       0  4583.7    0.05       0
  4702.1    0.12       0  4789.4    0.05       0  4981.9    0.05       0
  4986.3    0.05       0  4987.4    0.12       0
Bank Sta=4981.9,4986.3
Exp/Cntr=0.3,0.1

Type RM Length L Ch R = 1,2987,277,277,277
BEGIN DESCRIPTION:
TRIB 8 TO IRISH CREEK 6.0
END DESCRIPTION:
XS GIS Cut Line= 3
      2538074.99     13597425.02      2538275.00     13596825.00
      2538124.99     13596524.99
#Sta/Elev= 30
  4420.2  232.83  4462.4  230.39  4534.2  227.54  4599.4  224.58  4637.1  223.53
  4757.5  219.55  4926.2  216.49  4968.3  216.25  4989.4  215.49  5008.3  212.04
  5008.6  211.54  5012.4  211.54  5012.7  212.04  5021.1  214.60  5055.5  215.82
  5061.1  216.58  5133.7  216.11  5150.5  215.51  5156.1  214.01  5172.9  215.94
  5186.8  215.91  5200.8  217.26  5290.3  220.44  5321.0  222.05  5329.4  223.22
  5343.4  223.27  5351.8  224.60  5357.3  223.82  5374.1  225.39  5388.1  226.00
#Mann=5,-1,0
  4420.2    0.12       0  4534.2    0.05       0  4637.1    0.12       0
  5008.3    0.05       0  5012.7    0.12       0
Bank Sta=5008.3,5012.7
Exp/Cntr=0.3,0.1

Type RM Length L Ch R = 1,2710,298,298,298
BEGIN DESCRIPTION:
Mapping XS 0125e09c
END DESCRIPTION:
XS GIS Cut Line= 4
      2538354.48     13597491.14      2538545.43     13596939.10
      2538503.77     13596675.21      2538194.72     13596272.40
#Sta/Elev= 30
  4340.7  232.53  4374.9  230.32  4412.9  228.98  4417.4  228.24  4448.5  226.98
  4567.9  222.73  4604.4  222.42  4611.7  221.69  4661.4  220.76  4707.0  218.76
  4825.9  216.14  4929.0  214.77  4979.6  214.84  4989.7  213.14  4997.7  210.83
  4998.0  210.33  5002.1  210.83  5019.4  214.04  5029.2  213.44  5050.5  214.92
  5092.0  216.05  5141.6  213.47  5161.8  213.26  5172.0  211.86  5182.1  214.77
  5269.0  215.51  5333.4  217.45  5455.8  223.71  5576.4  231.52  5699.7  236.60
#Mann=8,-1,0
  4340.7    0.12       0  4374.9    0.04       0  4412.9    0.05       0
  4825.9    0.12       0  4929.0    0.05       0  4997.7    0.05       0
  5002.1    0.05       0  5029.2    0.12       0
Bank Sta=4997.7,5002.1
Exp/Cntr=0.3,0.1

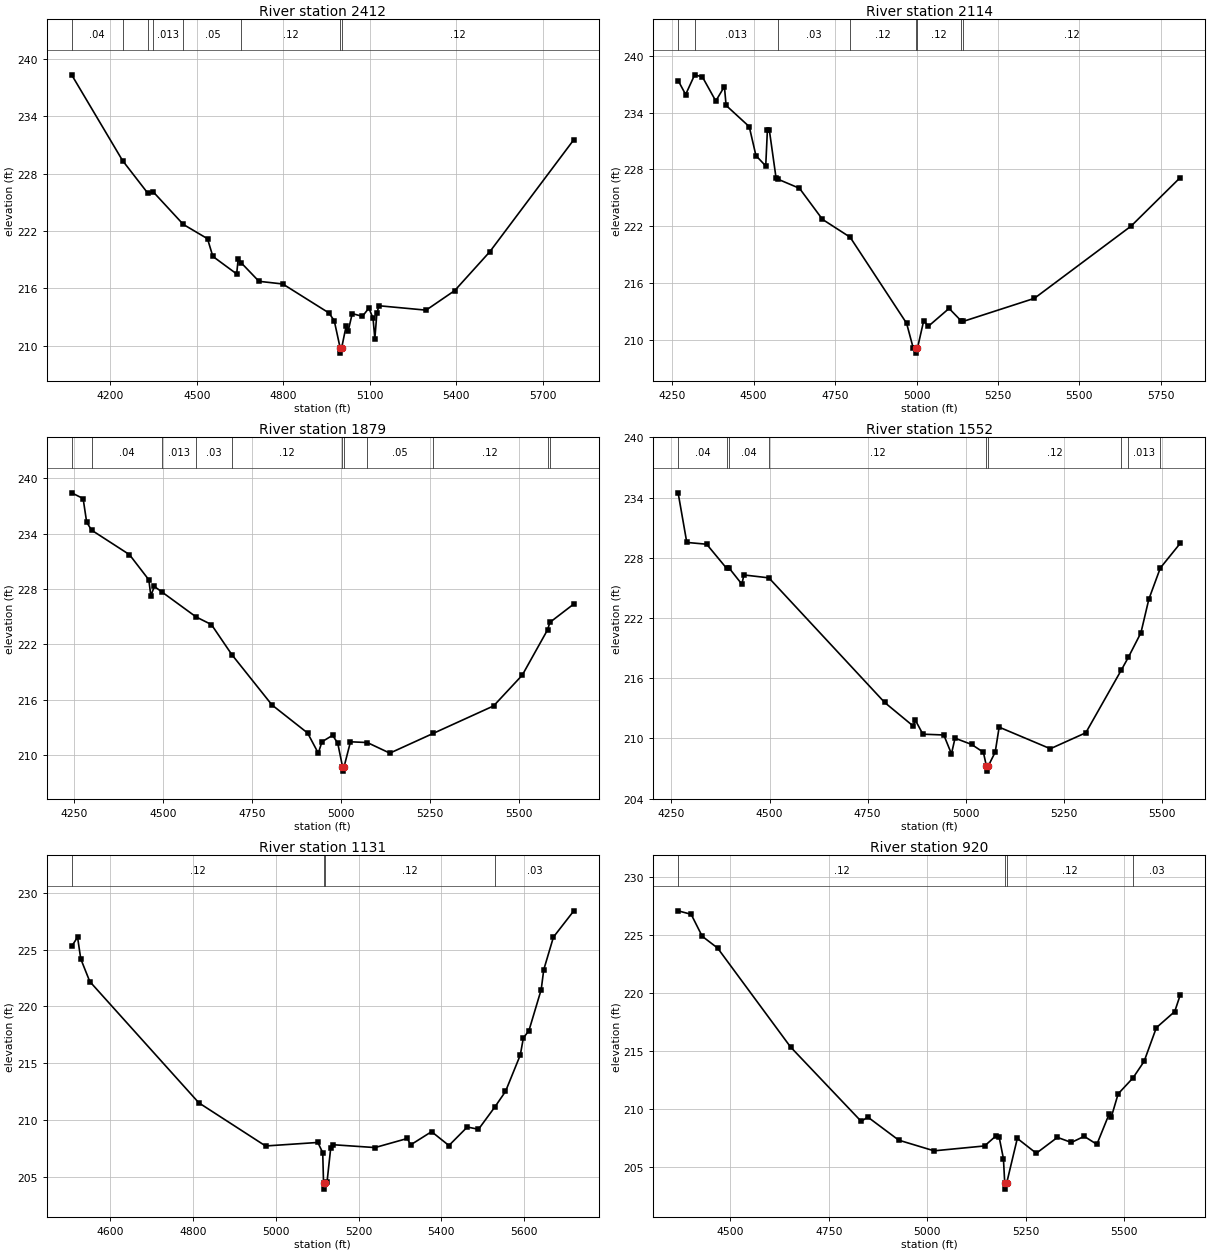
Type RM Length L Ch R = 1,2412,298,298,298
BEGIN DESCRIPTION:
Mapping XS f9ea0c6c
END DESCRIPTION:
XS GIS Cut Line= 3
      2538462.09     13597689.12      2538823.21     13596810.63
      2538330.51     13596189.55
#Sta/Elev= 30
  4066.1  238.36  4242.8  229.38  4331.0  225.94  4348.1  226.14  4453.4  222.70
  4537.5  221.20  4556.0  219.35  4638.7  217.51  4644.1  219.12  4655.3  218.65
  4716.0  216.74  4798.7  216.46  4958.7  213.43  4977.3  212.62  4998.1  209.72
  4998.4  209.22  5002.7  209.72  5018.9  212.11  5025.3  211.49  5039.7  213.36
  5075.0  213.07  5097.4  213.93  5111.9  212.88  5118.2  210.72  5125.2  213.41
  5132.7  214.18  5296.1  213.72  5395.4  215.77  5517.2  219.84  5808.7  231.57
#Mann=8,-1,0
  4066.1    0.04       0  4242.8   0.013       0  4331.0    0.04       0
  4348.1   0.013       0  4453.4    0.05       0  4655.3    0.12       0
  4998.1    0.05       0  5002.7    0.12       0
Bank Sta=4998.1,5002.7
Exp/Cntr=0.3,0.1

Type RM Length L Ch R = 1,2114,235,235,235
BEGIN DESCRIPTION:
Mapping XS 04d4b4cf
END DESCRIPTION:
XS GIS Cut Line= 3
      2539232.94     13597397.47      2539062.80     13596678.68
      2538486.55     13596119.79
#Sta/Elev= 30
  4268.3  237.38  4291.4  235.90  4319.1  237.98  4342.8  237.76  4383.9  235.22
  4410.4  236.74  4415.6  234.75  4486.6  232.51  4507.2  229.45  4537.2  228.36
  4542.4  232.20  4548.3  232.14  4568.8  227.12  4573.5  226.98  4640.8  226.00
  4711.4  222.72  4796.2  220.84  4969.6  211.75  4990.2  209.10  4998.2  209.10
  4998.5  208.60  5002.8  209.10  5022.1  212.02  5036.2  211.43  5100.0  213.32
  5136.6  212.02  5143.3  211.95  5361.6  214.38  5658.6  222.01  5809.7  227.14
#Mann=8,-1,0
  4268.3    0.03       0  4319.1   0.013       0  4573.5    0.03       0
  4796.2    0.12       0  4998.2    0.05       0  5002.8    0.12       0
  5136.6    0.05       0  5143.3    0.12       0
Bank Sta=4998.2,5002.8
Exp/Cntr=0.3,0.1

Type RM Length L Ch R = 1,1879,327,327,327
BEGIN DESCRIPTION:
Mapping XS 0eed8a00
END DESCRIPTION:
XS GIS Cut Line= 3
      2539278.07     13597307.16      2539250.30     13596564.10
      2539184.32     13595900.86
#Sta/Elev= 30
  4242.9  238.43  4275.1  237.81  4285.1  235.24  4299.0  234.38  4405.2  231.73
  4459.6  229.00  4465.2  227.28  4475.2  228.28  4496.4  227.68  4592.6  224.97
  4635.3  224.15  4692.5  220.90  4805.5  215.43  4905.5  212.39  4935.5  210.20
  4945.6  211.44  4975.6  212.14  4990.0  211.30  5003.4  208.76  5003.7  208.26
  5008.0  208.76  5025.8  211.44  5073.0  211.36  5136.3  210.21  5257.5  212.34
  5427.7  215.33  5508.1  218.66  5579.1  223.57  5585.8  224.39  5653.0  226.38
#Mann=11,-1,0
  4242.9    0.03       0  4299.0    0.04       0  4496.4   0.013       0
  4592.6    0.03       0  4692.5    0.12       0  5003.4    0.05       0
  5008.0    0.12       0  5073.0    0.05       0  5257.5    0.12       0
  5579.1    0.05       0  5585.8    0.03       0
Bank Sta=5003.4,5008
Exp/Cntr=0.3,0.1

Type RM Length L Ch R = 1,1552,421,421,421
BEGIN DESCRIPTION:
TRIB 8 TO IRISH CREEK 3.0
END DESCRIPTION:
XS GIS Cut Line= 3
      2539325.01     13597174.97      2539525.00     13596475.00
      2539475.00     13595925.05
#Sta/Elev= 30
  4267.0  234.47  4289.1  229.53  4339.8  229.35  4390.4  226.96  4397.3  226.96
  4429.5  225.37  4434.7  226.29  4498.4  226.00  4793.5  213.59  4866.3  211.24
  4871.5  211.84  4891.0  210.43  4944.3  210.35  4963.8  208.47  4972.9  210.03
  5015.1  209.41  5045.2  208.63  5052.9  207.25  5053.2  206.75  5057.5  207.25
  5075.3  208.64  5085.4  211.13  5215.9  208.98  5306.3  210.57  5397.0  216.83
  5414.8  218.09  5446.8  220.53  5466.9  223.86  5496.2  226.98  5547.2  229.45
#Mann=9,-1,0
  4267.0    0.04       0  4390.4   0.013       0  4397.3    0.04       0
  4498.4    0.12       0  5052.9    0.05       0  5057.5    0.12       0
  5397.0    0.03       0  5414.8   0.013       0  5496.2    0.03       0
Bank Sta=5052.9,5057.5
Exp/Cntr=0.3,0.1

Type RM Length L Ch R = 1,1131,211,211,211
BEGIN DESCRIPTION:
TRIB 8 TO IRISH CREEK 2.0
END DESCRIPTION:
XS GIS Cut Line= 3
      2539725.00     13596974.99      2539975.00     13596425.00
      2539624.99     13595924.98
#Sta/Elev= 30
  4506.1  225.29  4520.4  226.10  4528.1  224.19  4550.0  222.19  4813.7  211.51
  4975.1  207.71  5101.5  208.02  5113.3  207.12  5115.3  204.41  5115.7  203.91
  5120.0  204.41  5123.8  204.56  5132.5  207.49  5138.6  207.82  5239.7  207.57
  5317.8  208.37  5326.0  207.81  5376.6  208.97  5418.5  207.75  5462.9  209.38
  5490.0  209.18  5529.5  211.14  5555.3  212.51  5591.1  215.72  5598.5  217.22
  5612.0  217.87  5641.7  221.49  5647.8  223.23  5671.3  226.11  5720.6  228.42
#Mann=4,-1,0
  4506.1    0.12       0  5115.3    0.05       0  5120.0    0.12       0
  5529.5    0.03       0
Bank Sta=5115.3,5120
Exp/Cntr=0.3,0.1

Type RM Length L Ch R = 1,920,268,268,268
BEGIN DESCRIPTION:
Mapping XS 63a5b871
END DESCRIPTION:
XS GIS Cut Line= 3
      2539844.04     13597137.02      2540184.32     13596449.51
      2539993.91     13595978.67
#Sta/Elev= 30
  4367.5  227.05  4400.6  226.75  4428.6  224.86  4467.8  223.84  4652.9  215.32
  4832.3  208.91  4849.1  209.28  4927.6  207.29  5017.3  206.37  5145.5  206.79
  5175.0  207.67  5182.6  207.55  5193.4  205.70  5196.8  203.57  5197.1  203.07
  5201.5  203.57  5228.7  207.44  5276.9  206.16  5330.5  207.53  5366.0  207.09
  5398.4  207.62  5430.7  206.93  5461.9  209.55  5467.3  209.28  5484.7  211.28
  5522.3  212.65  5550.5  214.07  5581.7  216.98  5628.3  218.37  5642.5  219.82
#Mann=4,-1,0
  4367.5    0.12       0  5196.8    0.05       0  5201.5    0.12       0
  5522.3    0.03       0
Bank Sta=5196.8,5201.5
Exp/Cntr=0.3,0.1

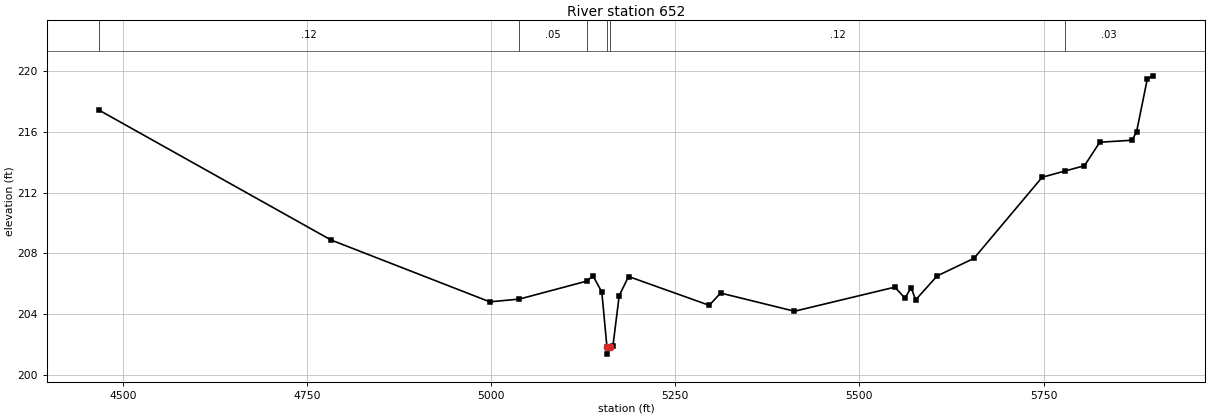
Type RM Length L Ch R = 1,652,0,0,0
BEGIN DESCRIPTION:
TRIB 8 TO IRISH CREEK 1.0
END DESCRIPTION:
XS GIS Cut Line= 3
      2540080.14     13597112.73      2540575.14     13596325.33
      2540174.98     13596024.98
#Sta/Elev= 30
  4467.9  217.44  4782.6  208.88  4998.2  204.80  5038.2  204.98  5130.1  206.17
  5138.3  206.52  5150.3  205.44  5157.2  201.85  5157.5  201.35  5161.9  201.85
  5165.4  201.89  5173.9  205.21  5186.6  206.47  5296.2  204.57  5311.5  205.38
  5411.9  204.18  5548.2  205.77  5561.9  205.04  5570.2  205.74  5576.4  204.93
  5605.6  206.51  5655.6  207.67  5748.2  213.02  5779.1  213.43  5805.6  213.78
  5826.4  215.33  5870.2  215.46  5876.4  216.03  5891.0  219.52  5898.3  219.71
#Mann=6,-1,0
  4467.9    0.12       0  5038.2    0.05       0  5130.1    0.12       0
  5157.2    0.05       0  5161.9    0.12       0  5779.1    0.03       0
Bank Sta=5157.2,5161.9
Exp/Cntr=0.3,0.1

Chan Stop Cuts=-1