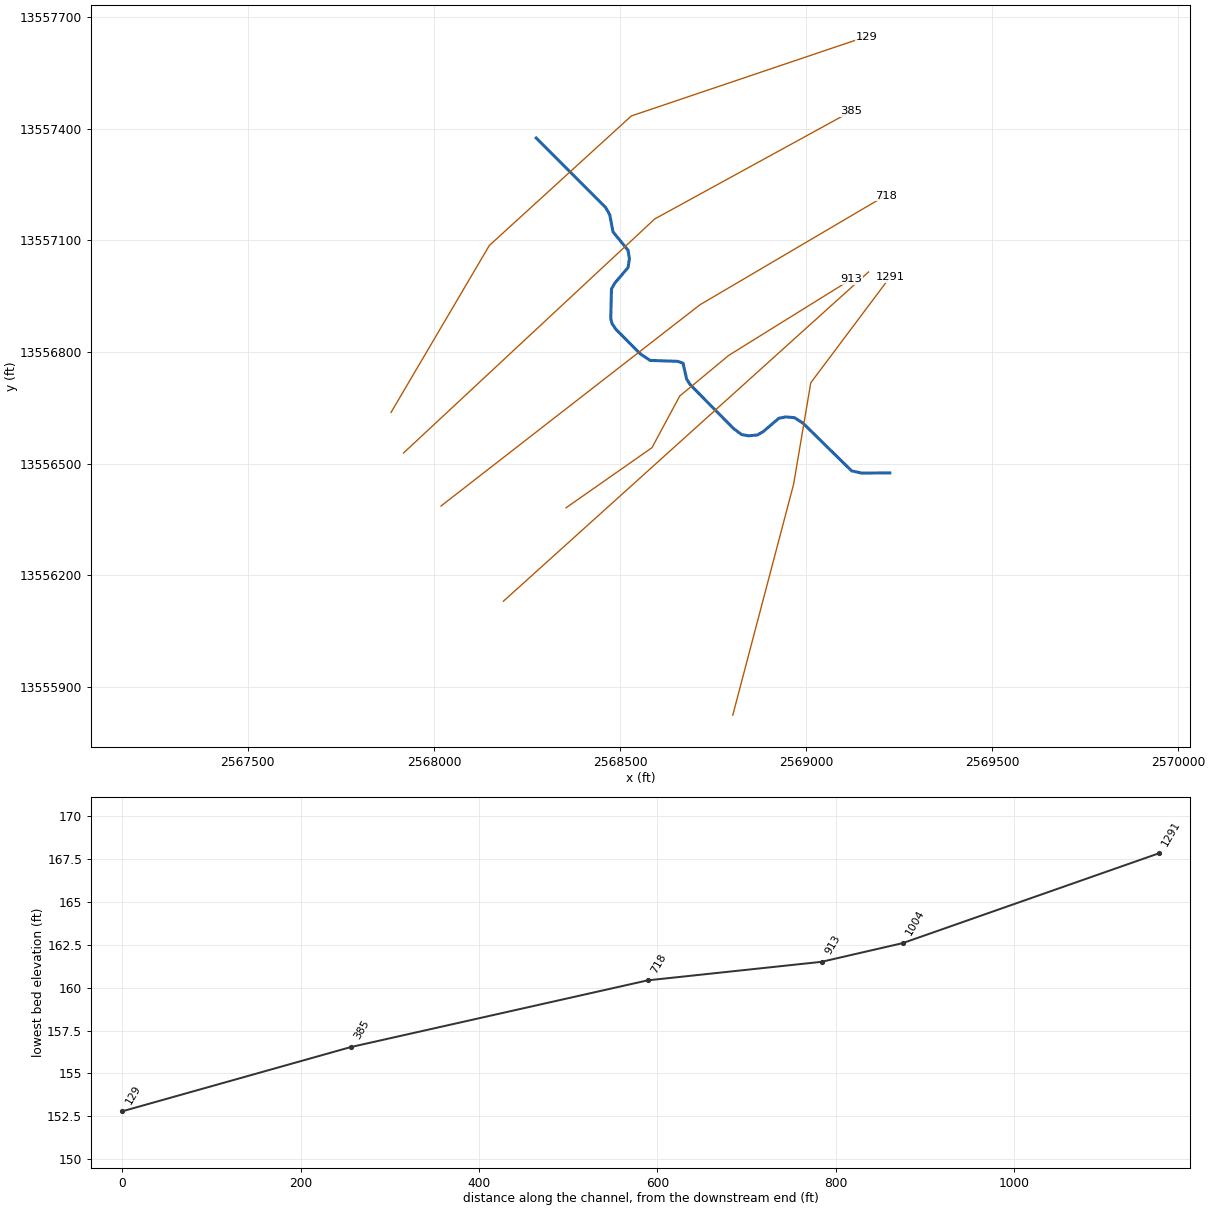
--- TRIB 8 TO PRICE CREEK.prj (project) ---

Proj Title=TRIB 8 TO PRICE CREEK Base Level Engineering
Current Plan=p01
Default Exp/Contr=0.3,0.1
English Units
Geom File=g01
Flow File=f01
Plan File=p01
Y Axis Title=Elevation
X Axis Title(PF)=Main Channel Distance
X Axis Title(XS)=Station
BEGIN DESCRIPTION:
TRIB 8 TO PRICE CREEK
END DESCRIPTION:
DSS Export Rating Curves= 0
DSS Export Rating Curve Sorted= 0
DSS Export Volume Flow Curves= 0
DXF OffsetX= 0
DXF OffsetY= 0
DXF ScaleX= 1
DXF ScaleY= 10

--- TRIB 8 TO PRICE CREEK.p01 (plan) ---

Plan Title=Multiple Run
Program Version=4.10
Short Identifier=Multiple
Geom File=g01
Flow File=f01
Subcritical Flow
K Sum by GR= 0
Std Step Tol= 0.01
Critical Tol= 0.01
Num of Std Step Trials= 20
Max Error Tol= 0.3
Flow Tol Ratio= 0.001
Split Flow NTrial= 30
Split Flow Tol= 0.02
Split Flow Ratio= 0.02
Log Output Level= 0
Friction Slope Method= 1
Unsteady Friction Slope Method= 2
Unsteady Bridges Friction Slope Method= 1
Parabolic Critical Depth
Global Vel Dist= 1 , 1 , 1
Global Log Level= 0
CheckData=True
Encroach Param=-1 ,0,0, 0
BEGIN DESCRIPTION:
Multiple Run
END DESCRIPTION:
Computation Interval=1HOUR
Output Interval=1HOUR
Run HTab= 0
Run UNet= 0
Run PostProcess= 0
Run WQNet= 0
UNET Theta= 1
UNET Theta Warmup= 1
UNET ZTol= 0.02
UNET ZSATol= 0.05
UNET MxIter= 20
UNET MaxInSteps= 0
UNET DtIC= 0
UNET DtMin= 0
UNET MaxCRTS= 20
UNET WFStab= 2
UNET SFStab= 1
UNET WFX= 1
UNET SFX= 1
UNET DSS MLevel= 4
UNET DZMax Abort= 100
UNET Convert EG Bridges= 0
UNET Use Existing IB Tables=-1
UNET Froude Reduction=False
UNET Froude Limit= 1
UNET Froude Power= 10
UNET Time Slicing=0,0, 5
UNET Junction Losses=0
Instantaneous Interval=1HOUR
Write IC File= 0
Write IC File at Sim End=0
Echo Input=False
Echo Parameters=False
Echo Output=False
Write Detailed= 0
WQ AD Non Conservative
WQ ULTIMATE=-1
WQ Max Comp Step=1HOUR
WQ Output Interval=15MIN
WQ Output Selected Increments= 0
WQ Output face flow=0
WQ Output face velocity=0
WQ Output face area=0
WQ Output face dispersion=0
WQ Output cell volume=0
WQ Output cell surface area=0
WQ Output cell continuity=0
WQ Output cumulative cell continuity=0
WQ Output face conc=0
WQ Output face dconc_dx=0
WQ Output face courant=0
WQ Output face peclet=0
WQ Output face adv mass=0
WQ Output face disp mass=0
WQ Output cell mass=0
WQ Output cell source sink temp=0
WQ Output cell source sink nsm=0
WQ Output MaxMinRange=-1
WQ Daily Max Min Mean=-1
WQ Daily Range=0
WQ Daily Time=0
WQ Create Restart=0
WQ Fixed Restart=0
WQ System Summary=0
WQ Use Fixed Temperature=0
Sorting and Armoring Iterations= 10
XS Update Threshold= 0.02
Hydraulics Update Threshold= 0.02
Energy Slope Method= 1
Volume Change Method= 0
XS Weighting Method= 0
Number of US Weighted Cross Sections= 1
Number of DS Weighted Cross Sections= 1
Upstream XS Weight=0.25
Main XS Weight=0.5
Downstream XS Weight=0.25
Number of DS XS's Weighted with US Boundary= 1
Upstream Boundary Weight= 1
Weight of XSs Associated with US Boundary= 0
Number of US XS's Weighted with DS Boundary= 1
Downstream Boundary Weight= 0.5
Weight of XSs Associated with DS Boundary= 0.5
Sediment Output Level= 4
Mass or Volume Output= 0
Output Increment Type= 1
Profile and TS Output Increment= 10
XS Output Flag= 0
XS Output Increment= 10
Disregard all LS=0
Disregard all Conn=0
Disregard all Breaches=0
Disregard all Pumps=0

--- TRIB 8 TO PRICE CREEK.f01 (steady flow) ---

Flow Title=Multiple
Number of Profiles=7
Profile Names=10-year,25-year,50-year,1pct_min,100-year,1pct_plu,500-year
River Rch & RM= TRIB 8 TO PRICE ,Reach-1,1291
     333     509     659     415     829    1653    1291
Boundary for River Rch & Prof#=TRIB 8 TO PRICE ,Reach-1,1
Up Type=0
Dn Type=3
Dn Slope=0.005
Boundary for River Rch & Prof#=TRIB 8 TO PRICE ,Reach-1,2
Up Type=0
Dn Type=3
Dn Slope=0.005
Boundary for River Rch & Prof#=TRIB 8 TO PRICE ,Reach-1,3
Up Type=0
Dn Type=3
Dn Slope=0.005
Boundary for River Rch & Prof#=TRIB 8 TO PRICE ,Reach-1,4
Up Type=0
Dn Type=3
Dn Slope=0.005
Boundary for River Rch & Prof#=TRIB 8 TO PRICE ,Reach-1,5
Up Type=0
Dn Type=3
Dn Slope=0.005
Boundary for River Rch & Prof#=TRIB 8 TO PRICE ,Reach-1,6
Up Type=0
Dn Type=3
Dn Slope=0.005
Boundary for River Rch & Prof#=TRIB 8 TO PRICE ,Reach-1,7
Up Type=0
Dn Type=3
Dn Slope=0.005

--- TRIB 8 TO PRICE CREEK.g01 (geometry) ---

Geom Title=Existing Conditions
Program Version=4.10

River Reach=TRIB 8 TO PRICE ,Reach-1
Reach XY= 30
        2569225.       13556475.      2569149.75     13556474.41
       2569122.5     13556480.35      2568991.68     13556608.78
      2568968.96     13556623.38       2568945.2     13556625.35
      2568926.74     13556621.63      2568884.55     13556585.61
      2568868.88     13556576.81      2568845.13     13556574.61
      2568826.63     13556578.13      2568804.91     13556594.43
      2568688.74     13556712.05      2568679.15     13556727.08
      2568669.53     13556769.74      2568654.74     13556774.78
      2568580.97     13556777.19      2568554.82     13556794.62
      2568488.33     13556861.67      2568478.45     13556876.48
      2568475.24     13556890.21      2568477.19     13556969.03
      2568485.87     13556984.65      2568521.63     13557026.74
      2568525.41       13557050.      2568521.66     13557073.28
      2568481.18     13557122.81      2568472.51     13557168.97
      2568461.38     13557188.22        2568275.       13557375.

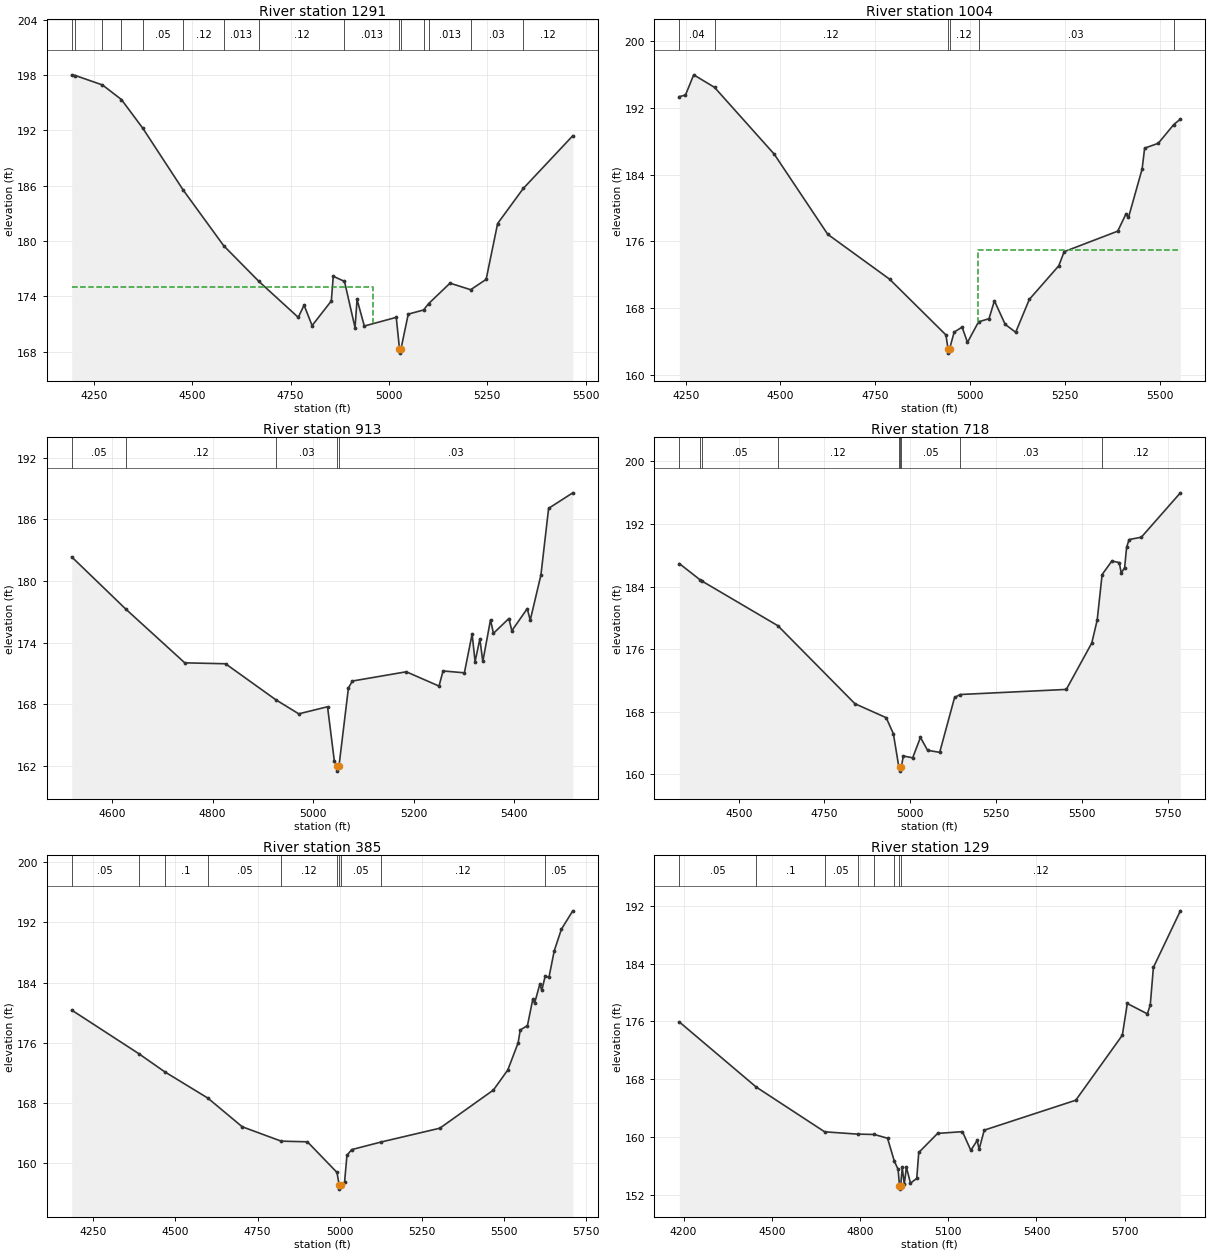
Type RM Length L Ch R = 1 ,1291    ,287,287,287
BEGIN DESCRIPTION:
LGII3160
END DESCRIPTION:
XS GIS Cut Line= 4
      2568803.13      13555824.1      2568966.64     13556444.63
      2569012.77     13556717.17      2569225.75     13557001.15
#Sta/Elev= 30
  4194.1  198.02  4203.6  197.94  4272.3  196.92  4320.4  195.34    4375  192.21
  4477.7   185.5  4580.3  179.48  4669.5  175.62  4769.7  171.71  4784.5  173.03
  4804.9  170.82  4853.7  173.49  4858.7  176.17  4887.2  175.61    4914  170.59
  4919.1  173.65  4937.6  170.77  5018.7  171.71  5026.9  168.33  5027.1  167.83
  5030.9  168.33  5049.2  172.06  5088.1  172.51  5100.7  173.19  5155.4  175.42
  5207.8  174.71  5247.1  175.83  5276.3  181.89  5341.4  185.69  5467.2  191.41
#Mann= 15 ,-1 , 0
  4194.1     .05       0  4203.6     .12       0  4272.3     .05       0
  4320.4     .12       0    4375     .05       0  4477.7     .12       0
  4580.3    .013       0  4669.5     .12       0  4887.2    .013       0
  5026.9     .03       0  5030.9    .013       0  5088.1     .03       0
  5100.7    .013       0  5207.8     .03       0  5341.4     .12       0
#XS Ineff= 2 , 0
       0    4960     175               0
Permanent Ineff=
       F       F
Bank Sta=5026.9,5030.9
XS Rating Curve= 0 ,0
Exp/Cntr=0.3,0.1

Type RM Length L Ch R = 1 ,1004    ,91,91,91
BEGIN DESCRIPTION:
LGII3159
END DESCRIPTION:
XS GIS Cut Line= 2
      2568186.79     13556130.18      2569167.92     13557014.88
#Sta/Elev= 30
  4233.3  193.35  4249.5  193.53  4271.2  195.96  4326.1  194.46  4483.4  186.46
  4624.7  176.84  4787.6  171.47  4936.3  164.78  4941.8   163.1  4942.1   162.6
  4945.8   163.1    4958  165.12  4978.9  165.72  4993.1  163.89  5022.3  166.35
  5049.9  166.73  5064.1  168.87  5092.5  166.05  5120.2   165.1  5156.1  169.04
  5233.8  173.07    5248  174.76  5389.2  177.22  5410.9  179.28  5417.6  178.86
  5453.5  184.66  5460.2  187.17  5496.1  187.75    5537     190  5554.4  190.65
#Mann= 6 ,-1 , 0
  4233.3     .04       0  4326.1     .12       0  4941.8     .05       0
  4945.8     .12       0  5022.3     .03       0    5537     .12       0
#XS Ineff= 2 , 0
       0                    5020       0     175
Permanent Ineff=
       F       F
Bank Sta=4941.8,4945.8
XS Rating Curve= 0 ,0
Exp/Cntr=0.3,0.1

Type RM Length L Ch R = 1 ,913     ,195,195,195
BEGIN DESCRIPTION:
4897
END DESCRIPTION:
XS GIS Cut Line= 5
      2568355.11     13556381.25      2568586.01     13556542.71
      2568660.66      13556681.6      2568792.61     13556790.97
      2569121.26     13556995.09
#Sta/Elev= 30
  4519.4  182.34  4627.2  177.26  4744.5  172.04  4825.7  171.95  4925.8  168.45
  4971.5  167.08  5028.8  167.77  5042.4  162.47  5047.6  162.01  5047.9  161.51
  5051.6  162.01  5070.4   169.6  5078.3  170.27  5185.6  171.17  5250.8  169.78
  5258.8  171.25  5301.3  171.07  5316.7  174.84  5322.6  172.16  5332.1  174.36
    5338  172.17  5353.3  176.22  5359.2  174.91  5389.9  176.35  5395.8  175.16
  5426.5  177.31  5432.4  176.18  5453.7  180.58    5469  187.06  5517.1  188.57
#Mann= 5 ,-1 , 0
  4519.4     .05       0  4627.2     .12       0  4925.8     .03       0
  5047.6     .03       0  5051.6     .03       0
Bank Sta=5047.6,5051.6
XS Rating Curve= 0 ,0
Exp/Cntr=0.3,0.1

Type RM Length L Ch R = 1 ,718     ,333,333,333
BEGIN DESCRIPTION:
LGII3158
END DESCRIPTION:
XS GIS Cut Line= 3
      2568019.05     13556385.93      2568715.07     13556926.81
      2569213.72     13557220.14
#Sta/Elev= 30
    4327  186.95  4386.8   184.9  4391.7  184.75  4614.2  179.01  4838.8  169.04
  4929.8  167.26  4950.8   165.2  4966.6  160.98  4969.7  160.93  4969.9  160.43
  4973.7  160.93  4979.8  162.36    5007  162.13  5029.6  164.74  5050.4  163.09
  5085.7  162.83  5129.1  169.84  5145.2  170.22  5454.6  170.87  5528.9   176.8
  5544.6  179.72    5559  185.55  5587.5  187.28  5608.9  187.08  5614.7  185.75
  5624.6  186.42  5630.4  189.04  5637.7  190.02  5673.3  190.32    5787  195.99
#Mann= 9 ,-1 , 0
    4327     .05       0  4386.8     .03       0  4391.7     .05       0
  4614.2     .12       0  4966.6     .05       0  4969.7     .05       0
  4973.7     .05       0  5145.2     .03       0    5559     .12       0
Bank Sta=4969.7,4973.7
XS Rating Curve= 0 ,0
Exp/Cntr=0.3,0.1

Type RM Length L Ch R = 1 ,385     ,256,256,256
BEGIN DESCRIPTION:
LGII3157
END DESCRIPTION:
XS GIS Cut Line= 3
      2567918.43     13556528.51      2568593.47     13557157.42
      2569120.86     13557446.23
#Sta/Elev= 30
  4184.9  180.34  4388.2  174.57  4467.7  172.14  4598.7  168.65  4703.5  164.83
  4821.9  162.92  4901.8  162.83  4991.7  158.76  4998.5  157.04  4998.8  156.54
  5002.5  157.04  5014.7  157.44    5022  161.03  5036.2  161.79  5125.4   162.8
  5304.5  164.64  5467.6  169.72  5511.2  172.38  5542.5  175.97  5549.1  177.69
    5571  178.29  5587.1  181.76  5592.8  181.27  5608.9  183.84  5614.6  182.95
  5624.8  184.84  5636.4   184.7  5652.5  188.23  5674.3   191.1  5708.8  193.54
#Mann= 10 ,-1 , 0
  4184.9     .05       0  4388.2     .12       0  4467.7      .1       0
  4598.7     .05       0  4821.9     .12       0  4991.7     .05       0
  4998.5     .05       0  5002.5     .05       0  5125.4     .12       0
  5624.8     .05       0
Bank Sta=4998.5,5002.5
XS Rating Curve= 0 ,0
Exp/Cntr=0.3,0.1

Type RM Length L Ch R = 1 ,129     ,0,0,0
BEGIN DESCRIPTION:
LGII3156
END DESCRIPTION:
XS GIS Cut Line= 4
      2567884.87      13556637.5      2568149.02     13557086.14
      2568530.58     13557434.16      2569161.89     13557647.38
#Sta/Elev= 30
  4185.7  175.93  4447.2  166.92  4679.8  160.73  4791.5  160.41  4848.7  160.36
  4893.6  159.84  4916.8  156.65  4929.4  155.55  4934.2   153.3  4934.4   152.8
  4938.2   153.3  4943.6   155.8  4950.4  153.49  4957.8  155.82  4971.6  153.63
  4992.9  154.28  4999.7  157.87  5063.9  160.51  5148.3  160.75  5176.7  158.17
  5198.3  159.53  5205.1  158.33  5222.4  160.96  5533.5   165.1  5691.8  174.09
  5708.7  178.48  5776.9  177.05  5786.8  178.29  5797.4  183.47  5889.1   191.3
#Mann= 8 ,-1 , 0
  4185.7     .05       0  4447.2      .1       0  4679.8     .05       0
  4791.5     .12       0  4848.7     .05       0  4916.8     .12       0
  4934.2     .05       0  4938.2     .12       0
Bank Sta=4934.2,4938.2
XS Rating Curve= 0 ,0
Exp/Cntr=0.3,0.1

Chan Stop Cuts=-1
Use User Specified Reach Order=0
Composite Channel Slope=5