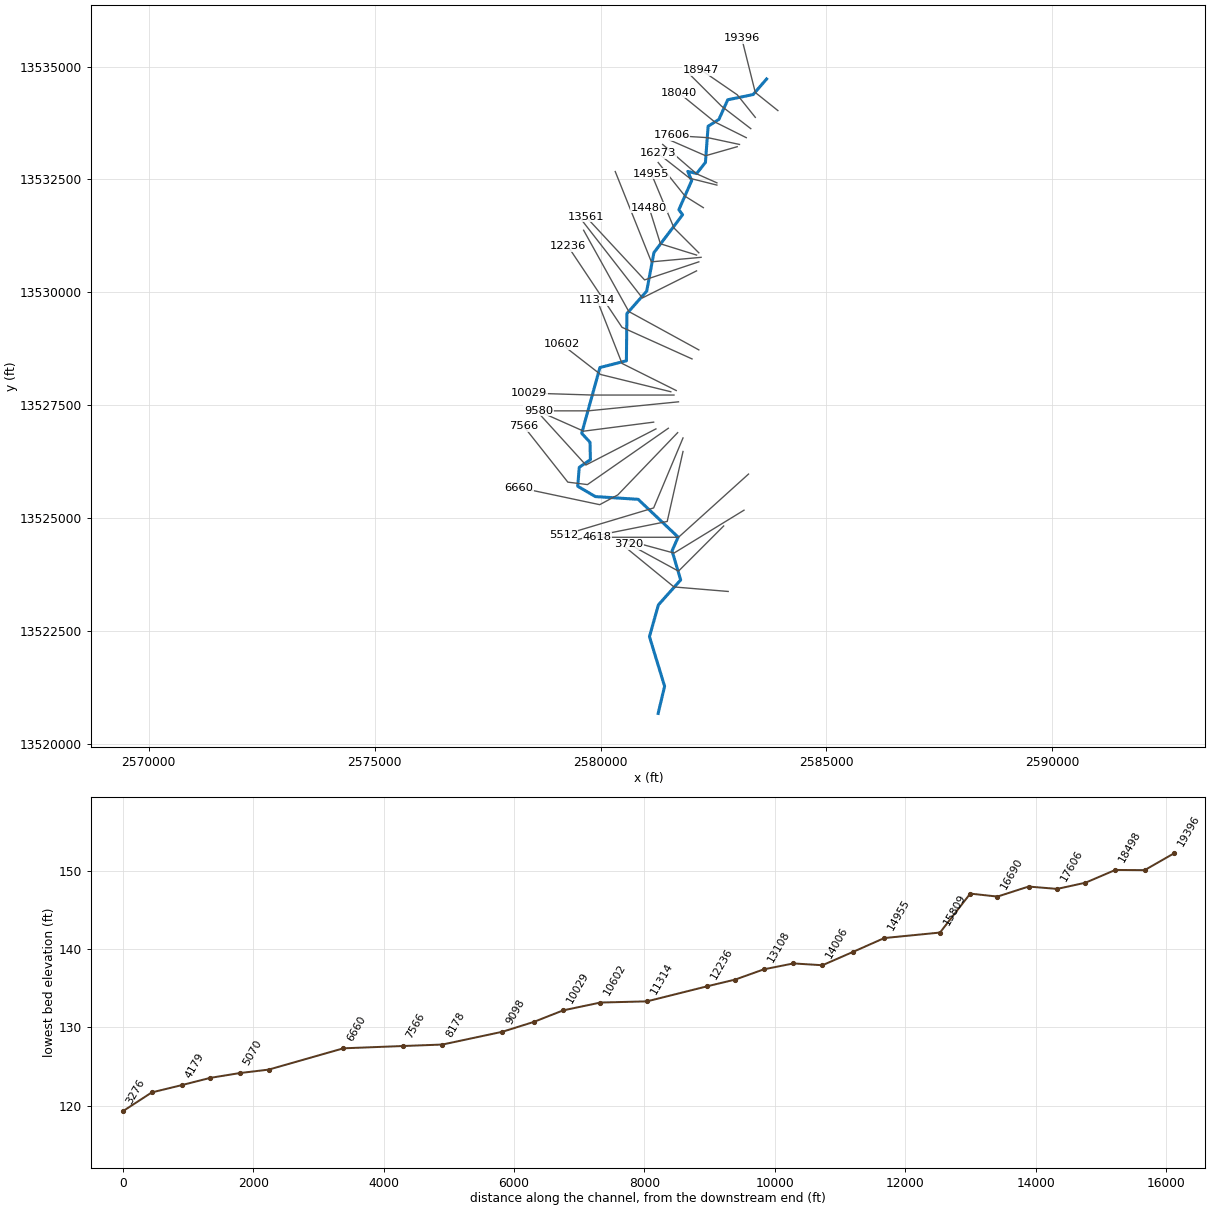
--- TRIB 8 TO SPRING CREEK.prj (project) ---

Proj Title=TRIB 8 TO SPRING CREEK Base Level Engineering
Current Plan=p01
Default Exp/Contr=0.3,0.1
English Units
Geom File=g01
Flow File=f01
Plan File=p01
Y Axis Title=Elevation
X Axis Title(PF)=Main Channel Distance
X Axis Title(XS)=Station
BEGIN DESCRIPTION:
TRIB 8 TO SPRING CREEK
END DESCRIPTION:
DSS Export Rating Curves= 0
DSS Export Rating Curve Sorted= 0
DSS Export Volume Flow Curves= 0
DXF OffsetX= 0
DXF OffsetY= 0
DXF ScaleX= 1
DXF ScaleY= 10

--- TRIB 8 TO SPRING CREEK.p01 (plan) ---

Plan Title=Multiple Run
Short Identifier=Multiple
Geom File=g01
Flow File=f01
Subcritical Flow
K Sum by GR= 0
Std Step Tol= 0.01
Critical Tol= 0.01
Num of Std Step Trials= 20
Max Error Tol= 0.3
Flow Tol Ratio= 0.001
Split Flow NTrial= 30
Split Flow Tol= 0.02
Split Flow Ratio= 0.02
Log Output Level= 0
Friction Slope Method= 1
Unsteady Friction Slope Method= 2
Unsteady Bridges Friction Slope Method= 1
Parabolic Critical Depth
Global Vel Dist=  1 , 1 , 1
Global Log Level= 0
CheckData=True
Encroach Param= -1, 0, 0, 0
BEGIN DESCRIPTION:
Multiple Run
END DESCRIPTION:

--- TRIB 8 TO SPRING CREEK.f01 (steady flow) ---

Flow Title=Multiple
Number of Profiles=7
Profile Names=10-year,25-year,50-year,1pct_min,100-year,1pct_plu,500-year
River Rch & RM= TRIB 8 TO SPRING,Reach-1,19396
     965    1539    2051    1319    2632    5252    4286
River Rch & RM= TRIB 8 TO SPRING,Reach-1,14480
    1151    1849    2476    1599    3191    6368    5242
River Rch & RM= TRIB 8 TO SPRING,Reach-1,10029
    1291    2085    2799    1813    3617    7216    5970
River Rch & RM= TRIB 8 TO SPRING,Reach-1,5070
    4119    6959    9637    6413   12797   25533   22315
Boundary for River Rch & Prof#=TRIB 8 TO SPRING,Reach-1,1
Up Type=0
Dn Type=3
Dn Slope=0.005
Boundary for River Rch & Prof#=TRIB 8 TO SPRING,Reach-1,2
Up Type=0
Dn Type=3
Dn Slope=0.005
Boundary for River Rch & Prof#=TRIB 8 TO SPRING,Reach-1,3
Up Type=0
Dn Type=3
Dn Slope=0.005
Boundary for River Rch & Prof#=TRIB 8 TO SPRING,Reach-1,4
Up Type=0
Dn Type=3
Dn Slope=0.005
Boundary for River Rch & Prof#=TRIB 8 TO SPRING,Reach-1,5
Up Type=0
Dn Type=3
Dn Slope=0.005
Boundary for River Rch & Prof#=TRIB 8 TO SPRING,Reach-1,6
Up Type=0
Dn Type=3
Dn Slope=0.005
Boundary for River Rch & Prof#=TRIB 8 TO SPRING,Reach-1,7
Up Type=0
Dn Type=3
Dn Slope=0.005

--- TRIB 8 TO SPRING CREEK.g01 (geometry) ---

Geom Title=Existing Conditions
Program Version=4.10

River Reach=TRIB 8 TO SPRING,Reach-1
Reach XY= 30
        2583675.       13534725.       2583377.3     13534380.09
      2582815.21     13534264.48      2582619.75     13533830.44
      2582380.45     13533677.47      2582321.25     13532876.55
      2582127.29     13532630.07       2581930.4       13532678.
      2582017.67      13532475.1      2581732.61     13531828.33
      2581816.03     13531718.33      2581180.52     13530877.43
      2581021.53      13530026.5      2580583.01     13529528.33
      2580571.93     13528483.25      2579986.23     13528335.02
      2579582.87     13526878.21      2579767.21     13526678.42
      2579775.06     13526294.98      2579528.54     13526123.56
      2579494.37       13525705.       2579885.5     13525476.22
      2580831.66     13525415.69      2581717.02     13524578.33
      2581582.09       13524275.      2581773.01     13523630.68
      2581280.11     13523077.29      2581082.33      13522375.1
      2581417.44       13521275.        2581275.       13520675.

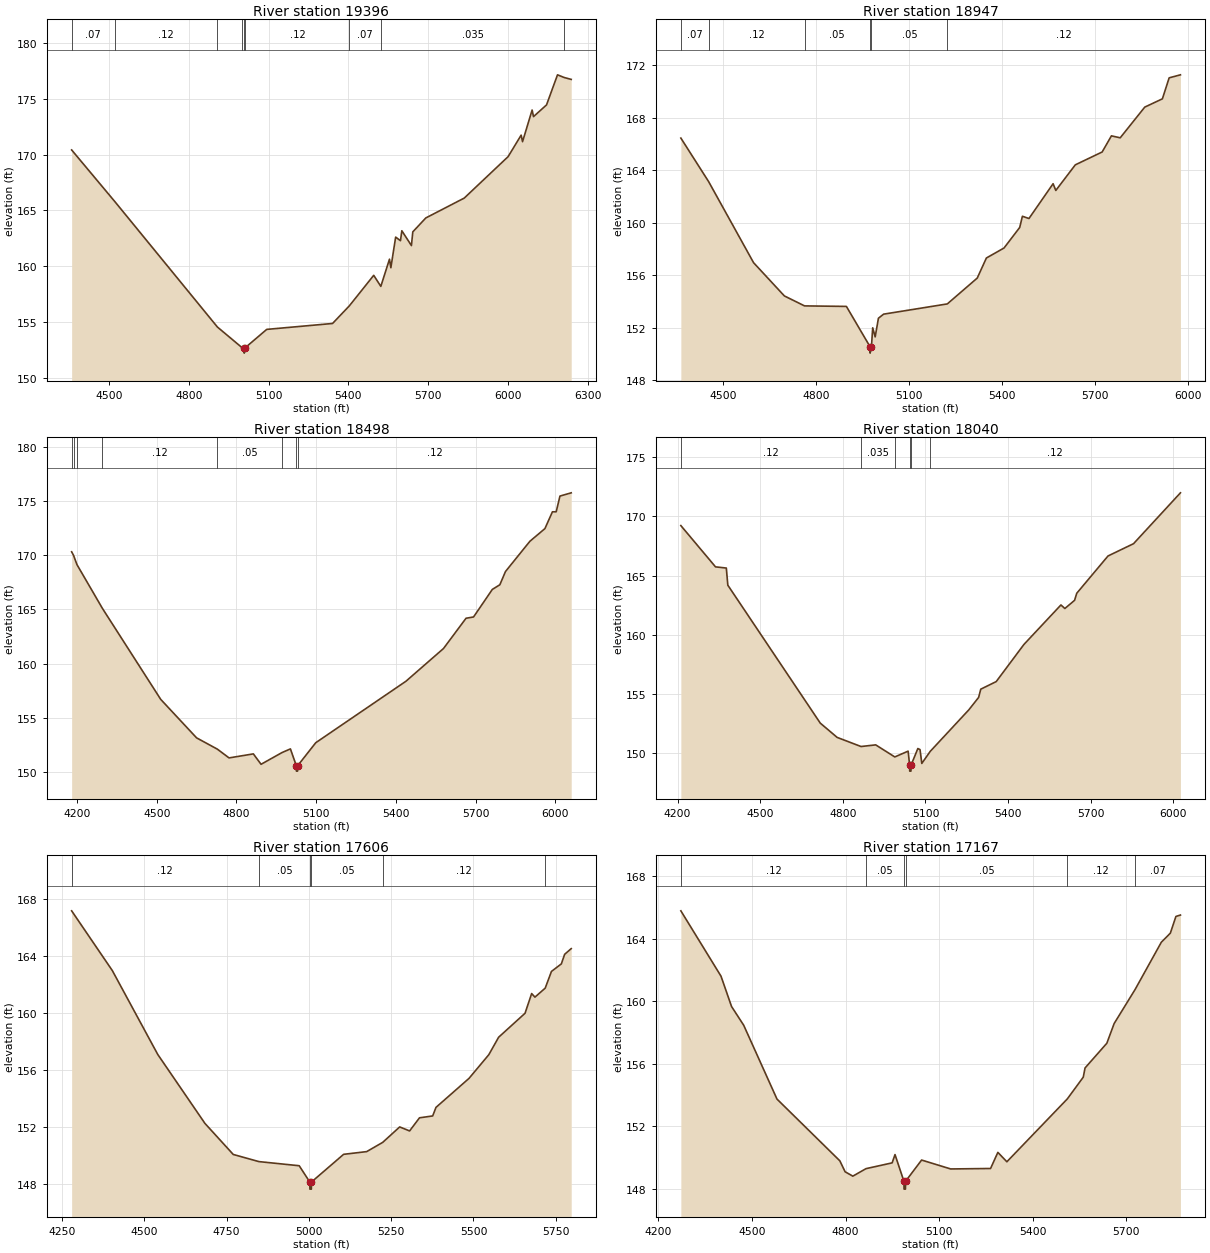
Type RM Length L Ch R = 1 ,19396   ,449,449,449
BEGIN DESCRIPTION:
TRIB 8 TO SPRING CREEK 33.0
END DESCRIPTION:
XS GIS Cut Line= 3
      2583924.98     13534025.02        2583425.       13534425.
        2583125.     13535624.98
#Sta/Elev= 30
    4360  170.43  4521.5  165.82  4907.8  154.54  4999.4  152.71  5008.2   152.7
  5008.5   152.2    5013   152.7  5093.1  154.33  5340.4  154.86  5403.4  156.44
  5495.1  159.18  5521.8  158.19  5554.3  160.63  5559.5  159.86  5577.5  162.61
  5595.6  162.29  5600.7  163.18  5636.8  161.85  5641.9  163.08  5690.9  164.33
  5835.2  166.11  6000.1  169.83  6049.1  171.76  6054.3  171.17  6090.3  174.01
  6095.5  173.42  6144.4  174.47  6185.7  177.17  6210.6  176.93  6237.2  176.76
#Mann= 9 ,-1 , 0
    4360     .07       0  4521.5     .12       0  4907.8     .07       0
  4999.4     .12       0  5008.2     .05       0    5013     .12       0
  5403.4     .07       0  5521.8    .035       0  6210.6     .07       0
Bank Sta=5008.2,5013
XS Rating Curve= 0 ,0
Exp/Cntr=0.3,0.1

Type RM Length L Ch R = 1 ,18947   ,449,449,449
BEGIN DESCRIPTION:
TRIB 8 TO SPRING CREEK 32.0
END DESCRIPTION:
XS GIS Cut Line= 3
      2583425.03     13533874.97        2583025.       13534375.
      2582224.98     13534925.01
#Sta/Elev= 30
  4364.2  166.45  4453.8  163.13  4598.8  156.95    4698  154.42  4763.1  153.66
  4898.1  153.62  4974.1  150.56  4974.5  150.06  4978.9  150.56  4982.9  151.99
  4990.9   151.3  5001.4  152.72  5018.1  153.03  5223.5  153.81  5320.1  155.78
  5349.6  157.31  5406.4  158.07  5457.1  159.64  5465.7  160.49  5486.9  160.32
  5564.7  162.97  5573.5  162.46  5636.4  164.41    5723  165.39  5752.8  166.62
  5781.2  166.47  5860.4  168.81  5917.2  169.44    5939  171.04  5975.4  171.27
#Mann= 6 ,-1 , 0
  4364.2     .07       0  4453.8     .12       0  4763.1     .05       0
  4974.1     .05       0  4978.9     .05       0  5223.5     .12       0
Bank Sta=4974.1,4978.9
XS Rating Curve= 0 ,0
Exp/Cntr=0.3,0.1

Type RM Length L Ch R = 1 ,18498   ,458,458,458
BEGIN DESCRIPTION:
TRIB 8 TO SPRING CREEK 31.0
END DESCRIPTION:
XS GIS Cut Line= 3
      2583324.99     13533625.01        2582675.       13534125.
      2581925.01     13534874.99
#Sta/Elev= 30
  4179.6  170.32  4186.8  169.99  4199.6  169.14  4295.2  165.11  4514.9  156.71
  4649.9  153.16    4728  152.12  4772.2  151.31  4863.7  151.68  4892.7  150.72
  4971.4   151.8  5003.2  152.14  5025.4  150.59  5025.8  150.09  5030.1  150.09
  5030.5  150.59  5098.6  152.71  5438.1  158.38  5579.5   161.4  5664.3  164.19
  5692.6  164.31  5763.3  166.85  5791.6  167.28  5812.8   168.5  5904.7  171.29
  5961.3  172.46  5989.6  174.01  6003.7  174.01  6017.9  175.46  6060.3  175.76
#Mann= 8 ,-1 , 0
  4179.6     .07       0  4186.8     .12       0  4199.6     .07       0
  4295.2     .12       0    4728     .05       0  4971.4     .12       0
  5025.4     .05       0  5030.5     .12       0
Bank Sta=5025.4,5030.5
XS Rating Curve= 0 ,0
Exp/Cntr=0.3,0.1

Type RM Length L Ch R = 1 ,18040   ,434,434,434
BEGIN DESCRIPTION:
TRIB 8 TO SPRING CREEK 30.0
END DESCRIPTION:
XS GIS Cut Line= 3
      2583225.04     13533424.98        2582525.       13533775.
      2581725.03     13534424.97
#Sta/Elev= 30
    4212  169.22  4337.8  165.73    4377  165.63  4382.5  164.18    4718  152.52
  4779.4  151.31  4866.1  150.54  4919.2  150.68  4988.6  149.66    5037  150.15
  5042.4  148.96  5042.8  148.46  5047.2  148.46  5047.6  148.96  5072.2  150.37
  5080.2  150.28  5086.6  149.11  5117.2  150.13  5257.6  153.65  5292.8  154.69
  5300.7  155.39  5356.7  156.03  5457.3  159.17  5591.6  162.51  5605.9  162.21
  5641.1   162.9  5649.1   163.5  5762.5  166.65  5855.2  167.69  6025.4  171.99
#Mann= 6 ,-1 , 0
    4212     .12       0  4866.1    .035       0  4988.6     .12       0
  5042.4     .05       0  5047.6     .12       0  5117.2     .12       0
Bank Sta=5042.4,5047.6
XS Rating Curve= 0 ,0
Exp/Cntr=0.3,0.1

Type RM Length L Ch R = 1 ,17606   ,439,439,439
BEGIN DESCRIPTION:
TRIB 8 TO SPRING CREEK 29.0
END DESCRIPTION:
XS GIS Cut Line= 3
        2583075.       13533275.        2582375.       13533425.
      2581575.05       13533475.
#Sta/Elev= 30
  4279.5  167.18  4403.1  162.99  4541.1  157.11  4684.3  152.28  4770.4   150.1
  4848.2   149.6  4970.7  149.31  5002.8  148.17  5003.2  147.67  5007.6  147.67
    5008  148.17  5105.6  150.11  5175.7   150.3  5224.5  150.95  5275.9  152.03
    5306  151.75  5336.1  152.67  5376.1   152.8  5386.1   153.4  5486.3  155.43
  5546.5  157.09  5576.5  158.32  5656.7     160  5676.7  161.38  5686.7  161.13
  5717.9  161.76  5736.8  162.93  5766.9  163.46  5776.9  164.13  5796.9  164.53
#Mann= 6 ,-1 , 0
  4279.5     .12       0  4848.2     .05       0  5002.8     .05       0
    5008     .05       0  5224.5     .12       0  5717.9     .07       0
Bank Sta=5002.8,5008
XS Rating Curve= 0 ,0
Exp/Cntr=0.3,0.1

Type RM Length L Ch R = 1 ,17167   ,477,477,477
BEGIN DESCRIPTION:
TRIB 8 TO SPRING CREEK 28.0
END DESCRIPTION:
XS GIS Cut Line= 3
      2583025.03     13533225.01        2582325.       13533025.
      2581524.95     13533375.02
#Sta/Elev= 30
    4272  165.77  4400.7  161.59  4434.5  159.65  4473.5  158.45  4580.1  153.73
  4781.6  149.78  4798.5  149.08  4823.2   148.8  4865.6  149.28  4949.3  149.65
  4958.4  150.18    4987  148.47  4987.4  147.97  4991.8  147.97  4992.2  148.47
  5043.7  149.83  5136.9  149.26  5264.7  149.29  5288.1  150.32    5317  149.72
  5510.7  153.74  5561.8  155.13  5567.6  155.72  5637.4   157.3  5660.8  158.56
    5728  160.74    5812  163.76  5840.9  164.34  5858.8  165.41  5873.3   165.5
#Mann= 6 ,-1 , 0
    4272     .12       0  4865.6     .05       0    4987     .05       0
  4992.2     .05       0  5510.7     .12       0    5728     .07       0
Bank Sta=4987,4992.2
XS Rating Curve= 0 ,0
Exp/Cntr=0.3,0.1

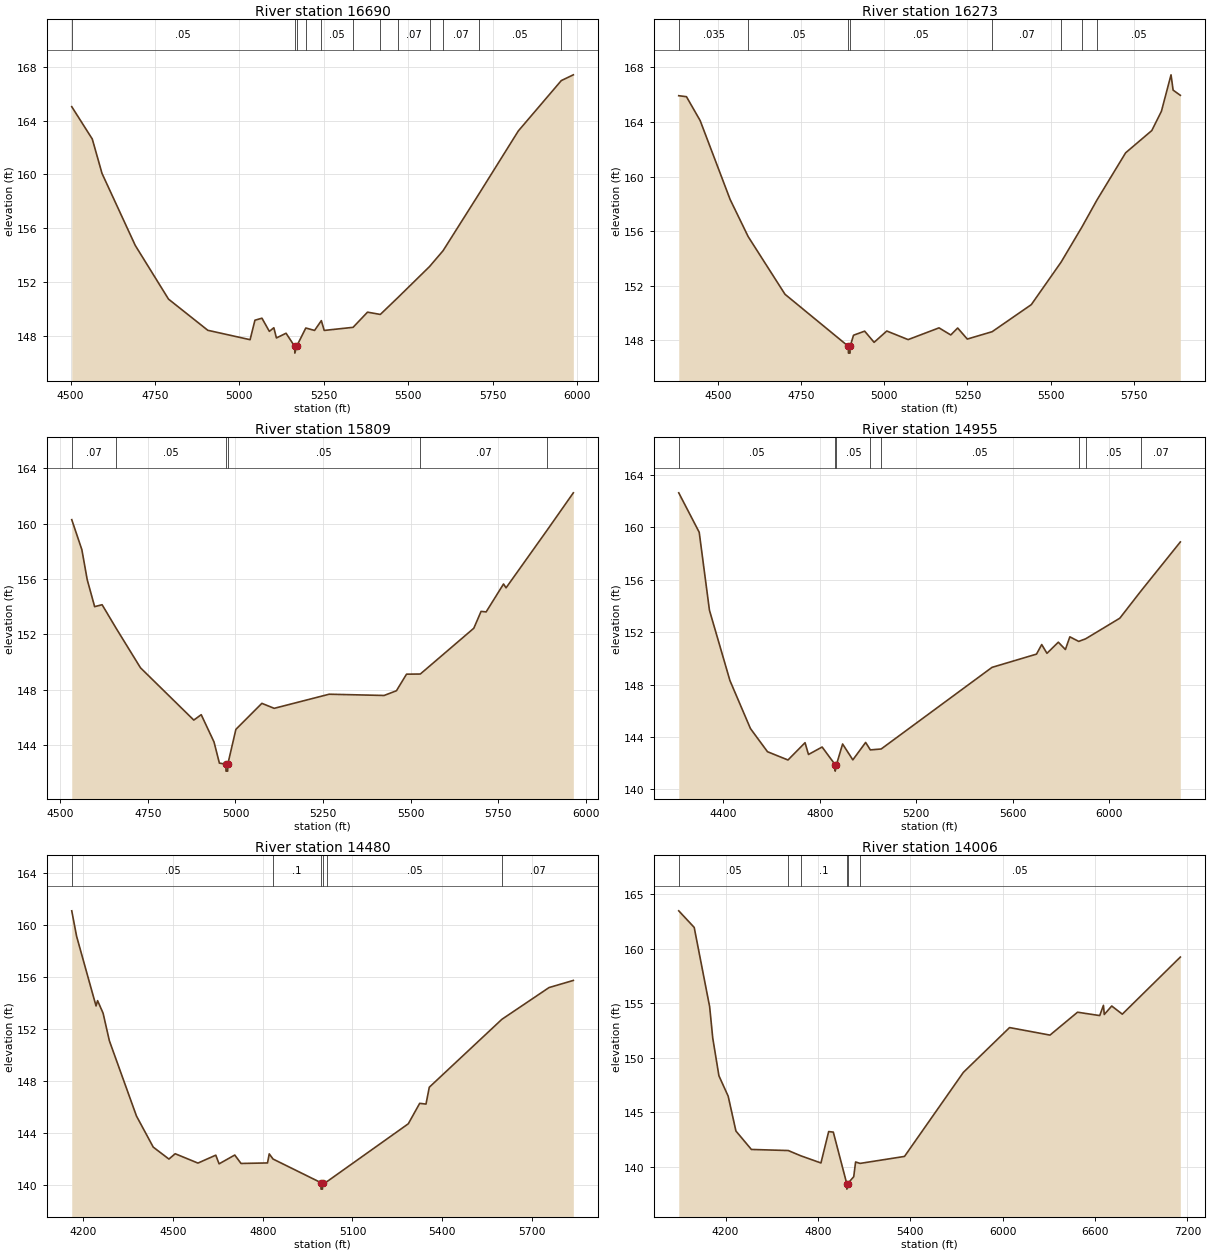
Type RM Length L Ch R = 1 ,16690   ,417,417,417
BEGIN DESCRIPTION:
TRIB 8 TO SPRING CREEK 27.0
END DESCRIPTION:
XS GIS Cut Line= 3
      2582574.96     13532425.02        2582125.       13532625.
      2581374.98     13533275.02
#Sta/Elev= 30
  4503.6  165.04  4564.4  162.63  4593.2  160.07  4691.6  154.71  4790.1  150.71
  4906.4  148.39  5031.6  147.69  5045.9  149.14  5066.7  149.29  5088.6  148.31
  5101.9  148.58  5109.5  147.82    5138  148.17  5163.7  147.19  5164.1  146.69
  5169.2  147.19  5196.5  148.56  5222.5  148.38  5242.5  149.11    5251  148.38
  5336.4  148.61  5379.2  149.74  5417.1  149.57  5469.7  150.84    5563  153.14
    5603  154.32  5708.8  158.53  5825.6  163.23  5952.8  166.98  5988.5  167.41
#Mann= 12 ,-1 , 0
  4503.6     .05       0  5163.7     .05       0  5169.2     .05       0
  5196.5     .07       0  5242.5     .05       0  5336.4     .07       0
  5417.1     .05       0  5469.7     .07       0    5563     .05       0
    5603     .07       0  5708.8     .05       0  5952.8     .07       0
Bank Sta=5163.7,5169.2
XS Rating Curve= 0 ,0
Exp/Cntr=0.3,0.1

Type RM Length L Ch R = 1 ,16273   ,464,464,464
BEGIN DESCRIPTION:
TRIB 8 TO SPRING CREEK 26.0
END DESCRIPTION:
XS GIS Cut Line= 3
      2582575.01       13532375.        2581975.       13532525.
        2581275.       13533075.
#Sta/Elev= 30
  4381.7  165.92  4404.9  165.85  4446.1   164.1  4536.3  158.32  4590.6   155.6
  4701.3  151.38  4891.8  147.57  4892.2  147.07  4896.9  147.07  4897.3  147.57
  4907.4  148.38  4940.9  148.68  4969.3  147.86  5007.4  148.69  5071.6  148.06
  5164.6  148.92  5199.9   148.4  5220.7  148.91  5249.6   148.1  5324.4  148.64
  5442.1  150.62  5531.9  153.74    5595  156.33  5639.3  158.27  5725.9  161.74
  5804.6  163.37  5833.5  164.78  5862.4  167.45  5868.7  166.33  5890.4  165.95
#Mann= 8 ,-1 , 0
  4381.7    .035       0  4590.6     .05       0  4891.8     .05       0
  4897.3     .05       0  5324.4     .07       0  5531.9     .05       0
    5595     .07       0  5639.3     .05       0
Bank Sta=4891.8,4897.3
XS Rating Curve= 0 ,0
Exp/Cntr=0.3,0.1

Type RM Length L Ch R = 1 ,15809   ,854,854,854
BEGIN DESCRIPTION:
TRIB 8 TO SPRING CREEK 25.0
END DESCRIPTION:
XS GIS Cut Line= 3
        2582275.       13531875.        2581875.       13532125.
      2581274.98     13532875.03
#Sta/Elev= 30
  4532.5  160.28  4561.4  158.11  4576.7  155.94  4597.9  153.99  4619.2  154.13
  4659.7  152.41  4728.8  149.57    4881  145.79  4902.2  146.18  4938.7  144.21
  4954.1  142.68  4972.5   142.6    4973   142.1  4977.7   142.1  4978.1   142.6
  5001.2  145.12  5075.4     147  5110.6  146.64  5267.5  147.66  5424.4  147.57
  5459.6  147.91  5488.4  149.11  5527.8  149.12  5680.5  152.43  5701.3  153.65
  5715.7  153.61  5765.4  155.63  5772.6  155.35  5890.7  159.55  5964.7  162.22
#Mann= 6 ,-1 , 0
  4532.5     .07       0  4659.7     .05       0  4972.5     .05       0
  4978.1     .05       0  5527.8     .07       0  5890.7     .05       0
Bank Sta=4972.5,4978.1
XS Rating Curve= 0 ,0
Exp/Cntr=0.3,0.1

Type RM Length L Ch R = 1 ,14955   ,475,475,475
BEGIN DESCRIPTION:
TRIB 8 TO SPRING CREEK 24.0
END DESCRIPTION:
XS GIS Cut Line= 3
      2582174.98     13530875.02        2581625.       13531425.
      2581124.99     13532625.01
#Sta/Elev= 30
  4215.7  162.64  4300.5  159.63  4342.9  153.68  4427.8  148.31  4512.7  144.65
  4583.4  142.88  4668.2  142.25  4738.9  143.57  4753.1  142.67  4809.6  143.24
  4863.3   141.9  4863.8   141.4  4869.1   141.9  4894.5  143.47  4936.9  142.26
  4989.9  143.59  5009.4  143.02  5054.3  143.09  5513.5  149.32  5697.7  150.33
  5719.3  151.06    5741  150.39  5788.1  151.24  5817.4  150.68  5835.8  151.65
  5872.6   151.3  5901.4   151.5  6042.7  153.07  6130.9  155.16  6293.5  158.89
#Mann= 8 ,-1 , 0
  4215.7     .05       0  4863.3     .05       0  4869.1     .05       0
  5009.4      .1       0  5054.3     .05       0  5872.6     .07       0
  5901.4     .05       0  6130.9     .07       0
Bank Sta=4863.3,4869.1
XS Rating Curve= 0 ,0
Exp/Cntr=0.3,0.1

Type RM Length L Ch R = 1 ,14480   ,474,474,474
BEGIN DESCRIPTION:
TRIB 8 TO SPRING CREEK 23.0
END DESCRIPTION:
XS GIS Cut Line= 3
      2582124.99       13530825.        2581325.       13531075.
        2581075.       13531875.
#Sta/Elev= 30
  4161.8  161.12    4178  159.16    4243  153.78  4248.2  154.19  4266.6  153.22
  4287.5   151.1  4378.1  145.29  4434.2  142.89  4486.6  141.97  4507.5  142.38
  4583.5  141.66  4643.2  142.27  4654.2   141.6  4706.6  142.28  4727.5  141.63
  4816.1  141.67  4821.8  142.37  4834.6  141.97  4994.4  140.15  4994.9  139.65
  4999.7  139.65  5000.2  140.15  5015.4  140.24  5286.5  144.69  5324.7  146.27
  5345.7  146.21  5356.7  147.51  5599.3  152.75  5756.9   155.2  5838.1  155.75
#Mann= 6 ,-1 , 0
  4161.8     .05       0  4834.6      .1       0  4994.4     .05       0
  5000.2      .1       0  5015.4     .05       0  5599.3     .07       0
Bank Sta=4994.4,5000.2
XS Rating Curve= 0 ,0
Exp/Cntr=0.3,0.1

Type RM Length L Ch R = 1 ,14006   ,445,445,445
BEGIN DESCRIPTION:
TRIB 8 TO SPRING CREEK 22.0
END DESCRIPTION:
XS GIS Cut Line= 3
      2582224.96       13530775.        2581125.       13530675.
      2580324.99     13532675.03
#Sta/Elev= 30
  3895.5  163.46  3995.9  161.94  4096.3  154.66  4116.4  151.79  4156.5  148.33
  4216.8  146.45    4267  143.26  4367.4  141.57    4607  141.47    4688  140.99
  4819.3  140.33  4869.5  143.21  4899.6  143.16  4987.1  138.43  4987.5  137.93
  4992.9  138.43  5032.3  139.07  5044.4  140.42  5073.8  140.29  5362.2  140.93
  5744.5  148.64  6044.7  152.75  6307.2  152.06  6486.3  154.16  6630.4  153.85
  6654.6  154.79    6660  153.95  6708.4  154.73  6777.1  153.98  7154.1  159.22
#Mann= 6 ,-1 , 0
  3895.5     .05       0    4607     .07       0    4688      .1       0
  4987.1     .05       0  4992.9      .1       0  5073.8     .05       0
Bank Sta=4987.1,4992.9
XS Rating Curve= 0 ,0
Exp/Cntr=0.3,0.1

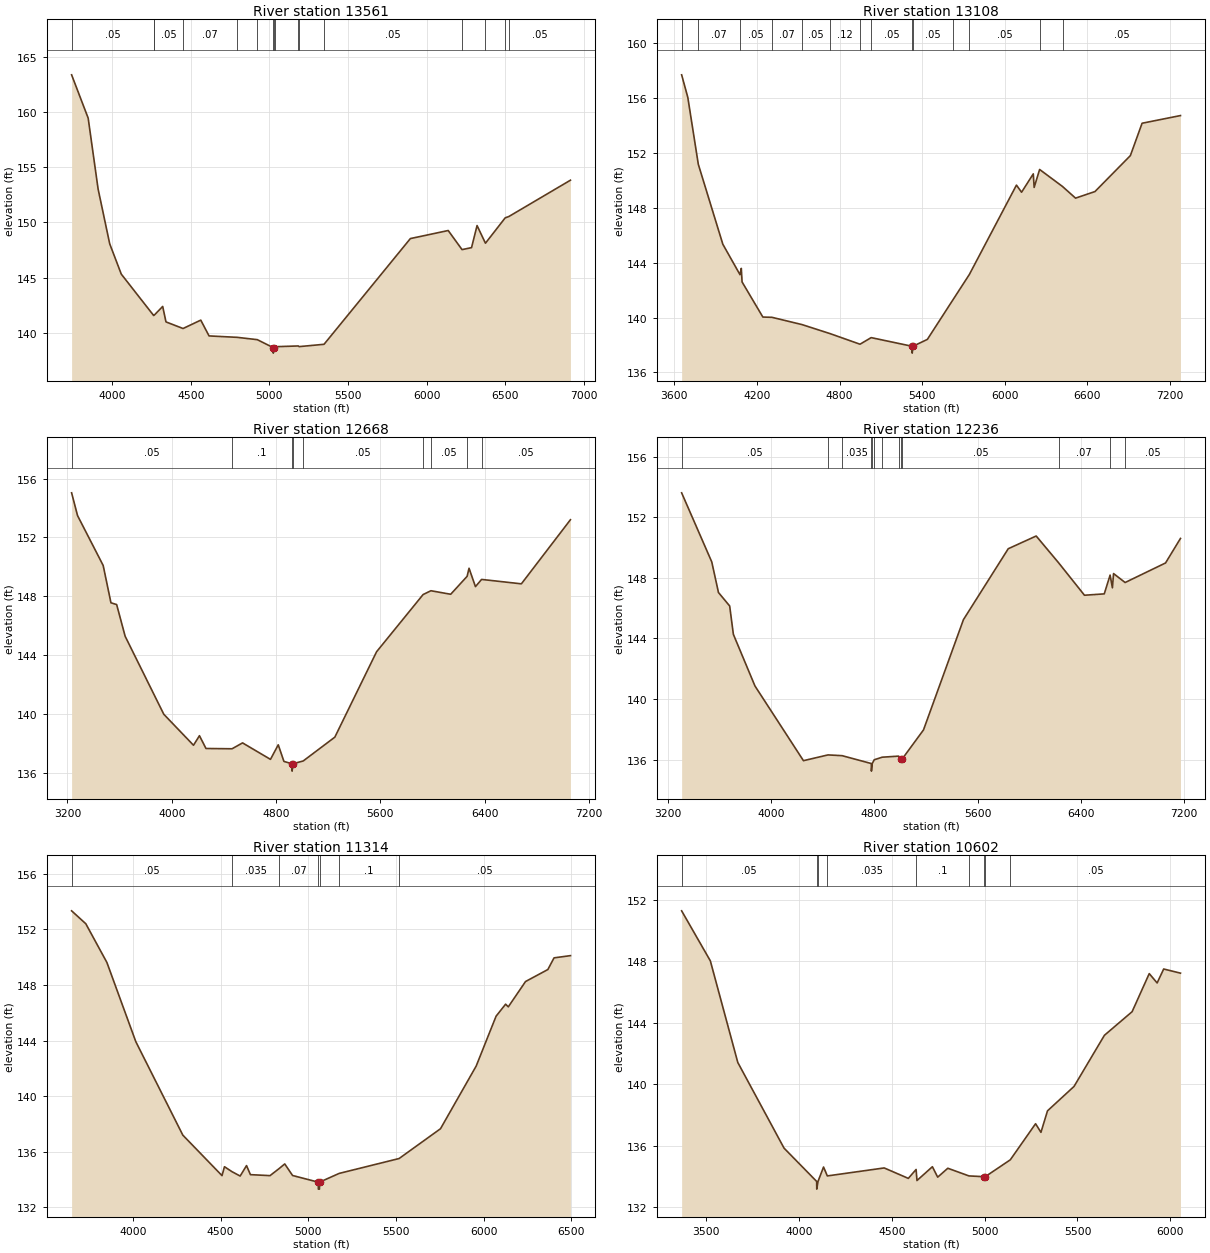
Type RM Length L Ch R = 1 ,13561   ,453,453,453
BEGIN DESCRIPTION:
TRIB 8 TO SPRING CREEK 21.0
END DESCRIPTION:
XS GIS Cut Line= 3
      2582175.01       13530675.        2580975.       13530275.
      2579675.01     13531674.99
#Sta/Elev= 30
  3740.8  163.38  3846.2  159.46  3909.5  153.03  3983.3  148.07    4057  145.32
  4263.1  141.57  4267.4  141.61  4320.6  142.39  4341.6  140.99  4450.2  140.39
    4563  141.15  4615.7  139.72    4795  139.59  4922.9  139.38  5024.1  138.66
  5024.5  138.16  5029.9  138.66  5034.6  138.74  5183.5  138.81  5189.6  138.75
  5347.7  138.96  5897.2  148.54  6138.1  149.27  6226.2  147.54  6286.6  147.72
  6321.8  149.72  6375.2  148.12    6501  150.42  6524.2  150.54  6916.2  153.83
#Mann= 16 ,-1 , 0
  3740.8     .05       0  4263.1     .07       0  4267.4     .05       0
  4450.2     .07       0    4795     .12       0  4922.9     .05       0
  5024.1     .05       0  5029.9     .05       0  5034.6      .1       0
  5183.5     .05       0  5189.6      .1       0  5347.7     .05       0
  6226.2    .035       0  6375.2     .05       0    6501    .035       0
  6524.2     .05       0
Bank Sta=5024.1,5029.9
XS Rating Curve= 0 ,0
Exp/Cntr=0.3,0.1

Type RM Length L Ch R = 1 ,13108   ,440,440,440
BEGIN DESCRIPTION:
TRIB 8 TO SPRING CREEK 20.0
END DESCRIPTION:
XS GIS Cut Line= 3
      2582124.99     13530474.99        2580925.       13529875.
      2579524.99     13531675.02
#Sta/Elev= 30
  3653.2   157.7  3697.9  156.06  3774.2  151.18  3952.3  145.35  4076.9  143.13
  4086.4  143.59    4092   142.6  4242.9  140.04  4309.1  140.02  4527.4  139.49
  4731.6  138.83  4948.4  138.06  5029.4  138.54  5326.7  137.91  5327.2  137.41
  5332.6  137.91  5437.3  138.41    5624  141.31  5742.1  143.14  6084.3  149.66
  6121.4  149.14  6206.5  150.48  6212.8  149.49  6252.5   150.8  6418.6  149.56
  6513.3  148.71  6654.4  149.19  6911.4  151.81  6996.5  154.17  7275.2  154.73
#Mann= 14 ,-1 , 0
  3653.2     .05       0  3774.2     .07       0  4076.9     .05       0
  4309.1     .07       0  4527.4     .05       0  4731.6     .12       0
  4948.4      .1       0  5029.4     .05       0  5326.7     .05       0
  5332.6     .05       0    5624     .07       0  5742.1     .05       0
  6252.5    .035       0  6418.6     .05       0
Bank Sta=5326.7,5332.6
XS Rating Curve= 0 ,0
Exp/Cntr=0.3,0.1

Type RM Length L Ch R = 1 ,12668   ,432,432,432
BEGIN DESCRIPTION:
TRIB 8 TO SPRING CREEK 19.0
END DESCRIPTION:
XS GIS Cut Line= 3
      2582174.98     13528725.01        2580625.       13529575.
      2579624.98     13531375.03
#Sta/Elev= 30
  3232.1  155.03  3277.7  153.48  3474.3  150.09    3534  147.55  3577.6  147.43
    3643  145.27  3939.2  139.97  4167.3  137.86  4212.9  138.51  4262.9  137.64
  4462.9  137.62  4543.6  138.02  4757.7   136.9  4817.4  137.89    4861  136.76
  4923.3   136.6  4923.8   136.1  4929.5   136.6  5008.7  136.79  5251.5  138.41
  5571.8  144.22  5928.6  148.11  5988.7  148.37  6140.4  148.13  6266.4  149.35
  6281.1   149.9  6330.3  148.65  6377.4  149.14  6682.6  148.84    7059   153.2
#Mann= 9 ,-1 , 0
  3232.1     .05       0  4462.9      .1       0  4923.3     .05       0
  4929.5      .1       0  5008.7     .05       0  5928.6     .07       0
  5988.7     .05       0  6266.4    .035       0  6377.4     .05       0
Bank Sta=4923.3,4929.5
XS Rating Curve= 0 ,0
Exp/Cntr=0.3,0.1

Type RM Length L Ch R = 1 ,12236   ,922,922,922
BEGIN DESCRIPTION:
TRIB 8 TO SPRING CREEK 18.0
END DESCRIPTION:
XS GIS Cut Line= 3
      2582025.01       13528525.        2580475.       13529225.
      2579274.98     13531025.02
#Sta/Elev= 30
  3308.1  153.61  3541.5  149.05  3593.4  147.03  3680.2  146.14  3708.8  144.27
  3876.1  140.86  4251.7  135.93    4442  136.31  4551.3  136.26  4777.6  135.74
  4778.1  135.24  4784.4  135.74    4800  135.99  4861.7  136.16  4989.2  136.23
  5006.1  136.03  5016.4  136.04  5181.6  137.96  5491.1  145.24  5838.1  149.92
  6054.5  150.76  6227.4     149  6428.5  146.85  6581.8  146.94  6627.2  148.18
  6644.9  147.34  6653.9  148.28  6743.5  147.69  7056.5  148.98  7172.2   150.6
#Mann= 13 ,-1 , 0
  3308.1     .05       0    4442      .1       0  4551.3    .035       0
  4777.6     .05       0  4784.4    .035       0    4800      .1       0
  4861.7    .035       0  4989.2     .05       0  5006.1     .05       0
  5016.4     .05       0  6227.4     .07       0  6627.2    .035       0
  6743.5     .05       0
Bank Sta=5006.1,5016.4
XS Rating Curve= 0 ,0
Exp/Cntr=0.3,0.1

Type RM Length L Ch R = 1 ,11314   ,712,712,712
BEGIN DESCRIPTION:
TRIB 8 TO SPRING CREEK 17.0
END DESCRIPTION:
XS GIS Cut Line= 3
      2581675.03     13527824.98        2580475.       13528425.
      2579925.01     13529824.97
#Sta/Elev= 30
  3649.7  153.32  3730.8  152.39    3851  149.61  4015.9  143.92  4284.2   137.2
  4507.8  134.29  4521.8  134.93  4565.2  134.57  4611.2  134.26  4647.6  135.01
  4669.9  134.36  4781.7  134.29  4833.8   134.8  4865.6  135.13  4910.3   134.3
    5057  133.82  5057.5  133.32  5063.5  133.32    5064  133.82  5176.3  134.45
  5518.2  135.52  5754.2  137.66  5957.6  142.16  6071.4  145.75  6125.6  146.61
    6141  146.42  6239.4  148.24  6366.6   149.1    6402  149.94  6495.5   150.1
#Mann= 7 ,-1 , 0
  3649.7     .05       0  4565.2    .035       0  4833.8     .07       0
    5057     .05       0    5064     .07       0  5176.3      .1       0
  5518.2     .05       0
Bank Sta=5057,5064
XS Rating Curve= 0 ,0
Exp/Cntr=0.3,0.1

Type RM Length L Ch R = 1 ,10602   ,573,573,573
BEGIN DESCRIPTION:
Mapping XS d6cfe62d
END DESCRIPTION:
XS GIS Cut Line= 3
      2581555.24     13527798.04      2580001.46     13528179.97
      2579142.12     13528848.35
#Sta/Elev= 30
  3366.6   151.3  3521.3  148.04  3669.3  141.42  3918.6  135.84  4094.4  133.67
  4094.9  133.17  4101.6  133.67  4131.5  134.61  4151.9  134.03  4458.4  134.55
  4588.4  133.87  4630.3  134.45  4635.1  133.73  4718.2  134.63  4746.7  133.95
  4801.3  134.53  4915.4  134.03  4996.5  133.98  5002.9  133.98  5138.1  135.08
  5274.3  137.43  5303.3  136.87  5338.6  138.27  5481.6  139.86  5645.3  143.19
  5794.7  144.73    5887  147.21  5929.5   146.6  5964.8  147.51  6055.3  147.24
#Mann= 9 ,-1 , 0
  3366.6     .05       0  4094.4    .035       0  4101.6     .05       0
  4151.9    .035       0  4630.3      .1       0  4915.4    .035       0
  4996.5    .035       0  5002.9    .035       0  5138.1     .05       0
Bank Sta=4996.5,5002.9
XS Rating Curve= 0 ,0
Exp/Cntr=0.3,0.1

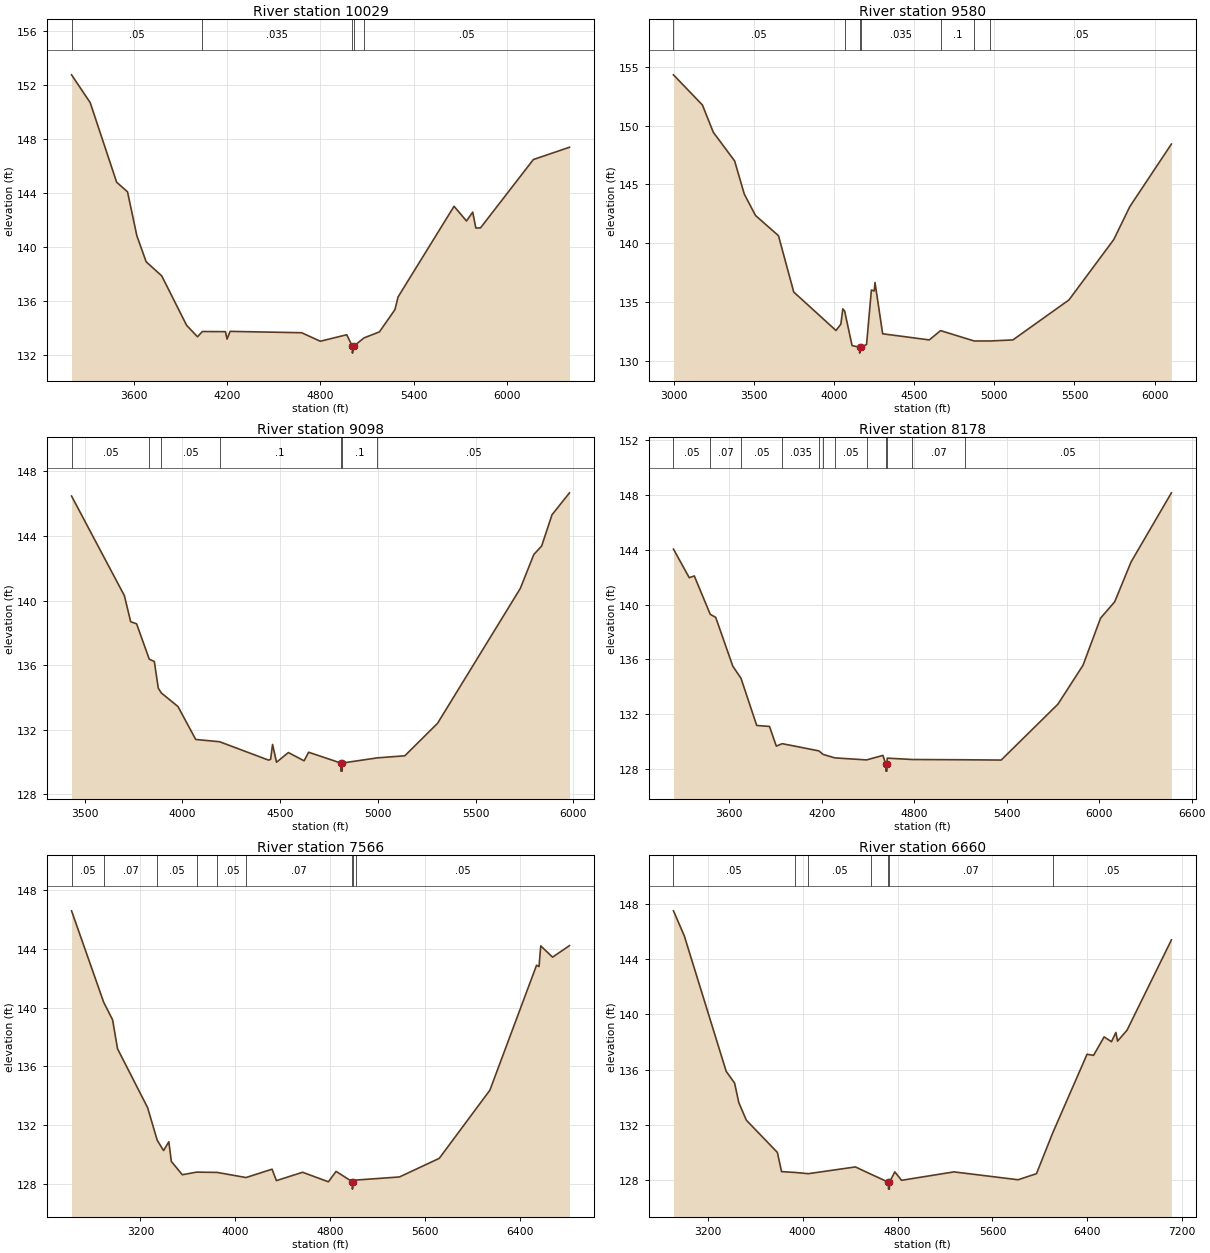
Type RM Length L Ch R = 1 ,10029   ,449,449,449
BEGIN DESCRIPTION:
TRIB 8 TO SPRING CREEK 15.0
END DESCRIPTION:
XS GIS Cut Line= 3
      2581625.04       13527725.        2579825.       13527725.
      2578422.82     13527768.46
#Sta/Elev= 30
  3200.1  152.77  3320.1  150.71  3490.1  144.82  3560.1  144.11  3620.1  140.86
  3680.1  138.93  3780.1  137.89  3940.1  134.23  4010.1  133.38  4041.5  133.77
  4190.1  133.76  4200.1  133.21  4220.1  133.78  4680.1  133.68  4800.1  133.05
  4970.1  133.53  5006.5  132.67    5007  132.17  5013.7  132.67  5081.7   133.3
  5180.2  133.74  5280.3  135.39  5300.3  136.33  5660.5  143.04  5740.5  141.95
  5780.5  142.61  5800.5  141.43  5830.5  141.44  6170.7   146.5    6403  147.41
#Mann= 5 ,-1 , 0
  3200.1     .05       0  4041.5    .035       0  5006.5    .035       0
  5013.7    .035       0  5081.7     .05       0
Bank Sta=5006.5,5013.7
XS Rating Curve= 0 ,0
Exp/Cntr=0.3,0.1

Type RM Length L Ch R = 1 ,9580    ,482,482,482
BEGIN DESCRIPTION:
TRIB 8 TO SPRING CREEK 14.0
END DESCRIPTION:
XS GIS Cut Line= 3
      2581724.97       13527575.        2579725.       13527375.
      2578625.04       13527375.
#Sta/Elev= 30
  2995.6   154.3  3176.5  151.74  3244.3  149.43  3377.5     147  3437.8  144.19
  3508.1  142.37  3651.3  140.66  3746.8  135.88  4010.6  132.62  4040.8  133.15
  4053.3  134.45  4064.5  134.27  4111.1  131.34  4157.8   131.2  4158.3   130.7
    4165   131.2  4201.6  131.43  4231.7  136.05  4249.3  135.97  4254.3  136.69
  4302.1  132.34  4593.5  131.82  4663.6  132.61  4873.7  131.73  4972.2  131.73
  5115.5  131.82  5465.5  135.21  5745.5  140.33  5845.5  143.12  6105.5  148.43
#Mann= 7 ,-1 , 0
  2995.6     .05       0  4064.5    .035       0  4157.8     .05       0
    4165    .035       0  4663.6      .1       0  4873.7    .035       0
  4972.2     .05       0
Bank Sta=4157.8,4165
XS Rating Curve= 0 ,0
Exp/Cntr=0.3,0.1

Type RM Length L Ch R = 1 ,9098    ,920,920,920
BEGIN DESCRIPTION:
TRIB 8 TO SPRING CREEK 13.0
END DESCRIPTION:
XS GIS Cut Line= 3
      2581175.04     13527125.01        2579625.       13526925.
      2578724.98     13527325.01
#Sta/Elev= 30
  3432.8  146.47  3703.2   140.3  3735.3  138.69  3765.6  138.56  3830.4  136.37
  3856.3  136.23  3876.5  134.58  3892.1  134.28  3977.3  133.44  4068.1   131.4
  4190.3  131.26  4441.1  130.12  4451.2  130.17  4461.3  131.09  4481.5  129.99
    4542  130.59  4622.6  130.08  4645.9  130.61  4810.6  129.94  4811.1  129.44
  4817.4  129.44  4817.9  129.94  4996.5  130.26    5138  130.39  5305.5   132.4
  5728.9  140.75    5798  142.85  5838.3  143.38    5891  145.31  5980.6  146.67
#Mann= 7 ,-1 , 0
  3432.8     .05       0  3830.4     .07       0  3892.1     .05       0
  4190.3      .1       0  4810.6     .05       0  4817.9      .1       0
  4996.5     .05       0
Bank Sta=4810.6,4817.9
XS Rating Curve= 0 ,0
Exp/Cntr=0.3,0.1

Type RM Length L Ch R = 1 ,8178    ,612,612,612
BEGIN DESCRIPTION:
TRIB 8 TO SPRING CREEK 12.0
END DESCRIPTION:
XS GIS Cut Line= 3
      2581225.02     13526975.01        2579675.       13526175.
        2578675.       13527275.
#Sta/Elev= 30
  3237.7  144.05  3340.2  141.96  3372.8  142.09  3476.4  139.28  3511.8  139.06
  3622.6  135.49  3675.9   134.6  3777.9  131.15  3860.7  131.08    3905  129.64
  3943.2  129.82  4181.7  129.29  4207.4  129.04  4283.7  128.78  4490.2  128.63
  4597.1  128.96  4615.5  128.31    4616  127.81  4622.6  127.81  4623.1  128.31
  4624.9  128.76  4787.7  128.66  5130.2  128.64  5364.1  128.62  5732.4  132.71
  5895.2  135.56  6008.8     139  6100.7   140.2  6206.8  143.11  6468.6  148.17
#Mann= 12 ,-1 , 0
  3237.7     .05       0  3476.4     .07       0  3675.9     .05       0
  3943.2    .035       0  4181.7     .05       0  4207.4    .035       0
  4283.7     .05       0  4490.2      .1       0  4615.5     .05       0
  4623.1      .1       0  4787.7     .07       0  5130.2     .05       0
Bank Sta=4615.5,4623.1
XS Rating Curve= 0 ,0
Exp/Cntr=0.3,0.1

Type RM Length L Ch R = 1 ,7566    ,906,906,906
BEGIN DESCRIPTION:
Mapping XS e6258cc4
END DESCRIPTION:
XS GIS Cut Line= 4
      2581500.27      13526989.7      2579709.94     13525741.89
      2579275.91     13525796.15      2578300.89     13527031.18
#Sta/Elev= 30
  2620.4   146.6  2890.8  140.37  2965.8  139.17  3007.7  137.19  3260.7  133.18
  3341.5  130.96  3395.1  130.25  3439.6  130.85  3460.6  129.51  3553.2   128.6
  3672.6  128.78  3846.4  128.76  4089.4  128.41  4308.9  128.98  4345.3   128.2
  4566.1  128.77  4783.4  128.12    4848  128.83  4985.1  128.12  4985.6  127.62
  4993.1  128.12  5018.1  128.24  5381.9  128.45    5717  129.72  6143.4  134.37
  6536.2  142.89  6557.1   142.8  6571.5  144.21  6670.9  143.44  6813.6  144.23
#Mann= 9 ,-1 , 0
  2620.4     .05       0  2890.8     .07       0  3341.5     .05       0
  3672.6    .035       0  3846.4     .05       0  4089.4     .07       0
  4985.1     .05       0  4993.1     .07       0  5018.1     .05       0
Bank Sta=4985.1,4993.1
XS Rating Curve= 0 ,0
Exp/Cntr=0.3,0.1

Type RM Length L Ch R = 1 ,6660    ,1148,1148,1148
BEGIN DESCRIPTION:
Mapping XS 8d2058b1
END DESCRIPTION:
XS GIS Cut Line= 4
       2581706.5      13526892.1      2580382.68     13525514.03
      2579981.21     13525297.02      2578190.82     13525676.79
#Sta/Elev= 30
  2911.2  147.51  3002.2   145.7  3355.7  135.87  3426.5  135.02  3461.8  133.61
  3525.5  132.33  3787.2  129.99  3822.4   128.6  3935.7  128.54    4048  128.45
    4445  128.94  4576.3  128.41  4723.7  127.83  4724.2  127.33  4731.3  127.33
  4731.8  127.83  4777.4  128.58  4833.5  127.97  5275.3  128.58  5816.4  128.01
  5971.2  128.45  6106.9  131.38  6397.6  137.11  6452.4  137.03  6541.5  138.37
  6603.5  138.02  6640.8  138.69  6654.6  138.06    6735  138.86  7108.7   145.4
#Mann= 7 ,-1 , 0
  2911.2     .05       0  3935.7    .035       0    4048     .05       0
  4576.3     .07       0  4723.7     .05       0  4731.8     .07       0
  6106.9     .05       0
Bank Sta=4723.7,4731.8
XS Rating Curve= 0 ,0
Exp/Cntr=0.3,0.1

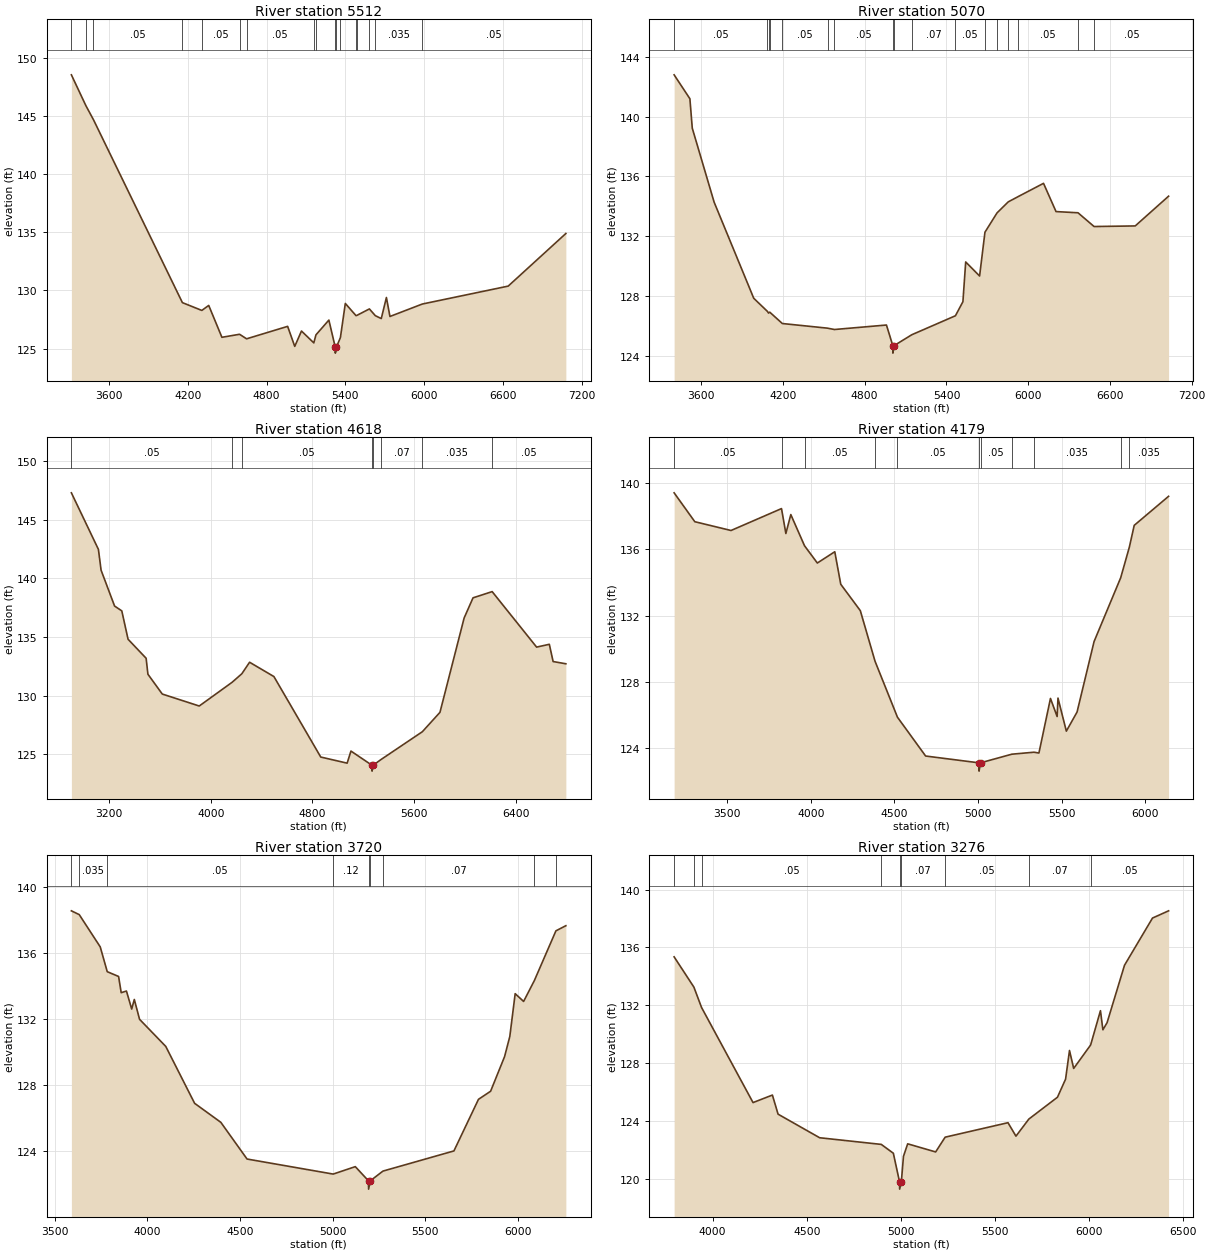
Type RM Length L Ch R = 1 ,5512    ,442,442,442
BEGIN DESCRIPTION:
TRIB 8 TO SPRING CREEK 11.0
END DESCRIPTION:
XS GIS Cut Line= 3
      2581824.98     13526774.96        2581175.       13525225.
      2579174.99       13524625.
#Sta/Elev= 30
  3311.8  148.53  3422.7  145.87  3480.2  144.67  4157.9  128.95  4306.1  128.28
  4358.6  128.71  4459.1  125.97  4593.7  126.23  4647.2  125.84    4960  126.91
  5014.3  125.19  5065.6  126.51  5159.6  125.49  5175.9  126.18  5274.4  127.45
  5323.2  125.11  5323.7  124.61  5331.7  125.11  5362.3  125.95  5399.7  128.88
  5481.4  127.83    5489  127.86  5583.2  128.41  5628.3  127.83  5673.8  127.58
  5712.9  129.39  5739.9  127.76  5986.7  128.83  6641.2  130.37  7080.6  134.89
#Mann= 17 ,-1 , 0
  3311.8     .05       0  3422.7    .035       0  3480.2     .05       0
  4157.9    .035       0  4306.1     .05       0  4593.7     .07       0
  4647.2     .05       0  5159.6     .07       0  5175.9    .035       0
  5323.2     .05       0  5331.7    .035       0  5362.3     .07       0
  5481.4     .05       0    5489     .07       0  5583.2     .05       0
  5628.3    .035       0  5986.7     .05       0
Bank Sta=5323.2,5331.7
XS Rating Curve= 0 ,0
Exp/Cntr=0.3,0.1

Type RM Length L Ch R = 1 ,5070    ,452,452,452
BEGIN DESCRIPTION:
TRIB 8 TO SPRING CREEK 10.0
END DESCRIPTION:
XS GIS Cut Line= 3
      2581824.99     13526474.96        2581475.       13524925.
      2579474.99       13524525.
#Sta/Elev= 30
  3401.6  142.79  3517.3  141.19  3534.8  139.22  3695.2  134.27  3985.9  127.84
  4086.5  126.96  4094.4  126.85  4103.3  126.91  4195.8  126.15  4527.5  125.84
  4577.7  125.75  4959.8  126.05  5006.4  124.67  5006.9  124.17  5015.5  124.67
  5145.8   125.4    5466  126.67  5520.9  127.61  5541.3  130.27  5643.3  129.33
  5682.6  132.26  5771.1  133.55  5853.5  134.29  5927.9  134.65  6112.4  135.53
  6204.2  133.64  6365.5  133.56  6483.4  132.64  6785.4  132.68  7030.2  134.67
#Mann= 17 ,-1 , 0
  3401.6     .05       0  4086.5    .035       0  4094.4     .05       0
  4103.3    .035       0  4195.8     .05       0  4527.5     .07       0
  4577.7     .05       0  5006.4     .05       0  5015.5     .05       0
  5145.8     .07       0    5466     .05       0  5682.6    .035       0
  5771.1     .05       0  5853.5    .035       0  5927.9     .05       0
  6365.5    .035       0  6483.4     .05       0
Bank Sta=5006.4,5015.5
XS Rating Curve= 0 ,0
Exp/Cntr=0.3,0.1

Type RM Length L Ch R = 1 ,4618    ,439,439,439
BEGIN DESCRIPTION:
TRIB 8 TO SPRING CREEK 9.0
END DESCRIPTION:
XS GIS Cut Line= 3
        2583275.       13525975.        2581725.       13524575.
      2579924.96       13524575.
#Sta/Elev= 30
  2903.8  147.28  3116.4  142.46  3137.3  140.69  3243.5  137.63  3300.2  137.22
  3349.6   134.8  3491.5  133.18  3505.7  131.82  3618.6  130.13  3909.3  129.11
  4167.6  131.13  4244.3  131.86  4305.3  132.84  4496.6  131.62    4865  124.76
  5072.5  124.24  5102.5  125.27  5267.9  124.06  5268.4  123.56  5277.1  124.06
  5339.2  124.55  5664.2  126.92  5802.5  128.57  5992.5  136.61  6062.5  138.33
    6213  138.86  6562.5  134.13  6662.5  134.37  6692.5   132.9  6792.5  132.71
#Mann= 8 ,-1 , 0
  2903.8     .05       0  4167.6    .035       0  4244.3     .05       0
  5267.9     .05       0  5277.1     .05       0  5339.2     .07       0
  5664.2    .035       0    6213     .05       0
Bank Sta=5267.9,5277.1
XS Rating Curve= 0 ,0
Exp/Cntr=0.3,0.1

Type RM Length L Ch R = 1 ,4179    ,459,459,459
BEGIN DESCRIPTION:
TRIB 8 TO SPRING CREEK 8.0
END DESCRIPTION:
XS GIS Cut Line= 3
      2583174.96     13525174.98        2581625.       13524225.
        2580525.       13524525.
#Sta/Elev= 30
  3181.8   139.4  3305.5  137.66  3522.2  137.13  3824.2  138.45  3850.3  136.95
  3879.9  138.09  3961.9  136.21  4038.6  135.17  4142.9  135.85  4178.7  133.89
  4295.7   132.3  4383.8  129.25  4517.9  125.88  4686.4  123.54  5005.5  123.13
    5006  122.63  5014.7  123.13  5202.1  123.65  5334.7  123.77  5364.2  123.72
  5433.3  127.01  5473.1  125.92  5478.2  127.03  5528.3  125.04  5592.3  126.19
  5694.2  130.44  5853.3  134.28  5905.5  136.14  5934.3  137.44  6139.9  139.19
#Mann= 11 ,-1 , 0
  3181.8     .05       0  3824.2    .035       0  3961.9     .05       0
  4383.8    .035       0  4517.9     .05       0  5005.5     .05       0
  5014.7     .05       0  5202.1     .07       0  5334.7    .035       0
  5853.3     .05       0  5905.5    .035       0
Bank Sta=5005.5,5014.7
XS Rating Curve= 0 ,0
Exp/Cntr=0.3,0.1

Type RM Length L Ch R = 1 ,3720    ,444,444,444
BEGIN DESCRIPTION:
TRIB 8 TO SPRING CREEK 7.0
END DESCRIPTION:
XS GIS Cut Line= 3
      2582725.02     13524825.02        2581725.       13523825.
      2580625.04     13524424.98
#Sta/Elev= 30
  3590.8  138.53  3633.2   138.3  3746.4  136.35  3784.2  134.85  3845.4  134.56
  3859.5  133.58  3887.8  133.68  3916.1  132.59  3930.2  133.17  3958.5  131.97
  4099.9  130.33  4255.5  126.89  4396.9  125.74  4538.4  123.52    5003  122.61
  5122.3  123.06  5193.5   122.2    5194   121.7  5202.9   122.2  5271.4  122.79
  5654.3  124.01  5786.7  127.13  5852.2  127.62  5927.7  129.72  5955.7  130.93
  5984.7  133.52  6030.2  133.05    6088  134.31  6204.5  137.32    6258  137.63
#Mann= 9 ,-1 , 0
  3590.8     .05       0  3633.2    .035       0  3784.2     .05       0
    5003     .12       0  5193.5     .05       0  5202.9     .12       0
  5271.4     .07       0    6088     .05       0  6204.5    .035       0
Bank Sta=5193.5,5202.9
XS Rating Curve= 0 ,0
Exp/Cntr=0.3,0.1

Type RM Length L Ch R = 1 ,3276    ,470,470,470
BEGIN DESCRIPTION:
TRIB 8 TO SPRING CREEK 6.0
END DESCRIPTION:
XS GIS Cut Line= 3
      2582825.01       13523375.        2581625.       13523475.
      2580525.03     13524374.98
#Sta/Elev= 30
  3796.1  135.35    3901  133.26  3941.8  131.85  4215.1  125.28  4317.9   125.8
    4348  124.48  4568.8  122.85  4896.1  122.39  4960.1  121.78    4993   119.8
  4993.5   119.3  5002.5   119.8  5013.9  121.57  5036.2  122.43  5184.7  121.87
  5235.1  122.89  5568.8  123.89  5611.1  122.96  5679.5  124.14  5831.5  125.65
  5874.6   126.9  5895.4  128.88  5917.6  127.64  6007.6  129.26  6059.8  131.63
  6072.7  130.31  6094.9   130.8  6187.5  134.77  6336.1  138.03  6421.5  138.53
#Mann= 9 ,-1 , 0
  3796.1     .05       0    3901     .07       0  3941.8     .05       0
  4896.1     .07       0    4993     .05       0  5002.5     .07       0
  5235.1     .05       0  5679.5     .07       0  6007.6     .05       0
Bank Sta=4993,5002.5
XS Rating Curve= 0 ,0
Exp/Cntr=0.3,0.1