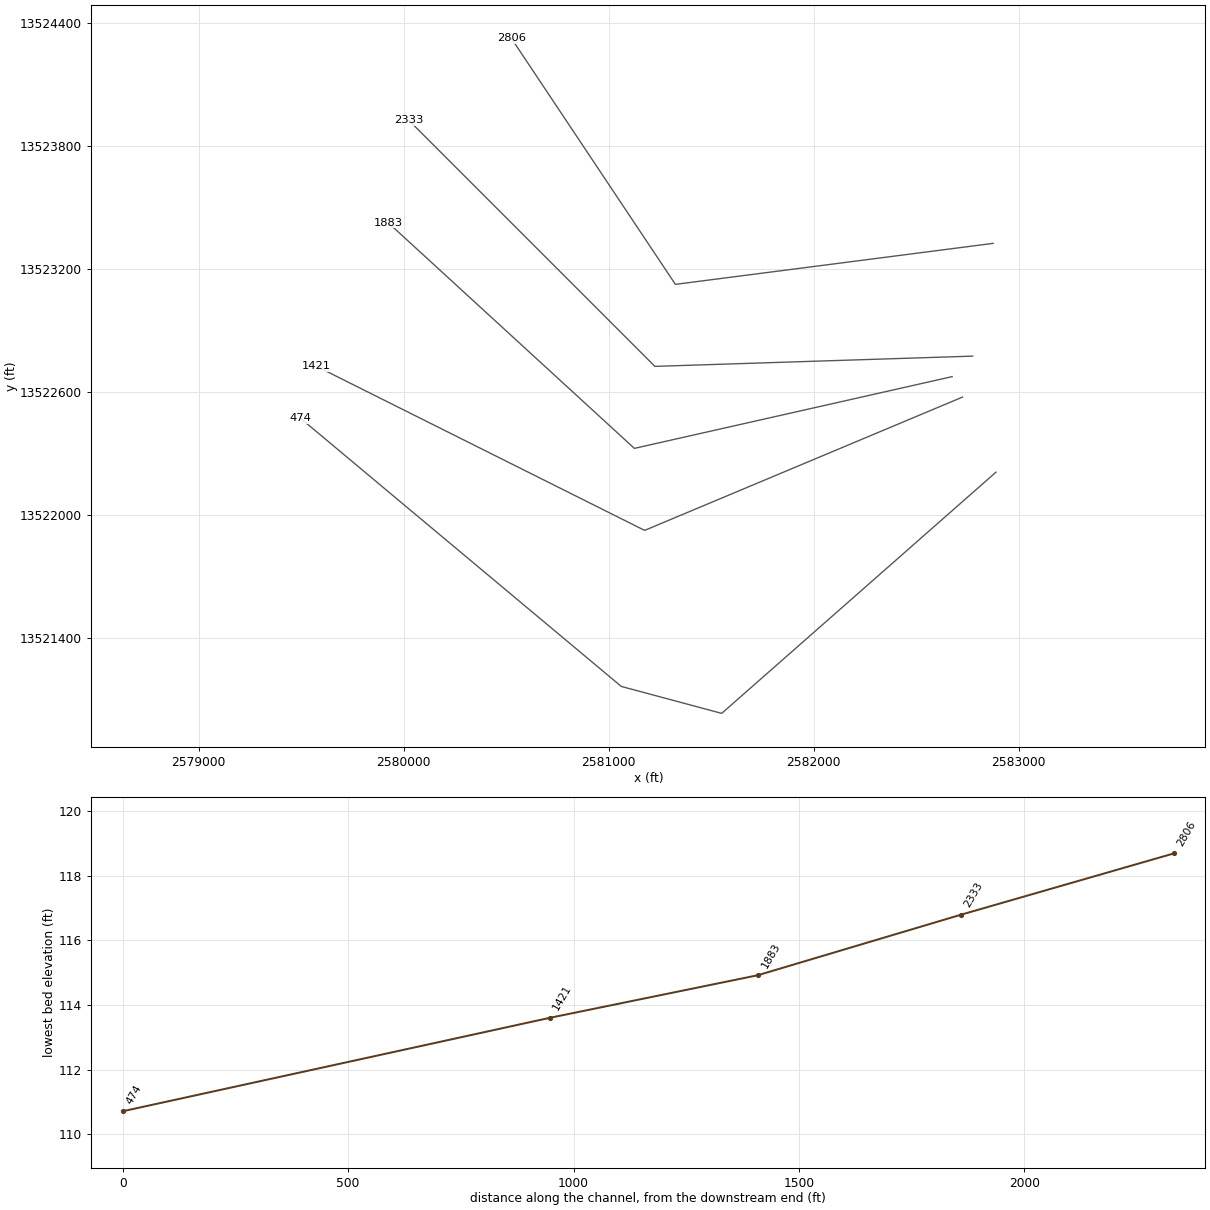
HEC-RAS study TRIB 8 TO SPRING CREEK.prj: TRIB 8 TO SPRING CREEK Base Level Engineering

--- TRIB 8 TO SPRING CREEK.g01 (geometry) --- (continued)

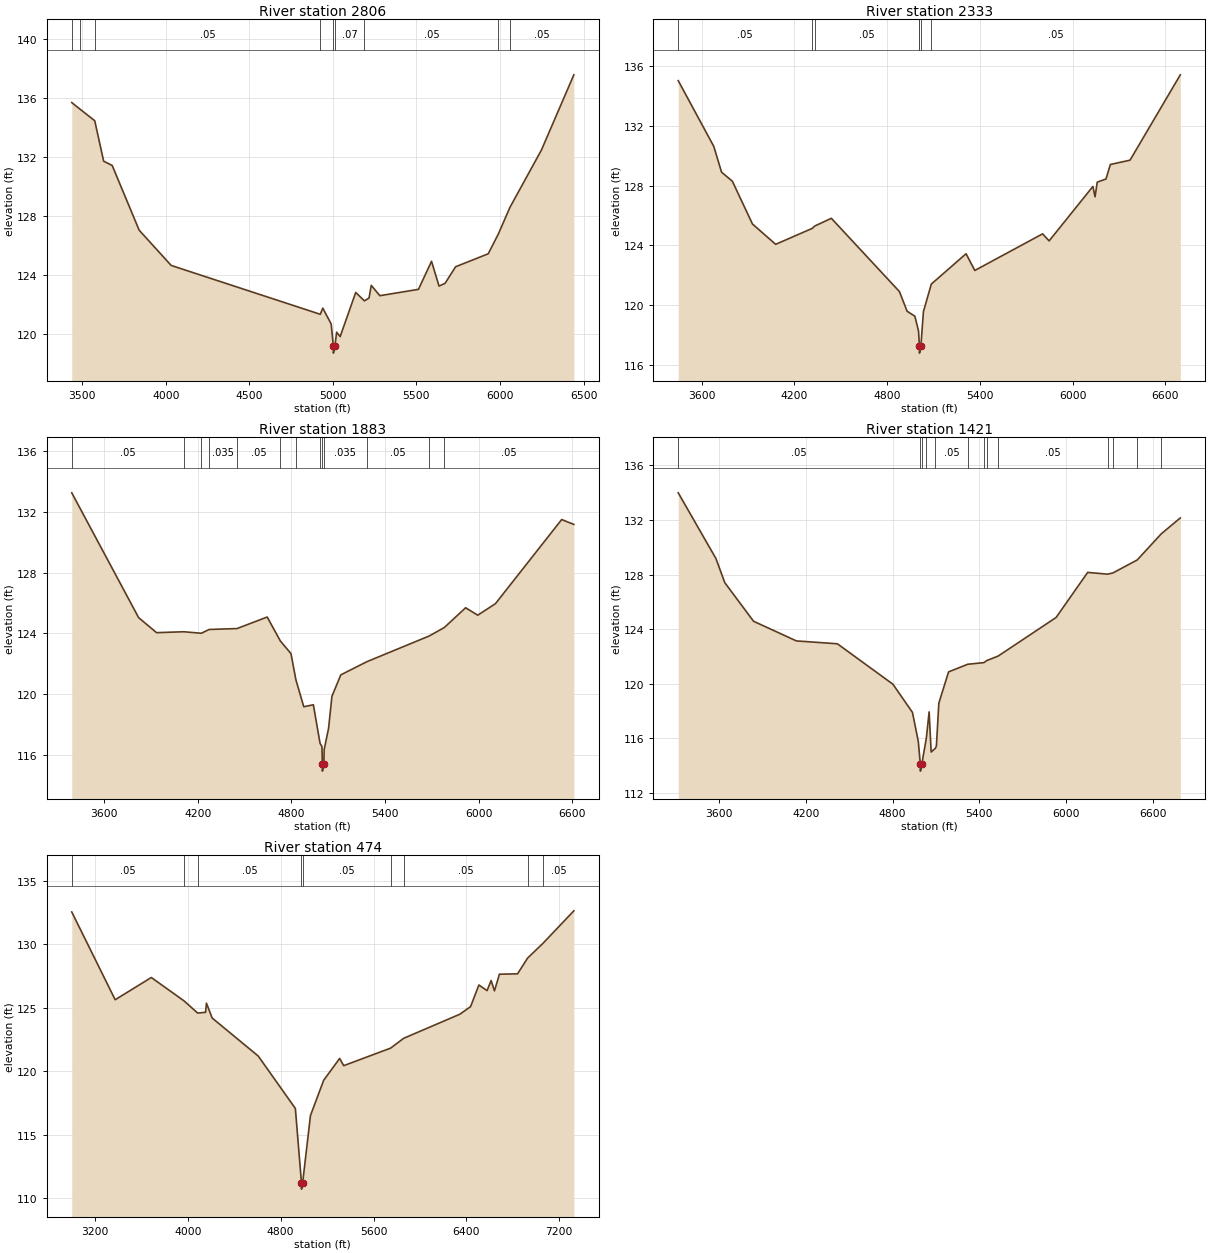
Type RM Length L Ch R = 1 ,2806    ,473,473,473
BEGIN DESCRIPTION:
TRIB 8 TO SPRING CREEK 5.0
END DESCRIPTION:
XS GIS Cut Line= 3
        2582875.       13523325.        2581325.       13523125.
      2580524.98     13524325.02
#Sta/Elev= 30
  3437.1  135.66  3484.7  135.23  3574.6  134.43    3628  131.69  3679.1   131.4
  3840.4  127.02    4032  124.63  4924.5  121.32  4939.5  121.74  4989.9  120.66
  5002.6  119.19  5003.1  118.69  5012.3  119.19  5022.5  120.11  5043.5  119.81
  5136.7   122.8  5188.6  122.23  5216.3  122.42  5229.8  123.28  5280.9  122.58
  5512.2  123.01  5590.4  124.91  5635.4  123.23  5671.5  123.42  5734.6  124.54
  5929.9  125.42  5990.8  126.77  6059.6  128.56  6248.4  132.45  6442.2  137.54
#Mann= 9 ,-1 , 0
  3437.1     .05       0  3484.7     .07       0  3574.6     .05       0
  4924.5     .07       0  5002.6     .05       0  5012.3     .07       0
  5188.6     .05       0  5990.8     .07       0  6059.6     .05       0
Bank Sta=5002.6,5012.3
XS Rating Curve= 0 ,0
Exp/Cntr=0.3,0.1

Type RM Length L Ch R = 1 ,2333    ,450,450,450
BEGIN DESCRIPTION:
TRIB 8 TO SPRING CREEK 4.0
END DESCRIPTION:
XS GIS Cut Line= 3
      2582774.98       13522775.        2581225.       13522725.
      2580025.03     13523924.97
#Sta/Elev= 30
  3449.1  135.02  3679.2  130.62  3729.2   128.9  3799.3  128.29  3929.3  125.43
  4079.4  124.07  4316.8  125.14  4333.3   125.3  4439.6  125.81  4879.8  120.91
  4929.8  119.59  4979.9  119.26  5003.4  118.28  5008.1  117.48  5009.2  117.29
  5009.7  116.79  5018.9  117.29  5035.2  119.57  5086.3  121.41    5311  123.44
  5367.6  122.32    5806  124.77  5848.4   124.3  6131.3  127.94  6145.4  127.25
  6159.5  128.23  6216.1  128.44  6244.4  129.41  6371.7   129.7  6696.9  135.41
#Mann= 7 ,-1 , 0
  3449.1     .05       0  4316.8    .035       0  4333.3     .05       0
  5008.1     .07       0  5009.2     .05       0  5018.9     .07       0
  5086.3     .05       0
Bank Sta=5009.2,5018.9
XS Rating Curve= 0 ,0
Exp/Cntr=0.3,0.1

Type RM Length L Ch R = 1 ,1883    ,462,462,462
BEGIN DESCRIPTION:
TRIB 8 TO SPRING CREEK 3.0
END DESCRIPTION:
XS GIS Cut Line= 3
      2582675.01       13522675.        2581125.       13522325.
      2579925.02     13523424.99
#Sta/Elev= 30
  3393.3  133.25  3821.7  125.03  3936.7  124.04  4111.3   124.1  4223.3     124
  4273.7  124.25  4452.2  124.31  4645.5  125.07  4729.3   123.5  4797.8  122.66
  4829.5  120.93  4879.8  119.16  4941.3  119.29  4984.2  116.75  4996.2  116.54
  4998.7  115.42  4999.2  114.92  5008.6  115.42  5010.4  116.33  5038.8  117.75
  5060.3  119.85  5117.1  121.26  5284.6  122.13  5683.3  123.82  5780.5  124.38
  5916.8  125.68  5994.5  125.19    6108  125.95  6532.2  131.49  6610.2  131.17
#Mann= 13 ,-1 , 0
  3393.3     .05       0  4111.3    .035       0  4223.3     .05       0
  4273.7    .035       0  4452.2     .05       0  4729.3    .035       0
  4829.5     .05       0  4984.2    .035       0  4998.7    .035       0
  5008.6    .035       0  5284.6     .05       0  5683.3    .035       0
  5780.5     .05       0
Bank Sta=4998.7,5008.6
XS Rating Curve= 0 ,0
Exp/Cntr=0.3,0.1

Type RM Length L Ch R = 1 ,1421    ,947,947,947
BEGIN DESCRIPTION:
TRIB 8 TO SPRING CREEK 2.0
END DESCRIPTION:
XS GIS Cut Line= 3
      2582725.03     13522575.01        2581175.       13521925.
      2579574.97     13522725.02
#Sta/Elev= 30
  3319.1  133.99  3579.4  129.18  3640.7  127.41  3839.6  124.58  4135.7  123.14
  4418.9  122.93  4802.6  119.97  4937.8   117.9  4978.2  115.77  4992.2   114.1
  4992.7   113.6  5002.2   114.1  5033.7  116.02    5053  117.94    5067     115
  5096.8  115.28  5103.3  115.46  5120.1  118.58  5187.2  120.87  5319.8  121.43
  5431.3  121.55  5451.3   121.7  5530.1  122.03  5930.7  124.86  6148.7  128.16
  6286.6  128.03  6323.1  128.12  6490.9  129.07  6657.5  130.99  6788.8  132.15
#Mann= 13 ,-1 , 0
  3319.1     .05       0  4992.2     .05       0  5002.2     .05       0
  5033.7    .035       0  5096.8     .05       0  5319.8    .035       0
  5431.3     .05       0  5451.3    .035       0  5530.1     .05       0
  6286.6    .035       0  6323.1     .05       0  6490.9    .035       0
  6657.5     .05       0
Bank Sta=4992.2,5002.2
XS Rating Curve= 0 ,0
Exp/Cntr=0.3,0.1

Type RM Length L Ch R = 1 ,474     ,0,0,0
BEGIN DESCRIPTION:
TRIB 8 TO SPRING CREEK 1.0
END DESCRIPTION:
XS GIS Cut Line= 4
      2582888.64     13522208.98      2581550.92      13521032.5
      2581061.21     13521163.89       2579497.6     13522470.87
#Sta/Elev= 30
  2999.9  132.53  3373.9  125.62  3685.2  127.37  3966.1  125.54  4085.1  124.57
  4152.9  124.63  4160.5  125.35  4209.8  124.18  4606.5  121.19  4926.7  117.06
  4979.1  111.21  4979.6  110.71  4989.3  111.21  5056.7   116.5  5170.6  119.28
  5308.3     121  5343.4  120.43  5747.2  121.81  5861.1  122.59  6344.1  124.48
  6436.5  125.08  6508.1  126.78  6578.4  126.34  6613.5  127.13  6642.2  126.32
  6685.1  127.63  6841.3  127.66  6927.9   128.9  7059.1  130.05  7326.3  132.62
#Mann= 9 ,-1 , 0
  2999.9     .05       0  3966.1    .035       0  4085.1     .05       0
  4979.1     .05       0  4989.3     .05       0  5747.2    .035       0
  5861.1     .05       0  6927.9    .035       0  7059.1     .05       0
Bank Sta=4979.1,4989.3
XS Rating Curve= 0 ,0
Exp/Cntr=0.3,0.1

Chan Stop Cuts=-1
Use User Specified Reach Order=0
Composite Channel Slope=5