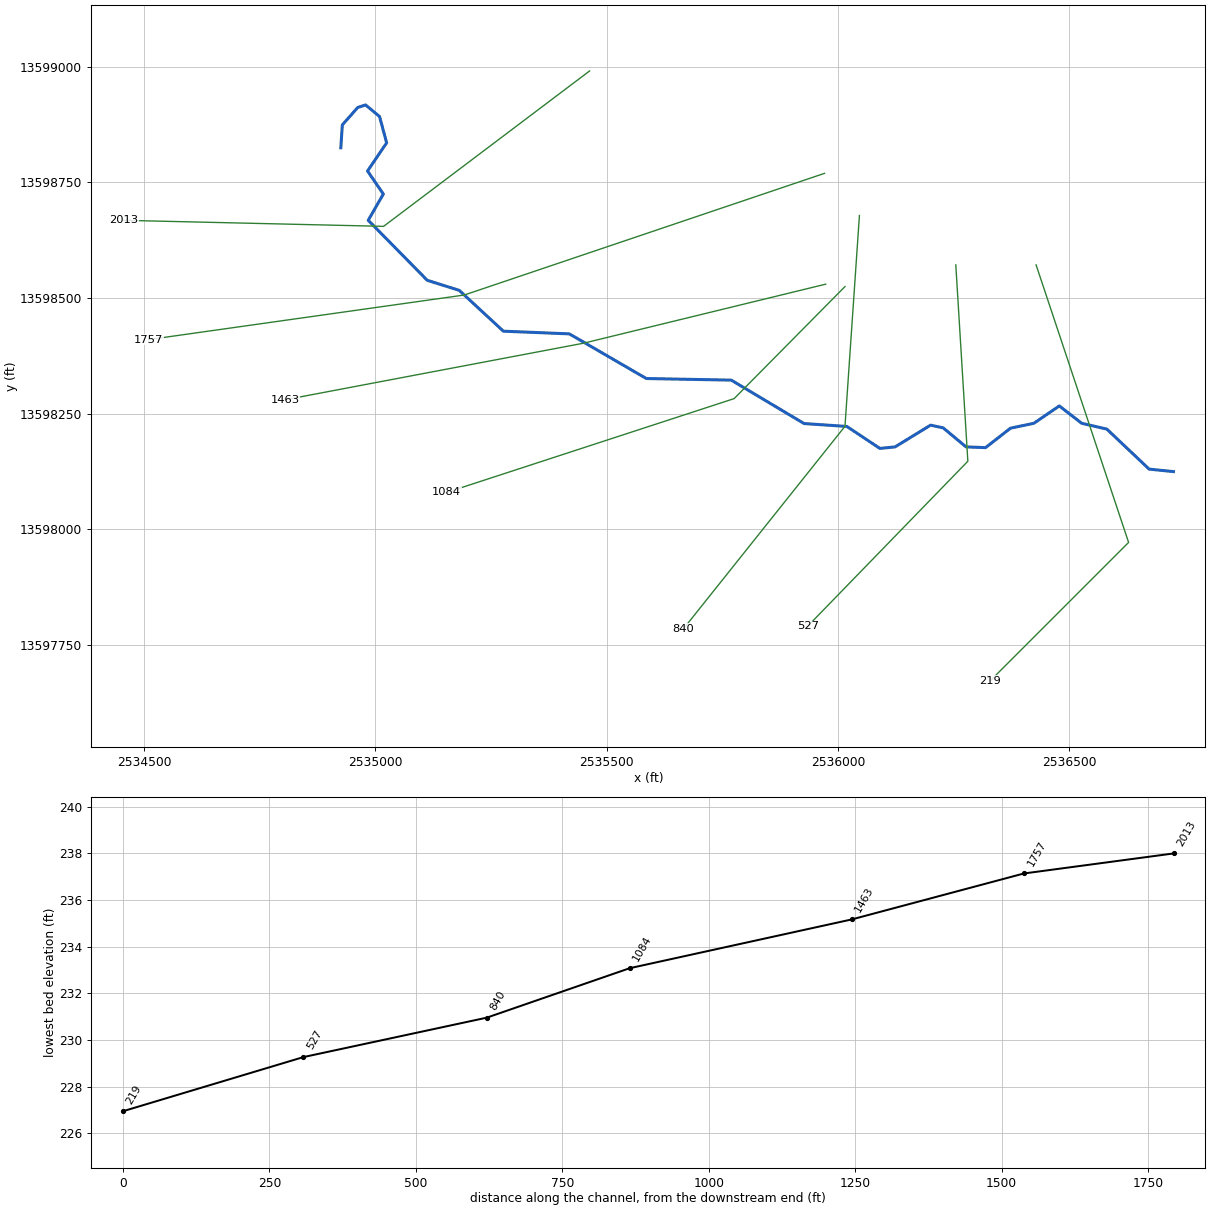
--- TRIB 8_1 TO IRISH CREEK.prj (project) ---

Proj Title=TRIB 8_1 TO IRISH CREEK Base Level Engineering
Current Plan=p01
Default Exp/Contr=0.3,0.1
English Units
Geom File=g01
Flow File=f01
Plan File=p01
BEGIN DESCRIPTION:
TRIB 8_1 TO IRISH CREEK
END DESCRIPTION:

--- TRIB 8_1 TO IRISH CREEK.p01 (plan) ---

Plan Title=Multiple Run
Short Identifier=Multiple
Geom File=g01
Flow File=f01
Subcritical Flow
K Sum by GR= 0
Std Step Tol= 0.01
Critical Tol= 0.01
Num of Std Step Trials= 20
Max Error Tol= 0.3
Flow Tol Ratio= 0.001
Split Flow NTrial= 30
Split Flow Tol= 0.02
Split Flow Ratio= 0.02
Log Output Level= 0
Friction Slope Method= 1
Unsteady Friction Slope Method= 2
Unsteady Bridges Friction Slope Method= 1
Parabolic Critical Depth
Global Vel Dist=  1 , 1 , 1
Global Log Level= 0
CheckData=True
Encroach Param= -1, 0, 0, 0
BEGIN DESCRIPTION:
Multiple Run
END DESCRIPTION:

--- TRIB 8_1 TO IRISH CREEK.f01 (steady flow) ---

Flow Title=Multiple
Number of Profiles=7
Profile Names=10-year,25-year,50-year,1pct_min,100-year,1pct_plu,500-year
River Rch & RM= TRIB 8_1 TO IRIS,Reach-1,2013
     424     670     888     572    1141    2276    1863
Boundary for River Rch & Prof#=TRIB 8_1 TO IRIS,Reach-1,1
Up Type=0
Dn Type=3
Dn Slope=0.005
Boundary for River Rch & Prof#=TRIB 8_1 TO IRIS,Reach-1,2
Up Type=0
Dn Type=3
Dn Slope=0.005
Boundary for River Rch & Prof#=TRIB 8_1 TO IRIS,Reach-1,3
Up Type=0
Dn Type=3
Dn Slope=0.005
Boundary for River Rch & Prof#=TRIB 8_1 TO IRIS,Reach-1,4
Up Type=0
Dn Type=3
Dn Slope=0.005
Boundary for River Rch & Prof#=TRIB 8_1 TO IRIS,Reach-1,5
Up Type=0
Dn Type=3
Dn Slope=0.005
Boundary for River Rch & Prof#=TRIB 8_1 TO IRIS,Reach-1,6
Up Type=0
Dn Type=3
Dn Slope=0.005
Boundary for River Rch & Prof#=TRIB 8_1 TO IRIS,Reach-1,7
Up Type=0
Dn Type=3
Dn Slope=0.005

--- TRIB 8_1 TO IRISH CREEK.g01 (geometry) ---

Geom Title=Existing Conditions

River Reach=TRIB 8_1 TO IRIS,Reach-1
Reach XY= 30
      2534925.00     13598825.00      2534928.29     13598874.40
      2534961.54     13598912.10      2534978.54     13598917.72
      2535008.77     13598892.60      2535024.13     13598835.74
      2534982.81     13598774.91      2535016.96     13598725.00
      2534984.29     13598668.33      2535111.79     13598538.63
      2535181.04     13598516.82      2535276.47     13598428.55
      2535419.07     13598422.75      2535585.50     13598326.20
      2535769.07     13598322.76      2535926.58     13598228.83
      2536019.03     13598222.62      2536090.40     13598175.10
      2536123.28     13598178.40      2536200.00     13598225.38
      2536227.20     13598219.58      2536276.72     13598178.40
      2536318.89     13598176.80      2536372.81     13598218.87
      2536423.36     13598229.42      2536478.31     13598266.98
      2536526.65     13598229.45      2536581.05     13598216.88
      2536672.49     13598130.33      2536725.00     13598125.00

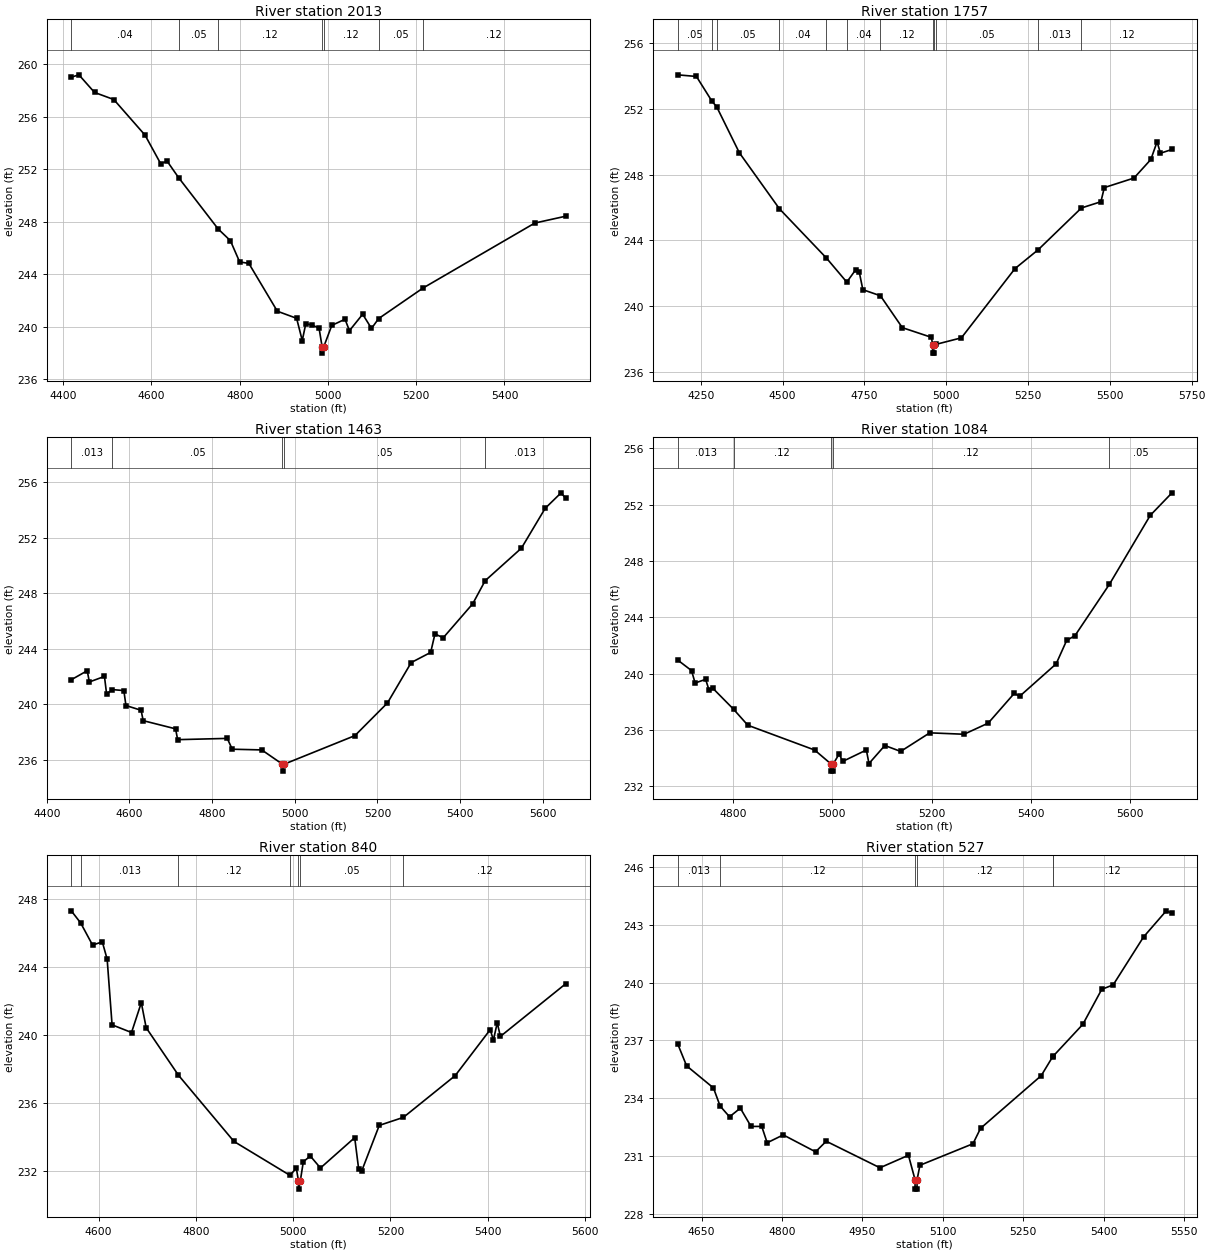
Type RM Length L Ch R = 1,2013,256,256,256
BEGIN DESCRIPTION:
Mapping XS f258783f
END DESCRIPTION:
XS GIS Cut Line= 3
      2535462.89     13598991.14      2535017.55     13598655.18
      2534455.05     13598668.21
#Sta/Elev= 30
  4418.3  259.00  4435.6  259.18  4471.0  257.84  4514.7  257.30  4585.5  254.59
  4620.9  252.42  4635.5  252.61  4661.7  251.35  4751.4  247.44  4778.9  246.56
  4799.9  244.94  4820.7  244.83  4885.3  241.19  4929.0  240.65  4941.8  238.96
  4949.8  240.24  4964.4  240.13  4979.9  239.90  4986.7  238.50  4987.0  238.00
  4990.7  238.50  5008.7  240.11  5038.7  240.58  5048.7  239.71  5078.7  240.96
  5098.7  239.88  5114.9  240.63  5215.3  242.95  5468.8  247.90  5538.8  248.42
#Mann=7,-1,0
  4418.3    0.04       0  4661.7    0.05       0  4751.4    0.12       0
  4986.7    0.05       0  4990.7    0.12       0  5114.9    0.05       0
  5215.3    0.12       0
Bank Sta=4986.7,4990.7
Exp/Cntr=0.3,0.1

Type RM Length L Ch R = 1,1757,294,294,294
BEGIN DESCRIPTION:
Mapping XS cd3a674a
END DESCRIPTION:
XS GIS Cut Line= 3
      2535970.71     13598769.78      2535192.03     13598506.75
      2534509.90     13598410.42
#Sta/Elev= 30
  4179.1  254.07  4236.8  253.97  4284.7  252.45  4298.3  252.14  4367.9  249.33
  4490.4  245.92  4634.2  242.92  4696.2  241.46  4723.4  242.21  4734.0  242.10
  4745.3  241.00  4799.0  240.63  4865.9  238.69  4955.0  238.10  4958.3  237.64
  4958.5  237.14  4962.0  237.14  4962.3  237.64  4970.0  237.68  5046.4  238.07
  5210.1  242.28  5281.1  243.43  5413.1  245.97  5472.7  246.35  5483.1  247.21
  5573.7  247.79  5625.3  248.92  5644.4  250.00  5654.5  249.30  5689.9  249.53
#Mann=12,-1,0
  4179.1    0.05       0  4284.7    0.04       0  4298.3    0.05       0
  4490.4    0.04       0  4634.2   0.013       0  4696.2    0.04       0
  4799.0    0.12       0  4958.3    0.05       0  4962.3    0.12       0
  4970.0    0.05       0  5281.1   0.013       0  5413.1    0.12       0
Bank Sta=4958.3,4962.3
Exp/Cntr=0.3,0.1

Type RM Length L Ch R = 1,1463,379,379,379
BEGIN DESCRIPTION:
Mapping XS cc0df3b5
END DESCRIPTION:
XS GIS Cut Line= 3
      2535973.30     13598530.19      2535449.85     13598402.58
      2534804.03     13598280.19
#Sta/Elev= 30
  4459.2  241.76  4497.8  242.41  4503.0  241.60  4539.5  242.00  4544.7  240.73
  4558.3  241.05  4586.4  240.98  4591.5  239.90  4628.1  239.56  4633.2  238.81
  4711.5  238.22  4716.6  237.44  4836.6  237.53  4848.6  236.75  4920.0  236.70
  4970.1  235.67  4970.3  235.17  4974.1  235.67  5145.4  237.73  5224.2  240.09
  5281.6  243.00  5328.6  243.73  5339.0  245.06  5359.1  244.79  5430.4  247.24
  5460.4  248.90  5548.2  251.25  5605.6  254.12  5644.1  255.24  5655.3  254.84
#Mann=5,-1,0
  4459.2   0.013       0  4558.3    0.05       0  4970.1    0.05       0
  4974.1    0.05       0  5460.4   0.013       0
Bank Sta=4970.1,4974.1
Exp/Cntr=0.3,0.1

Type RM Length L Ch R = 1,1084,244,244,244
BEGIN DESCRIPTION:
Mapping XS 8ac9be2a
END DESCRIPTION:
XS GIS Cut Line= 3
      2536014.96     13598524.99      2535775.37     13598282.79
      2535153.44     13598079.82
#Sta/Elev= 30
  4688.9  240.98  4717.1  240.22  4724.2  239.34  4745.4  239.60  4752.5  238.81
  4759.5  238.98  4801.5  237.48  4830.3  236.34  4964.7  234.58  4998.0  233.58
  4998.2  233.08  5001.7  233.08  5002.0  233.58  5014.1  234.30  5021.2  233.77
  5068.8  234.58  5074.1  233.62  5106.0  234.90  5137.8  234.48  5196.4  235.80
  5265.4  235.70  5314.0  236.49  5366.6  238.61  5377.1  238.39  5450.7  240.70
  5471.8  242.36  5488.7  242.71  5558.0  246.36  5640.1  251.25  5683.8  252.85
#Mann=5,-1,0
  4688.9   0.013       0  4801.5    0.12       0  4998.0    0.05       0
  5002.0    0.12       0  5558.0    0.05       0
Bank Sta=4998,5002
Exp/Cntr=0.3,0.1

Type RM Length L Ch R = 1,840,313,313,313
BEGIN DESCRIPTION:
Mapping XS adf328cd
END DESCRIPTION:
XS GIS Cut Line= 3
      2536046.20     13598678.66      2536014.95     13598222.89
      2535665.97     13597785.36
#Sta/Elev= 30
  4543.8  247.29  4563.1  246.58  4587.6  245.28  4607.6  245.47  4617.6  244.45
  4627.7  240.60  4667.7  240.15  4687.8  241.90  4697.8  240.43  4764.0  237.65
  4878.2  233.76  4993.4  231.77  5006.5  232.19  5010.8  231.46  5011.1  230.96
  5014.8  231.46  5020.9  232.57  5035.3  232.90  5056.1  232.20  5126.5  233.98
  5134.6  232.15  5141.0  232.03  5177.0  234.70  5226.6  235.17  5333.1  237.62
  5405.2  240.32  5411.6  239.70  5419.6  240.72  5426.0  239.92  5560.3  243.01
#Mann=7,-1,0
  4543.8    0.04       0  4563.1   0.013       0  4764.0    0.12       0
  4993.4    0.05       0  5010.8    0.05       0  5014.8    0.05       0
  5226.6    0.12       0
Bank Sta=5010.8,5014.8
Exp/Cntr=0.3,0.1

Type RM Length L Ch R = 1,527,308,308,308
BEGIN DESCRIPTION:
Mapping XS e5c80dbe
END DESCRIPTION:
XS GIS Cut Line= 3
      2536254.53     13598571.85      2536280.58     13598147.37
      2535934.23     13597790.61
#Sta/Elev= 30
  4605.1  236.84  4622.0  235.68  4672.1  234.53  4684.5  233.59  4702.1  233.03
  4722.2  233.48  4742.2  232.53  4762.2  232.53  4772.3  231.68  4802.3  232.09
  4862.6  231.21  4882.5  231.76  4982.7  230.38  5035.9  231.03  5048.1  229.77
  5048.3  229.27  5051.8  229.27  5052.1  229.77  5057.3  230.51  5156.3  231.63
  5170.4  232.43  5283.6  235.17  5305.1  236.16  5305.5  236.17  5361.3  237.84
  5396.6  239.66  5417.9  239.89  5474.5  242.38  5516.9  243.74  5527.6  243.61
#Mann=6,-1,0
  4605.1   0.013       0  4684.5    0.12       0  5048.1    0.05       0
  5052.1    0.12       0  5305.1    0.05       0  5305.5    0.12       0
Bank Sta=5048.1,5052.1
Exp/Cntr=0.3,0.1

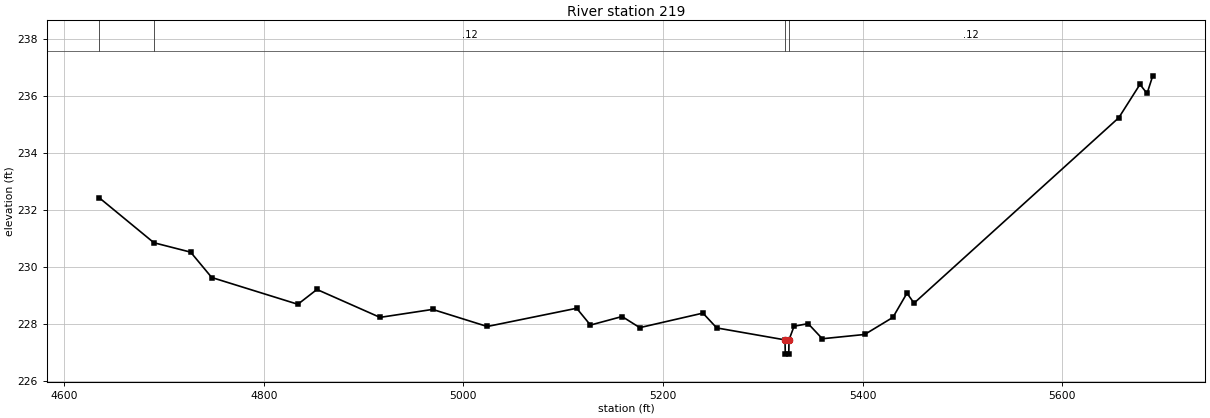
Type RM Length L Ch R = 1,219,0,0,0
BEGIN DESCRIPTION:
TRIB 8_1 TO IRISH CREEK 1.0
END DESCRIPTION:
XS GIS Cut Line= 3
      2536428.12     13598571.88      2536628.13     13597971.88
      2536329.06     13597672.81
#Sta/Elev= 30
  4635.2  232.44  4690.0  230.86  4726.8  230.53  4747.9  229.64  4834.2  228.70
  4853.3  229.22  4916.5  228.24  4969.2  228.52  5023.9  227.92  5113.5  228.56
  5127.3  227.97  5159.0  228.27  5176.7  227.88  5240.0  228.39  5253.8  227.87
  5322.2  227.45  5322.5  226.95  5326.0  226.95  5326.2  227.45  5331.3  227.93
  5345.4  228.02  5359.6  227.49  5402.0  227.64  5430.3  228.24  5444.4  229.09
  5451.5  228.74  5656.6  235.25  5677.8  236.42  5684.9  236.10  5690.6  236.72
#Mann=4,-1,0
  4635.2   0.013       0  4690.0    0.12       0  5322.2    0.05       0
  5326.2    0.12       0
Bank Sta=5322.2,5326.2
Exp/Cntr=0.3,0.1

Chan Stop Cuts=-1