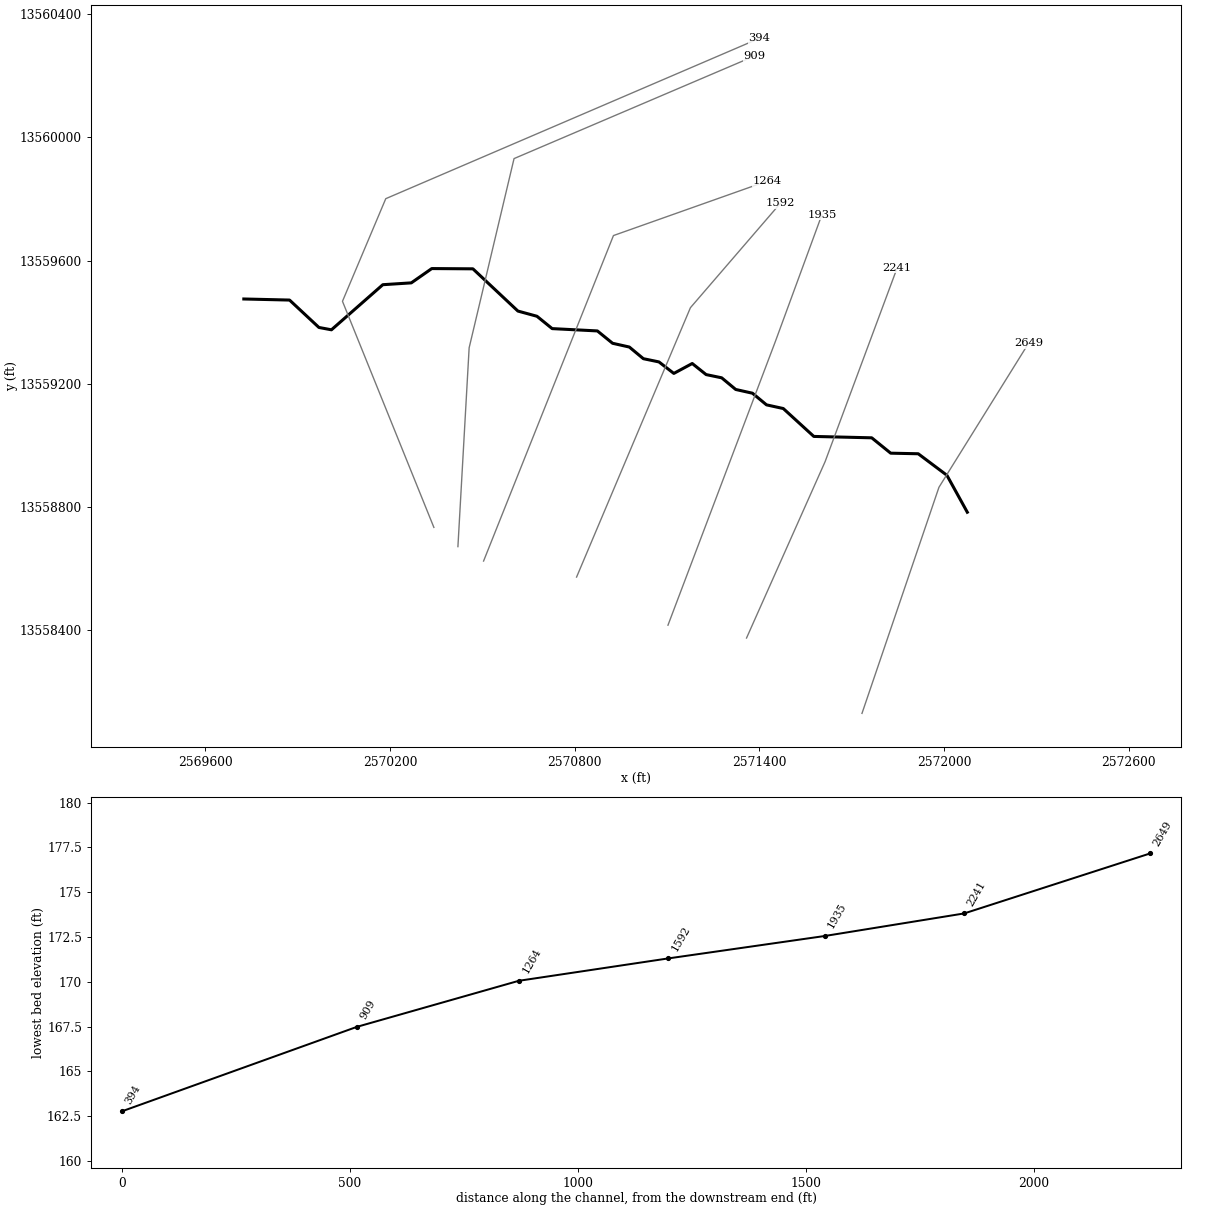
--- TRIB 9 TO PRICE CREEK.prj (project) ---

Proj Title=TRIB 9 TO PRICE CREEK Base Level Engineering
Current Plan=p01
Default Exp/Contr=0.3,0.1
English Units
Geom File=g01
Flow File=f01
Plan File=p01
BEGIN DESCRIPTION:
TRIB 9 TO PRICE CREEK
END DESCRIPTION:

--- TRIB 9 TO PRICE CREEK.p01 (plan) ---

Plan Title=Multiple Run
Short Identifier=Multiple
Geom File=g01
Flow File=f01
Subcritical Flow
K Sum by GR= 0
Std Step Tol= 0.01
Critical Tol= 0.01
Num of Std Step Trials= 20
Max Error Tol= 0.3
Flow Tol Ratio= 0.001
Split Flow NTrial= 30
Split Flow Tol= 0.02
Split Flow Ratio= 0.02
Log Output Level= 0
Friction Slope Method= 1
Unsteady Friction Slope Method= 2
Unsteady Bridges Friction Slope Method= 1
Parabolic Critical Depth
Global Vel Dist=  1 , 1 , 1
Global Log Level= 0
CheckData=True
Encroach Param= -1, 0, 0, 0
BEGIN DESCRIPTION:
Multiple Run
END DESCRIPTION:

--- TRIB 9 TO PRICE CREEK.f01 (steady flow) ---

Flow Title=Multiple
Number of Profiles=7
Profile Names=10-year,25-year,50-year,1pct_min,100-year,1pct_plu,500-year
River Rch & RM= TRIB 9 TO PRICE ,Reach-1,2649
     392     603     785     496     989    1974    1551
River Rch & RM= TRIB 9 TO PRICE ,Reach-1,2241
     503     786    1033     659    1315    2623    2104
Boundary for River Rch & Prof#=TRIB 9 TO PRICE ,Reach-1,1
Up Type=0
Dn Type=3
Dn Slope=0.005
Boundary for River Rch & Prof#=TRIB 9 TO PRICE ,Reach-1,2
Up Type=0
Dn Type=3
Dn Slope=0.005
Boundary for River Rch & Prof#=TRIB 9 TO PRICE ,Reach-1,3
Up Type=0
Dn Type=3
Dn Slope=0.005
Boundary for River Rch & Prof#=TRIB 9 TO PRICE ,Reach-1,4
Up Type=0
Dn Type=3
Dn Slope=0.005
Boundary for River Rch & Prof#=TRIB 9 TO PRICE ,Reach-1,5
Up Type=0
Dn Type=3
Dn Slope=0.005
Boundary for River Rch & Prof#=TRIB 9 TO PRICE ,Reach-1,6
Up Type=0
Dn Type=3
Dn Slope=0.005
Boundary for River Rch & Prof#=TRIB 9 TO PRICE ,Reach-1,7
Up Type=0
Dn Type=3
Dn Slope=0.005

--- TRIB 9 TO PRICE CREEK.g01 (geometry) ---

Geom Title=Existing Conditions

River Reach=TRIB 9 TO PRICE ,Reach-1
Reach XY= 30
      2572075.05     13558782.35      2572008.77     13558902.38
      2571915.61     13558972.25      2571826.20     13558974.13
      2571764.60     13559024.04      2571576.47     13559028.55
      2571477.29     13559119.15      2571422.81     13559131.10
      2571377.20     13559168.92      2571322.80     13559181.08
      2571277.19     13559218.95      2571226.63     13559229.41
      2571181.55     13559265.42      2571121.77     13559233.24
      2571073.37     13559270.59      2571022.81     13559281.05
      2570977.20     13559318.92      2570922.82     13559331.12
      2570873.44     13559371.24      2570726.56     13559378.76
      2570677.17     13559418.86      2570615.32     13559435.76
      2570469.14     13559572.95      2570335.51     13559573.80
      2570269.02     13559527.36      2570176.50     13559521.39
      2570009.64     13559374.89      2569968.96     13559382.48
      2569873.55     13559471.49      2569725.00     13559475.00

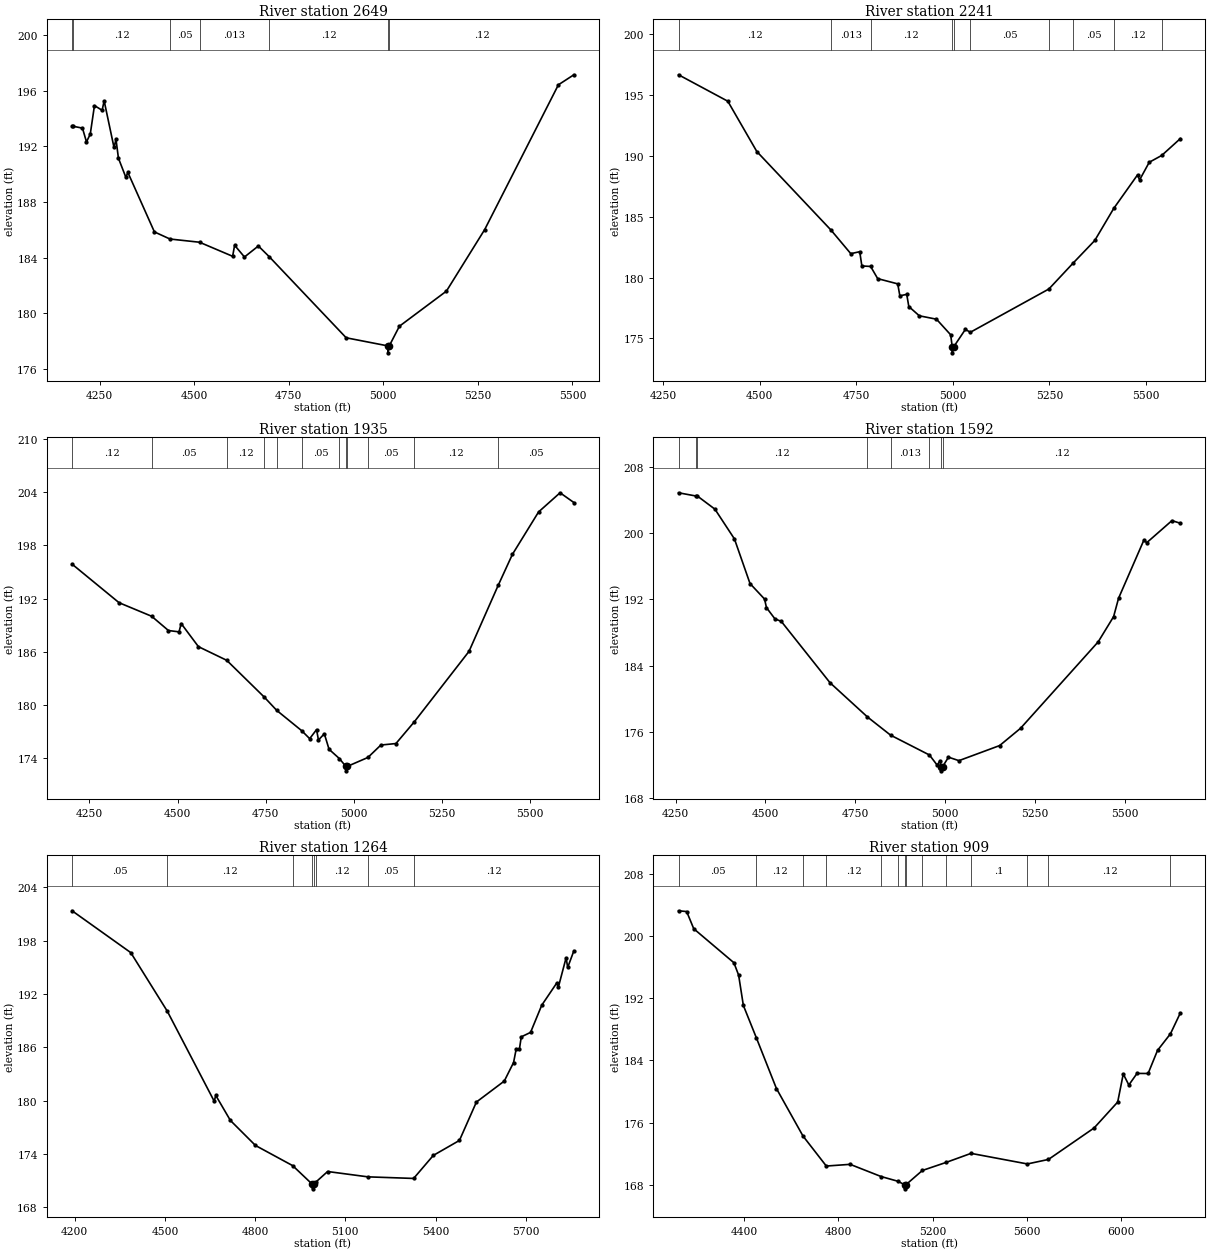
Type RM Length L Ch R = 1,2649,408,408,408
BEGIN DESCRIPTION:
LGII3167
END DESCRIPTION:
XS GIS Cut Line= 3
      2571732.95     13558128.95      2571982.94     13558863.31
      2572273.96     13559331.02
#Sta/Elev= 30
  4177.3  193.46  4180.8  193.43  4204.8  193.30  4215.4  192.31  4225.4  192.87
  4236.5  194.92  4256.8  194.58  4262.1  195.26  4288.2  191.91  4293.4  192.50
  4299.9  191.14  4319.5  189.77  4324.8  190.12  4395.0  185.85  4436.2  185.34
  4514.2  185.11  4601.8  184.10  4607.0  184.89  4633.1  184.05  4669.8  184.84
  4698.6  184.07  4902.0  178.25  5011.9  177.67  5012.2  177.17  5015.9  177.67
  5042.7  179.08  5167.0  181.60  5268.2  186.02  5463.0  196.41  5503.9  197.13
#Mann=7,-1,0
  4177.3    0.03       0  4180.8    0.12       0  4436.2    0.05       0
  4514.2   0.013       0  4698.6    0.12       0  5011.9    0.05       0
  5015.9    0.12       0
Bank Sta=5011.9,5015.9
Exp/Cntr=0.3,0.1

Type RM Length L Ch R = 1,2241,306,306,306
BEGIN DESCRIPTION:
LGII3166
END DESCRIPTION:
XS GIS Cut Line= 3
      2571357.94     13558373.73      2571613.15     13558946.65
      2571847.54     13559576.88
#Sta/Elev= 30
  4289.5  196.64  4417.1  194.47  4492.3  190.34  4684.5  183.89  4735.6  181.96
  4758.8  182.12  4764.3  180.95  4787.0  180.91  4805.3  179.91  4857.2  179.48
  4862.7  178.50  4880.5  178.62  4885.9  177.62  4913.1  176.86  4957.6  176.58
  4994.3  175.30  4998.3  174.32  4998.5  173.82  5002.3  174.32  5032.3  175.74
  5045.4  175.51  5248.7  179.06  5311.9  181.20  5367.5  183.04  5416.6  185.67
  5478.2  188.42  5483.6  188.01  5508.6  189.46  5540.9  190.02  5589.1  191.40
#Mann=10,-1,0
  4289.5    0.12       0  4684.5   0.013       0  4787.0    0.12       0
  4998.3    0.05       0  5002.3    0.12       0  5045.4    0.05       0
  5248.7    0.12       0  5311.9    0.05       0  5416.6    0.12       0
  5540.9    0.05       0
Bank Sta=4998.3,5002.3
Exp/Cntr=0.3,0.1

Type RM Length L Ch R = 1,1935,343,343,343
BEGIN DESCRIPTION:
LGII3165
END DESCRIPTION:
XS GIS Cut Line= 3
      2571102.75     13558415.43      2571451.69     13559337.27
      2571602.74     13559748.75
#Sta/Elev= 30
  4200.7  195.88  4334.0  191.53  4426.5  190.00  4474.2  188.39  4504.3  188.24
  4510.3  189.18  4559.3  186.57  4639.6  185.03  4746.1  180.88  4781.5  179.38
  4852.6  177.08  4875.0  176.19  4894.5  177.21  4899.9  176.04  4916.6  176.74
  4930.0  174.99  4959.1  173.95  4977.7  173.06  4977.9  172.56  4981.7  173.06
  5040.3  174.07  5077.0  175.47  5119.8  175.64  5172.1  178.10  5327.2  186.04
  5410.0  193.49  5450.3  196.98  5524.6  201.77  5585.6  203.93  5624.7  202.83
#Mann=12,-1,0
  4200.7    0.12       0  4426.5    0.05       0  4639.6    0.12       0
  4746.1    0.05       0  4781.5   0.013       0  4852.6    0.05       0
  4959.1    0.12       0  4977.7    0.05       0  4981.7    0.12       0
  5040.3    0.05       0  5172.1    0.12       0  5410.0    0.05       0
Bank Sta=4977.7,4981.7
Exp/Cntr=0.3,0.1

Type RM Length L Ch R = 1,1592,328,328,328
BEGIN DESCRIPTION:
LGII3164
END DESCRIPTION:
XS GIS Cut Line= 3
      2570805.87     13558571.67      2571175.65     13559446.65
      2571467.34     13559785.22
#Sta/Elev= 30
  4258.4  204.88  4306.9  204.49  4310.4  204.50  4359.7  202.90  4414.0  199.31
  4457.4  193.92  4497.8  192.05  4503.2  191.01  4526.9  189.65  4544.3  189.36
  4680.0  181.95  4784.4  177.81  4848.6  175.62  4956.9  173.22  4978.5  171.99
  4986.1  172.54  4989.5  171.81  4989.8  171.31  4993.5  171.81  5009.8  172.96
  5038.9  172.54  5152.2  174.36  5210.5  176.45  5426.7  186.89  5469.5  189.93
  5483.3  192.15  5554.0  199.19  5561.6  198.85  5631.9  201.52  5655.2  201.20
#Mann=8,-1,0
  4258.4    0.04       0  4306.9    0.05       0  4310.4    0.12       0
  4784.4    0.05       0  4848.6   0.013       0  4956.9    0.12       0
  4989.5    0.05       0  4993.5    0.12       0
Bank Sta=4989.5,4993.5
Exp/Cntr=0.3,0.1

Type RM Length L Ch R = 1,1264,355,355,355
BEGIN DESCRIPTION:
LGII3163
END DESCRIPTION:
XS GIS Cut Line= 3
      2570503.78     13558623.74      2570925.65     13559681.02
      2571425.67     13559858.11
#Sta/Elev= 30
  4191.1  201.36  4386.3  196.65  4507.7  190.06  4663.7  179.93  4669.1  180.57
  4717.6  177.76  4801.1  174.94  4924.8  172.67  4990.5  170.56  4990.7  170.06
  4994.5  170.56  5003.8  170.88  5041.0  172.01  5174.8  171.41  5327.0  171.23
  5392.4  173.82  5479.4  175.51  5535.8  179.83  5628.5  182.19  5659.4  184.28
  5668.2  185.81  5678.8  185.78  5685.0  187.17  5715.9  187.67  5753.1  190.73
  5803.2  193.24  5808.5  192.78  5834.1  196.07  5839.4  194.98  5859.9  196.85
#Mann=8,-1,0
  4191.1    0.05       0  4507.7    0.12       0  4924.8   0.013       0
  4990.5    0.03       0  4994.5   0.013       0  5003.8    0.12       0
  5174.8    0.05       0  5327.0    0.12       0
Bank Sta=4990.5,4994.5
Exp/Cntr=0.3,0.1

Type RM Length L Ch R = 1,909,515,515,515
BEGIN DESCRIPTION:
LGII3162
END DESCRIPTION:
XS GIS Cut Line= 4
      2570420.44     13558670.58      2570456.90     13559316.44
      2570602.74     13559931.02      2571383.96     13560264.35
#Sta/Elev= 30
  4122.8  203.24  4157.3  203.14  4187.3  200.93  4357.6  196.56  4377.6  194.97
  4397.7  191.07  4452.9  186.90  4537.9  180.39  4650.6  174.28  4749.5  170.42
  4850.4  170.64  4982.0  169.07  5054.8  168.45  5082.0  167.99  5082.2  167.49
  5086.0  167.99  5156.7  169.85  5258.7  170.90  5363.2  172.05  5602.1  170.69
  5691.5  171.27  5885.2  175.32  5985.1  178.65  6008.7  182.26  6032.4  180.84
  6067.0  182.33  6114.1  182.32  6154.0  185.29  6208.8  187.42  6250.7  190.10
#Mann=14,-1,0
  4122.8    0.05       0  4452.9    0.12       0  4650.6   0.013       0
  4749.5    0.12       0  4982.0     0.1       0  5054.8    0.12       0
  5082.0    0.05       0  5086.0    0.12       0  5156.7     0.1       0
  5258.7    0.05       0  5363.2     0.1       0  5602.1    0.05       0
  5691.5    0.12       0  6208.8    0.05       0
Bank Sta=5082,5086
Exp/Cntr=0.3,0.1

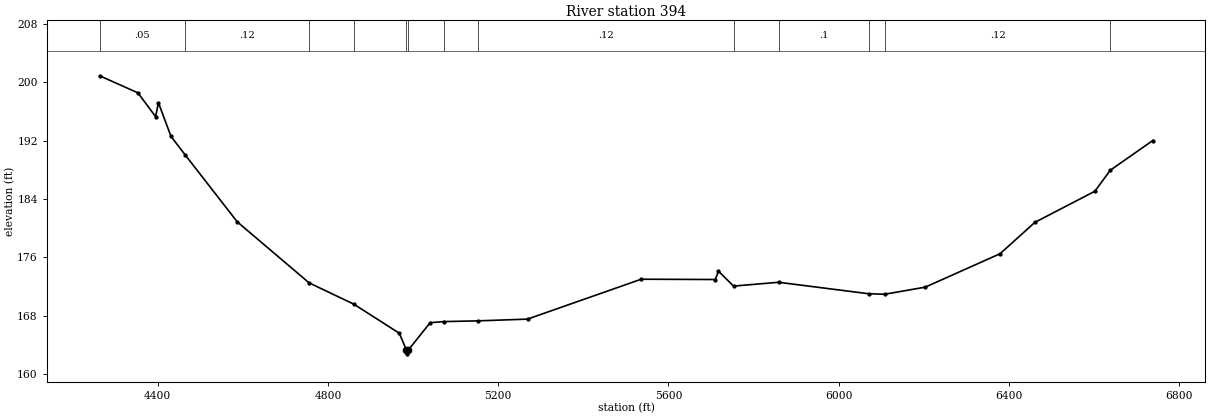
Type RM Length L Ch R = 1,394,0,0,0
BEGIN DESCRIPTION:
LGII3161
END DESCRIPTION:
XS GIS Cut Line= 4
      2570342.32     13558733.09      2570045.44     13559467.48
      2570186.07     13559800.81      2571399.61     13560321.65
#Sta/Elev= 30
  4263.6  200.90  4353.6  198.56  4395.1  195.30  4401.8  197.20  4431.4  192.58
  4464.1  190.09  4586.9  180.88  4755.8  172.51  4860.9  169.59  4967.8  165.60
  4984.6  163.28  4984.8  162.78  4988.6  163.28  5040.2  167.05  5071.6  167.20
  5152.3  167.30  5269.0  167.54  5536.1  173.01  5710.2  172.97  5717.7  174.11
  5753.1  172.07  5858.9  172.59  6070.4  171.02  6108.2  170.95  6203.4  171.92
  6379.2  176.50  6461.0  180.80  6602.1  185.07  6638.3  187.95  6738.1  192.02
#Mann=13,-1,0
  4263.6    0.05       0  4464.1    0.12       0  4755.8   0.013       0
  4860.9    0.12       0  4984.6    0.05       0  4988.6    0.12       0
  5071.6     0.1       0  5152.3    0.12       0  5753.1    0.05       0
  5858.9     0.1       0  6070.4    0.05       0  6108.2    0.12       0
  6638.3    0.05       0
Bank Sta=4984.6,4988.6
Exp/Cntr=0.3,0.1

Chan Stop Cuts=-1