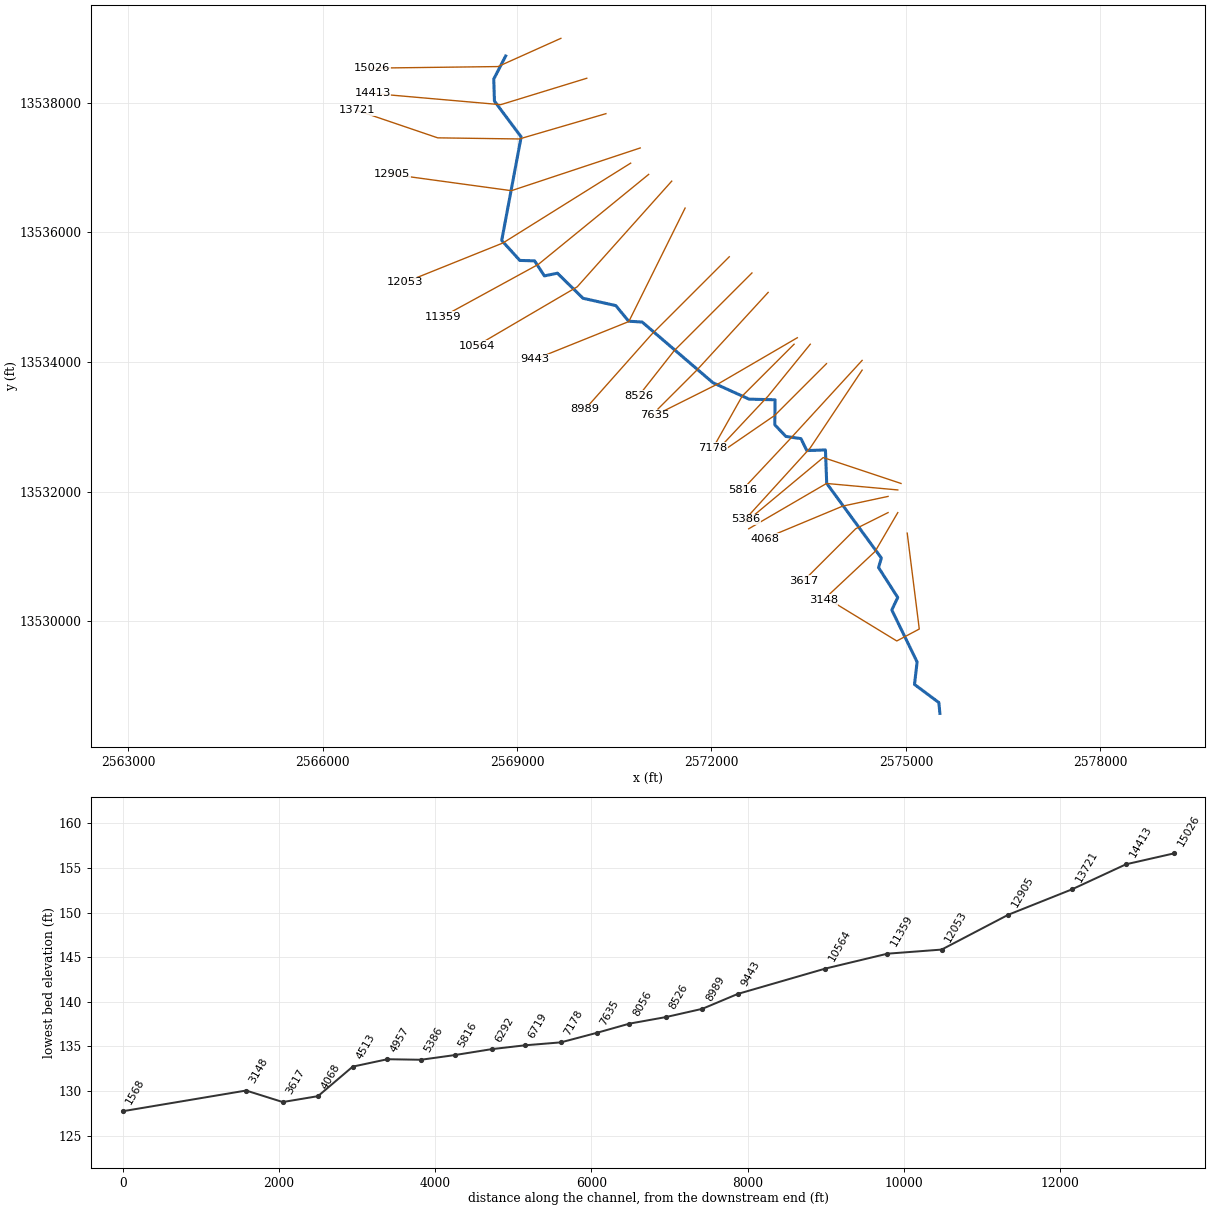
--- TRIB 9 TO SPRING CREEK.prj (project) ---

Proj Title=TRIB 9 TO SPRING CREEK Base Level Engineering
Current Plan=p01
Default Exp/Contr=0.3,0.1
English Units
Geom File=g01
Flow File=f01
Plan File=p01
Y Axis Title=Elevation
X Axis Title(PF)=Main Channel Distance
X Axis Title(XS)=Station
BEGIN DESCRIPTION:
TRIB 9 TO SPRING CREEK
END DESCRIPTION:
DSS Export Rating Curves= 0
DSS Export Rating Curve Sorted= 0
DSS Export Volume Flow Curves= 0
DXF OffsetX= 0
DXF OffsetY= 0
DXF ScaleX= 1
DXF ScaleY= 10

--- TRIB 9 TO SPRING CREEK.p01 (plan) ---

Plan Title=Multiple Run
Short Identifier=Multiple
Geom File=g01
Flow File=f01
Subcritical Flow
K Sum by GR= 0
Std Step Tol= 0.01
Critical Tol= 0.01
Num of Std Step Trials= 20
Max Error Tol= 0.3
Flow Tol Ratio= 0.001
Split Flow NTrial= 30
Split Flow Tol= 0.02
Split Flow Ratio= 0.02
Log Output Level= 0
Friction Slope Method= 1
Unsteady Friction Slope Method= 2
Unsteady Bridges Friction Slope Method= 1
Parabolic Critical Depth
Global Vel Dist=  1 , 1 , 1
Global Log Level= 0
CheckData=True
Encroach Param= -1, 0, 0, 0
BEGIN DESCRIPTION:
Multiple Run
END DESCRIPTION:

--- TRIB 9 TO SPRING CREEK.f01 (steady flow) ---

Flow Title=Multiple
Number of Profiles=7
Profile Names=10-year,25-year,50-year,1pct_min,100-year,1pct_plu,500-year
River Rch & RM= TRIB 9 TO SPRING,Reach-1,15026
     418     646     843     534    1066    2126    1679
River Rch & RM= TRIB 9 TO SPRING,Reach-1,14413
     730    1164    1552    1002    1999    3988    3273
River Rch & RM= TRIB 9 TO SPRING,Reach-1,11359
    1001    1619    2179    1417    2827    5640    4704
River Rch & RM= TRIB 9 TO SPRING,Reach-1,8056
    1246    2034    2753    1798    3588    7158    6027
River Rch & RM= TRIB 9 TO SPRING,Reach-1,4513
    1494    2445    3316    2169    4327    8633    7286
Boundary for River Rch & Prof#=TRIB 9 TO SPRING,Reach-1,1
Up Type=0
Dn Type=3
Dn Slope=0.005
Boundary for River Rch & Prof#=TRIB 9 TO SPRING,Reach-1,2
Up Type=0
Dn Type=3
Dn Slope=0.005
Boundary for River Rch & Prof#=TRIB 9 TO SPRING,Reach-1,3
Up Type=0
Dn Type=3
Dn Slope=0.005
Boundary for River Rch & Prof#=TRIB 9 TO SPRING,Reach-1,4
Up Type=0
Dn Type=3
Dn Slope=0.005
Boundary for River Rch & Prof#=TRIB 9 TO SPRING,Reach-1,5
Up Type=0
Dn Type=3
Dn Slope=0.005
Boundary for River Rch & Prof#=TRIB 9 TO SPRING,Reach-1,6
Up Type=0
Dn Type=3
Dn Slope=0.005
Boundary for River Rch & Prof#=TRIB 9 TO SPRING,Reach-1,7
Up Type=0
Dn Type=3
Dn Slope=0.005

--- TRIB 9 TO SPRING CREEK.g01 (geometry) ---

Geom Title=Existing Conditions
Program Version=4.10

River Reach=TRIB 9 TO SPRING,Reach-1
Reach XY= 30
        2568825.       13538725.      2568640.77       13538369.
      2568651.66     13538028.66      2569063.91     13537476.25
      2568763.81     13535877.22      2569043.34     13535568.64
      2569271.24     13535561.91      2569422.45     13535329.99
       2569623.5     13535371.53      2570018.33      13534984.3
      2570523.78     13534871.56      2570722.55     13534630.47
      2570931.21      13534617.2      2572022.57     13533680.52
      2572581.12     13533426.82       2572981.7     13533416.87
      2572977.07     13533030.86      2573148.13     13532851.17
      2573381.52     13532817.32      2573471.38     13532632.87
      2573758.93     13532642.22      2573778.46      13532126.5
      2574621.87     13530973.37      2574578.34     13530826.72
      2574874.41     13530364.38      2574782.77     13530171.59
      2575173.08     13529369.28      2575132.98     13529021.67
      2575508.77     13528742.24        2575525.       13528575.

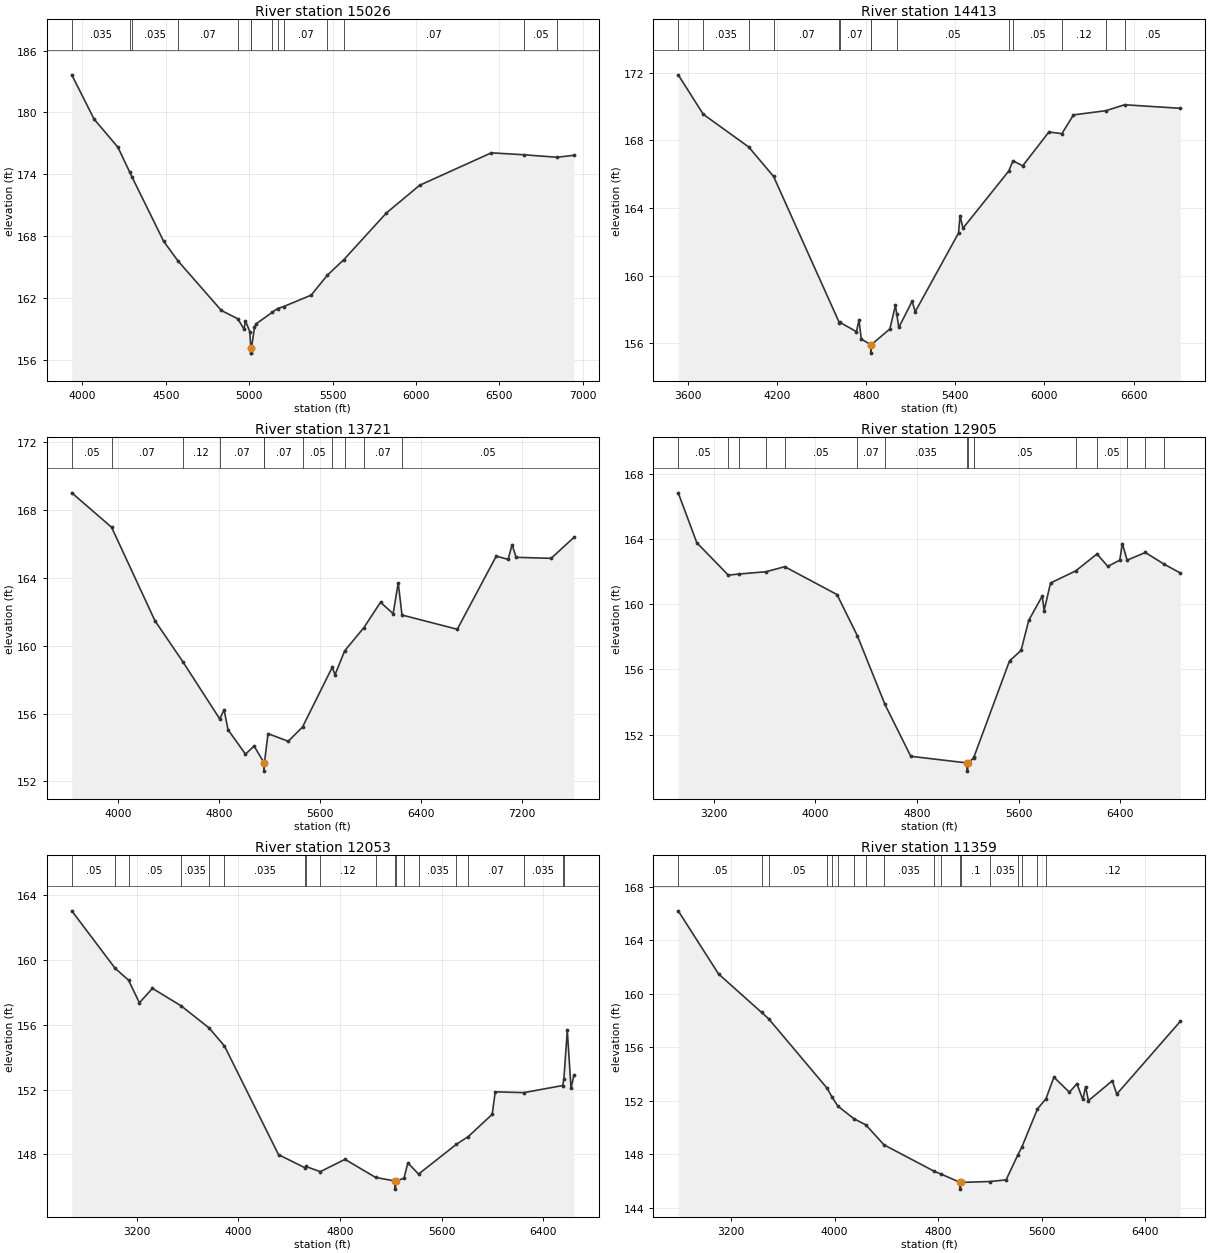
Type RM Length L Ch R = 1 ,15026   ,613,613,613
BEGIN DESCRIPTION:
TRIB 9 TO SPRING CREEK 20.0
END DESCRIPTION:
XS GIS Cut Line= 3
      2569677.11      13538997.9      2568706.28     13538561.99
      2566760.43     13538537.83
#Sta/Elev= 30
  3935.8  183.65  4069.7  179.35  4212.2  176.63    4283  174.22  4296.8  173.74
  4486.2  167.51    4572   165.6  4832.7  160.78  4931.4  159.97  4968.5  158.97
  4977.2  159.77  5003.1  158.73  5009.3  157.14  5009.5  156.64    5013  156.64
  5013.3  157.14  5031.3  159.15  5041.3  159.49  5137.2  160.59  5169.6  160.97
  5206.4  161.16  5371.3  162.27  5468.5  164.21  5566.8  165.71  5821.3  170.23
  6021.4  172.93  6451.4  176.08  6648.1  175.89  6844.7  175.65    6946  175.84
#Mann= 14 ,-1 , 0
  3935.8    .035       0    4283     .07       0  4296.8    .035       0
    4572     .07       0  4931.4    .035       0  5009.3    .035       0
  5013.3    .035       0  5137.2     .07       0  5169.6    .035       0
  5206.4     .07       0  5468.5     .05       0  5566.8     .07       0
  6648.1     .05       0  6844.7     .12       0
Bank Sta=5009.3,5013.3
XS Rating Curve= 0 ,0
Exp/Cntr=0.3,0.1

Type RM Length L Ch R = 1 ,14413   ,692,692,692
BEGIN DESCRIPTION:
Mapping XS 8d4fc672
END DESCRIPTION:
XS GIS Cut Line= 3
      2570076.41     13538381.57      2568748.29     13537973.59
      2566769.56     13538147.16
#Sta/Elev= 30
  3537.6  171.88  3705.7  169.55  4011.7  167.61  4178.5  165.87  4620.2  157.23
  4622.9  157.25  4735.9  156.69  4752.6  157.37  4768.6  156.25    4832  155.92
  4832.3  155.42    4836  155.92  4960.4  156.85  4997.9  158.24  5006.8  157.74
  5020.6  156.94  5110.3  158.49    5131  157.87  5422.2  162.52  5432.2  163.55
  5452.3  162.81  5759.8  166.19    5788  166.79  5853.8   166.5  6029.9   168.5
    6117   168.4  6195.1  169.51  6413.8  169.76  6538.4  170.11  6913.3   169.9
#Mann= 14 ,-1 , 0
  3537.6     .05       0  3705.7    .035       0  4011.7     .05       0
  4178.5     .07       0  4620.2     .12       0  4622.9     .07       0
    4832     .05       0    4836     .07       0  5006.8     .05       0
  5759.8     .07       0    5788     .05       0    6117     .12       0
  6413.8     .07       0  6538.4     .05       0
Bank Sta=4832,4836
XS Rating Curve= 0 ,0
Exp/Cntr=0.3,0.1

Type RM Length L Ch R = 1 ,13721   ,816,816,816
BEGIN DESCRIPTION:
Mapping XS 53bcb719
END DESCRIPTION:
XS GIS Cut Line= 4
      2570371.52     13537834.69      2569034.75     13537444.08
      2567776.07     13537461.44      2566526.03      13537886.8
#Sta/Elev= 30
  3636.6  169.01  3951.7  166.98  4294.8  161.47  4514.3  159.07  4807.7  155.68
  4841.5  156.24  4872.7  155.05  5010.8  153.61    5079  154.09    5157  153.11
  5157.3  152.61    5161  153.11    5189  154.82  5349.1  154.37    5462  155.21
  5697.2  158.73  5719.1  158.29  5795.6   159.7  5946.9  161.06  6079.1  162.56
    6179  161.89  6219.1  163.71  6249.1  161.81  6686.2  160.97  6994.6  165.28
  7088.7  165.09  7120.1  165.96  7151.4  165.21  7428.5  165.15  7608.5  166.38
#Mann= 11 ,-1 , 0
  3636.6     .05       0  3951.7     .07       0  4514.3     .12       0
  4807.7     .07       0    5157     .05       0    5161     .07       0
    5462     .05       0  5697.2    .035       0  5795.6     .05       0
  5946.9     .07       0  6249.1     .05       0
Bank Sta=5157,5161
XS Rating Curve= 0 ,0
Exp/Cntr=0.3,0.1

Type RM Length L Ch R = 1 ,12905   ,852,852,852
BEGIN DESCRIPTION:
Mapping XS 4aa5f794
END DESCRIPTION:
XS GIS Cut Line= 3
      2570901.12      13537305.2      2568913.22     13536645.47
      2567072.97      13536897.2
#Sta/Elev= 30
  2921.2  166.83  3067.3  163.77  3315.4  161.78  3399.1  161.85  3612.1  161.99
  3759.5   162.3  4170.8  160.59  4330.7  158.07  4548.4  153.85  4751.5  150.67
  5196.7  150.26  5196.9  149.76  5200.7  150.26  5245.7  150.56    5248  150.61
  5528.7  156.52  5619.5  157.16  5680.1  159.01  5786.5   160.5  5801.2  159.61
  5851.6   161.3  6049.5  162.04  6217.3  163.08  6302.1  162.32  6396.7   162.7
  6416.9  163.72  6454.4   162.7  6598.1  163.17  6742.3  162.47  6873.1  161.91
#Mann= 16 ,-1 , 0
  2921.2     .05       0  3315.4     .07       0  3399.1     .05       0
  3612.1     .07       0  3759.5     .05       0  4330.7     .07       0
  4548.4    .035       0  5196.7    .035       0  5200.7    .035       0
  5245.7     .07       0    5248     .05       0  6049.5     .07       0
  6217.3     .05       0  6454.4     .07       0  6598.1     .05       0
  6742.3     .07       0
Bank Sta=5196.7,5200.7
XS Rating Curve= 0 ,0
Exp/Cntr=0.3,0.1

Type RM Length L Ch R = 1 ,12053   ,694,694,694
BEGIN DESCRIPTION:
Mapping XS 5541848f
END DESCRIPTION:
XS GIS Cut Line= 3
      2570753.46     13537070.79      2568783.02     13535838.17
      2567272.58     13535230.53
#Sta/Elev= 30
  2687.8  163.05  3029.1   159.5  3134.5  158.77    3220  157.37  3322.9  158.26
  3548.9  157.18  3768.1  155.82  3889.2  154.71  4315.3  147.99  4525.7  147.17
  4530.3  147.26  4644.3  146.94  4838.8   147.7  5080.1  146.58  5234.2  146.36
  5234.5  145.86  5238.2  146.36  5302.8  146.53  5333.6  147.48  5417.9  146.79
  5715.7  148.63  5809.5  149.11  5997.3  150.48  6021.5  151.87  6246.2  151.82
  6552.6  152.26  6561.6  152.66  6588.5  155.66    6618  152.09  6640.1  152.88
#Mann= 19 ,-1 , 0
  2687.8     .05       0  3029.1     .07       0  3134.5     .05       0
  3548.9    .035       0  3768.1     .07       0  3889.2    .035       0
  4525.7     .12       0  4530.3      .1       0  4644.3     .12       0
  5080.1      .1       0  5234.2     .05       0  5238.2      .1       0
  5302.8     .05       0  5417.9    .035       0  5715.7      .1       0
  5809.5     .07       0  6246.2    .035       0  6552.6     .07       0
  6561.6    .063       0
Bank Sta=5234.2,5238.2
XS Rating Curve= 0 ,0
Exp/Cntr=0.3,0.1

Type RM Length L Ch R = 1 ,11359   ,795,795,795
BEGIN DESCRIPTION:
Mapping XS aba950ed
END DESCRIPTION:
XS GIS Cut Line= 3
      2571031.25     13536897.18      2569329.89     13535508.31
      2567854.24     13534701.04
#Sta/Elev= 30
    2792   166.2  3103.6  161.48  3435.6  158.61  3489.6  158.14  3943.1  152.93
  3979.8  152.28  4025.5   151.6  4149.6  150.66  4241.6   150.2  4381.4  148.71
  4770.2  146.73  4823.4  146.52  4970.3   145.9  4970.6   145.4  4974.8   145.9
    5200  145.97  5324.4  146.09  5416.4  147.98    5447  148.56  5567.1   151.4
  5632.9  152.16    5694  153.77  5813.5  152.64  5871.5  153.28  5916.9   152.1
  5938.7  153.06  5960.5  152.01  6145.1   153.5  6179.3   152.5  6670.3  157.94
#Mann= 18 ,-1 , 0
    2792     .05       0  3435.6     .07       0  3489.6     .05       0
  3943.1     .07       0  3979.8     .05       0  4025.5     .07       0
  4149.6    .035       0  4241.6     .07       0  4381.4    .035       0
  4770.2     .12       0  4823.4      .1       0  4970.3     .05       0
  4974.8      .1       0    5200    .035       0  5416.4     .07       0
    5447     .12       0  5567.1    .035       0  5632.9     .12       0
Bank Sta=4970.3,4974.8
XS Rating Curve= 0 ,0
Exp/Cntr=0.3,0.1

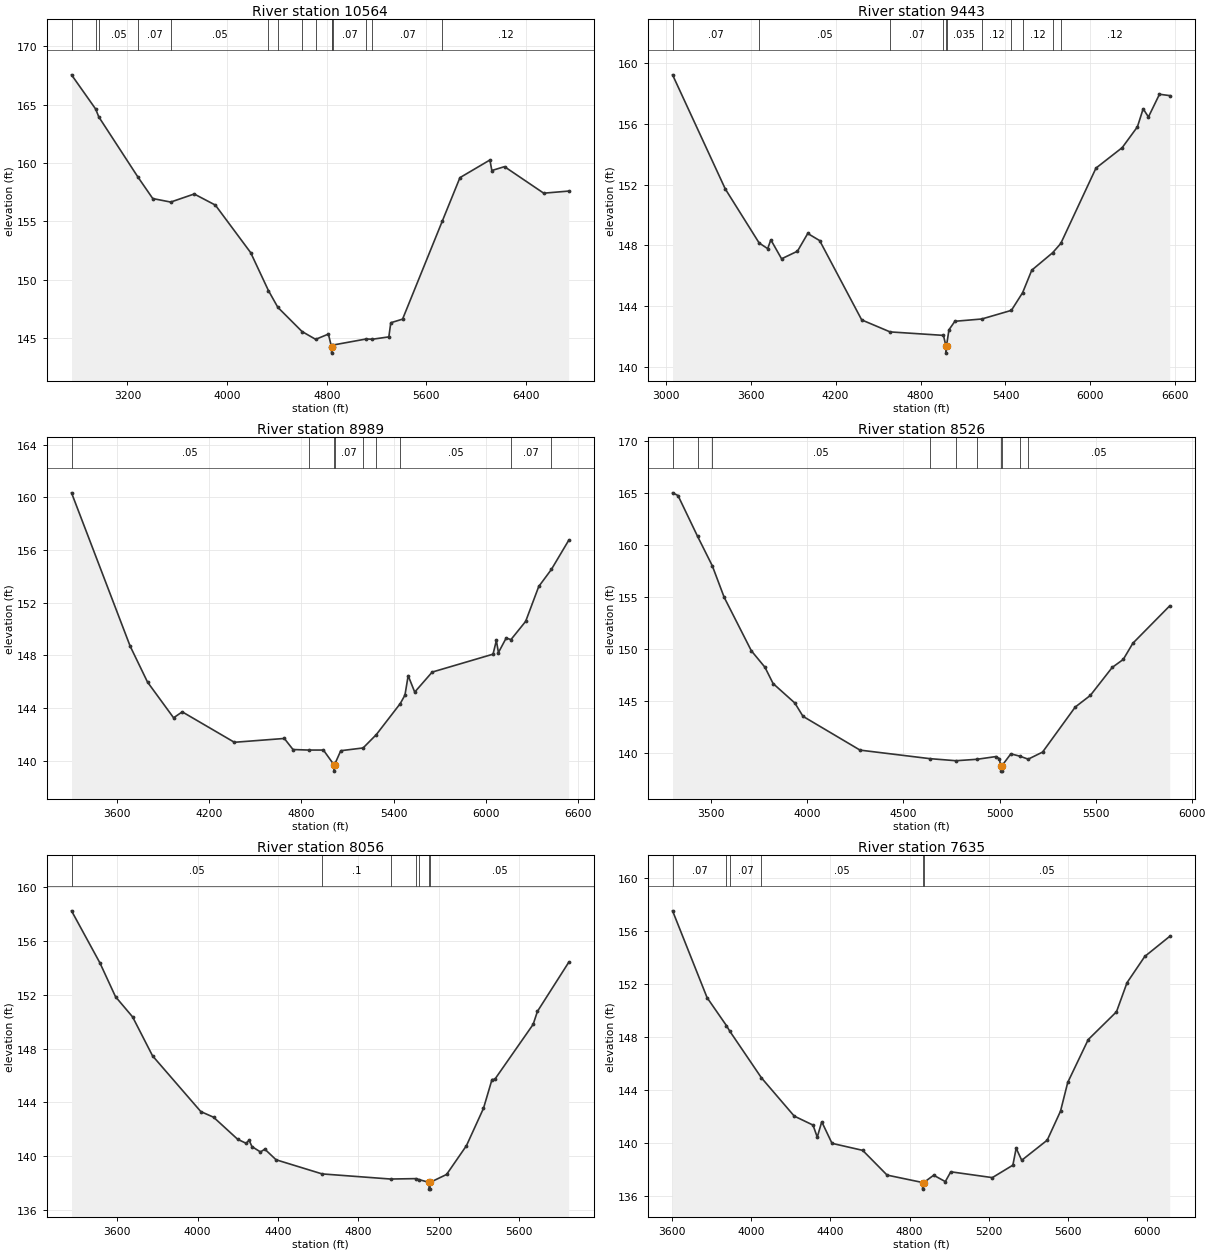
Type RM Length L Ch R = 1 ,10564   ,1121,1121,1121
BEGIN DESCRIPTION:
Mapping XS 6cc9d733
END DESCRIPTION:
XS GIS Cut Line= 3
       2571387.2     13536793.06      2569928.85     13535161.09
      2568375.33     13534249.81
#Sta/Elev= 30
  2751.9  167.55  2945.7  164.62  2970.7  163.95  3285.5  158.79  3403.9  156.96
  3547.8  156.66  3736.6  157.35  3906.3   156.4  4189.7  152.33  4332.4  149.08
  4407.6  147.65  4601.7  145.58  4711.1  144.91  4813.3  145.36  4839.2  144.23
  4839.5  143.73  4843.7  144.23  4853.8  144.43  5116.8  144.94  5166.8  144.92
  5298.5  145.12  5314.2  146.33  5408.7  146.64  5727.1  155.02  5869.1  158.75
  6109.5  160.26  6125.1  159.36  6226.7  159.69  6541.3  157.42  6741.6   157.6
#Mann= 15 ,-1 , 0
  2751.9     .12       0  2945.7     .07       0  2970.7     .05       0
  3285.5     .07       0  3547.8     .05       0  4332.4    .035       0
  4407.6     .05       0  4601.7    .035       0  4711.1     .05       0
  4839.2     .05       0  4843.7     .05       0  4853.8     .07       0
  5116.8     .12       0  5166.8     .07       0  5727.1     .12       0
Bank Sta=4839.2,4843.7
XS Rating Curve= 0 ,0
Exp/Cntr=0.3,0.1

Type RM Length L Ch R = 1 ,9443    ,454,454,454
BEGIN DESCRIPTION:
TRIB 9 TO SPRING CREEK 16.0
END DESCRIPTION:
XS GIS Cut Line= 3
      2571593.55      13536377.1        2570725.       13534625.
      2569281.05     13534043.77
#Sta/Elev= 30
  3048.3  159.24  3420.5  151.72  3660.2  148.15  3720.3  147.78  3742.6  148.36
  3818.5  147.11  3930.6  147.61  4003.4  148.78  4087.5  148.31  4384.6  143.08
    4585  142.29  4961.8  142.06  4979.2  141.39  4979.6  140.89  4983.8  141.39
  5001.1  142.43  5042.8  142.99  5232.5  143.14  5442.1  143.71  5521.5  144.88
    5586  146.36  5733.5  147.51  5790.9  148.12  6039.5  153.09  6224.9  154.44
  6332.3  155.81  6372.9     157  6410.2  156.46  6488.1  157.96  6560.4  157.87
#Mann= 11 ,-1 , 0
  3048.3     .07       0  3660.2     .05       0    4585     .07       0
  4961.8    .035       0  4979.2    .035       0  4983.8    .035       0
  5232.5     .12       0  5442.1     .07       0  5521.5     .12       0
  5733.5     .07       0  5790.9     .12       0
Bank Sta=4979.2,4983.8
XS Rating Curve= 0 ,0
Exp/Cntr=0.3,0.1

Type RM Length L Ch R = 1 ,8989    ,463,463,463
BEGIN DESCRIPTION:
TRIB 9 TO SPRING CREEK 15.0
END DESCRIPTION:
XS GIS Cut Line= 3
      2572274.99     13535624.99        2571075.       13534425.
       2570051.9     13533272.96
#Sta/Elev= 30
  3302.5  160.35  3684.3  148.71  3797.5  145.98  3967.2  143.27  4023.7  143.72
  4363.1  141.41  4688.4   141.7    4745  140.86  4846.6  140.82    4943  140.82
  5010.7  139.72  5011.1  139.22    5016  139.72    5056  140.77  5201.6  140.98
  5287.4  141.99  5443.5  144.35  5474.1  144.99    5495  146.47  5537.7  145.22
  5651.4  146.74  6047.8   148.1  6069.5  149.14  6082.9  148.22  6133.1  149.32
  6164.7  149.21  6260.2  150.59  6345.5  153.24  6427.6  154.53  6540.3  156.74
#Mann= 9 ,-1 , 0
  3302.5     .05       0  4846.6     .07       0  5010.7     .05       0
    5016     .07       0  5201.6     .05       0  5287.4     .07       0
  5443.5     .05       0  6164.7     .07       0  6427.6     .05       0
Bank Sta=5010.7,5016
XS Rating Curve= 0 ,0
Exp/Cntr=0.3,0.1

Type RM Length L Ch R = 1 ,8526    ,470,470,470
BEGIN DESCRIPTION:
TRIB 9 TO SPRING CREEK 14.0
END DESCRIPTION:
XS GIS Cut Line= 3
        2572625.       13535375.        2571425.       13534175.
      2570874.99     13533474.98
#Sta/Elev= 30
  3298.4  165.06  3326.7   164.8  3428.2  160.89  3505.3  158.04  3567.1  155.01
  3708.5  149.87  3779.2  148.29  3821.7  146.72  3934.8  144.85  3977.2  143.57
  4274.2  140.32  4637.3   139.5  4773.8   139.3  4883.5  139.44  4981.3   139.7
  4998.6  139.51  5006.4   138.8  5006.8   138.3  5011.3   138.3  5011.7   138.8
    5059  139.96  5105.6  139.74  5149.2  139.45  5224.1  140.13    5394  144.46
  5472.7  145.58  5586.5  148.27    5644  149.04  5694.1   150.6  5885.7  154.19
#Mann= 10 ,-1 , 0
  3298.4     .05       0  3428.2     .07       0  3505.3     .05       0
  4637.3      .1       0  4773.8    .035       0  4883.5     .05       0
  5006.4     .05       0  5011.7     .05       0  5105.6     .07       0
  5149.2     .05       0
Bank Sta=5006.4,5011.7
XS Rating Curve= 0 ,0
Exp/Cntr=0.3,0.1

Type RM Length L Ch R = 1 ,8056    ,421,421,421
BEGIN DESCRIPTION:
TRIB 9 TO SPRING CREEK 13.0
END DESCRIPTION:
XS GIS Cut Line= 3
      2572874.98     13535074.98        2571775.       13533875.
      2571174.99     13533274.99
#Sta/Elev= 30
  3371.9  158.23  3513.4  154.36  3591.1  151.85  3676.2  150.35  3775.5  147.46
  4015.9  143.32  4079.5   142.9  4199.7  141.26  4242.2  140.96  4256.4   141.2
  4270.6  140.72  4313.2  140.32  4334.7  140.53  4390.8  139.74  4620.2  138.69
  4960.9  138.31  5087.3  138.34  5102.6  138.27  5152.7  138.06  5153.1  137.56
  5157.6  137.56    5158  138.06  5240.2  138.65  5339.2  140.79    5424  143.56
  5466.4   145.7  5480.6  145.72  5671.5   149.8  5692.7  150.76  5848.3   154.4
#Mann= 7 ,-1 , 0
  3371.9     .05       0  4620.2      .1       0  4960.9     .05       0
  5087.3      .1       0  5102.6     .05       0  5152.7     .05       0
    5158     .05       0
Bank Sta=5152.7,5158
XS Rating Curve= 0 ,0
Exp/Cntr=0.3,0.1

Type RM Length L Ch R = 1 ,7635    ,457,457,457
BEGIN DESCRIPTION:
TRIB 9 TO SPRING CREEK 12.0
END DESCRIPTION:
XS GIS Cut Line= 3
        2573325.       13534375.        2572125.       13533675.
      2571124.98     13533174.99
#Sta/Elev= 30
  3604.7  157.55  3778.8  150.99  3876.3  148.88  3893.1  148.46    4053  144.93
  4218.3  142.04    4313  141.36  4334.5  140.45  4357.2  141.61  4408.9  139.98
  4563.5  139.45  4686.7  137.58  4865.6  137.02  4866.1  136.52  4871.7  137.02
  4921.6  137.57  4980.3  137.09  5007.9  137.83  5217.5  137.39    5321  138.33
  5337.7  139.61  5365.7   138.7  5494.3  140.22  5561.3  142.41  5597.7  144.58
  5701.1  147.82  5843.6  149.92  5896.8  152.12  5986.2   154.1    6112  155.62
#Mann= 6 ,-1 , 0
  3604.7     .07       0  3876.3     .05       0  3893.1     .07       0
    4053     .05       0  4865.6     .05       0  4871.7     .05       0
Bank Sta=4865.6,4871.7
XS Rating Curve= 0 ,0
Exp/Cntr=0.3,0.1

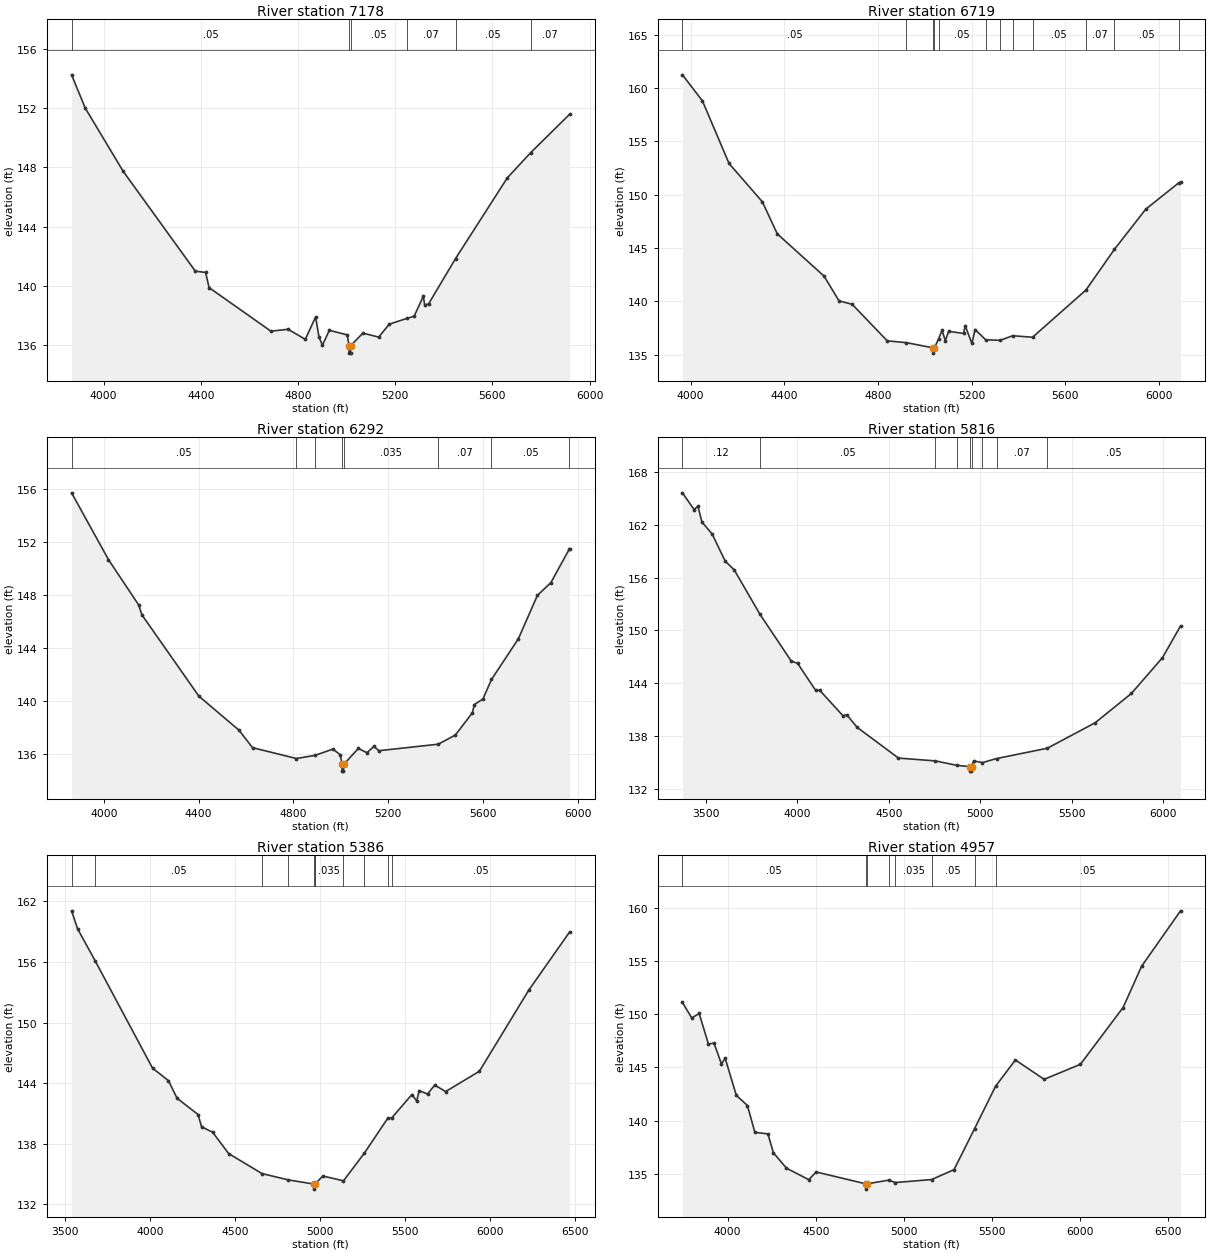
Type RM Length L Ch R = 1 ,7178    ,459,459,459
BEGIN DESCRIPTION:
TRIB 9 TO SPRING CREEK 11.0
END DESCRIPTION:
XS GIS Cut Line= 3
      2573274.98     13534274.98        2572475.       13533475.
      2572025.01     13532675.01
#Sta/Elev= 30
  3868.6  154.23  3925.1  151.98  4080.7  147.73  4377.7  140.99  4420.1   140.9
  4434.3  139.88  4688.8  136.94  4759.5  137.07  4830.2  136.39  4872.7   137.9
  4886.8  136.53  4900.9     136  4929.2     137  5002.8  136.69  5010.4  135.96
  5010.9  135.46  5016.4  135.46  5016.9  135.96  5067.2  136.81  5132.2  136.54
  5175.5  137.41  5247.5   137.8  5278.2  137.95  5315.8   139.3  5321.5   138.7
  5337.4  138.78  5448.5  141.84  5661.3  147.28  5756.8  148.97  5917.8  151.57
#Mann= 6 ,-1 , 0
  3868.6     .05       0  5010.4     .05       0  5016.9     .05       0
  5247.5     .07       0  5448.5     .05       0  5756.8     .07       0
Bank Sta=5010.4,5016.9
XS Rating Curve= 0 ,0
Exp/Cntr=0.3,0.1

Type RM Length L Ch R = 1 ,6719    ,427,427,427
BEGIN DESCRIPTION:
TRIB 9 TO SPRING CREEK 10.0
END DESCRIPTION:
XS GIS Cut Line= 3
      2573525.01     13534275.01        2572875.       13533475.
      2572124.99     13532674.99
#Sta/Elev= 30
  3965.1  161.22  4050.6  158.77  4164.1  152.91  4306.3  149.32  4370.2  146.31
    4570  142.35  4633.9  140.03  4689.9  139.71    4840  136.28    4922  136.11
  5034.9  135.63  5035.4  135.13  5041.4  135.63  5058.9  136.45  5073.8  137.26
    5088  136.31  5102.1  137.17  5165.6  136.98  5172.9   137.7  5201.3  136.04
  5215.2  137.34  5260.3  136.38  5321.7  136.33  5375.8  136.76  5460.4  136.62
  5688.4  141.04  5810.5  144.87  5943.8  148.62  6085.3   151.1  6092.5  151.13
#Mann= 12 ,-1 , 0
  3965.1     .05       0    4922      .1       0  5034.9     .05       0
  5041.4      .1       0  5058.9     .05       0  5260.3      .1       0
  5321.7    .035       0  5375.8      .1       0  5460.4     .05       0
  5688.4     .07       0  5810.5     .05       0  6085.3     .07       0
Bank Sta=5034.9,5041.4
XS Rating Curve= 0 ,0
Exp/Cntr=0.3,0.1

Type RM Length L Ch R = 1 ,6292    ,476,476,476
BEGIN DESCRIPTION:
TRIB 9 TO SPRING CREEK 9.0
END DESCRIPTION:
XS GIS Cut Line= 3
        2573775.       13533975.        2572975.       13533175.
      2572174.99     13532624.99
#Sta/Elev= 30
  3864.2  155.68  4019.8  150.65    4147  147.24  4161.2  146.48  4401.6  140.35
  4571.3  137.78  4627.9  136.47  4813.3  135.65  4891.8  135.89  4967.3  136.36
  4998.6  135.93  5005.8   135.2  5006.3   134.7  5011.9   134.7  5012.4   135.2
  5074.7  136.41  5110.6  136.09  5140.4  136.56  5161.3  136.24    5412  136.73
    5484  137.42  5555.7  139.09  5564.5  139.72  5600.4  140.14  5636.6  141.61
  5749.9  144.67  5830.4  147.95  5887.2  148.91  5964.5  151.42  5966.4  151.42
#Mann= 8 ,-1 , 0
  3864.2     .05       0  4813.3      .1       0  4891.8    .035       0
  5005.8    .035       0  5012.4    .035       0    5412     .07       0
  5636.6     .05       0  5964.5     .07       0
Bank Sta=5005.8,5012.4
XS Rating Curve= 0 ,0
Exp/Cntr=0.3,0.1

Type RM Length L Ch R = 1 ,5816    ,430,430,430
BEGIN DESCRIPTION:
TRIB 9 TO SPRING CREEK 8.0
END DESCRIPTION:
XS GIS Cut Line= 3
      2574325.02     13534025.02        2573225.       13532825.
      2572474.99     13532024.99
#Sta/Elev= 30
  3371.5  165.61  3435.3  163.71  3456.3  164.09  3477.9   162.3  3534.3  160.93
  3604.9  157.87  3654.9  156.86    3796  151.81  3966.3  146.53  4001.4  146.26
  4100.7  143.18  4121.6  143.22  4249.3  140.32  4270.3  140.43    4327     139
  4553.3  135.51  4754.7  135.19  4871.8  134.69  4946.4  134.53  4946.9  134.03
  4952.6  134.03  4953.1  134.53    4964  135.19  5012.8     135  5090.3  135.46
  5367.8  136.63  5629.3  139.52  5827.1  142.84  5997.1   146.9    6096   150.5
#Mann= 9 ,-1 , 0
  3371.5     .12       0    3796     .05       0  4754.7      .1       0
  4871.8    .035       0  4946.4     .05       0  4953.1    .035       0
  5012.8    .035       0  5090.3     .07       0  5367.8     .05       0
Bank Sta=4946.4,4953.1
XS Rating Curve= 0 ,0
Exp/Cntr=0.3,0.1

Type RM Length L Ch R = 1 ,5386    ,429,429,429
BEGIN DESCRIPTION:
TRIB 9 TO SPRING CREEK 7.0
END DESCRIPTION:
XS GIS Cut Line= 3
      2574324.98     13533874.96        2573525.       13532675.
      2572524.99     13531574.99
#Sta/Elev= 30
  3539.4  161.07  3575.4  159.27  3677.8  156.13  4015.6  145.49  4108.7  144.26
  4159.8  142.51    4283   140.9    4304  139.68  4368.6  139.15  4463.3  137.03
  4659.1  135.05  4812.6  134.43  4964.7  134.01  4965.2  133.51  4971.5  134.01
  4971.9  134.03  5017.1  134.81  5138.3  134.33  5261.6  137.09  5398.3  140.52
    5422  140.56  5540.7  142.88  5569.1  142.24  5583.3  143.27  5632.6  142.93
  5675.2  143.82  5738.7  143.17  5937.4  145.18  6227.3   153.2  6468.2  158.98
#Mann= 11 ,-1 , 0
  3539.4     .12       0  3677.8     .05       0  4659.1    .035       0
  4812.6      .1       0  4964.7    .035       0  4971.5      .1       0
  4971.9    .035       0  5138.3      .1       0  5261.6     .05       0
  5398.3     .07       0    5422     .05       0
Bank Sta=4964.7,4971.5
XS Rating Curve= 0 ,0
Exp/Cntr=0.3,0.1

Type RM Length L Ch R = 1 ,4957    ,444,444,444
BEGIN DESCRIPTION:
TRIB 9 TO SPRING CREEK 6.0
END DESCRIPTION:
XS GIS Cut Line= 3
      2574924.99       13532125.        2573725.       13532525.
      2572524.96     13531524.97
#Sta/Elev= 30
  3743.5   151.1  3796.2  149.64  3838.4  150.06  3891.1  147.19  3922.7  147.28
  3964.8  145.33  3985.9  145.86  4049.2  142.38  4112.4  141.42  4154.6   138.9
  4228.4  138.76    4260  136.98  4333.8  135.54  4460.3  134.46  4502.4  135.18
  4783.6  134.07  4784.1  133.57  4790.5  134.07  4913.9  134.41  4952.3  134.19
  5157.8  134.47    5285   135.4    5402  139.26  5520.8  143.23  5633.2   145.7
  5796.6  143.88  6002.3  145.29  6244.4  150.62  6349.8   154.5  6570.5   159.7
#Mann= 8 ,-1 , 0
  3743.5     .05       0  4783.6    .035       0  4790.5     .05       0
  4913.9      .1       0  4952.3    .035       0  5157.8     .05       0
    5402     .07       0  5520.8     .05       0
Bank Sta=4783.6,4790.5
XS Rating Curve= 0 ,0
Exp/Cntr=0.3,0.1

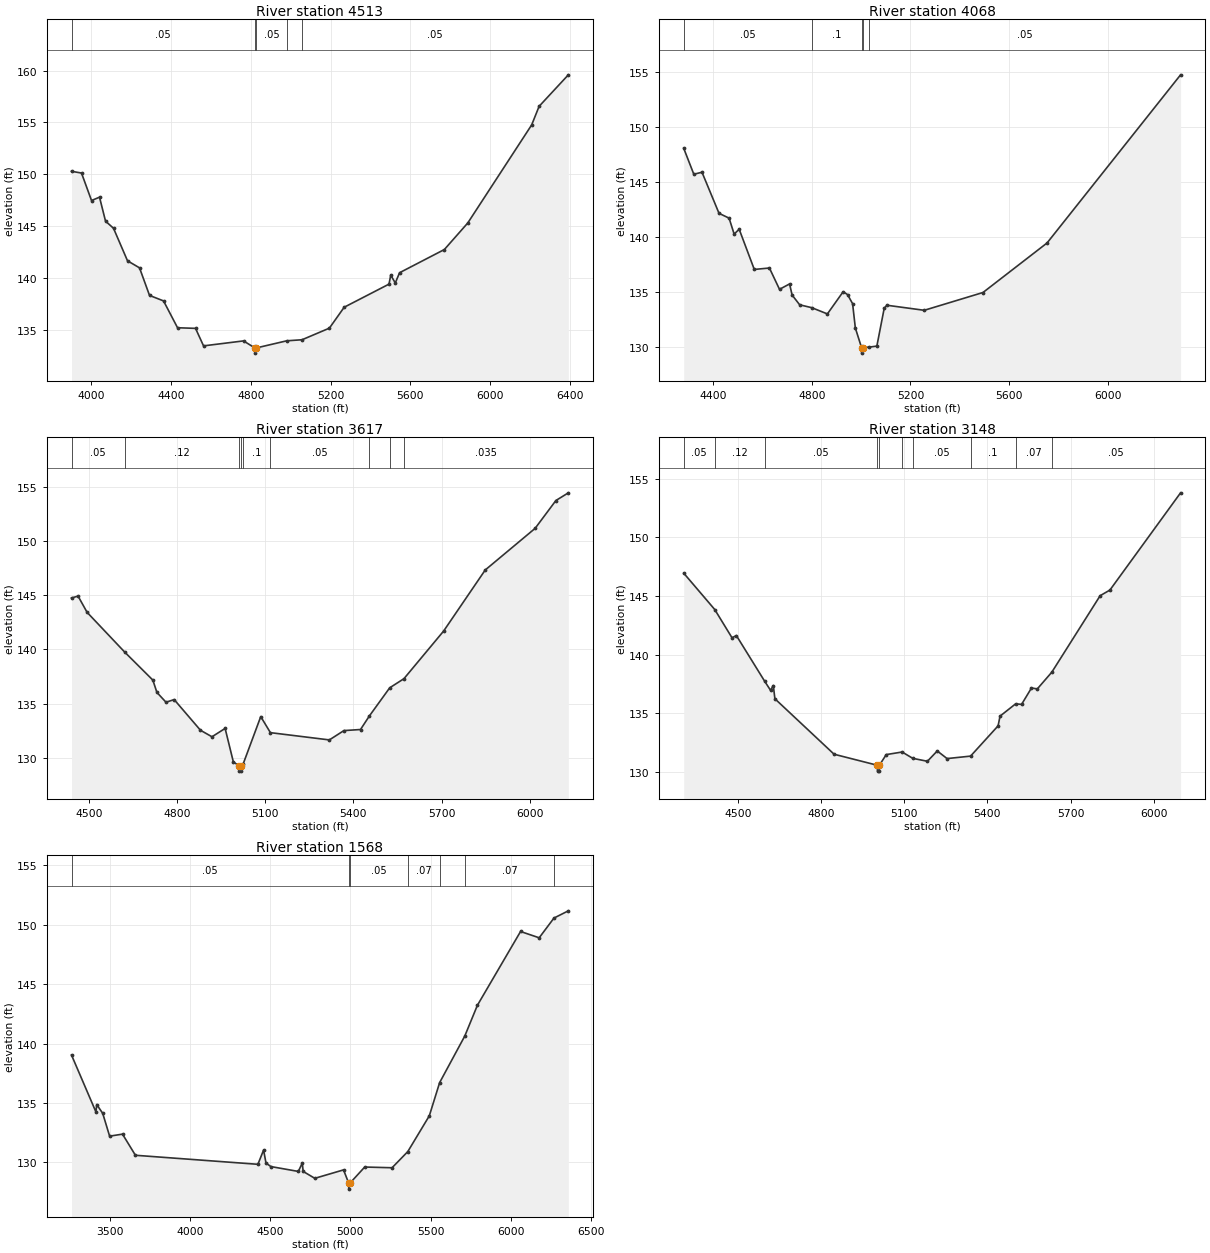
Type RM Length L Ch R = 1 ,4513    ,445,445,445
BEGIN DESCRIPTION:
TRIB 9 TO SPRING CREEK 5.0
END DESCRIPTION:
XS GIS Cut Line= 3
      2574874.98       13532025.        2573775.       13532125.
      2572574.96     13531424.98
#Sta/Elev= 30
  3899.9  150.29  3950.1  150.12  4000.3  147.47  4040.5  147.79  4070.6  145.48
  4110.7  144.79    4181  141.65  4241.3  140.97  4291.5  138.31  4361.8  137.78
  4432.1  135.19  4522.4  135.13  4562.6  133.44  4763.4  133.92  4820.2  133.24
  4820.7  132.74  4827.1  133.24  4980.5  133.93  5056.9  134.03  5194.2  135.15
  5268.6  137.17  5493.5   139.4  5502.2  140.27    5525  139.51  5546.5   140.5
  5771.4  142.74  5888.8   145.3  6209.7  154.77  6246.9  156.56  6393.7   159.6
#Mann= 5 ,-1 , 0
  3899.9     .05       0  4820.2     .05       0  4827.1     .05       0
  4980.5     .07       0  5056.9     .05       0
Bank Sta=4820.2,4827.1
XS Rating Curve= 0 ,0
Exp/Cntr=0.3,0.1

Type RM Length L Ch R = 1 ,4068    ,451,451,451
BEGIN DESCRIPTION:
TRIB 9 TO SPRING CREEK 4.0
END DESCRIPTION:
XS GIS Cut Line= 3
      2574724.98       13531925.        2574025.       13531775.
      2572824.97     13531274.99
#Sta/Elev= 30
  4280.2  148.08  4321.1  145.72  4354.3   145.9  4423.4  142.16  4464.3  141.72
  4484.7  140.27  4505.2  140.71  4566.5  137.05  4627.9  137.18  4668.8  135.24
  4709.7  135.73  4719.9  134.72  4750.6  133.83  4799.4  133.57  4863.1     133
    4927  135.02  4944.9  134.76  4965.4  133.93  4976.5  131.72  5001.7  129.93
  5002.2  129.43  5008.9  129.93  5033.4  129.98  5063.8  130.07  5093.6  133.51
  5104.4  133.79  5256.1  133.33  5494.4  134.95  5754.4  139.46  6296.1  154.77
#Mann= 5 ,-1 , 0
  4280.2     .05       0  4799.4      .1       0  5001.7     .05       0
  5008.9      .1       0  5033.4     .05       0
Bank Sta=5001.7,5008.9
XS Rating Curve= 0 ,0
Exp/Cntr=0.3,0.1

Type RM Length L Ch R = 1 ,3617    ,469,469,469
BEGIN DESCRIPTION:
TRIB 9 TO SPRING CREEK 3.0
END DESCRIPTION:
XS GIS Cut Line= 3
      2574724.96     13531674.98        2574225.       13531425.
      2573425.03     13530625.03
#Sta/Elev= 30
    4441  144.75  4463.3  144.92  4494.1  143.42  4621.8  139.76  4717.7  137.17
  4731.6  136.03  4762.4  135.13  4790.3  135.37  4879.8  132.54  4918.9  131.94
  4963.6  132.71  4991.6  129.62  5010.5  129.27    5011  128.77  5017.3  128.77
  5017.8  129.27  5024.4  129.39  5084.8   133.8  5117.7  132.32  5318.2  131.65
  5367.7  132.51  5424.2  132.61  5454.6  133.87  5523.6  136.46    5572   137.3
  5707.1   141.7  5848.5  147.33  6018.2  151.17  6088.9  153.74  6131.3  154.45
#Mann= 9 ,-1 , 0
    4441     .05       0  4621.8     .12       0  5010.5     .05       0
  5017.8     .12       0  5024.4      .1       0  5117.7     .05       0
  5454.6    .035       0  5523.6     .07       0    5572    .035       0
Bank Sta=5010.5,5017.8
XS Rating Curve= 0 ,0
Exp/Cntr=0.3,0.1

Type RM Length L Ch R = 1 ,3148    ,1580,1580,1580
BEGIN DESCRIPTION:
TRIB 9 TO SPRING CREEK 2.0
END DESCRIPTION:
XS GIS Cut Line= 3
      2574875.01     13531675.02        2574525.       13531075.
      2573725.02     13530325.02
#Sta/Elev= 30
  4305.4  146.94  4417.2  143.84  4479.5  141.43  4495.2  141.62  4597.3  137.72
  4618.4  136.95  4628.3  137.36  4634.1  136.23  4847.5   131.5  5003.5  130.56
    5004  130.06  5010.3  130.06  5010.8  130.56  5035.5  131.47  5092.8  131.69
  5131.2  131.15  5183.9   130.9  5219.4  131.78  5254.8  131.13  5339.5  131.34
  5438.7  133.92  5445.8  134.75  5502.1   135.8  5523.4  135.75  5559.1  137.15
  5580.1  137.07  5632.5   138.5  5806.7  145.02  5841.9   145.5  6096.6  153.79
#Mann= 10 ,-1 , 0
  4305.4     .05       0  4417.2     .12       0  4597.3     .05       0
  5003.5     .05       0  5010.8     .05       0  5092.8      .1       0
  5131.2     .05       0  5339.5      .1       0  5502.1     .07       0
  5632.5     .05       0
Bank Sta=5003.5,5010.8
XS Rating Curve= 0 ,0
Exp/Cntr=0.3,0.1

Type RM Length L Ch R = 1 ,1568    ,0,0,0
BEGIN DESCRIPTION:
TRIB 9 TO SPRING CREEK 1.0
END DESCRIPTION:
XS GIS Cut Line= 4
      2575020.67     13531358.12      2575206.71     13529877.34
      2574859.49     13529692.88      2573825.03     13530324.98
#Sta/Elev= 30
  3261.2  139.03  3413.4  134.24  3418.4  134.86  3455.8  134.12  3498.8   132.2
  3579.2  132.37  3659.7  130.59  4423.4  129.83  4458.9  131.03  4473.8  129.94
    4504  129.64  4675.3  129.23  4700.1  129.93  4705.6  129.23  4778.2  128.65
  4957.4  129.36  4989.6  128.24  4990.1  127.74  4997.2  128.24  5089.3   129.6
  5259.9  129.54    5358   130.9  5492.1  133.91  5556.6  136.71  5713.4  140.63
  5792.1  143.22  6061.1  149.43  6177.2   148.9  6269.3  150.56  6359.1  151.17
#Mann= 7 ,-1 , 0
  3261.2     .05       0  4989.6     .05       0  4997.2     .05       0
    5358     .07       0  5556.6     .05       0  5713.4     .07       0
  6269.3     .05       0
Bank Sta=4989.6,4997.2
XS Rating Curve= 0 ,0
Exp/Cntr=0.3,0.1

Chan Stop Cuts=-1
Use User Specified Reach Order=0
Composite Channel Slope=5