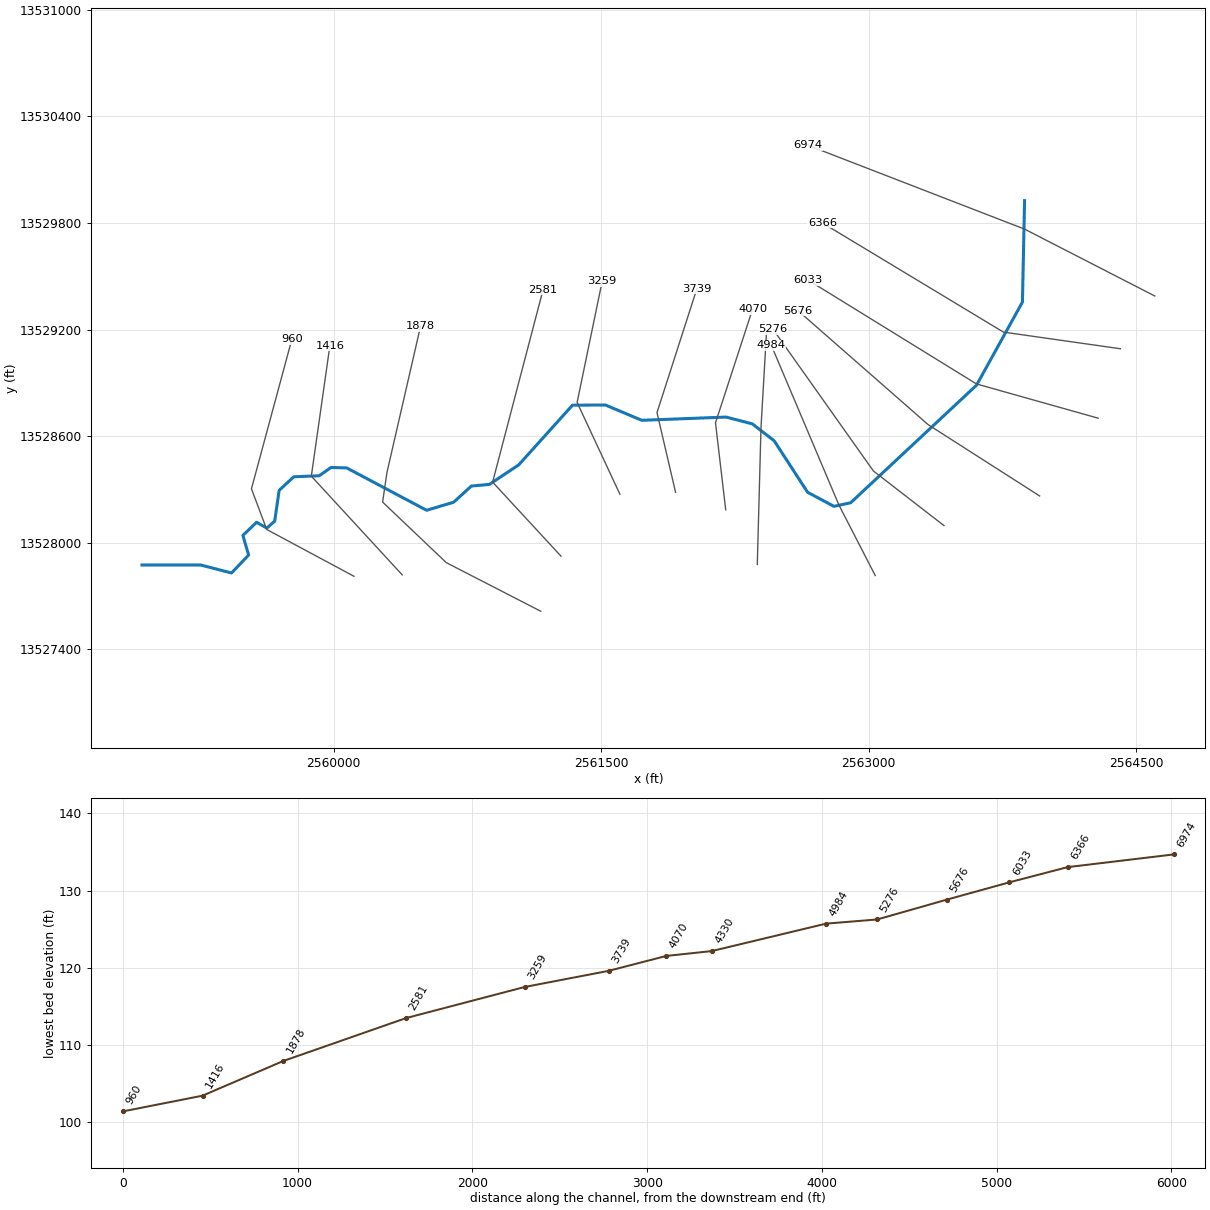
--- TRIB 9_1 TO GUADALUPE RIVER.prj (project) ---

Proj Title=TRIB 9_1 TO GUADALUPE RIVER Base Level Engineering
Current Plan=p01
Default Exp/Contr=0.3,0.1
English Units
Geom File=g01
Flow File=f01
Plan File=p01
Y Axis Title=Elevation
X Axis Title(PF)=Main Channel Distance
X Axis Title(XS)=Station
BEGIN DESCRIPTION:
TRIB 9_1 TO GUADALUPE RIVER
END DESCRIPTION:
DSS Export Rating Curves= 0
DSS Export Rating Curve Sorted= 0
DSS Export Volume Flow Curves= 0
DXF OffsetX= 0
DXF OffsetY= 0
DXF ScaleX= 1
DXF ScaleY= 10

--- TRIB 9_1 TO GUADALUPE RIVER.p01 (plan) ---

Plan Title=Multiple Run
Short Identifier=Multiple
Geom File=g01
Flow File=f01
Subcritical Flow
K Sum by GR= 0
Std Step Tol= 0.01
Critical Tol= 0.01
Num of Std Step Trials= 20
Max Error Tol= 0.3
Flow Tol Ratio= 0.001
Split Flow NTrial= 30
Split Flow Tol= 0.02
Split Flow Ratio= 0.02
Log Output Level= 0
Friction Slope Method= 1
Unsteady Friction Slope Method= 2
Unsteady Bridges Friction Slope Method= 1
Parabolic Critical Depth
Global Vel Dist=  1 , 1 , 1
Global Log Level= 0
CheckData=True
Encroach Param= -1, 0, 0, 0
BEGIN DESCRIPTION:
Multiple Run
END DESCRIPTION:

--- TRIB 9_1 TO GUADALUPE RIVER.f01 (steady flow) ---

Flow Title=Multiple
Number of Profiles=7
Profile Names=10-year,25-year,50-year,1pct_min,100-year,1pct_plu,500-year
River Rch & RM= TRIB 9_1 TO GUAD,Reach-1,6974
     366     552     709     441     879    1754    1335
River Rch & RM= TRIB 9_1 TO GUAD,Reach-1,6366
     463     710     922     580    1157    2308    1798
River Rch & RM= TRIB 9_1 TO GUAD,Reach-1,4070
     738    1172    1558    1001    1997    3985    3243
Boundary for River Rch & Prof#=TRIB 9_1 TO GUAD,Reach-1,1
Up Type=0
Dn Type=3
Dn Slope=0.005
Boundary for River Rch & Prof#=TRIB 9_1 TO GUAD,Reach-1,2
Up Type=0
Dn Type=3
Dn Slope=0.005
Boundary for River Rch & Prof#=TRIB 9_1 TO GUAD,Reach-1,3
Up Type=0
Dn Type=3
Dn Slope=0.005
Boundary for River Rch & Prof#=TRIB 9_1 TO GUAD,Reach-1,4
Up Type=0
Dn Type=3
Dn Slope=0.005
Boundary for River Rch & Prof#=TRIB 9_1 TO GUAD,Reach-1,5
Up Type=0
Dn Type=3
Dn Slope=0.005
Boundary for River Rch & Prof#=TRIB 9_1 TO GUAD,Reach-1,6
Up Type=0
Dn Type=3
Dn Slope=0.005
Boundary for River Rch & Prof#=TRIB 9_1 TO GUAD,Reach-1,7
Up Type=0
Dn Type=3
Dn Slope=0.005

--- TRIB 9_1 TO GUADALUPE RIVER.g01 (geometry) ---

Geom Title=Existing Conditions
Program Version=4.10

River Reach=TRIB 9_1 TO GUAD,Reach-1
Reach XY= 30
        2563875.       13529925.      2563862.97     13529354.24
      2563605.58     13528886.92      2562899.72     13528225.38
      2562806.17     13528205.12      2562657.97      13528284.5
       2562470.7     13528574.01      2562348.17     13528669.26
       2562201.1     13528707.42      2561728.35      13528689.2
        2561525.       13528775.      2561340.03     13528774.68
      2561038.21     13528438.63       2560873.5     13528328.63
      2560772.58     13528319.46       2560673.5     13528228.62
      2560521.68     13528183.04      2560073.42     13528421.33
      2559985.55      13528423.9      2559919.06     13528377.27
      2559776.46     13528371.46      2559694.59     13528295.21
      2559669.53     13528122.01      2559625.24     13528082.46
       2559568.3     13528115.69       2559491.3     13528041.77
      2559523.35     13527931.04      2559427.44     13527830.39
      2559254.97     13527874.93        2558925.       13527875.

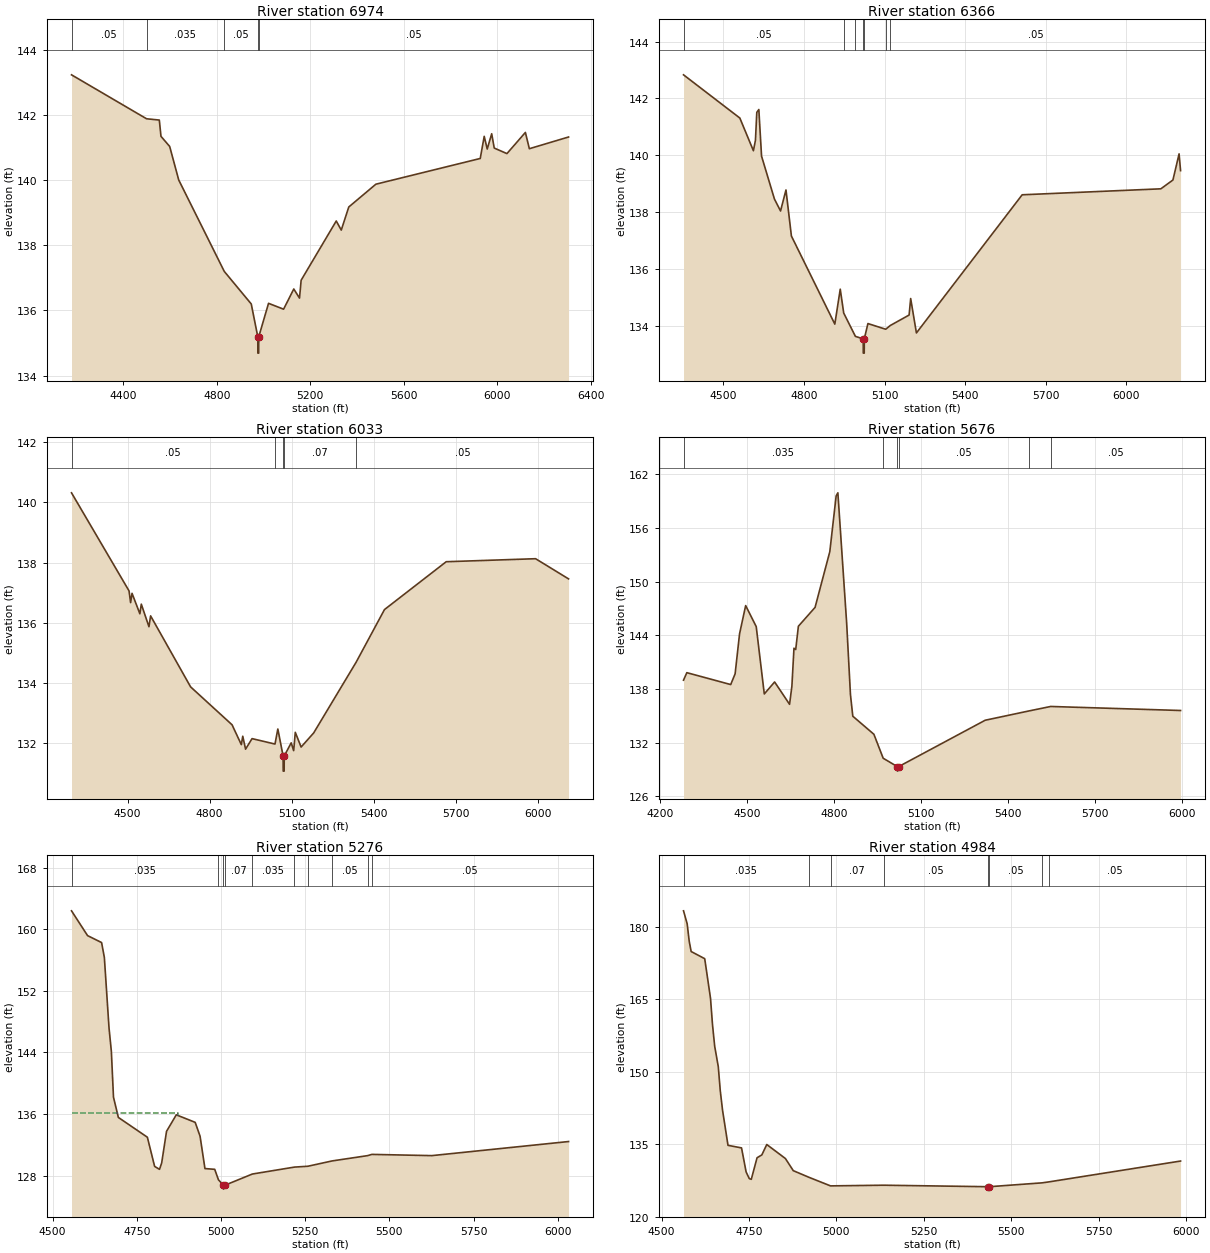
Type RM Length L Ch R = 1 ,6974    ,608,608,608
BEGIN DESCRIPTION:
TRIB 9-1 TO GUADALUPE RIVER 6.0
END DESCRIPTION:
XS GIS Cut Line= 3
      2564605.18     13529388.67      2563875.27     13529764.76
      2562658.64     13530237.09
#Sta/Elev= 30
  4178.9  143.24  4499.9  141.89  4554.5  141.85  4561.6  141.35  4598.8  141.04
  4637.5  140.01  4832.4   137.2  4947.8   136.2  4975.8  135.19  4976.1  134.69
  4979.6  134.69  4979.8  135.19  5021.7  136.22  5086.1  136.04  5129.7  136.66
  5154.2  136.38  5161.2  136.93  5311.4  138.75  5332.8  138.47    5365  139.18
  5480.9  139.88  5927.3  140.67  5944.3  141.35  5957.2  140.96  5976.3  141.43
  5987.2  140.99  6041.5  140.82  6120.5  141.47  6137.4  140.97  6305.1  141.33
#Mann= 5 ,-1 , 0
  4178.9     .05       0  4499.9    .035       0  4832.4     .05       0
  4975.8     .05       0  4979.8     .05       0
Bank Sta=4975.8,4979.8
XS Rating Curve= 0 ,0
Exp/Cntr=0.3,0.1

Type RM Length L Ch R = 1 ,6366    ,333,333,333
BEGIN DESCRIPTION:
Mapping XS 1daf5b55
END DESCRIPTION:
XS GIS Cut Line= 3
      2564412.46     13529091.79      2563756.22     13529185.54
      2562740.68     13529800.07
#Sta/Elev= 30
    4352  142.83  4561.6  141.31  4612.1  140.16  4619.7  140.53  4624.7  141.51
  4632.3  141.61  4642.4  139.97  4690.4  138.46  4713.1  138.04  4733.3  138.78
  4753.5  137.16  4915.1  134.06  4935.3  135.29  4948.2  134.45  4991.7  133.63
  5020.8  133.54  5021.1  133.04  5024.6  133.04  5024.8  133.54  5038.3  134.08
  5104.6  133.88  5121.2  134.01  5191.6  134.38  5197.4  134.96  5218.8  133.75
  5612.4  138.61  6128.5  138.82  6173.5  139.13  6196.4  140.05  6201.9  139.46
#Mann= 7 ,-1 , 0
    4352     .05       0  4948.2     .12       0  4991.7     .05       0
  5020.8     .05       0  5024.8     .05       0  5104.6     .12       0
  5121.2     .05       0
Bank Sta=5020.8,5024.8
XS Rating Curve= 0 ,0
Exp/Cntr=0.3,0.1

Type RM Length L Ch R = 1 ,6033    ,357,357,357
BEGIN DESCRIPTION:
Mapping XS 7248d1e6
END DESCRIPTION:
XS GIS Cut Line= 3
      2564287.51     13528701.15      2563605.18     13528893.87
      2562662.49      13529477.2
#Sta/Elev= 30
  4294.8  140.32  4505.2  137.06  4510.9  136.67  4516.1  136.98  4544.8   136.3
    4550  136.62    4578  135.87    4584  136.23  4730.3  133.87  4881.9  132.61
  4915.8  131.95    4921  132.23  4931.3   131.8    4955  132.15  5038.9  131.97
  5049.3  132.47  5068.6  131.57  5068.9  131.07  5072.4  131.07  5072.6  131.57
  5098.1  132.01  5107.2  131.75  5113.1  132.36  5134.4  131.87  5180.4  132.34
  5335.6  134.69  5439.3  136.44    5665  138.03  5991.9  138.13  6112.4  137.46
#Mann= 5 ,-1 , 0
  4294.8     .05       0  5038.9     .07       0  5068.6     .05       0
  5072.6     .07       0  5335.6     .05       0
Bank Sta=5068.6,5072.6
XS Rating Curve= 0 ,0
Exp/Cntr=0.3,0.1

Type RM Length L Ch R = 1 ,5676    ,400,400,400
BEGIN DESCRIPTION:
Mapping XS 68162b8e
END DESCRIPTION:
XS GIS Cut Line= 3
      2563959.31     13528263.69      2563334.35     13528664.71
      2562605.16     13529305.35
#Sta/Elev= 30
  4281.8     139  4293.2  139.84  4444.5  138.51  4459.7  139.72  4474.9  144.18
    4496  147.34  4532.4  144.99  4560.2  137.46  4595.8   138.8  4647.3   136.3
  4655.3  138.32  4662.5  142.57  4668.5  142.43  4677.7  145.03  4735.2  147.14
    4786  153.37  4807.9  159.61  4813.8  159.95  4844.2  145.33  4857.2  137.38
  4865.3  134.97    4938  132.95    4970  130.27    5019  129.33  5019.3  128.83
    5023  129.33  5321.6  134.52    5471  135.55  5547.5  136.06    5995  135.61
#Mann= 6 ,-1 , 0
  4281.8    .035       0    4970     .05       0    5019     .05       0
    5023     .05       0    5471    .035       0  5547.5     .05       0
Bank Sta=5019,5023
XS Rating Curve= 0 ,0
Exp/Cntr=0.3,0.1

Type RM Length L Ch R = 1 ,5276    ,292,292,292
BEGIN DESCRIPTION:
Mapping XS fbbb9c94
END DESCRIPTION:
XS GIS Cut Line= 3
      2563422.89       13528097.      2563027.06     13528404.29
      2562464.97     13529200.58
#Sta/Elev= 30
  4556.1  162.39  4603.8  159.17  4645.4  158.27  4653.6  156.34  4667.4  147.22
  4674.4  144.14  4680.7  138.19  4695.2  135.56  4781.3  132.99  4802.9   129.2
  4817.4  128.82  4823.8  129.65  4838.2  133.75  4867.2   135.9  4923.3  134.92
  4937.8  133.12  4952.3  128.92  4981.3  128.82  4992.4  127.46  5007.2  126.75
  5007.4  126.25  5011.2  126.75    5093  128.21  5217.9  129.11  5257.8  129.22
  5329.7  129.91  5435.3   130.6    5448  130.76  5625.8   130.6  6031.9  132.43
#Mann= 10 ,-1 , 0
  4556.1    .035       0  4992.4     .07       0  5007.2     .05       0
  5011.2     .07       0    5093    .035       0  5217.9     .05       0
  5257.8    .035       0  5329.7     .05       0  5435.3    .035       0
    5448     .05       0
#XS Ineff= 2 , 0
       0  4873.5  136.14               0
Permanent Ineff=
       F       F
Bank Sta=5007.2,5011.2
XS Rating Curve= 0 ,0
Exp/Cntr=0.3,0.1

Type RM Length L Ch R = 1 ,4984    ,654,654,654
BEGIN DESCRIPTION:
Mapping XS 50136e0b
END DESCRIPTION:
XS GIS Cut Line= 3
      2563037.49     13527815.72      2562834.35     13528211.58
      2562454.69     13529111.32
#Sta/Elev= 30
  4562.8  183.29  4573.2  180.61    4579  177.04  4584.6  174.87  4623.4  173.39
    4640  165.19  4645.6  159.81  4651.9  155.28  4662.2  151.05  4667.8  146.13
  4674.4  142.04    4690  134.77  4728.7  134.24  4741.8  129.27  4750.9  127.88
  4756.6  127.74  4773.1   132.2  4786.8  132.79  4800.9  134.94  4854.2  132.04
  4876.7  129.53  4920.7  128.18  4983.2  126.38    5135  126.52  5433.3  126.21
  5433.6  125.71  5437.3  126.21  5588.5  127.01    5607   127.2  5984.3  131.52
#Mann= 8 ,-1 , 0
  4562.8    .035       0  4920.7     .05       0  4983.2     .07       0
    5135     .05       0  5433.3     .05       0  5437.3     .05       0
  5588.5    .035       0    5607     .05       0
#XS Ineff= 2 , 0
       0  4800.9  134.94               0
Permanent Ineff=
       F       F
Bank Sta=5433.3,5437.3
XS Rating Curve= 0 ,0
Exp/Cntr=0.3,0.1

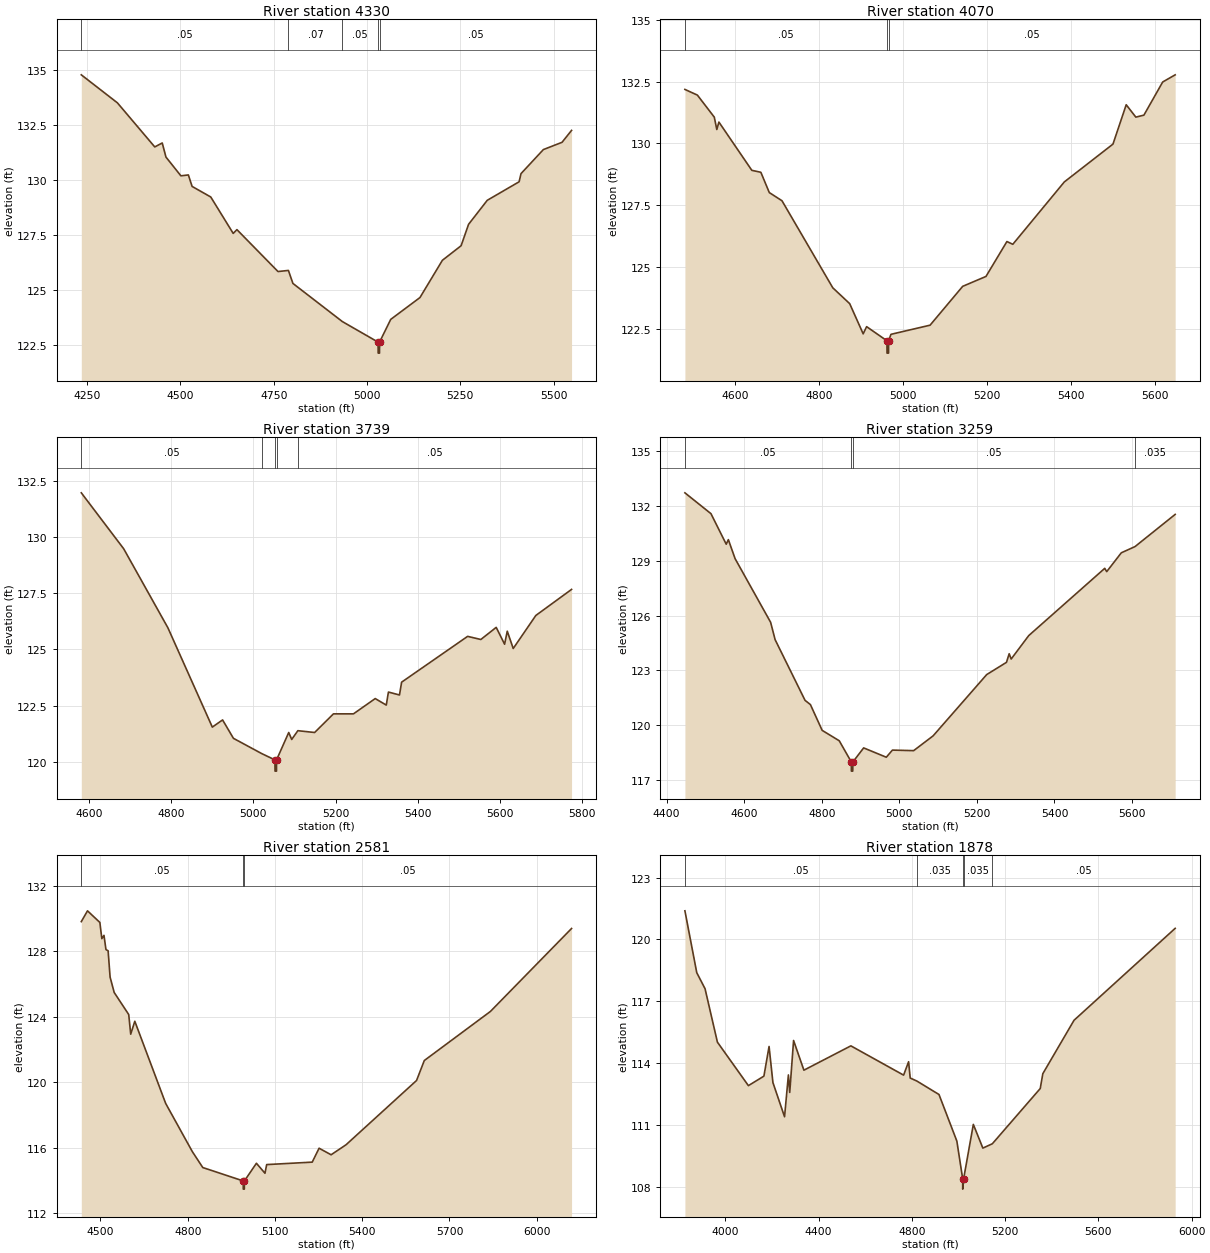
Type RM Length L Ch R = 1 ,4330    ,260,260,260
BEGIN DESCRIPTION:
Mapping XS 8ce3a5ce
END DESCRIPTION:
XS GIS Cut Line= 3
      2562376.02      13527878.3      2562396.85     13528649.08
      2562428.08     13529190.41
#Sta/Elev= 30
  4234.6  134.77  4331.3   133.5  4431.4   131.5  4451.4  131.68  4461.4  131.04
  4501.4  130.19  4521.4  130.23  4531.4  129.71  4581.4  129.23  4641.5  127.58
  4651.5  127.75  4761.5  125.85  4789.4   125.9  4801.5  125.31    4934  123.58
  5029.6  122.65  5029.9  122.15  5033.4  122.15  5033.6  122.65  5063.5  123.68
  5141.8  124.67  5201.9  126.36    5252  127.02    5272  127.99  5322.1  129.08
  5407.4  129.92  5412.5  130.29  5472.4  131.38  5522.4  131.71  5547.9  132.25
#Mann= 5 ,-1 , 0
  4234.6     .05       0  4789.4     .07       0    4934     .05       0
  5029.6     .05       0  5033.6     .05       0
Bank Sta=5029.6,5033.6
XS Rating Curve= 0 ,0
Exp/Cntr=0.3,0.1

Type RM Length L Ch R = 1 ,4070    ,331,331,331
BEGIN DESCRIPTION:
Mapping XS 5a433f67
END DESCRIPTION:
XS GIS Cut Line= 3
      2562198.93     13528185.53      2562141.64     13528675.12
      2562349.98     13529315.77
#Sta/Elev= 30
  4481.2  132.18  4510.9  131.95  4551.1  131.06  4557.1  130.56  4562.1  130.86
  4640.4  128.91  4661.9  128.83    4682  128.01  4712.2  127.68  4833.1  124.16
  4873.3  123.52  4905.4   122.3  4913.6  122.59  4961.9  122.02  4962.2  121.52
  4965.7  121.52  4965.9  122.02  4971.5  122.28  5064.6  122.65  5142.2  124.22
  5197.6  124.62  5247.4  126.03  5261.5  125.92    5384  128.44  5499.8  129.97
  5531.3  131.56  5554.2  131.06  5573.4  131.14  5618.1  132.48  5647.8  132.77
#Mann= 3 ,-1 , 0
  4481.2     .05       0  4961.9     .05       0  4965.9     .05       0
Bank Sta=4961.9,4965.9
XS Rating Curve= 0 ,0
Exp/Cntr=0.3,0.1

Type RM Length L Ch R = 1 ,3739    ,480,480,480
BEGIN DESCRIPTION:
Mapping XS 0a6e5448
END DESCRIPTION:
XS GIS Cut Line= 3
      2561917.67     13528284.54      2561813.51     13528732.41
      2562037.41     13529430.14
#Sta/Elev= 30
  4581.3  131.97  4684.4  129.48    4792  125.96    4900  121.54    4925  121.86
  4951.4  121.04  5020.3  120.36  5052.3  120.08  5052.6  119.58  5056.1  119.58
  5056.3  120.08  5085.9   121.3  5093.1  120.99  5108.1  121.38  5148.9   121.3
  5194.7  122.13  5243.4  122.13  5296.3  122.81  5323.2  122.52  5328.4   123.1
  5355.3  122.97  5360.5  123.54  5521.1  125.58  5553.2  125.44  5590.6  125.98
    5611  125.23  5617.5  125.81    5632  125.04    5687  126.51  5773.9  127.67
#Mann= 5 ,-1 , 0
  4581.3     .05       0  5020.3     .07       0  5052.3     .05       0
  5056.3     .07       0  5108.1     .05       0
Bank Sta=5052.3,5056.3
XS Rating Curve= 0 ,0
Exp/Cntr=0.3,0.1

Type RM Length L Ch R = 1 ,3259    ,678,678,678
BEGIN DESCRIPTION:
Mapping XS 22883f49
END DESCRIPTION:
XS GIS Cut Line= 3
      2561605.19     13528274.07       2561365.6     13528789.71
      2561506.02       13529471.
#Sta/Elev= 30
  4447.1  132.71  4514.3  131.57  4553.6   129.9  4559.1  130.15  4576.5  129.11
  4668.1  125.63  4679.7  124.68  4756.9  121.36  4770.7  121.13    4801  119.72
  4845.1  119.15  4876.2  117.99  4876.4  117.49  4879.9  117.49  4880.2  117.99
    4908  118.76  4966.4  118.25  4982.2  118.64  5036.9  118.61  5087.2  119.42
  5225.3  122.77  5276.3  123.44  5283.3  123.91  5288.4  123.62  5333.6   124.9
  5529.7  128.58  5534.8   128.4  5572.4  129.43  5607.8  129.77  5711.3  131.53
#Mann= 4 ,-1 , 0
  4447.1     .05       0  4876.2     .05       0  4880.2     .05       0
  5607.8    .035       0
Bank Sta=4876.2,4880.2
XS Rating Curve= 0 ,0
Exp/Cntr=0.3,0.1

Type RM Length L Ch R = 1 ,2581    ,703,703,703
BEGIN DESCRIPTION:
TRIB 9-1 TO GUADALUPE RIVER 5.0
END DESCRIPTION:
XS GIS Cut Line= 3
        2561275.       13527925.      2560891.74     13528341.49
      2561174.99     13529424.98
#Sta/Elev= 30
    4434  129.81  4455.3  130.47  4497.8  129.76  4504.6  128.77    4512  128.97
  4518.8   128.1  4526.2  128.03    4533  126.42  4547.1  125.48  4597.1  124.13
  4603.9  122.93    4618  123.72  4724.1   118.7  4815.9  115.75  4851.7  114.78
  4990.9  113.96  4991.1  113.46  4994.6  113.46  4994.9  113.96  5036.2  115.04
  5065.6  114.43  5071.5  114.96  5228.1  115.11  5251.7  115.96    5293  115.56
  5344.3  116.17  5586.9   120.1  5613.5  121.32  5840.9  124.32  6119.9  129.39
#Mann= 3 ,-1 , 0
    4434     .05       0  4990.9     .05       0  4994.9     .05       0
Bank Sta=4990.9,4994.9
XS Rating Curve= 0 ,0
Exp/Cntr=0.3,0.1

Type RM Length L Ch R = 1 ,1878    ,462,462,462
BEGIN DESCRIPTION:
TRIB 9-1 TO GUADALUPE RIVER 4.0
END DESCRIPTION:
XS GIS Cut Line= 5
      2561161.75     13527614.99      2560631.82     13527888.45
      2560274.74     13528229.23      2560299.16      13528396.1
      2560487.77     13529219.19
#Sta/Elev= 30
  3826.4  121.39  3877.2  118.39  3912.8  117.61  3965.8  115.02  4098.7  112.91
  4165.2  113.37  4187.4  114.81  4203.9  113.06  4253.8   111.4  4270.3  113.43
    4276  112.58  4292.5   115.1  4336.8  113.66  4538.3  114.84  4764.5  113.42
  4785.9  114.07  4792.8  113.28  4821.8  113.13  4916.3  112.48  4992.9  110.22
  5017.9  108.39  5018.1  107.89    5022  108.39  5063.6  111.03  5104.4  109.88
  5145.1  110.09  5350.6  112.77  5361.7  113.49  5495.5  116.08  5929.4  120.54
#Mann= 5 ,-1 , 0
  3826.4     .05       0  4821.8    .035       0  5017.9    .035       0
    5022    .035       0  5145.1     .05       0
Bank Sta=5017.9,5022
XS Rating Curve= 0 ,0
Exp/Cntr=0.3,0.1

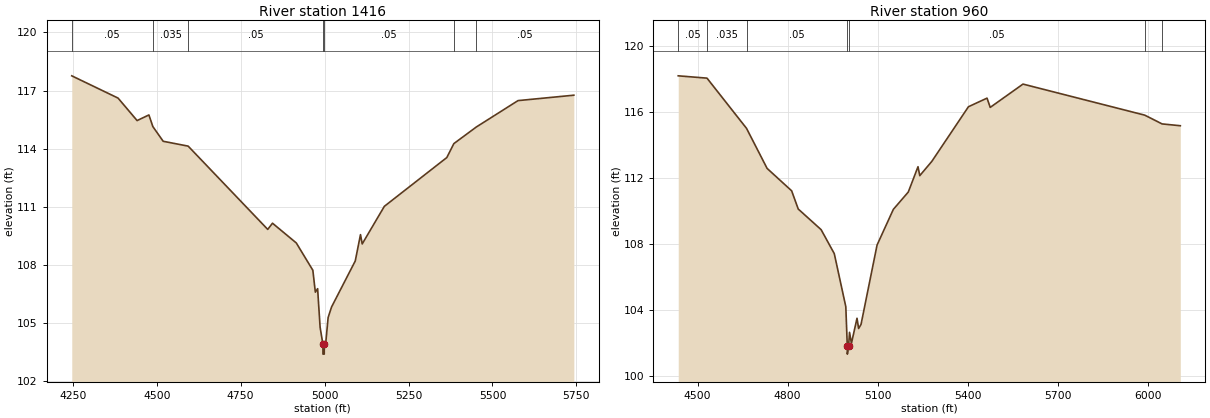
Type RM Length L Ch R = 1 ,1416    ,456,456,456
BEGIN DESCRIPTION:
TRIB 9-1 TO GUADALUPE RIVER 3.0
END DESCRIPTION:
XS GIS Cut Line= 3
      2560384.52     13527819.82        2559875.       13528375.
      2559979.14     13529109.61
#Sta/Elev= 30
  4246.9  117.76  4384.8  116.61  4441.5  115.45  4476.7  115.74  4488.4  115.14
  4519.2  114.38  4593.6  114.13  4830.6  109.83  4844.8  110.15  4915.7  109.13
    4965  107.72  4972.4  106.59  4979.2  106.77  4986.6  104.78    4995  103.89
  4995.2  103.39  4998.9  103.39  4999.2  103.89    5003  103.89  5010.5  105.28
  5020.6  105.82  5091.3   108.2  5106.9  109.56    5112  109.08  5177.9  111.02
    5364  113.54    5385  114.26  5452.1  115.12  5576.1  116.48  5742.4  116.76
#Mann= 7 ,-1 , 0
  4246.9     .05       0  4488.4    .035       0  4593.6     .05       0
    4995     .05       0  4999.2     .05       0    5385    .035       0
  5452.1     .05       0
Bank Sta=4995,4999.2
XS Rating Curve= 0 ,0
Exp/Cntr=0.3,0.1

Type RM Length L Ch R = 1 ,960     ,0,0,0
BEGIN DESCRIPTION:
TRIB 9-1 TO GUADALUPE RIVER 2.0
END DESCRIPTION:
XS GIS Cut Line= 4
      2560114.23     13527811.67        2559625.       13528075.
      2559539.19     13528303.83      2559766.24     13529146.49
#Sta/Elev= 30
  4435.8  118.19  4531.6  118.05  4663.4  115.01  4731.8  112.59  4813.7  111.23
  4835.6  110.13  4911.9  108.88  4955.7  107.43  4994.1  104.22    4999  101.85
  4999.3  101.35  5003.3  101.85  5006.5  102.67  5012.8     102  5031.4  103.52
  5036.8   102.9  5044.8  103.15  5098.2  107.95  5152.5  110.11  5202.3  111.16
  5234.6  112.69  5240.5  112.15  5280.5  113.01  5402.7  116.32  5464.6  116.84
  5475.2  116.28  5584.4  117.69  5990.1  115.81  6047.8  115.28  6108.5  115.17
#Mann= 7 ,-1 , 0
  4435.8     .05       0  4531.6    .035       0  4663.4     .05       0
    4999     .05       0  5003.3     .05       0  5990.1    .035       0
  6047.8     .05       0
Bank Sta=4999,5003.3
XS Rating Curve= 0 ,0
Exp/Cntr=0.3,0.1

Chan Stop Cuts=-1
Use User Specified Reach Order=0
Composite Channel Slope=5