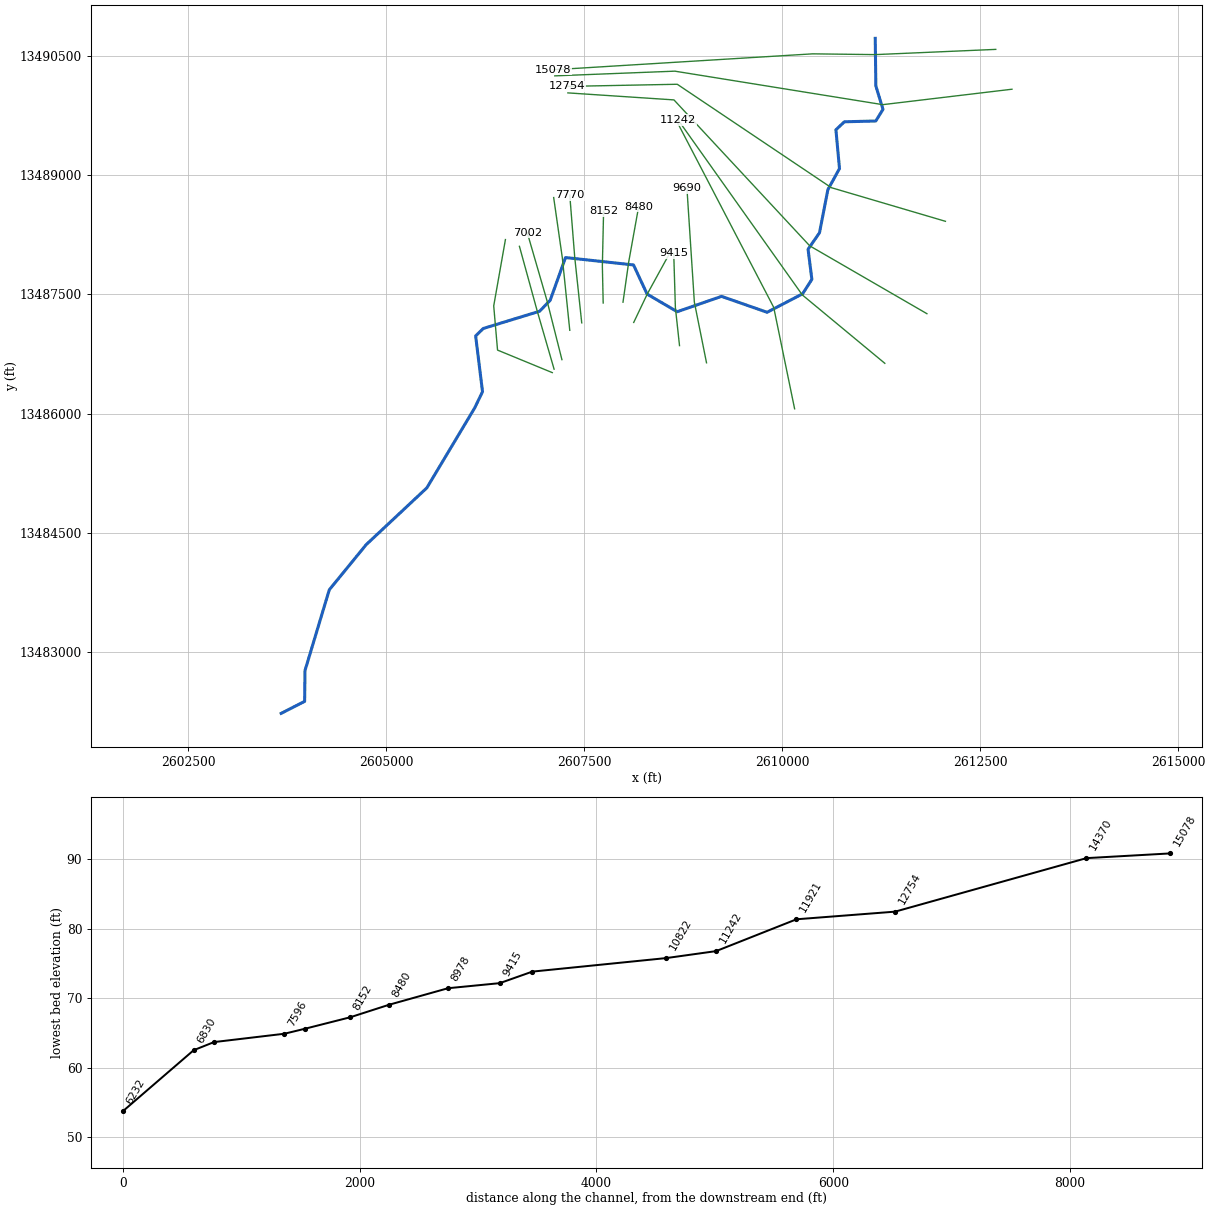
--- WEST OUTFALL.prj (project) ---

Proj Title=WEST OUTFALL Base Level Engineering
Current Plan=p01
Default Exp/Contr=0.3,0.1
English Units
Geom File=g01
Flow File=f01
Plan File=p01
Y Axis Title=Elevation
X Axis Title(PF)=Main Channel Distance
X Axis Title(XS)=Station
BEGIN DESCRIPTION:
WEST OUTFALL
END DESCRIPTION:
DSS Export Rating Curves= 0
DSS Export Rating Curve Sorted= 0
DSS Export Volume Flow Curves= 0
DXF OffsetX= 0
DXF OffsetY= 0
DXF ScaleX= 1
DXF ScaleY= 10

--- WEST OUTFALL.p01 (plan) ---

Plan Title=Multiple Run
Short Identifier=Multiple
Geom File=g01
Flow File=f01
Subcritical Flow
K Sum by GR= 0
Std Step Tol= 0.01
Critical Tol= 0.01
Num of Std Step Trials= 20
Max Error Tol= 0.3
Flow Tol Ratio= 0.001
Split Flow NTrial= 30
Split Flow Tol= 0.02
Split Flow Ratio= 0.02
Log Output Level= 0
Friction Slope Method= 1
Unsteady Friction Slope Method= 2
Unsteady Bridges Friction Slope Method= 1
Parabolic Critical Depth
Global Vel Dist=  1 , 1 , 1
Global Log Level= 0
CheckData=True
Encroach Param= -1, 0, 0, 0
BEGIN DESCRIPTION:
Multiple Run
END DESCRIPTION:

--- WEST OUTFALL.f01 (steady flow) ---

Flow Title=Multiple
Number of Profiles=7
Profile Names=10-year,25-year,50-year,1pct_min,100-year,1pct_plu,500-year
River Rch & RM= WEST OUTFALL,Reach-1,15078
     746    1158    1515     957    1910    3810    2999
River Rch & RM= WEST OUTFALL,Reach-1,10822
    1159    1853    2474    1593    3178    6341    5183
Boundary for River Rch & Prof#=WEST OUTFALL,Reach-1,1
Up Type=0
Dn Type=3
Dn Slope=0.005
Boundary for River Rch & Prof#=WEST OUTFALL,Reach-1,2
Up Type=0
Dn Type=3
Dn Slope=0.005
Boundary for River Rch & Prof#=WEST OUTFALL,Reach-1,3
Up Type=0
Dn Type=3
Dn Slope=0.005
Boundary for River Rch & Prof#=WEST OUTFALL,Reach-1,4
Up Type=0
Dn Type=3
Dn Slope=0.005
Boundary for River Rch & Prof#=WEST OUTFALL,Reach-1,5
Up Type=0
Dn Type=3
Dn Slope=0.005
Boundary for River Rch & Prof#=WEST OUTFALL,Reach-1,6
Up Type=0
Dn Type=3
Dn Slope=0.005
Boundary for River Rch & Prof#=WEST OUTFALL,Reach-1,7
Up Type=0
Dn Type=3
Dn Slope=0.005

--- WEST OUTFALL.g01 (geometry) ---

Geom Title=Existing Conditions
Program Version=4.10

River Reach=WEST OUTFALL    ,Reach-1
Reach XY= 30
        2611175.       13490725.      2611182.78      13490125.1
      2611272.86     13489830.96      2611181.95     13489684.18
      2610785.48     13489674.06      2610678.53     13489573.55
      2610723.78      13489085.5      2610577.07     13488819.14
      2610471.17     13488276.58      2610327.06     13488069.14
      2610375.04     13487690.34      2610258.36     13487508.29
      2609809.78     13487275.51      2609235.05     13487475.76
      2608675.01     13487282.53      2608294.63     13487504.84
      2608123.55     13487871.47      2607264.88     13487964.66
      2607071.39      13487426.5      2606938.21     13487288.63
      2606226.45     13487071.47      2606130.45     13486977.47
      2606217.25     13486275.09      2606119.15     13486072.71
      2605514.61      13485064.9      2604747.86     13484348.84
      2604282.82     13483781.19      2603976.22      13482764.5
      2603971.57     13482376.22        2603675.       13482225.

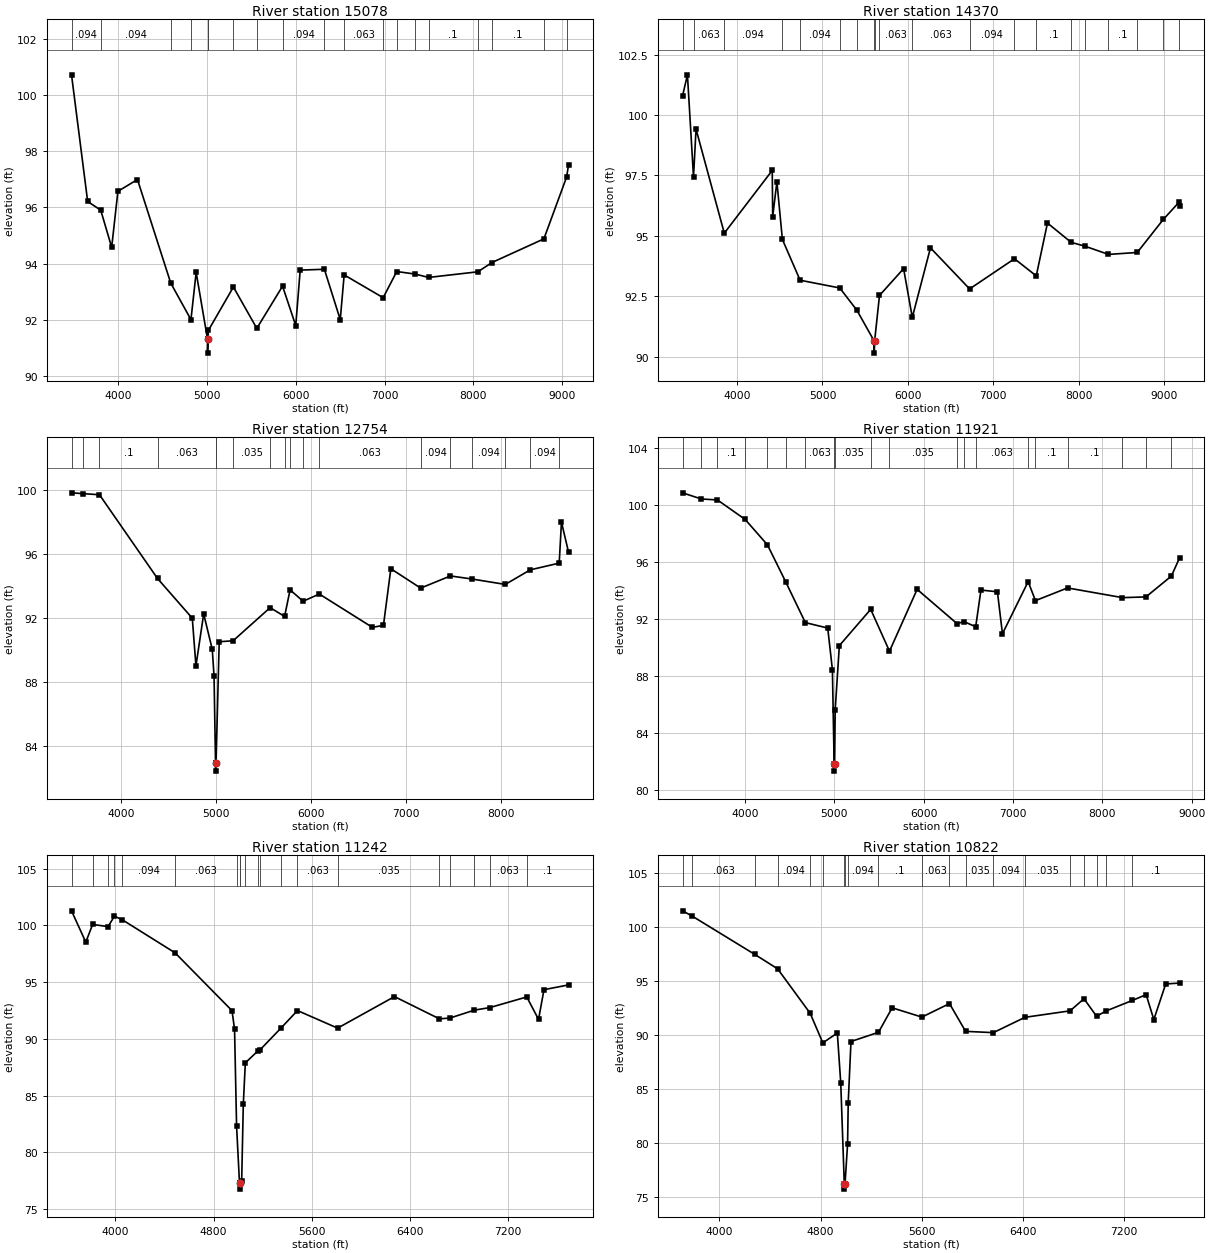
Type RM Length L Ch R = 1 ,15078   ,708,708,708
BEGIN DESCRIPTION:
WEST OUTFALL 30.0
END DESCRIPTION:
XS GIS Cut Line= 4
      2612696.43     13490585.87      2611175.06     13490520.03
       2610384.8     13490529.76      2607110.46     13490329.14
#Sta/Elev= 30
  3477.2  100.71  3658.8   96.21  3806.1    95.9  3929.1   94.58  3999.1   96.57
  4219.3   96.99  4593.8   93.31  4821.2   92.01  4879.9   93.69  5007.6   91.32
    5008   90.82  5012.5   91.32  5017.8   91.63  5298.9   93.17  5562.4    91.7
  5852.2    93.2  6000.5    91.8  6050.6   93.77  6322.8    93.8  6501.4   92.01
  6545.5    93.6  6984.4   92.79  7137.3   93.72  7343.5   93.63  7495.8   93.51
    8050   93.71  8208.9   94.04    8793   94.88  9049.1   97.08  9070.8   97.52
#Mann= 20 ,-1 , 0
  3477.2    .094       0  3806.1    .094       0  4593.8    .063       0
  4821.2      .1       0  5007.6     .05       0  5012.5      .1       0
  5017.8    .063       0  5298.9    .094       0  5562.4    .063       0
  5852.2    .094       0  6322.8    .094       0  6545.5    .063       0
  6984.4    .094       0  7137.3      .1       0  7343.5    .094       0
  7495.8      .1       0    8050    .094       0  8208.9      .1       0
    8793      .1       0  9049.1    .063       0
Bank Sta=5007.6,5012.5
XS Rating Curve= 0 ,0
Exp/Cntr=0.3,0.1

Type RM Length L Ch R = 1 ,14370   ,1616,1616,1616
BEGIN DESCRIPTION:
Mapping XS e1482bef
END DESCRIPTION:
XS GIS Cut Line= 4
      2612901.48     13490084.32      2611269.53     13489889.87
      2608645.26      13490311.6      2607129.64     13490252.45
#Sta/Elev= 30
  3362.7   100.8  3419.6  101.67  3490.7   97.44  3520.3   99.42  3851.1   95.11
  4412.5   97.71  4417.5   95.79  4466.9   97.24  4531.2   94.85  4738.5   93.16
  5202.7   92.84  5402.7   91.92  5605.8   90.64  5606.2   90.14  5610.8   90.64
  5667.8   92.53    5950   93.64  6051.8   91.62  6264.5    94.5  6722.9    92.8
  7247.9   94.05  7502.9   93.34    7634   95.53  7911.2   94.73  8073.2   94.57
  8348.5   94.23  8684.9   94.31  8990.3   95.68  9176.3    96.4  9180.9   96.24
#Mann= 20 ,-1 , 0
  3362.7    .063       0  3490.7    .063       0  3851.1    .094       0
  4531.2    .063       0  4738.5    .094       0  5202.7    .035       0
  5402.7    .094       0  5605.8     .05       0  5610.8    .094       0
  5667.8    .063       0  6051.8    .063       0  6722.9    .094       0
  7247.9    .094       0  7502.9      .1       0  7911.2      .1       0
  8073.2    .094       0  8348.5      .1       0  8684.9      .1       0
  8990.3      .1       0  9176.3    .094       0
Bank Sta=5605.8,5610.8
XS Rating Curve= 0 ,0
Exp/Cntr=0.3,0.1

Type RM Length L Ch R = 1 ,12754   ,833,833,833
BEGIN DESCRIPTION:
Mapping XS 231376ea
END DESCRIPTION:
XS GIS Cut Line= 4
      2612061.16     13488421.14      2610620.23     13488844.74
      2608675.64     13490146.67      2607280.19     13490119.62
#Sta/Elev= 30
  3479.3   99.82  3601.7   99.77  3774.1    99.7  4385.6   94.47  4751.9   91.99
  4790.5   89.01    4872   92.26  4962.5   90.04  4981.2   88.38  4996.9   82.94
  4997.3   82.44  5002.2   82.94  5035.6   90.52  5181.9   90.58  5572.4   92.65
  5724.6    92.1  5782.5   93.76    5920   93.05  6090.7    93.5  6649.3   91.42
  6766.4   91.54  6844.4   95.08  7158.7   93.87  7472.7   94.63  7695.8   94.44
  8050.4    94.1  8313.5   95.01  8618.6   95.43  8642.3   97.99  8717.1   96.11
#Mann= 18 ,-1 , 0
  3479.3      .1       0  3601.7    .094       0  3774.1      .1       0
  4385.6    .063       0  4996.9     .05       0  5002.2    .063       0
  5181.9    .035       0  5572.4    .063       0  5724.6    .094       0
  5782.5    .063       0    5920    .094       0  6090.7    .063       0
  7158.7    .094       0  7472.7      .1       0  7695.8    .094       0
  8050.4      .1       0  8313.5    .094       0  8618.6      .1       0
Bank Sta=4996.9,5002.2
XS Rating Curve= 0 ,0
Exp/Cntr=0.3,0.1

Type RM Length L Ch R = 1 ,11921   ,679,679,679
BEGIN DESCRIPTION:
Mapping XS 98e93e48
END DESCRIPTION:
XS GIS Cut Line= 4
      2611827.26     13487257.83      2610348.12     13488111.98
      2608633.96     13489949.81      2607295.07       13490038.
#Sta/Elev= 30
  3301.7  100.83  3511.2   100.4  3692.6  100.33  4001.5   98.97  4251.3   97.19
  4455.8    94.6    4676   91.74  4926.3   91.36  4978.7   88.45  4998.3   81.84
  4998.7   81.34  5003.6   81.84  5009.8   85.62  5056.4   90.13  5407.4   92.67
  5617.6   89.74  5926.9   94.07  6373.5   91.67  6452.2   91.81  6582.5   91.45
  6641.2   94.02  6825.4    93.9    6882   90.96  7169.7   94.61  7251.2   93.28
  7610.2   94.17  8224.7   93.49  8487.7   93.54  8772.5      95  8864.7   96.28
#Mann= 20 ,-1 , 0
  3301.7      .1       0  3511.2    .094       0  3692.6      .1       0
  4001.5    .094       0  4251.3    .063       0  4455.8    .094       0
    4676    .063       0  4998.3    .035       0  5003.6    .035       0
  5407.4    .094       0  5617.6    .035       0  6373.5    .063       0
  6452.2    .094       0  6582.5    .063       0  7169.7    .094       0
  7251.2      .1       0  7610.2      .1       0  8224.7      .1       0
  8487.7    .094       0  8772.5      .1       0
Bank Sta=4998.3,5003.6
XS Rating Curve= 0 ,0
Exp/Cntr=0.3,0.1

Type RM Length L Ch R = 1 ,11242   ,420,420,420
BEGIN DESCRIPTION:
Mapping XS 3494f66d
END DESCRIPTION:
XS GIS Cut Line= 3
      2611296.03     13486632.82      2610254.37     13487493.93
       2608686.5     13489697.45
#Sta/Elev= 30
  3641.4  101.29  3757.8   98.53  3813.8  100.09  3939.7    99.9  3991.8  100.82
    4056   100.5  4486.2   97.59    4951   92.49  4971.8   90.85  4988.4   82.29
  5012.3   77.26  5012.8   76.76    5018   77.26  5029.9   77.49  5043.3   84.26
  5059.7   87.89  5163.2   88.95  5176.3      89    5352   90.97  5485.1    92.5
  5812.8   90.95  6276.8   93.73  6643.1   91.77  6729.7   91.84  6929.6   92.54
  7054.7   92.76  7356.3    93.7  7452.4   91.72  7496.7   94.34  7697.3   94.76
#Mann= 20 ,-1 , 0
  3641.4      .1       0  3813.8    .063       0  3939.7    .094       0
  3991.8    .063       0    4056    .094       0  4486.2    .063       0
  4988.4    .035       0  5012.3    .035       0    5018    .035       0
  5059.7    .063       0  5163.2    .094       0  5176.3      .1       0
    5352    .094       0  5485.1    .063       0  5812.8    .035       0
  6643.1    .094       0  6729.7    .063       0  6929.6    .094       0
  7054.7    .063       0  7356.3      .1       0
Bank Sta=5012.3,5018
XS Rating Curve= 0 ,0
Exp/Cntr=0.3,0.1

Type RM Length L Ch R = 1 ,10822   ,1132,1132,1132
BEGIN DESCRIPTION:
Mapping XS c5dea774
END DESCRIPTION:
XS GIS Cut Line= 3
      2610157.16     13486059.85      2609893.26     13487337.68
      2608677.81      13489664.9
#Sta/Elev= 30
  3708.2  101.53  3783.1  101.05  4279.8   97.49  4459.7   96.16  4717.3   92.04
  4817.4    89.3    4932   90.22  4959.2   85.55  4986.9   76.26  4987.4   75.76
  4992.8   76.26    5013   79.92  5018.1   83.77  5039.9   89.43  5257.4   90.28
  5365.5   92.55  5600.6   91.69  5818.9   92.94  5946.1   90.37  6165.1   90.25
  6416.2   91.67  6772.6   92.27  6882.3   93.39  6981.6   91.77  7059.9   92.27
  7264.7   93.23    7374   93.77  7434.6   91.46  7528.6   94.76  7638.5   94.84
#Mann= 20 ,-1 , 0
  3708.2    .035       0  3783.1    .063       0  4279.8    .063       0
  4459.7    .094       0  4717.3    .094       0  4817.4    .035       0
  4986.9    .035       0  4992.8    .035       0  5018.1    .094       0
  5257.4      .1       0  5600.6    .063       0  5818.9    .094       0
  5946.1    .035       0  6165.1    .094       0  6416.2    .035       0
  6772.6    .063       0  6882.3    .094       0  6981.6    .063       0
  7059.9    .094       0  7264.7      .1       0
Bank Sta=4986.9,4992.8
XS Rating Curve= 0 ,0
Exp/Cntr=0.3,0.1

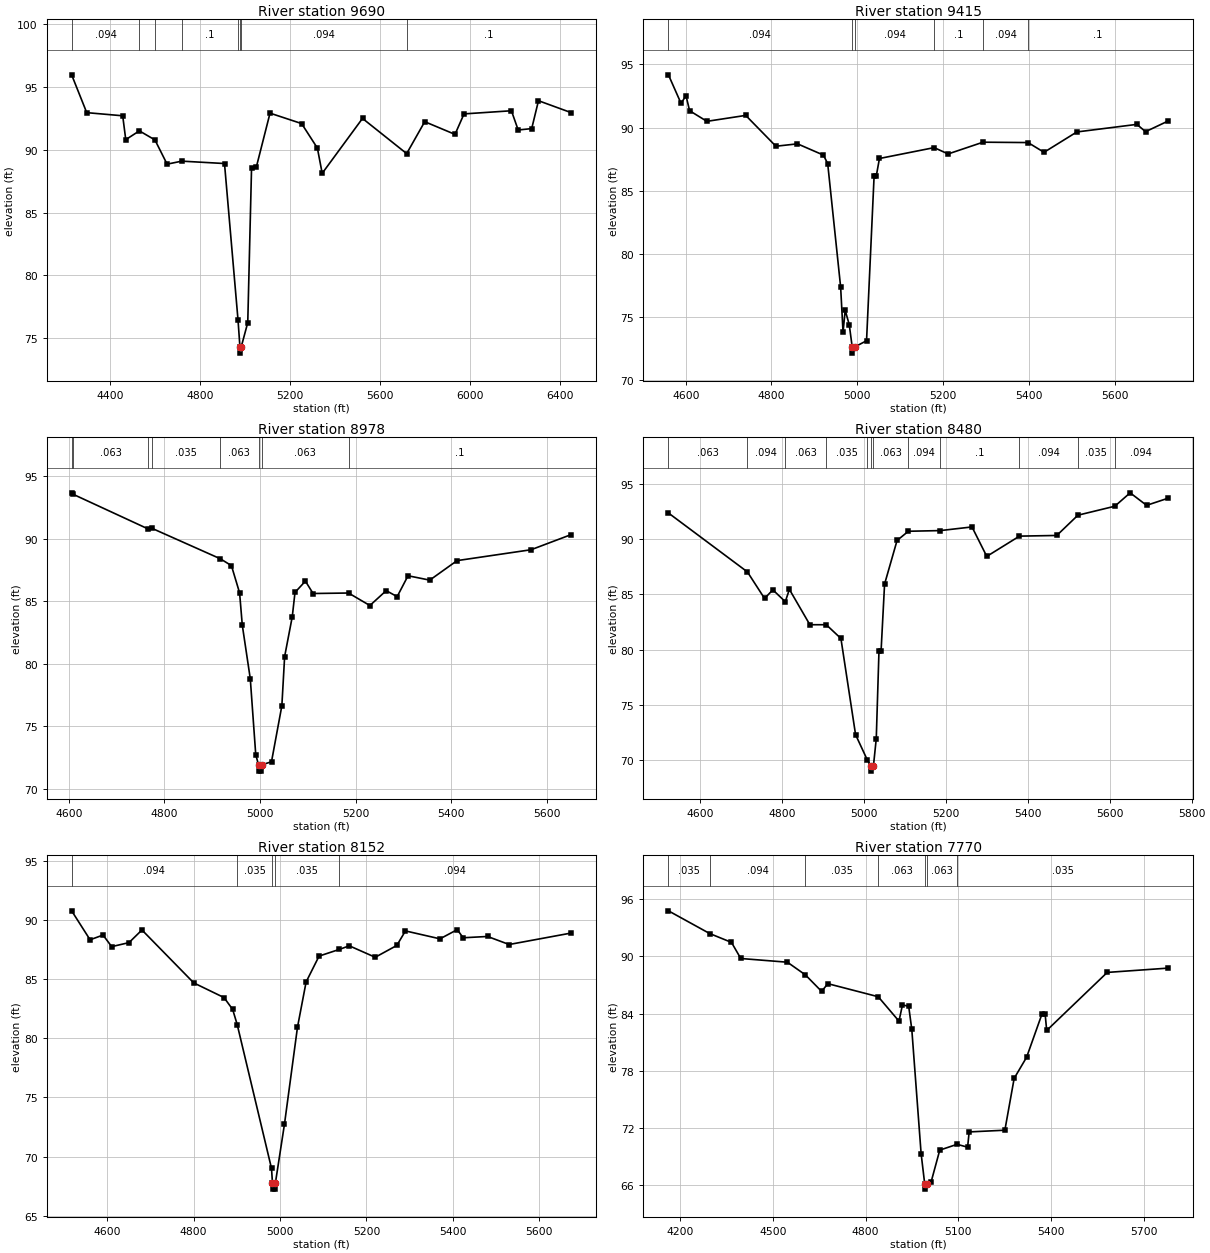
Type RM Length L Ch R = 1 ,9690    ,275,275,275
BEGIN DESCRIPTION:
Mapping XS 64d82603
END DESCRIPTION:
XS GIS Cut Line= 3
      2609045.03     13486639.32      2608891.55      13487402.7
      2608797.63     13488839.88
#Sta/Elev= 30
  4230.4   95.96  4297.4   92.95  4457.2    92.7  4470.8    90.8  4531.2    91.5
  4600.4   90.78  4654.4   88.85  4719.6   89.09  4909.4    88.9  4969.5   76.44
  4977.9   74.31  4978.4   73.81  4983.8   74.31  5012.7   76.24  5029.6   88.58
  5051.4   88.66  5111.6   92.91  5251.9   92.08    5322   90.13  5343.3   88.12
  5522.4   92.49  5718.6   89.69  5798.8   92.23  5933.3   91.22  5973.4   92.85
  6183.9    93.1  6213.9   91.57    6274   91.68  6304.1    93.9  6449.3   92.95
#Mann= 8 ,-1 , 0
  4230.4    .094       0  4531.2    .063       0  4600.4    .094       0
  4719.6      .1       0  4969.5    .094       0  4977.9     .05       0
  4983.8    .094       0  5718.6      .1       0
Bank Sta=4977.9,4983.8
XS Rating Curve= 0 ,0
Exp/Cntr=0.3,0.1

Type RM Length L Ch R = 1 ,9415    ,437,437,437
BEGIN DESCRIPTION:
Mapping XS 8df7f22e
END DESCRIPTION:
XS GIS Cut Line= 3
      2608704.05     13486855.85      2608651.97       13487335.
      2608631.14     13488017.31
#Sta/Elev= 30
  4559.7   94.17    4589   91.92  4600.7   92.51  4609.1   91.33  4649.4   90.49
  4739.9   90.96  4810.3   88.52  4860.6   88.71    4921   87.82    4931   87.15
  4961.2   77.38  4966.8    73.8  4971.8   75.54  4981.3    74.4  4988.1   72.65
  4988.6   72.15  4994.6   72.65  5021.6   73.13  5039.2   86.15  5044.2   86.15
  5051.7   87.55  5179.2   88.41  5211.8   87.91  5293.2   88.84  5398.1   88.81
  5435.4   88.04  5511.9   89.65    5652   90.25    5672   89.67  5724.3   90.51
#Mann= 6 ,-1 , 0
  4559.7    .094       0  4988.1     .05       0  4994.6    .094       0
  5179.2      .1       0  5293.2    .094       0  5398.1      .1       0
Bank Sta=4988.1,4994.6
XS Rating Curve= 0 ,0
Exp/Cntr=0.3,0.1

Type RM Length L Ch R = 1 ,8978    ,498,498,498
BEGIN DESCRIPTION:
Mapping XS 9d4509da
END DESCRIPTION:
XS GIS Cut Line= 3
      2608125.95     13487147.53       2608297.8     13487506.87
      2608610.13     13488074.27
#Sta/Elev= 30
  4605.6   93.67  4608.9   93.55  4766.5   90.77  4774.5   90.82  4916.8    88.4
  4940.2   87.85  4957.3   85.67  4962.9    83.1  4979.7    78.8  4991.1   72.74
  4996.9   71.92  4997.4   71.42  5002.9   71.42  5003.4   71.92  5024.1   72.17
  5045.8   76.65  5051.6   80.58  5067.6   83.77  5073.3   85.71  5095.1   86.61
  5111.2   85.62  5185.4   85.66  5230.1   84.66  5264.3   85.85  5287.2   85.37
    5310   87.04  5355.5   86.69  5412.7   88.25  5567.6   89.12  5651.6   90.33
#Mann= 8 ,-1 , 0
  4605.6    .094       0  4608.9    .063       0  4766.5    .094       0
  4774.5    .035       0  4916.8    .063       0  4996.9     .05       0
  5003.4    .063       0  5185.4      .1       0
Bank Sta=4996.9,5003.4
XS Rating Curve= 0 ,0
Exp/Cntr=0.3,0.1

Type RM Length L Ch R = 1 ,8480    ,328,328,328
BEGIN DESCRIPTION:
Mapping XS f826f868
END DESCRIPTION:
XS GIS Cut Line= 3
      2607990.51     13487402.69      2608063.43     13487913.12
      2608188.43     13488605.82
#Sta/Elev= 30
  4522.6   92.35  4715.4   87.03  4757.3   84.63  4777.5   85.41  4807.9   84.34
  4817.9   85.45  4867.9   82.26  4907.9   82.26  4943.7   81.02  4979.5   72.33
  5007.9   70.07  5016.6   69.54  5017.1   69.04  5023.2   69.54    5030   71.97
  5036.6   79.85  5041.7   79.85  5050.3   85.93  5080.8   89.87  5108.4    90.7
  5186.3   90.76  5263.7   91.09  5299.8   88.43  5379.6   90.26  5470.7   90.32
  5522.3   92.15  5612.4   92.96  5649.8   94.17    5690   93.04  5742.1   93.68
#Mann= 12 ,-1 , 0
  4522.6    .063       0  4715.4    .094       0  4807.9    .063       0
  4907.9    .035       0  5007.9    .063       0  5016.6    .035       0
  5023.2    .063       0  5108.4    .094       0  5186.3      .1       0
  5379.6    .094       0  5522.3    .035       0  5612.4    .094       0
Bank Sta=5016.6,5023.2
XS Rating Curve= 0 ,0
Exp/Cntr=0.3,0.1

Type RM Length L Ch R = 1 ,8152    ,382,382,382
BEGIN DESCRIPTION:
Mapping XS 61a5b676
END DESCRIPTION:
XS GIS Cut Line= 3
      2607740.51     13487392.28       2607730.1     13487861.04
      2607745.72     13488548.58
#Sta/Elev= 30
  4517.5   90.79  4560.2   88.34  4590.2   88.74  4610.2   87.76  4650.3    88.1
  4680.3   89.17  4800.3   84.69  4870.3   83.45  4890.3   82.45  4900.8   81.17
  4980.3   68.99  4982.5   67.74    4983   67.24  4988.7   67.24  4989.2   67.74
  5010.3   72.74  5040.4   80.94  5060.4   84.77  5090.4   86.96  5136.9   87.52
  5160.4   87.83  5220.4   86.86  5270.4   87.86  5290.4   89.09  5370.4   88.42
  5410.4    89.2  5423.9   88.51  5480.5   88.62  5530.5   87.94  5674.1   88.91
#Mann= 5 ,-1 , 0
  4517.5    .094       0  4900.8    .035       0  4982.5    .035       0
  4989.2    .035       0  5136.9    .094       0
Bank Sta=4982.5,4989.2
XS Rating Curve= 0 ,0
Exp/Cntr=0.3,0.1

Type RM Length L Ch R = 1 ,7770    ,174,174,174
BEGIN DESCRIPTION:
Mapping XS bbf0576e
END DESCRIPTION:
XS GIS Cut Line= 3
      2607469.68      13487142.3      2607381.14     13487970.41
      2607318.71     13488750.78
#Sta/Elev= 30
  4162.4   94.78  4295.7    92.4  4366.3   91.47  4396.4   89.78  4547.3   89.39
  4605.5   88.06  4657.9   86.33    4678   87.14    4841   85.77  4908.1   83.21
  4919.4   84.91  4939.5   84.77  4949.6   82.34  4979.7   69.32  4991.5   66.09
    4992   65.59  4998.5   66.09  5012.2   66.36    5040   69.68    5096   70.29
  5130.1   69.99  5135.1   71.59  5250.6   71.77  5280.7   77.21  5320.9   79.42
    5371   83.99  5380.9   83.94  5385.9   82.23  5581.7   88.32  5778.1   88.77
#Mann= 7 ,-1 , 0
  4162.4    .035       0  4295.7    .094       0  4605.5    .035       0
    4841    .063       0  4991.5     .05       0  4998.5    .063       0
    5096    .035       0
Bank Sta=4991.5,4998.5
XS Rating Curve= 0 ,0
Exp/Cntr=0.3,0.1

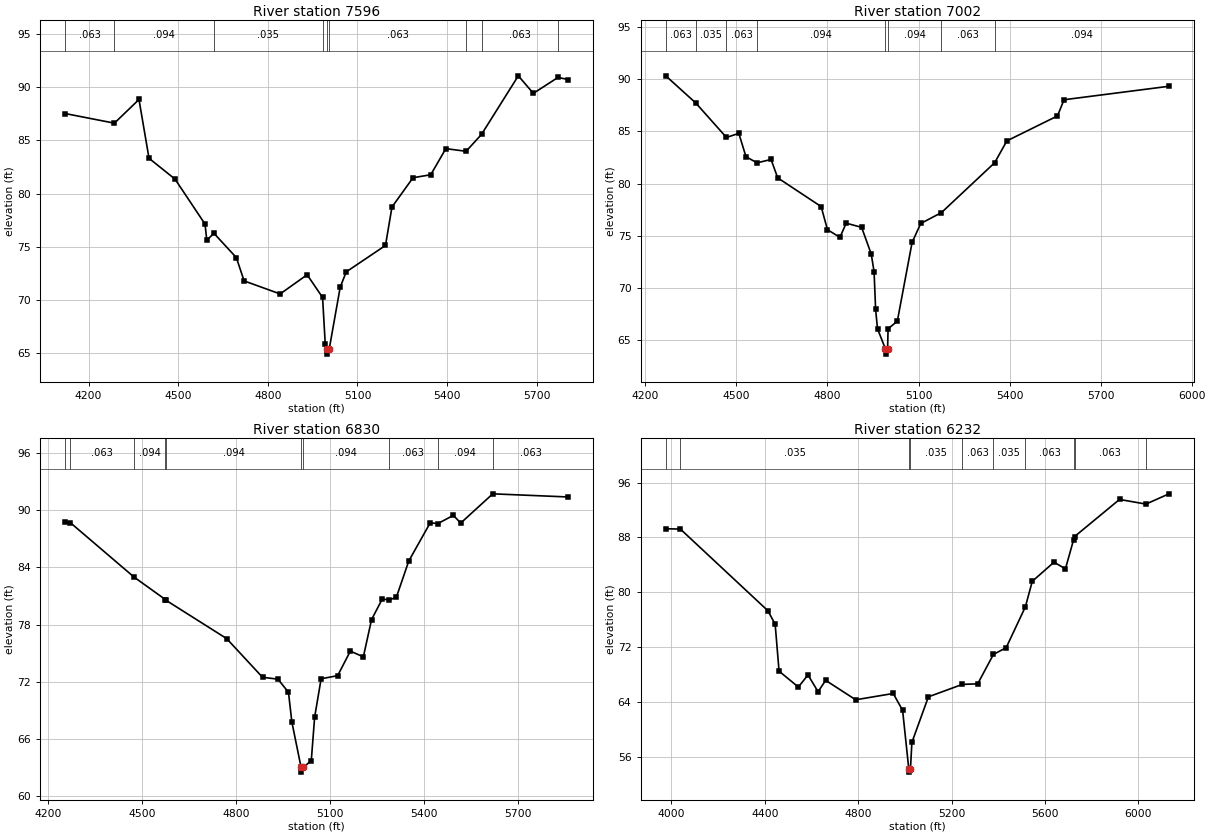
Type RM Length L Ch R = 1 ,7596    ,594,594,594
BEGIN DESCRIPTION:
Mapping XS 36d1ef61
END DESCRIPTION:
XS GIS Cut Line= 3
      2607318.64     13487048.52      2607224.89       13487960.
      2607115.55     13488720.19
#Sta/Elev= 30
  4120.8   87.54  4286.3   86.63  4368.6   88.86  4402.2   83.32  4489.2   81.36
  4589.7   77.12  4595.5   75.61  4619.7   76.25  4694.6   73.96  4720.4   71.77
  4841.1   70.54  4931.5   72.35  4983.1   70.21    4992   65.86  4998.4   65.37
  4998.9   64.87  5005.5   65.37  5042.1   71.17  5062.3   72.62  5193.7   75.11
  5215.4   78.73  5285.9   81.49  5345.2   81.77  5395.7   84.23  5463.6   83.98
  5515.1   85.57  5638.3   91.09  5688.7   89.44  5771.1   90.94  5805.1   90.74
#Mann= 9 ,-1 , 0
  4120.8    .063       0  4286.3    .094       0  4619.7    .035       0
  4983.1    .063       0  4998.4     .05       0  5005.5    .063       0
  5463.6    .035       0  5515.1    .063       0  5771.1    .035       0
Bank Sta=4998.4,5005.5
XS Rating Curve= 0 ,0
Exp/Cntr=0.3,0.1

Type RM Length L Ch R = 1 ,7002    ,172,172,172
BEGIN DESCRIPTION:
Mapping XS bc485575
END DESCRIPTION:
XS GIS Cut Line= 3
      2607219.67     13486678.79      2607032.18     13487418.33
      2606782.19     13488277.67
#Sta/Elev= 30
  4267.3   90.32  4366.1   87.72  4467.2   84.42    4508   84.81  4531.6   82.57
  4568.2   81.99  4614.2   82.31  4636.1   80.55  4779.2    77.8    4800   75.59
  4841.1   74.85  4861.7   76.21  4912.6   75.81  4944.3   73.25  4953.6   71.57
  4958.7   67.95  4964.9    66.1    4991   64.17  4991.5   63.67  4998.2   64.17
  4999.7    66.1  5030.2   66.82  5078.9   74.37  5107.3   76.18  5175.5   77.22
    5351      82  5391.1   84.09  5557.9   86.48  5579.5   88.03  5925.2   89.32
#Mann= 8 ,-1 , 0
  4267.3    .063       0  4366.1    .035       0  4467.2    .063       0
  4568.2    .094       0    4991     .05       0  4998.2    .094       0
  5175.5    .063       0    5351    .094       0
Bank Sta=4991,4998.2
XS Rating Curve= 0 ,0
Exp/Cntr=0.3,0.1

Type RM Length L Ch R = 1 ,6830    ,598,598,598
BEGIN DESCRIPTION:
Mapping XS 8d1e67f7
END DESCRIPTION:
XS GIS Cut Line= 3
      2607120.73     13486558.94      2606907.18     13487293.33
      2606683.22     13488105.82
#Sta/Elev= 30
    4253   88.71  4269.9    88.7  4473.7   82.98  4573.8   80.62  4575.5   80.55
  4769.6   76.52  4884.2   72.46  4933.6   72.26  4967.1   70.88  4977.9   67.77
  5007.4      63  5007.9    62.5  5014.6      63    5040   63.71  5050.7   68.27
  5071.4    72.3  5124.3   72.63  5164.8   75.21  5206.3    74.6  5232.6   78.52
    5267   80.69  5287.7   80.57  5311.7   80.85  5351.5   84.67    5420   88.68
    5444   88.59    5494   89.46  5517.4   88.65  5619.8   91.72  5860.6   91.39
#Mann= 10 ,-1 , 0
    4253    .094       0  4269.9    .063       0  4473.7    .094       0
  4573.8    .035       0  4575.5    .094       0  5007.4     .05       0
  5014.6    .094       0  5287.7    .063       0    5444    .094       0
  5619.8    .063       0
Bank Sta=5007.4,5014.6
XS Rating Curve= 0 ,0
Exp/Cntr=0.3,0.1

Type RM Length L Ch R = 1 ,6232    ,0,0,0
BEGIN DESCRIPTION:
WEST OUTFALL 14.0
END DESCRIPTION:
XS GIS Cut Line= 4
      2607098.15     13486515.55      2606406.85     13486799.45
      2606358.59     13487355.99      2606506.37     13488191.26
#Sta/Elev= 30
  3976.5   89.28  4039.1   89.23  4413.6    77.3  4444.8   75.33  4461.5   68.47
  4544.2   66.15  4585.3   67.92  4628.5   65.47    4661   67.13  4789.6   64.29
  4950.2   65.21  4990.4   62.75  5016.8   54.22  5017.3   53.72  5024.1   54.22
  5030.1   58.05  5100.8   64.72  5246.3   66.54  5311.9   66.62  5379.2   70.92
  5433.8    71.9    5516   77.87  5545.5    81.6  5638.5   84.39  5687.5   83.42
  5722.3   87.66  5726.7   88.14  5919.1   93.56  6032.3   92.88  6130.7   94.38
#Mann= 10 ,-1 , 0
  3976.5    .094       0  4039.1    .035       0  5016.8    .035       0
  5024.1    .035       0  5246.3    .063       0  5379.2    .035       0
    5516    .063       0  5722.3    .094       0  5726.7    .063       0
  6032.3    .035       0
Bank Sta=5016.8,5024.1
XS Rating Curve= 0 ,0
Exp/Cntr=0.3,0.1

Chan Stop Cuts=-1
Use User Specified Reach Order=0
Composite Channel Slope=5