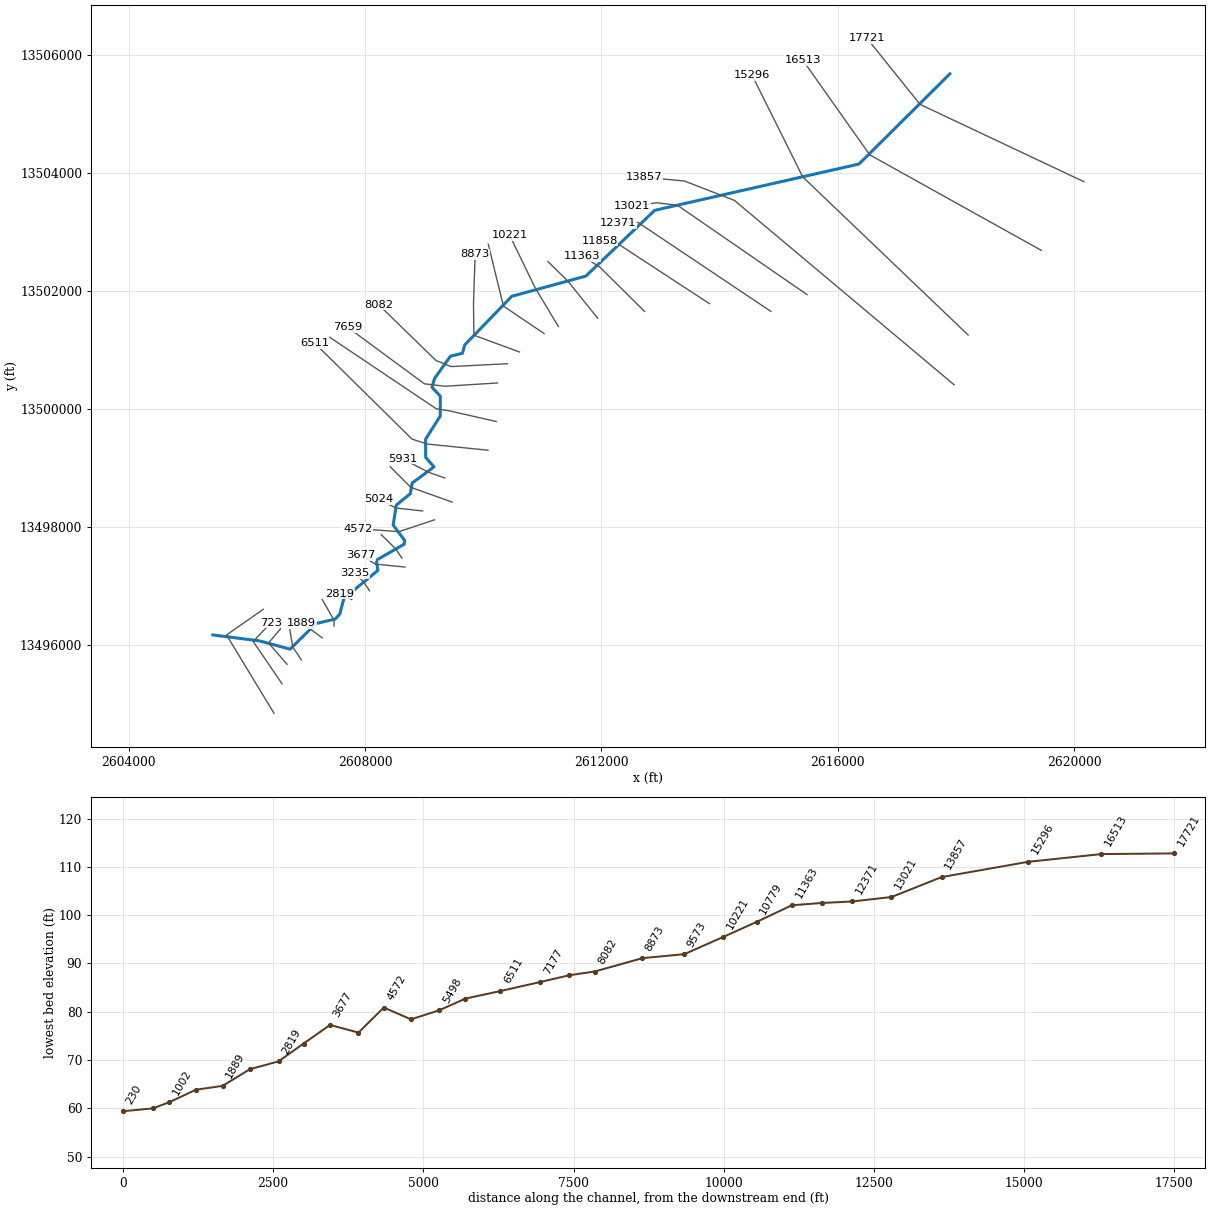
--- WHISPERING CREEK.prj (project) ---

Proj Title=WHISPERING CREEK Base Level Engineering
Current Plan=p01
Default Exp/Contr=0.3,0.1
English Units
Geom File=g01
Flow File=f01
Plan File=p01
Y Axis Title=Elevation
X Axis Title(PF)=Main Channel Distance
X Axis Title(XS)=Station
BEGIN DESCRIPTION:
WHISPERING CREEK
END DESCRIPTION:
DSS Export Rating Curves= 0
DSS Export Rating Curve Sorted= 0
DSS Export Volume Flow Curves= 0
DXF OffsetX= 0
DXF OffsetY= 0
DXF ScaleX= 1
DXF ScaleY= 10

--- WHISPERING CREEK.p01 (plan) ---

Plan Title=Multiple Run
Short Identifier=Multiple
Geom File=g01
Flow File=f01
Subcritical Flow
K Sum by GR= 0
Std Step Tol= 0.01
Critical Tol= 0.01
Num of Std Step Trials= 20
Max Error Tol= 0.3
Flow Tol Ratio= 0.001
Split Flow NTrial= 30
Split Flow Tol= 0.02
Split Flow Ratio= 0.02
Log Output Level= 0
Friction Slope Method= 1
Unsteady Friction Slope Method= 2
Unsteady Bridges Friction Slope Method= 1
Parabolic Critical Depth
Global Vel Dist=  1 , 1 , 1
Global Log Level= 0
CheckData=True
Encroach Param= -1, 0, 0, 0
BEGIN DESCRIPTION:
Multiple Run
END DESCRIPTION:

--- WHISPERING CREEK.f01 (steady flow) ---

Flow Title=Multiple
Number of Profiles=7
Profile Names=10-year,25-year,50-year,1pct_min,100-year,1pct_plu,500-year
River Rch & RM= WHISPERING CREEK,Reach-1,17721
     211     300     369     221     440     878     617
River Rch & RM= WHISPERING CREEK,Reach-1,13021
     493     750     967     603    1204    2403    1844
River Rch & RM= WHISPERING CREEK,Reach-1,8873
     725    1129    1481     938    1872    3736    2959
River Rch & RM= WHISPERING CREEK,Reach-1,4572
     993    1577    2096    1344    2681    5350    4337
Boundary for River Rch & Prof#=WHISPERING CREEK,Reach-1,1
Up Type=0
Dn Type=3
Dn Slope=0.005
Boundary for River Rch & Prof#=WHISPERING CREEK,Reach-1,2
Up Type=0
Dn Type=3
Dn Slope=0.005
Boundary for River Rch & Prof#=WHISPERING CREEK,Reach-1,3
Up Type=0
Dn Type=3
Dn Slope=0.005
Boundary for River Rch & Prof#=WHISPERING CREEK,Reach-1,4
Up Type=0
Dn Type=3
Dn Slope=0.005
Boundary for River Rch & Prof#=WHISPERING CREEK,Reach-1,5
Up Type=0
Dn Type=3
Dn Slope=0.005
Boundary for River Rch & Prof#=WHISPERING CREEK,Reach-1,6
Up Type=0
Dn Type=3
Dn Slope=0.005
Boundary for River Rch & Prof#=WHISPERING CREEK,Reach-1,7
Up Type=0
Dn Type=3
Dn Slope=0.005

--- WHISPERING CREEK.g01 (geometry) ---

Geom Title=Existing Conditions
Program Version=4.10

River Reach=WHISPERING CREEK,Reach-1
Reach XY= 30
      2617900.07     13505679.62      2616361.62      13504151.9
      2612902.99     13503367.78        2611737.     13502252.94
      2610483.65     13501911.48       2609688.4      13501088.3
      2609648.82     13500947.31      2609444.63     13500895.48
      2609178.62      13500523.5      2609132.79     13500371.58
      2609272.94     13500219.15       2609273.8      13499885.5
      2609024.56     13499490.18      2609027.06     13499180.85
      2609167.41     13499021.67      2608797.86     13498748.53
      2608767.19     13498568.79      2608528.53     13498373.55
      2608475.94     13498035.48      2608669.92     13497777.28
       2608661.9     13497711.76      2608191.21     13497441.71
      2608217.52     13497268.93       2607641.3     13496792.13
      2607571.39     13496526.48      2607495.13     13496444.76
      2607168.79      13496367.2      2606731.73     13495934.15
       2606214.5     13496073.78        2605425.       13496175.

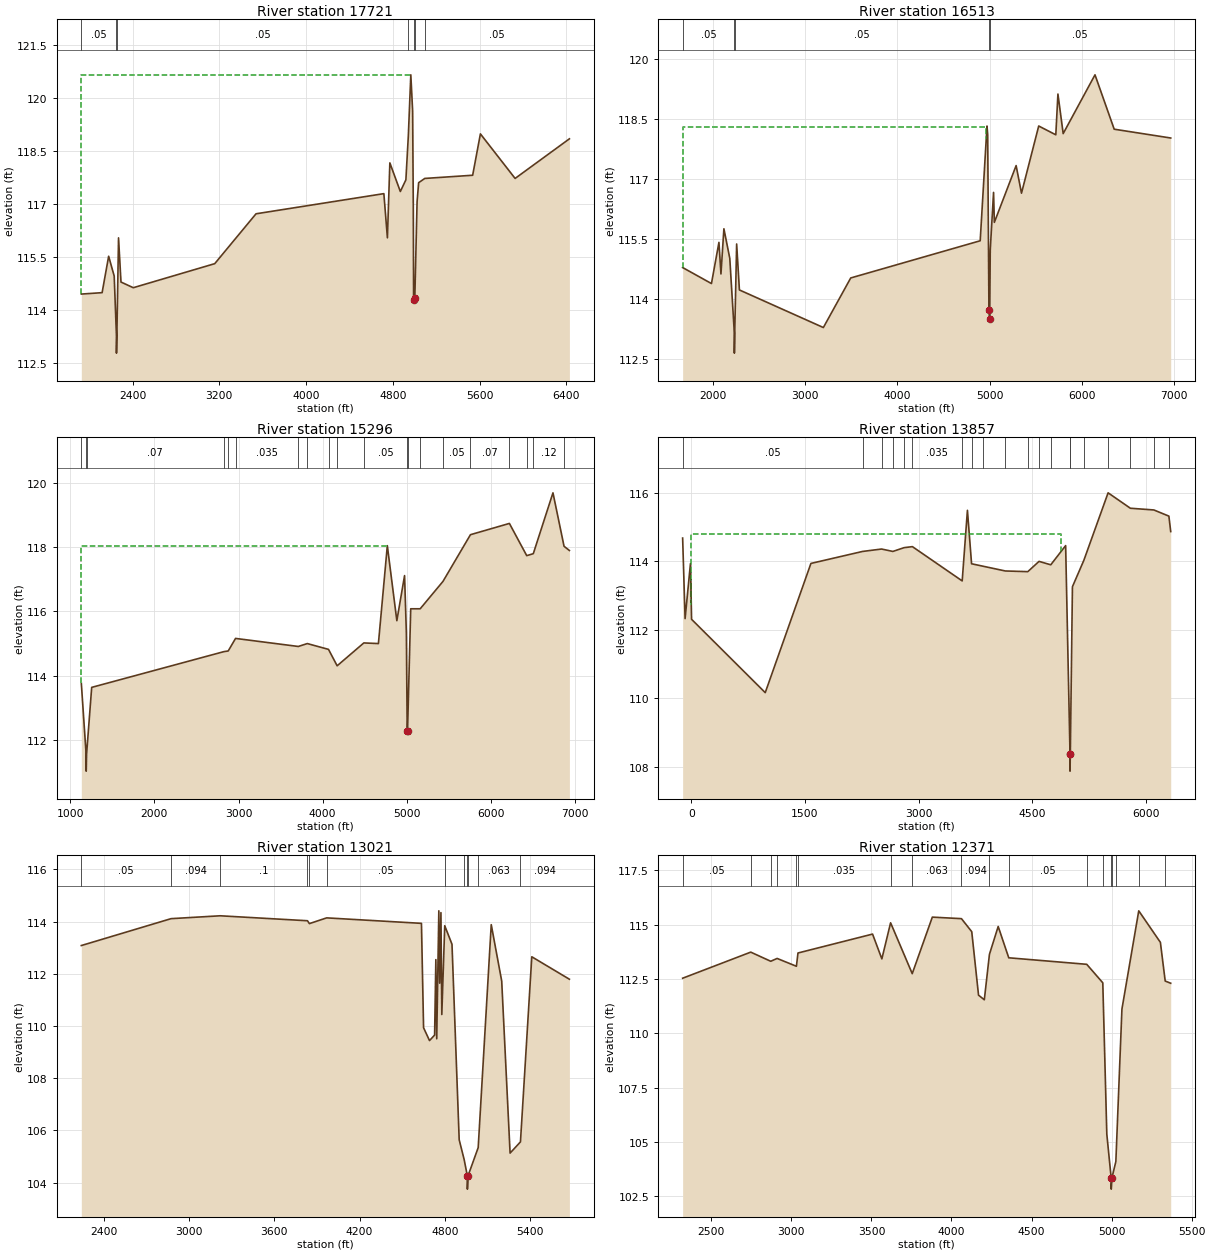
Type RM Length L Ch R = 1 ,17721   ,1208,1208,1208
BEGIN DESCRIPTION:
Mapping XS 73040e38
END DESCRIPTION:
XS GIS Cut Line= 3
      2620168.43      13503852.6      2617394.59     13505162.15
      2616496.96     13506280.94
#Sta/Elev= 30
  1927.2  114.45    2119  114.49  2179.3  115.52  2230.4  114.96  2251.1  113.28
  2251.4  112.78  2255.1  113.28  2270.4  116.04  2293.1  114.79  2406.5  114.63
  3157.8  115.31  3538.7  116.72  4717.7  117.29  4750.4  116.04    4773  118.16
  4869.7  117.35  4920.8  117.68  4943.5  118.93  4966.3  120.65  4983.1  119.63
  4989.1  116.95  4992.1  114.27  5003.3  114.35  5024.1  117.06  5038.5   117.6
  5095.4  117.72  5536.8  117.81  5608.2  118.98  5928.3  117.72    6429  118.84
#Mann= 7 ,-1 , 0
  1927.2     .05       0  2251.1    .035       0  2255.1     .05       0
  4943.5    .035       0  4992.1    .035       0  5003.3    .035       0
  5095.4     .05       0
#XS Ineff= 2 , 0
       0  4966.3  120.65               0
Permanent Ineff=
       F       F
Bank Sta=4992.1,5003.3
XS Rating Curve= 0 ,0
Exp/Cntr=0.3,0.1

Type RM Length L Ch R = 1 ,16513   ,1217,1217,1217
BEGIN DESCRIPTION:
Mapping XS a099d08c
END DESCRIPTION:
XS GIS Cut Line= 3
      2619446.29     13502689.94      2616543.29     13504307.53
      2615408.62     13505913.23
#Sta/Elev= 30
  1674.4  114.78  1986.7  114.38  2067.8  115.41  2089.6  114.62  2121.6  115.75
  2185.3  115.01  2234.8  113.14  2235.1  112.64  2238.8  113.14  2259.7  115.37
  2289.6  114.22  3199.5  113.28  3496.1  114.52  4899.2  115.45  4972.8  118.32
  4980.3   118.1  4993.8  113.72    5002   113.5  5008.1  115.22  5043.8  116.66
  5052.5  115.91  5288.4  117.33  5346.7  116.64  5533.3  118.32  5718.5   118.1
  5741.5  119.12  5798.5  118.13  6143.2   119.6  6351.3  118.24  6963.8  118.02
#Mann= 5 ,-1 , 0
  1674.4     .05       0  2234.8     .05       0  2238.8     .05       0
  4993.8     .05       0    5002     .05       0
#XS Ineff= 2 , 0
       0  4964.4   118.3               0
Permanent Ineff=
       F       F
Bank Sta=4993.8,5002
XS Rating Curve= 0 ,0
Exp/Cntr=0.3,0.1

Type RM Length L Ch R = 1 ,15296   ,1439,1439,1439
BEGIN DESCRIPTION:
Mapping XS b78c9388
END DESCRIPTION:
XS GIS Cut Line= 3
      2618209.38     13501255.05      2615408.62     13503934.07
      2614550.02     13505659.95
#Sta/Elev= 30
  1130.7  113.77  1188.5  111.54  1188.7  111.04  1192.5  111.54    1254  113.64
  2826.4  114.75  2877.3  114.77  2964.7  115.16  3710.4  114.91  3817.7     115
  4069.8  114.82  4172.6  114.31  4489.7  115.02  4663.2     115  4769.2  118.04
  4882.4  115.71  4974.2  117.11  4995.6  115.33  5005.5   112.3  5009.8   112.3
  5047.4  116.08    5160  116.08  5430.9  116.93  5757.6  118.38  6220.7  118.73
  6426.7  117.73  6504.7  117.79  6738.7  119.68  6870.6  118.02  6934.1  117.89
#Mann= 20 ,-1 , 0
  1130.7     .07       0  1188.5     .05       0  1192.5     .07       0
  2826.4    .035       0  2877.3     .07       0  2964.7    .035       0
  3710.4     .07       0  3817.7    .035       0  4069.8     .07       0
  4172.6    .035       0  4489.7     .05       0  5005.5     .05       0
  5009.8     .05       0    5160     .07       0  5430.9     .05       0
  5757.6     .07       0  6220.7     .12       0  6426.7     .05       0
  6504.7     .12       0  6870.6     .05       0
#XS Ineff= 2 , 0
       0  4769.2  118.04               0
Permanent Ineff=
       F       F
Bank Sta=5005.5,5009.8
XS Rating Curve= 0 ,0
Exp/Cntr=0.3,0.1

Type RM Length L Ch R = 1 ,13857   ,836,836,836
BEGIN DESCRIPTION:
Mapping XS 3af5f5cc
END DESCRIPTION:
XS GIS Cut Line= 4
       2617969.8      13500413.9      2614254.11     13503534.77
      2613407.32     13503864.16      2612729.55     13503928.01
#Sta/Elev= 30
  -114.2  114.68   -81.8  112.33   -10.7  113.94     3.6  112.31     976  110.17
  1578.9  113.94  2261.2  114.29  2511.8  114.36  2660.3  114.29  2808.7   114.4
  2918.3  114.43  3575.4  113.43  3644.5  115.49  3699.2  113.93  3847.6  113.86
  4144.5  113.72  4441.3   113.7  4589.7     114  4744.3   113.9  4940.8  114.46
  4998.5  108.38  4998.8  107.88  5002.5  108.38  5030.4  113.26    5181  114.03
  5501.2     116  5795.2  115.55  6105.4   115.5  6303.4  115.32  6327.6  114.87
#Mann= 20 ,-1 , 0
  -114.2     .05       0  2261.2    .094       0  2511.8    .035       0
  2660.3     .05       0  2808.7    .094       0  2918.3    .035       0
  3575.4    .094       0  3699.2    .063       0  3847.6     .07       0
  4144.5    .035       0  4441.3    .035       0  4589.7     .05       0
  4744.3    .035       0  4998.5     .05       0  5002.5     .05       0
    5181    .035       0  5501.2     .07       0  5795.2     .05       0
  6105.4     .05       0  6303.4     .12       0
#XS Ineff= 2 , 0
       0  4876.8   114.8               0
Permanent Ineff=
       F       F
Bank Sta=4998.5,5002.5
XS Rating Curve= 0 ,0
Exp/Cntr=0.3,0.1

Type RM Length L Ch R = 1 ,13021   ,650,650,650
BEGIN DESCRIPTION:
Mapping XS 6bd4d88f
END DESCRIPTION:
XS GIS Cut Line= 4
      2615481.56     13501940.13      2613287.09     13503454.04
      2612932.93      13503495.7       2612522.5      13503440.8
#Sta/Elev= 30
  2240.9  113.08  2872.9  114.11  3218.6  114.22  3833.4  114.03  3846.9  113.92
  3968.6  114.14  4635.9  113.93  4650.8  109.93  4692.7  109.44  4728.5  109.65
  4737.3  112.54  4743.4  109.51  4758.3  114.41  4764.3  111.64  4773.1  114.34
  4779.2  110.44  4799.8  113.84  4850.9  113.13  4901.6  105.64  4936.7  104.88
  4959.2  104.25  4959.4  103.75  4963.2  104.25  5035.4  105.34  5127.3  113.88
    5201  111.72    5260  105.13    5333  105.56  5412.8  112.65  5677.6  111.79
#Mann= 12 ,-1 , 0
  2240.9     .05       0  2872.9    .094       0  3218.6      .1       0
  3833.4    .094       0  3846.9    .035       0  3968.6     .05       0
  4799.8    .063       0  4936.7    .094       0  4959.2     .05       0
  4963.2    .094       0  5035.4    .063       0    5333    .094       0
Bank Sta=4959.2,4963.2
XS Rating Curve= 0 ,0
Exp/Cntr=0.3,0.1

Type RM Length L Ch R = 1 ,12371   ,513,513,513
BEGIN DESCRIPTION:
Mapping XS 07e692ca
END DESCRIPTION:
XS GIS Cut Line= 3
      2614870.45     13501655.41      2612620.43     13503162.37
      2612280.55      13503148.8
#Sta/Elev= 30
    2321  112.53  2746.3  113.73  2871.2  113.31  2911.1  113.44  3031.6  113.08
  3041.3  113.69  3507.1  114.56  3565.2  113.42  3619.8  115.08  3754.9  112.74
  3880.4  115.34  4062.3  115.27  4126.6  114.67    4169  111.75  4205.1  111.54
  4237.1  113.63  4291.7  114.91  4357.7  113.47  4844.7  113.17    4945  112.32
  4970.1  105.36  4997.5  103.33  4997.7  102.83  5001.5  103.33  5026.6   104.1
  5064.5  111.11  5169.6  115.63  5304.7  114.18  5334.8   112.4  5369.2   112.3
#Mann= 18 ,-1 , 0
    2321     .05       0  2746.3    .035       0  2871.2    .063       0
  2911.1    .094       0  3031.6    .063       0  3041.3    .035       0
  3619.8    .094       0  3754.9    .063       0  4062.3    .094       0
  4237.1    .035       0  4357.7     .05       0  4844.7    .063       0
    4945    .094       0  4997.5     .05       0  5001.5    .094       0
  5026.6    .063       0  5169.6    .094       0  5334.8     .05       0
Bank Sta=4997.5,5001.5
XS Rating Curve= 0 ,0
Exp/Cntr=0.3,0.1

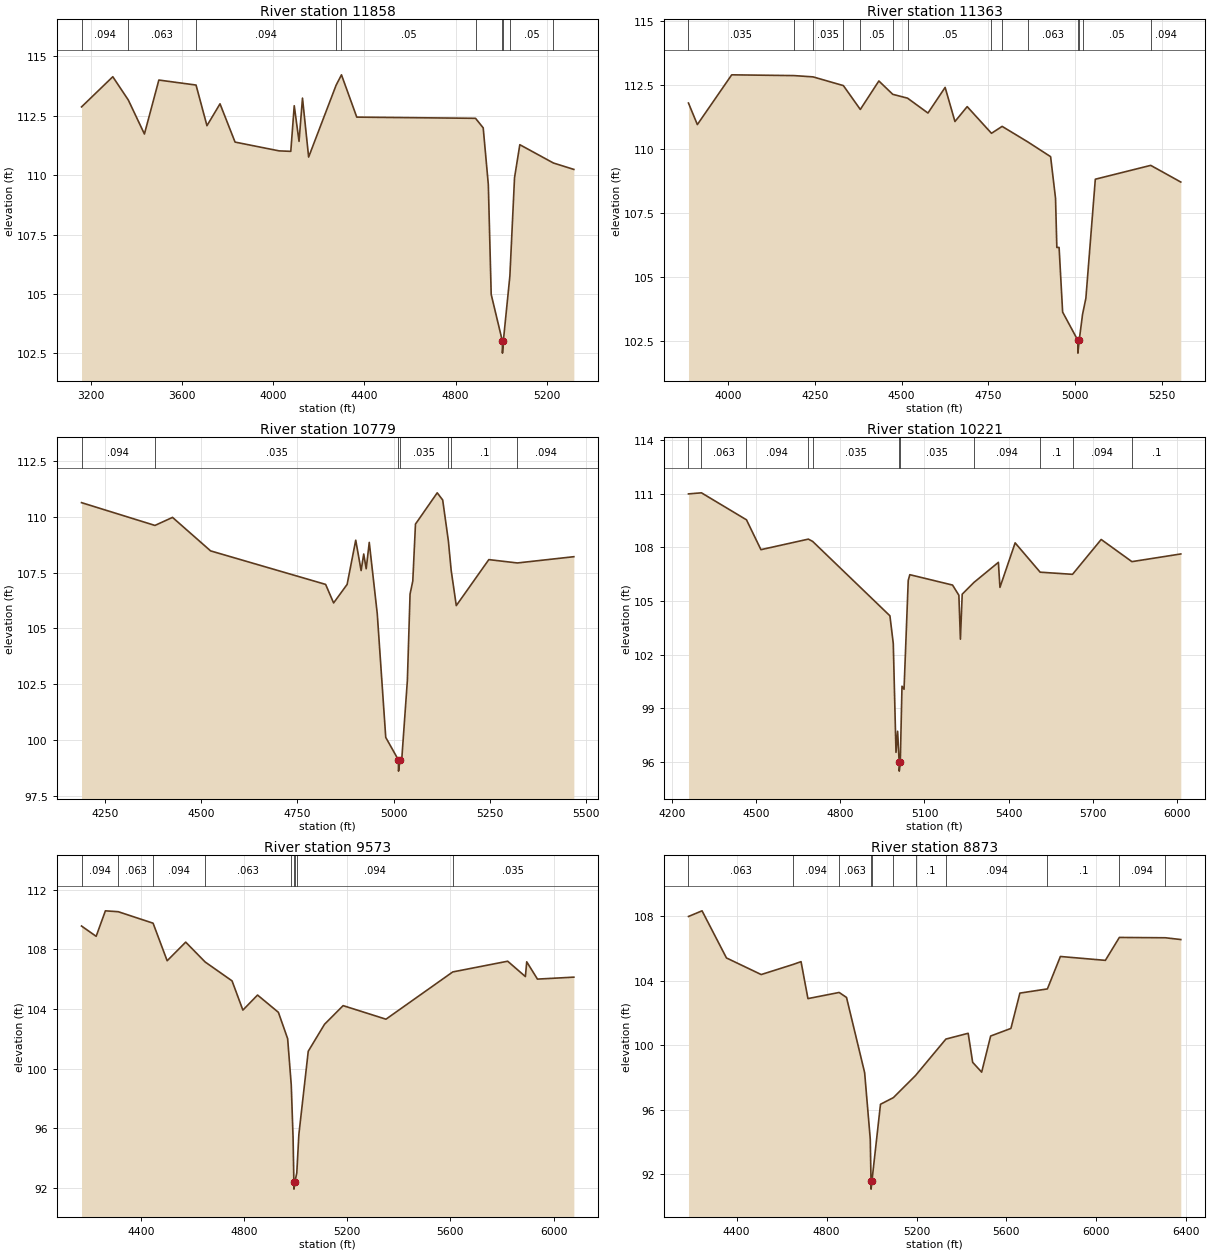
Type RM Length L Ch R = 1 ,11858   ,495,495,495
BEGIN DESCRIPTION:
Mapping XS 42f8cd0a
END DESCRIPTION:
XS GIS Cut Line= 3
      2613828.72      13501787.4      2612321.82     13502773.48
      2611971.16      13502852.9
#Sta/Elev= 30
  3158.8  112.87    3296  114.14  3364.1  113.16  3434.8  111.73  3498.1     114
  3661.3  113.79  3709.2  112.08  3766.5     113  3832.5  111.39  4025.8  111.02
  4077.1     111  4092.2  112.92  4113.3  111.42  4128.4  113.24  4155.4  110.76
  4275.8  113.78  4299.5  114.22  4366.6  112.44  4887.7  112.39  4921.4  111.99
  4943.9   109.6  4956.5  104.98  5005.7  103.01  5005.9  102.51  5009.7  103.01
  5038.5  105.76  5058.9  109.89  5082.1  111.28  5229.4  110.51  5319.2  110.24
#Mann= 10 ,-1 , 0
  3158.8    .094       0  3364.1    .063       0  3661.3    .094       0
  4275.8    .063       0  4299.5     .05       0  4887.7    .063       0
  5005.7     .05       0  5009.7    .063       0  5038.5     .05       0
  5229.4    .035       0
Bank Sta=5005.7,5009.7
XS Rating Curve= 0 ,0
Exp/Cntr=0.3,0.1

Type RM Length L Ch R = 1 ,11363   ,584,584,584
BEGIN DESCRIPTION:
Mapping XS 328a8b09
END DESCRIPTION:
XS GIS Cut Line= 3
      2612731.57     13501655.39      2611974.59     13502405.43
      2611675.81     13502594.28
#Sta/Elev= 30
  3885.6  111.79  3911.2  110.95  4010.2  112.89  4189.8  112.86  4244.6  112.81
  4332.1  112.47  4380.9  111.54  4434.4  112.65  4474.4  112.13  4517.1  111.98
  4575.9   111.4  4625.4   112.4  4653.7  111.07    4689  111.65    4759  110.61
  4789.7  110.88  4863.1  110.28  4929.4   109.7  4943.6  108.08  4947.4  106.16
  4953.9  106.16  4964.1  103.64  5007.9  102.54  5008.1  102.04  5011.9  102.54
  5021.5  103.55  5031.1  104.18  5058.3  108.82    5218  109.36  5304.7  108.71
#Mann= 14 ,-1 , 0
  3885.6    .035       0  4189.8    .094       0  4244.6    .035       0
  4332.1    .094       0  4380.9     .05       0  4474.4    .035       0
  4517.1     .05       0    4759    .063       0  4789.7     .05       0
  4863.1    .063       0  5007.9     .05       0  5011.9    .063       0
  5021.5     .05       0    5218    .094       0
Bank Sta=5007.9,5011.9
XS Rating Curve= 0 ,0
Exp/Cntr=0.3,0.1

Type RM Length L Ch R = 1 ,10779   ,558,558,558
BEGIN DESCRIPTION:
Mapping XS 07caf025
END DESCRIPTION:
XS GIS Cut Line= 3
      2611939.85     13501537.39      2611432.93     13502169.32
      2611096.77     13502499.62
#Sta/Elev= 30
  4187.9  110.63    4379  109.61  4424.7  109.97  4523.9  108.47  4823.2  106.97
    4844  106.14  4879.2  106.97  4901.6  108.95  4915.6  107.59  4922.4  108.33
  4928.8  107.67  4936.8  108.85  4957.6  105.66  4979.7  100.12  5012.7   99.11
    5013   98.61  5016.7   99.11  5021.8   99.24    5036  102.67    5043  106.54
  5050.1  107.12  5057.1  109.67  5113.7  111.07  5127.9  110.75  5142.7  108.92
    5150   107.6  5163.3  106.02    5248  108.08  5322.3  107.93  5469.3  108.21
#Mann= 7 ,-1 , 0
  4187.9    .094       0    4379    .035       0  5012.7    .035       0
  5016.7    .035       0  5142.7    .094       0    5150      .1       0
  5322.3    .094       0
Bank Sta=5012.7,5016.7
XS Rating Curve= 0 ,0
Exp/Cntr=0.3,0.1

Type RM Length L Ch R = 1 ,10221   ,648,648,648
BEGIN DESCRIPTION:
Mapping XS 36ab60c7
END DESCRIPTION:
XS GIS Cut Line= 3
      2611273.18     13501398.52      2610877.37      13502058.2
      2610446.81      13502947.1
#Sta/Elev= 30
  4257.7  110.99    4304  111.05  4464.7  109.54  4516.3  107.87  4685.6  108.46
    4701  108.33  4976.6  104.17  4988.6  102.62  4998.3   96.53  5004.1   97.71
  5009.6   95.98  5009.9   95.48  5013.6   95.98  5019.7  100.23    5027  100.06
    5042  106.15  5047.6  106.47  5200.1  105.89  5222.7  105.32  5228.2  102.86
  5234.6  105.38  5275.9  106.03  5363.7  107.16  5369.3  105.76  5423.5  108.25
  5512.8  106.61  5628.3  106.49  5730.6  108.44  5840.2   107.2  6014.7  107.63
#Mann= 11 ,-1 , 0
  4257.7    .094       0    4304    .063       0  4464.7    .094       0
  4685.6    .063       0    4701    .035       0  5009.6    .035       0
  5013.6    .035       0  5275.9    .094       0  5512.8      .1       0
  5628.3    .094       0  5840.2      .1       0
Bank Sta=5009.6,5013.6
XS Rating Curve= 0 ,0
Exp/Cntr=0.3,0.1

Type RM Length L Ch R = 1 ,9573    ,700,700,700
BEGIN DESCRIPTION:
Mapping XS 6870a990
END DESCRIPTION:
XS GIS Cut Line= 3
      2611030.15     13501280.42      2610342.65      13501745.7
       2610085.7     13502794.33
#Sta/Elev= 30
  4169.1  109.56  4225.8  108.87  4261.7  110.58  4311.6  110.52  4446.7  109.75
  4501.3  107.23  4573.2  108.48  4648.5  107.15    4753  105.88    4795  103.92
  4851.9  104.93  4932.8  103.77  4968.7     102  4982.7   98.89  4989.7   95.36
  4992.8   92.41  4993.1   91.91  4996.8   92.41  5004.1   92.99  5012.2   95.58
  5048.6  101.16  5111.8  102.97  5183.9  104.22  5350.1  103.31  5609.1  106.48
  5822.2   107.2  5890.9  106.17  5896.1  107.16  5937.7     106  6078.9  106.13
#Mann= 9 ,-1 , 0
  4169.1    .094       0  4311.6    .063       0  4446.7    .094       0
  4648.5    .063       0  4982.7    .035       0  4992.8    .035       0
  4996.8    .035       0  5004.1    .094       0  5609.1    .035       0
Bank Sta=4992.8,4996.8
XS Rating Curve= 0 ,0
Exp/Cntr=0.3,0.1

Type RM Length L Ch R = 1 ,8873    ,791,791,791
BEGIN DESCRIPTION:
Mapping XS 4c644e2a
END DESCRIPTION:
XS GIS Cut Line= 4
      2610613.47     13500967.93      2609842.65     13501252.65
       2609835.7     13501794.32      2609863.47     13502620.31
#Sta/Elev= 30
  4185.7  107.98  4246.1  108.33  4354.6  105.41  4509.2  104.38  4651.9  105.01
  4686.4  105.18  4717.1  102.89    4856  103.27  4888.7  102.96  4969.3    98.3
  4994.3   94.18  4997.7   91.58  4997.9   91.08  5001.7   91.58  5039.8   96.34
    5097   96.75  5195.6   98.12  5330.7  100.38  5429.8  100.74  5449.8   98.94
  5489.8   98.33  5529.8  100.57  5619.9  101.04  5659.9  103.23  5782.2  103.49
    5840   105.5  6040.1  105.26  6102.3  106.68  6307.1  106.66  6375.6  106.55
#Mann= 11 ,-1 , 0
  4185.7    .063       0  4651.9    .094       0    4856    .063       0
  4997.7     .05       0  5001.7    .063       0    5097    .094       0
  5195.6      .1       0  5330.7    .094       0  5782.2      .1       0
  6102.3    .094       0  6307.1      .1       0
Bank Sta=4997.7,5001.7
XS Rating Curve= 0 ,0
Exp/Cntr=0.3,0.1

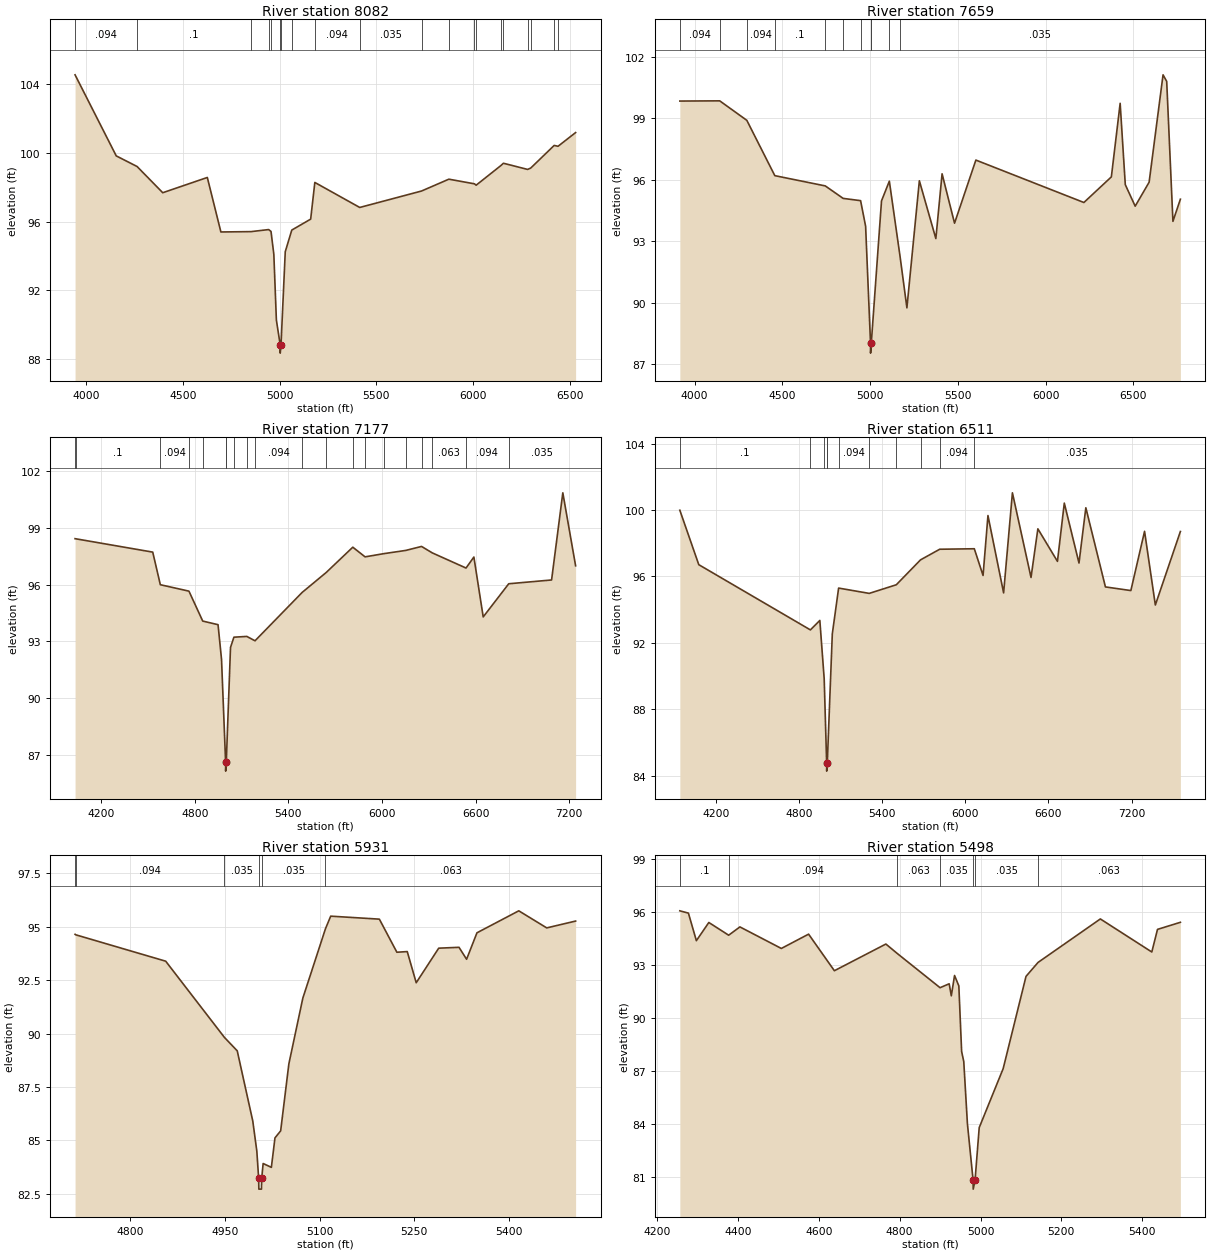
Type RM Length L Ch R = 1 ,8082    ,423,423,423
BEGIN DESCRIPTION:
Mapping XS 25307dc5
END DESCRIPTION:
XS GIS Cut Line= 4
      2610407.43     13500769.49      2609456.07     13500720.88
      2609199.13     13500825.04      2608227.62     13501771.39
#Sta/Elev= 30
  3943.7  104.56  4156.4   99.83  4264.1   99.21  4396.7   97.68    4627   98.57
  4697.1   95.39  4852.8   95.41  4943.9   95.53  4956.1   95.42  4970.7   94.08
  4983.8   90.25  5003.3   88.82  5003.6   88.32  5007.8   88.82  5029.7   94.24
  5063.4    95.5    5161   96.14  5182.5   98.28  5414.5   96.82  5733.9   97.78
  5874.9   98.47  6006.9    98.2  6015.9   98.12  6144.3   99.27    6157    99.4
  6281.7   99.04    6298   99.12  6419.1  100.44    6439  100.39  6529.8  101.19
#Mann= 20 ,-1 , 0
  3943.7    .094       0  4264.1      .1       0  4852.8    .094       0
  4943.9    .063       0  4956.1    .035       0  5003.3    .035       0
  5007.8    .035       0  5063.4    .063       0  5182.5    .094       0
  5414.5    .035       0  5733.9    .035       0  5874.9    .035       0
  6006.9    .094       0  6015.9    .035       0  6144.3    .094       0
    6157    .035       0  6281.7    .094       0    6298    .035       0
  6419.1    .094       0    6439    .035       0
Bank Sta=5003.3,5007.8
XS Rating Curve= 0 ,0
Exp/Cntr=0.3,0.1

Type RM Length L Ch R = 1 ,7659    ,482,482,482
BEGIN DESCRIPTION:
Mapping XS 534e4e70
END DESCRIPTION:
XS GIS Cut Line= 4
      2610240.84      13500443.1      2609351.91     13500387.54
      2609004.68     13500429.21      2607706.78     13501385.94
#Sta/Elev= 30
  3915.8   99.85  4143.1   99.86  4297.5   98.91  4457.1   96.21  4744.5   95.71
  4846.6    95.1    4946   94.99  4974.6   93.74  5002.5   88.05  5002.8   87.55
    5007   88.05  5065.2   94.98  5109.8   95.94    5171   92.26  5209.9   89.76
  5280.9   95.96  5374.9   93.14  5410.4    96.3  5481.4   93.89    5603   96.97
  6218.6    94.9  6375.2   96.15  6425.3   99.74  6454.6   95.77    6511   94.72
  6590.4   95.89  6669.8  101.13  6690.6  100.81  6726.1   93.98  6768.6   95.06
#Mann= 11 ,-1 , 0
  3915.8    .094       0  4143.1      .1       0  4297.5    .094       0
  4457.1      .1       0  4744.5    .094       0  4846.6    .063       0
    4946    .035       0  5002.5    .035       0    5007    .035       0
  5109.8    .063       0    5171    .035       0
Bank Sta=5002.5,5007
XS Rating Curve= 0 ,0
Exp/Cntr=0.3,0.1

Type RM Length L Ch R = 1 ,7177    ,666,666,666
BEGIN DESCRIPTION:
Mapping XS 410ed7f8
END DESCRIPTION:
XS GIS Cut Line= 4
      2610219.96     13499790.32      2609428.29     13499970.88
      2609206.07      13500005.6      2607403.32     13501216.69
#Sta/Elev= 30
  4032.9   98.42  4039.7   98.41  4530.8   97.71  4579.5   95.99  4762.9   95.65
  4851.3   94.07  4949.4   93.88  4971.8   92.05  4997.8   86.65  4998.1   86.15
  5002.4   86.65  5029.4   92.68  5051.2   93.22    5134   93.26  5186.5   93.03
  5488.3   95.58  5643.5   96.64  5813.3   97.97    5892   97.46  6012.7   97.63
  6152.9    97.8    6254   98.01  6322.7   97.67  6539.2   96.87  6589.5   97.45
  6649.3   94.29  6812.9   96.04  7087.6   96.24  7159.6  100.84  7241.6   96.99
#Mann= 20 ,-1 , 0
  4032.9    .094       0  4039.7      .1       0  4579.5    .094       0
  4762.9      .1       0  4851.3    .094       0  4997.8     .05       0
  5002.4    .063       0  5051.2    .035       0    5134    .063       0
  5186.5    .094       0  5488.3    .063       0  5643.5    .035       0
  5813.3    .035       0    5892    .094       0  6012.7    .063       0
  6152.9    .035       0    6254    .094       0  6322.7    .063       0
  6539.2    .094       0  6812.9    .035       0
Bank Sta=4997.8,5002.4
XS Rating Curve= 0 ,0
Exp/Cntr=0.3,0.1

Type RM Length L Ch R = 1 ,6511    ,580,580,580
BEGIN DESCRIPTION:
Mapping XS 14813d8e
END DESCRIPTION:
XS GIS Cut Line= 4
      2610081.12     13499304.21      2609053.29     13499408.38
      2608796.35     13499491.71      2607149.51     13501115.43
#Sta/Elev= 30
  3937.1   99.99  4073.9   96.71  4880.2   92.78  4948.4   93.35  4979.8   89.84
  4997.6   84.77  4997.9   84.27  5002.3   84.77  5038.5   92.54  5084.1    95.3
  5305.2   94.98  5500.8    95.5  5675.7      97  5814.2   97.64  6064.3   97.67
  6127.5   96.06  6162.9   99.67    6276   95.01  6339.6  101.04    6474   95.94
  6523.5   98.87  6664.9   96.91  6714.4  100.42  6820.5   96.81    6870  100.14
  7011.5   95.37  7195.2   95.15  7294.2   98.72  7372.1   94.28    7553   98.71
#Mann= 11 ,-1 , 0
  3937.1      .1       0  4880.2    .094       0  4979.8    .063       0
  4997.6     .05       0  5002.3    .063       0  5084.1    .094       0
  5305.2    .063       0  5500.8    .094       0  5675.7    .063       0
  5814.2    .094       0  6064.3    .035       0
Bank Sta=4997.6,5002.3
XS Rating Curve= 0 ,0
Exp/Cntr=0.3,0.1

Type RM Length L Ch R = 1 ,5931    ,433,433,433
BEGIN DESCRIPTION:
Mapping XS a24e8d3d
END DESCRIPTION:
XS GIS Cut Line= 3
      2609350.26      13498834.2      2609069.05     13498933.15
      2608631.55     13499162.31
#Sta/Elev= 30
  4713.2   94.65  4713.9   94.63  4856.6   93.39  4949.5   89.82  4969.8   89.19
  4994.4    85.9  5000.8   84.49  5003.7   83.21    5004   82.71  5008.1   82.71
  5008.5   83.21  5010.8   83.91  5023.8   83.73  5029.5   85.11  5038.5   85.44
  5051.5   88.58  5073.6   91.66  5109.4   94.91  5117.7    95.5  5194.7   95.36
  5222.4   93.81  5238.8   93.84    5253   92.38  5288.6      94  5320.7   94.04
  5332.7   93.48  5349.1   94.72  5415.3   95.75  5459.5   94.95  5505.2   95.27
#Mann= 6 ,-1 , 0
  4713.2      .1       0  4713.9    .094       0  4949.5    .035       0
  5003.7    .035       0  5008.5    .035       0  5109.4    .063       0
Bank Sta=5003.7,5008.5
XS Rating Curve= 0 ,0
Exp/Cntr=0.3,0.1

Type RM Length L Ch R = 1 ,5498    ,474,474,474
BEGIN DESCRIPTION:
WHISPERING CREEK 11.0
END DESCRIPTION:
XS GIS Cut Line= 3
      2609474.98     13498425.01        2608775.       13498675.
      2608424.97     13499025.03
#Sta/Elev= 30
  4256.2   96.06  4277.4   95.93  4297.1   94.37  4327.9    95.4    4377   94.68
  4404.8   95.15  4507.3   93.93  4574.7   94.74  4638.5   92.67  4765.9   94.18
  4794.4   93.64  4899.9   91.71  4922.5   91.93  4927.8   91.25  4935.8    92.4
  4946.4   91.81  4953.3    88.1  4958.6   87.53  4967.6   84.02  4981.7   80.81
    4982   80.31  4986.5   80.81  4996.8   83.79  5056.1   87.13  5112.6   92.35
  5142.4   93.14  5296.5    95.6  5423.8   93.73  5437.9   95.01  5494.5   95.41
#Mann= 7 ,-1 , 0
  4256.2      .1       0    4377    .094       0  4794.4    .063       0
  4899.9    .035       0  4981.7    .035       0  4986.5    .035       0
  5142.4    .063       0
Bank Sta=4981.7,4986.5
XS Rating Curve= 0 ,0
Exp/Cntr=0.3,0.1

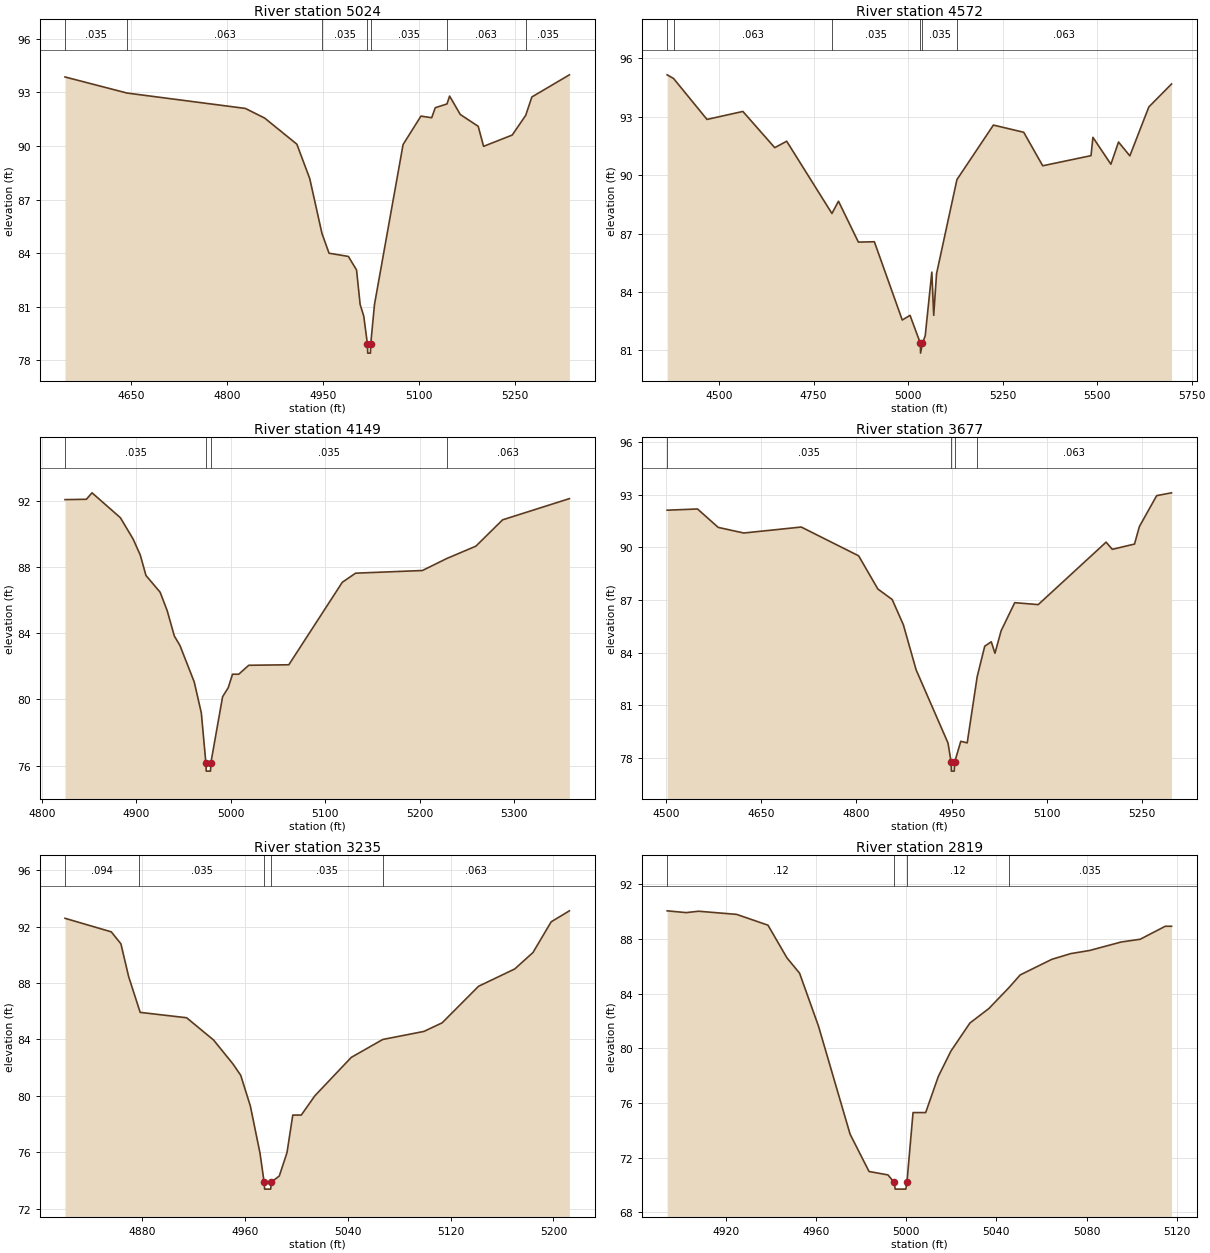
Type RM Length L Ch R = 1 ,5024    ,452,452,452
BEGIN DESCRIPTION:
WHISPERING CREEK 10.0
END DESCRIPTION:
XS GIS Cut Line= 3
      2608975.05     13498274.99        2608525.       13498325.
      2608225.02     13498474.99
#Sta/Elev= 30
  4546.7   93.86  4643.7   92.96  4828.5    92.1  4858.7   91.56    4909    90.1
  4929.1   88.18  4948.2   85.11  4959.3      84  4989.5   83.82  5002.3   83.06
  5007.9   81.13  5013.5   80.49  5019.3   78.91  5019.7   78.41    5024   78.41
  5024.4   78.91  5030.3   81.13    5075   90.08  5102.9   91.67  5119.7   91.58
  5125.3   92.14  5143.6   92.35  5147.7   92.79  5164.4   91.76  5192.4    91.1
  5200.8   89.98  5245.5   90.61  5266.6   91.71  5276.2   92.74  5334.9   93.98
#Mann= 7 ,-1 , 0
  4546.7    .035       0  4643.7    .063       0  4948.2    .035       0
  5019.3    .035       0  5024.4    .035       0  5143.6    .063       0
  5266.6    .035       0
Bank Sta=5019.3,5024.4
XS Rating Curve= 0 ,0
Exp/Cntr=0.3,0.1

Type RM Length L Ch R = 1 ,4572    ,423,423,423
BEGIN DESCRIPTION:
WHISPERING CREEK 9.0
END DESCRIPTION:
XS GIS Cut Line= 3
      2609174.99       13498125.        2608575.       13497925.
      2607875.02       13497975.
#Sta/Elev= 30
  4362.6   95.15  4379.7   94.96    4468   92.86  4562.9   93.27  4647.2   91.41
  4678.8   91.74  4798.5   88.03  4815.8   88.66  4868.5   86.56  4910.7   86.58
  4984.5   82.56  5005.1    82.8  5032.5   81.36  5032.9   80.86  5037.8   81.36
  5045.2   81.75  5062.7   85.02  5067.7    82.8  5075.2   84.94  5129.1   89.77
  5225.6   92.57  5305.8    92.2    5356   90.48  5483.8      91  5488.8   91.94
  5536.4   90.56  5556.5    91.7  5586.5   90.99  5636.7    93.5  5696.8   94.68
#Mann= 6 ,-1 , 0
  4362.6    .094       0  4379.7    .063       0  4798.5    .035       0
  5032.5    .035       0  5037.8    .035       0  5129.1    .063       0
Bank Sta=5032.5,5037.8
XS Rating Curve= 0 ,0
Exp/Cntr=0.3,0.1

Type RM Length L Ch R = 1 ,4149    ,472,472,472
BEGIN DESCRIPTION:
WHISPERING CREEK 8.0
END DESCRIPTION:
XS GIS Cut Line= 3
      2608625.02     13497474.97        2608525.       13497625.
      2608274.98     13497875.02
#Sta/Elev= 30
  4824.4   92.06    4847   92.08    4853   92.47    4883   90.97  4896.6   89.67
  4904.1   88.71  4910.1   87.48  4925.1   86.47  4932.6   85.35  4940.1   83.83
  4946.1   83.25  4961.2   81.05  4968.7   79.18  4973.5   76.17  4973.9   75.67
  4978.4   75.67  4978.8   76.17  4991.2   80.16  4997.2   80.71  5001.7   81.52
  5008.3   81.52  5018.9   82.06  5061.3   82.09  5117.9   87.07    5132   87.62
  5202.7   87.78  5228.3    88.5  5259.3   89.25  5287.6   90.84  5358.3   92.12
#Mann= 4 ,-1 , 0
  4824.4    .035       0  4973.5    .035       0  4978.8    .035       0
  5228.3    .063       0
Bank Sta=4973.5,4978.8
XS Rating Curve= 0 ,0
Exp/Cntr=0.3,0.1

Type RM Length L Ch R = 1 ,3677    ,442,442,442
BEGIN DESCRIPTION:
WHISPERING CREEK 7.0
END DESCRIPTION:
XS GIS Cut Line= 3
      2608675.03       13497325.        2608175.       13497375.
      2607924.97     13497525.02
#Sta/Elev= 30
    4502   92.12  4549.8   92.19  4582.4   91.14  4622.6   90.82  4713.1   91.16
  4803.5   89.52  4833.7   87.63  4856.3   87.03  4873.9   85.59    4894   83.02
  4944.2   78.85  4949.1   77.75  4949.5   77.25    4954   77.25  4954.5   77.75
  4964.3   78.95  4974.4   78.86  4990.1   82.63    5002   84.37  5012.3   84.62
  5018.1   83.97  5027.8   85.25  5049.2   86.85  5086.2   86.74  5193.1    90.3
  5202.8   89.89  5237.8   90.19  5245.5   91.19  5272.7   92.95  5296.1   93.11
#Mann= 4 ,-1 , 0
    4502    .035       0  4949.1     .05       0  4954.5    .035       0
  4990.1    .063       0
Bank Sta=4949.1,4954.5
XS Rating Curve= 0 ,0
Exp/Cntr=0.3,0.1

Type RM Length L Ch R = 1 ,3235    ,416,416,416
BEGIN DESCRIPTION:
WHISPERING CREEK 6.0
END DESCRIPTION:
XS GIS Cut Line= 3
      2608074.98     13496925.04        2607975.       13497075.
      2607824.98     13497225.02
#Sta/Elev= 30
    4820   92.59    4856   91.63  4863.5   90.78  4869.5   88.46  4877.6   86.17
  4878.5   85.92  4914.6   85.54  4935.6   83.96  4950.7   82.26  4956.7   81.46
  4964.2   79.28  4971.7   75.94  4974.9   73.89  4975.3   73.39    4980   73.39
  4980.5   73.89  4986.7   74.32  4992.7   75.98  4997.2   78.64  5003.8   78.64
  5014.4   80.01  5042.7   82.73  5067.2      84  5099.2   84.57  5113.4   85.18
  5141.7   87.77  5169.9      89  5184.1   90.17  5198.2   92.34  5212.4   93.12
#Mann= 5 ,-1 , 0
    4820    .094       0  4877.6    .035       0  4974.9    .035       0
  4980.5    .035       0  5067.2    .063       0
Bank Sta=4974.9,4980.5
XS Rating Curve= 0 ,0
Exp/Cntr=0.3,0.1

Type RM Length L Ch R = 1 ,2819    ,476,476,476
BEGIN DESCRIPTION:
WHISPERING CREEK 5.0
END DESCRIPTION:
XS GIS Cut Line= 3
      2607775.02     13496774.99        2607675.       13496825.
      2607575.03     13496874.99
#Sta/Elev= 30
  4894.1   90.06  4902.5   89.93  4908.1   90.03  4924.9    89.8  4938.8   89.01
  4947.2   86.62  4952.8    85.5  4961.2   81.62  4975.2   73.72  4983.6   70.99
    4992   70.74  4994.7    70.2  4995.2    69.7  4999.9    69.7  5000.4    70.2
  5003.1    75.3  5008.7    75.3  5014.3   77.94  5019.9    79.8  5028.3   81.85
  5036.7   82.91  5045.5   84.42  5050.6   85.37  5064.6   86.51    5073   86.93
  5081.4   87.16  5095.4   87.78  5103.8   87.98  5114.9   88.93  5117.7   88.93
#Mann= 4 ,-1 , 0
  4894.1     .12       0  4994.7     .05       0  5000.4     .12       0
  5045.5    .035       0
Bank Sta=4994.7,5000.4
XS Rating Curve= 0 ,0
Exp/Cntr=0.3,0.1

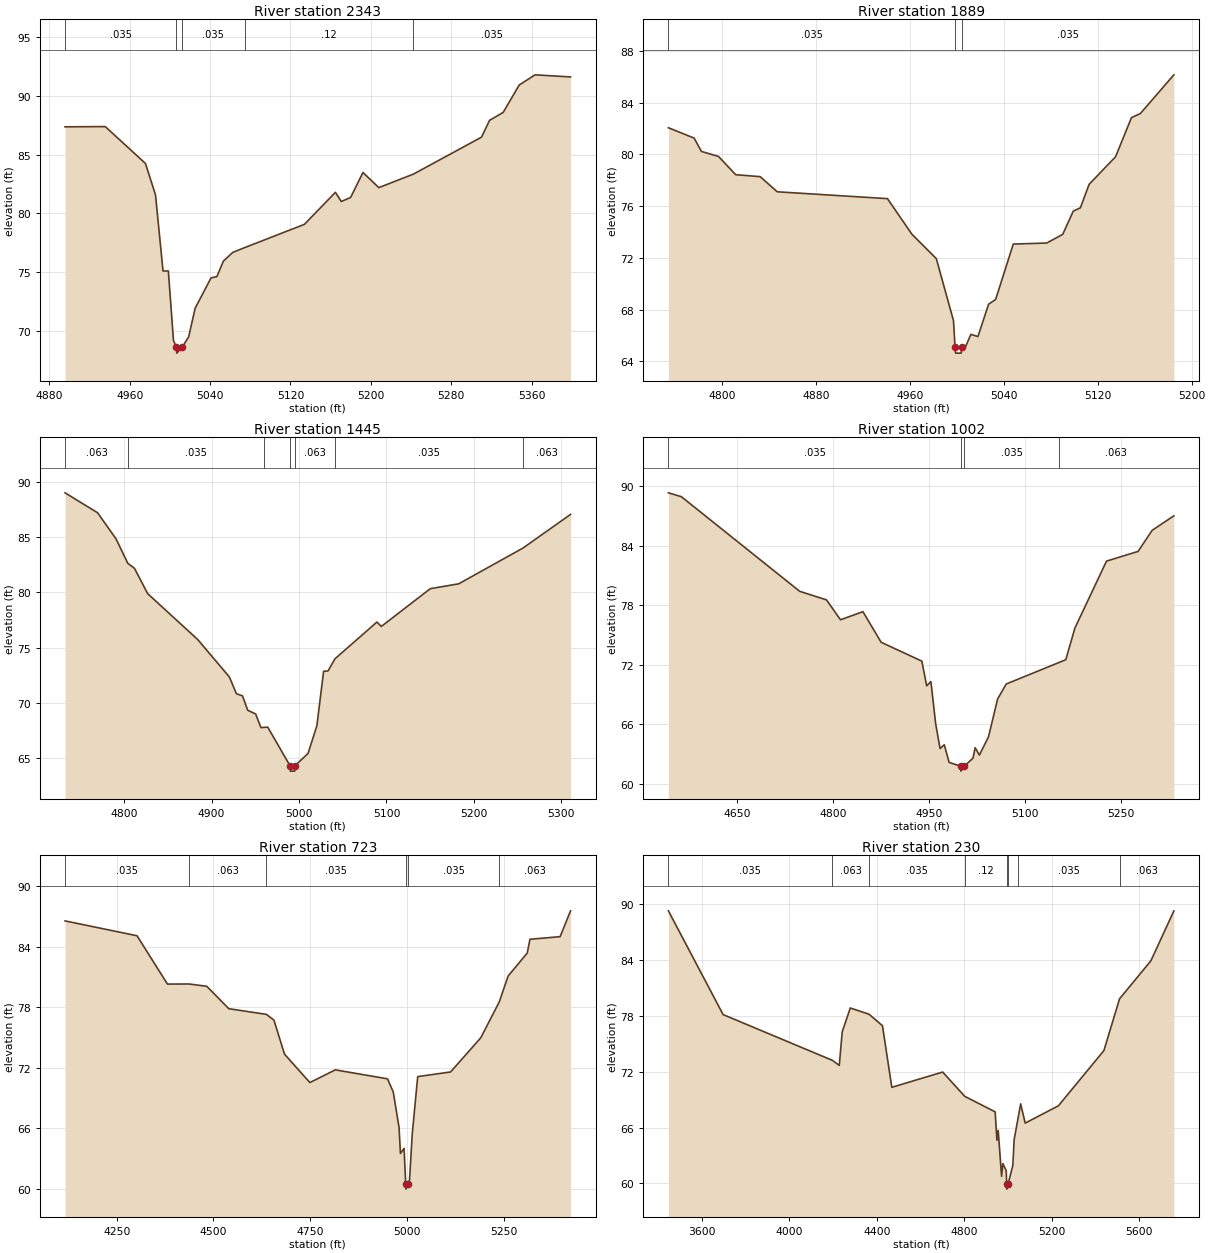
Type RM Length L Ch R = 1 ,2343    ,454,454,454
BEGIN DESCRIPTION:
WHISPERING CREEK 4.0
END DESCRIPTION:
XS GIS Cut Line= 3
        2607475.     13496325.04        2607475.       13496425.
      2607274.99     13496775.02
#Sta/Elev= 30
  4895.7   87.37  4935.7   87.39  4975.7   84.25  4985.7   81.58  4993.2   75.09
  4998.5   75.09  5003.6   69.18  5006.5   68.59  5006.9   68.09  5012.2   68.59
  5018.7   69.47  5025.2   71.92    5041    74.5  5046.8   74.61  5053.3   75.93
  5062.6   76.67  5074.5   77.08  5133.9   79.06  5164.8   81.79  5170.6   81.01
  5179.9   81.35  5192.2   83.48    5208   82.19  5242.4   83.34  5310.2   86.49
  5318.2   87.92  5331.8    88.6  5347.7   90.93  5363.5    91.8  5398.8   91.62
#Mann= 5 ,-1 , 0
  4895.7    .035       0  5006.5    .035       0  5012.2    .035       0
  5074.5     .12       0  5242.4    .035       0
Bank Sta=5006.5,5012.2
XS Rating Curve= 0 ,0
Exp/Cntr=0.3,0.1

Type RM Length L Ch R = 1 ,1889    ,444,444,444
BEGIN DESCRIPTION:
WHISPERING CREEK 3.0
END DESCRIPTION:
XS GIS Cut Line= 3
      2607275.02     13496124.99        2607075.       13496275.
        2606925.       13496375.
#Sta/Elev= 30
  4754.5   82.05  4776.4   81.25  4782.6   80.22  4797.2   79.83  4811.8   78.42
  4832.6   78.27  4847.2    77.1    4941   76.57  4961.8   73.82  4982.6   71.93
  4997.2   67.14  4998.5   65.13    4999   64.63  5003.8   64.63  5004.2   65.13
  5007.5   65.13    5012   66.08    5018   65.91  5027.1   68.41  5033.1   68.78
  5048.1   73.06  5076.6   73.14  5090.2   73.81  5099.2   75.61  5105.2   75.86
  5112.7   77.68  5135.2   79.81  5148.7   82.83  5156.3   83.15  5184.8   86.14
#Mann= 3 ,-1 , 0
  4754.5    .035       0  4998.5    .035       0  5004.2    .035       0
Bank Sta=4998.5,5004.2
XS Rating Curve= 0 ,0
Exp/Cntr=0.3,0.1

Type RM Length L Ch R = 1 ,1445    ,443,443,443
BEGIN DESCRIPTION:
WHISPERING CREEK 2.0
END DESCRIPTION:
XS GIS Cut Line= 3
      2606921.94     13495751.19        2606775.       13495975.
      2606724.25     13496281.19
#Sta/Elev= 30
  4732.4   88.98  4769.6   87.18  4790.7   84.82  4804.2   82.61  4811.8   82.16
  4826.9   79.87  4884.1   75.73  4920.3   72.35  4928.4   70.83  4935.3   70.64
  4941.3   69.34  4950.4      69  4956.4   67.77  4959.6   67.79  4964.2   67.81
  4989.6   64.34  4990.1   63.84    4995   63.84  4995.5   64.34  5010.3   65.44
  5020.4   67.94  5028.1   72.86  5033.2   72.89    5041   73.98  5089.1   77.31
  5094.1   76.91  5150.1   80.32  5182.6   80.76  5256.3      84  5310.5   87.03
#Mann= 7 ,-1 , 0
  4732.4    .063       0  4804.2    .035       0  4959.6    .063       0
  4989.6     .05       0  4995.5    .063       0    5041    .035       0
  5256.3    .063       0
Bank Sta=4989.6,4995.5
XS Rating Curve= 0 ,0
Exp/Cntr=0.3,0.1

Type RM Length L Ch R = 1 ,1002    ,279,279,279
BEGIN DESCRIPTION:
Mapping XS e1b90464
END DESCRIPTION:
XS GIS Cut Line= 3
      2606678.88     13495679.65      2606366.36     13496039.05
       2606569.5     13496278.65
#Sta/Elev= 30
  4542.3   89.33  4562.6   88.94  4747.7   79.39  4789.5   78.53  4811.4   76.52
  4846.5   77.34    4875   74.25  4938.6   72.35  4946.2   69.86  4952.8   70.28
  4960.2   66.05  4967.1   63.53  4973.7   63.91  4981.3   62.13  4999.2   61.75
  4999.7   61.25  5005.1   61.75  5018.6   62.56    5022   63.61  5028.6   62.87
  5042.9   64.72  5057.1   68.53  5070.6   70.04  5152.7    72.2  5163.7   72.49
    5178   75.69  5227.4   82.44  5276.8   83.42  5298.8   85.55  5332.7   87.01
#Mann= 4 ,-1 , 0
  4542.3    .035       0  4999.2    .035       0  5005.1    .035       0
  5152.7    .063       0
Bank Sta=4999.2,5005.1
XS Rating Curve= 0 ,0
Exp/Cntr=0.3,0.1

Type RM Length L Ch R = 1 ,723     ,493,493,493
BEGIN DESCRIPTION:
Mapping XS 91a86c2f
END DESCRIPTION:
XS GIS Cut Line= 3
      2606595.52     13495346.35      2606105.94     13496065.09
      2606406.69     13496381.39
#Sta/Elev= 30
  4116.6   86.54  4302.5   85.07  4381.2   80.28    4437   80.29  4482.8   80.06
  4539.7   77.84  4636.8   77.28  4656.3   76.71  4683.6   73.34  4749.2   70.52
  4814.9   71.78  4949.8   70.89  4964.6   69.59  4979.6   66.08  4983.2   63.49
  4992.6      64  4996.8   60.46  4997.3   59.96  5002.8   60.46  5006.7   60.89
  5013.7   65.43  5027.8   71.11  5112.7   71.57  5190.8   74.96  5238.4    78.5
  5261.5   81.08  5310.9   83.36  5317.8   84.72  5395.8   84.98  5422.7   87.54
#Mann= 6 ,-1 , 0
  4116.6    .035       0    4437    .063       0  4636.8    .035       0
  4996.8    .035       0  5002.8    .035       0  5238.4    .063       0
Bank Sta=4996.8,5002.8
XS Rating Curve= 0 ,0
Exp/Cntr=0.3,0.1

Type RM Length L Ch R = 1 ,230     ,0,0,0
BEGIN DESCRIPTION:
WHISPERING CREEK 1.0
END DESCRIPTION:
XS GIS Cut Line= 3
       2606460.1     13494846.35      2605654.97     13496174.93
      2606277.47     13496609.36
#Sta/Elev= 30
  3446.5   89.31  3696.9   78.15  4196.8   73.23  4228.3   72.69  4241.8    76.3
  4278.7   78.86  4364.6   78.19    4426   76.95  4468.7   70.33  4701.4   71.97
  4802.3   69.36  4941.6   67.69  4949.6   64.63  4955.4    65.7  4970.9   60.76
  4976.8   62.13  4992.3   61.36  4994.1   59.88  4994.6   59.38  5000.1   59.88
  5022.3   61.93  5028.4    64.7    5046   66.97  5058.1   68.55    5079   66.48
  5230.8   68.34    5439   74.28  5510.7   79.85  5653.9   83.93  5759.1    89.3
#Mann= 8 ,-1 , 0
  3446.5    .035       0  4196.8    .063       0  4364.6    .035       0
  4802.3     .12       0  4994.1     .05       0  5000.1     .12       0
    5046    .035       0  5510.7    .063       0
Bank Sta=4994.1,5000.1
XS Rating Curve= 0 ,0
Exp/Cntr=0.3,0.1

Chan Stop Cuts=-1
Use User Specified Reach Order=0
Composite Channel Slope=5