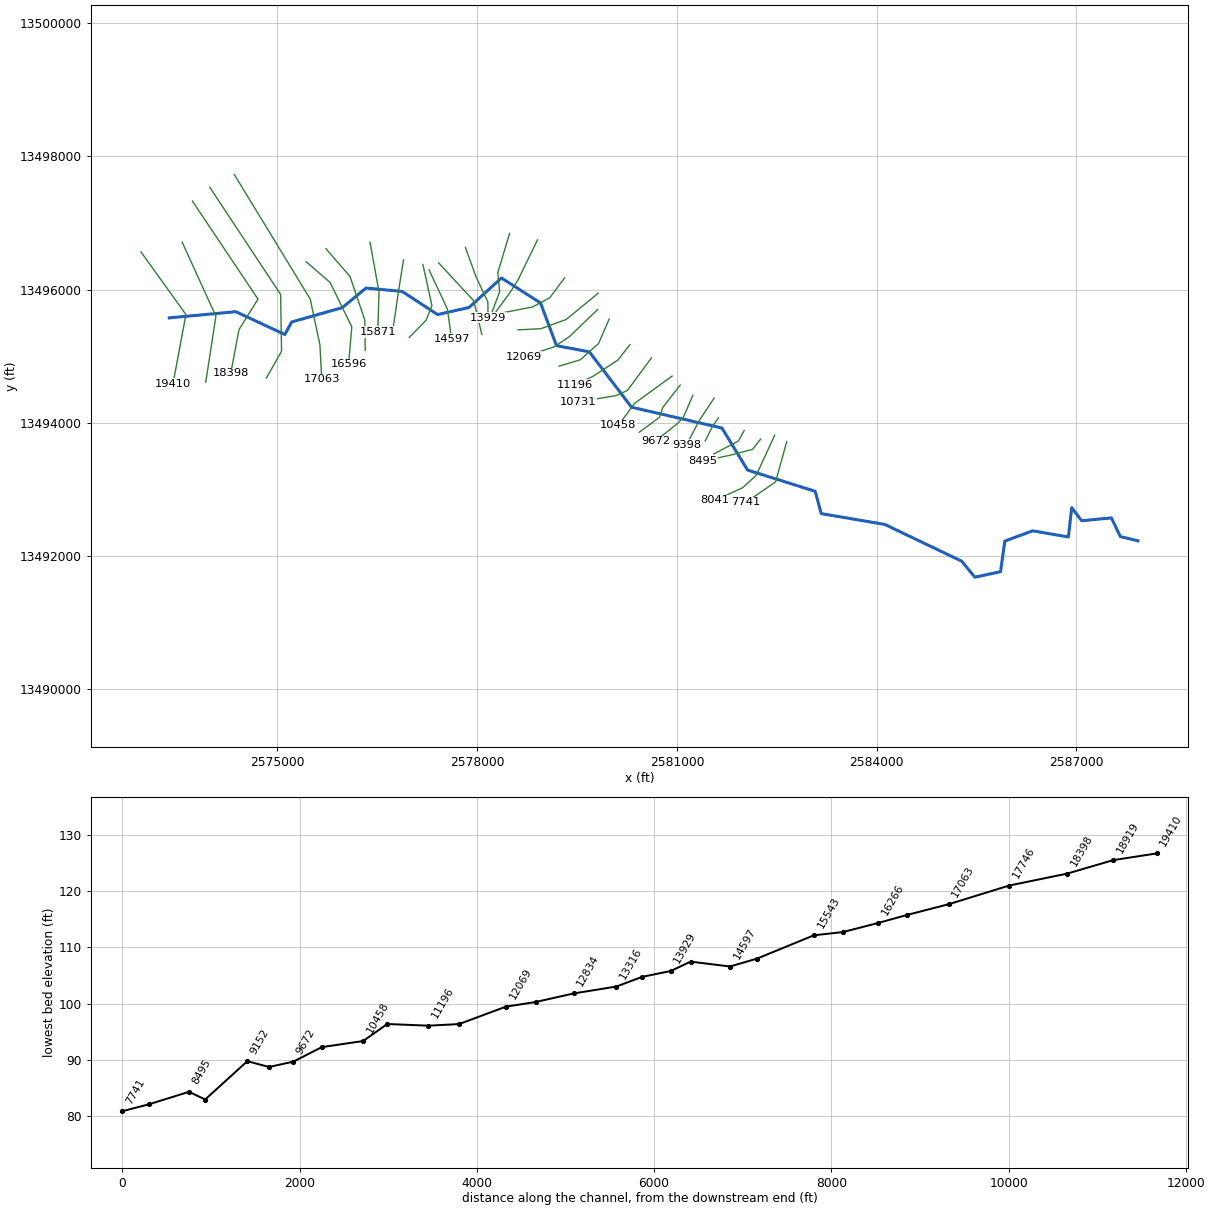
--- WRIGHT CREEK.prj (project) ---

Proj Title=WRIGHT CREEK Base Level Engineering
Current Plan=p01
Default Exp/Contr=0.3,0.1
English Units
Geom File=g01
Flow File=f01
Plan File=p01
Y Axis Title=Elevation
X Axis Title(PF)=Main Channel Distance
X Axis Title(XS)=Station
BEGIN DESCRIPTION:
WRIGHT CREEK
END DESCRIPTION:
DSS Export Rating Curves= 0
DSS Export Rating Curve Sorted= 0
DSS Export Volume Flow Curves= 0
DXF OffsetX= 0
DXF OffsetY= 0
DXF ScaleX= 1
DXF ScaleY= 10

--- WRIGHT CREEK.p01 (plan) ---

Plan Title=Multiple Run
Short Identifier=Multiple
Geom File=g01
Flow File=f01
Subcritical Flow
K Sum by GR= 0
Std Step Tol= 0.01
Critical Tol= 0.01
Num of Std Step Trials= 20
Max Error Tol= 0.3
Flow Tol Ratio= 0.001
Split Flow NTrial= 30
Split Flow Tol= 0.02
Split Flow Ratio= 0.02
Log Output Level= 0
Friction Slope Method= 1
Unsteady Friction Slope Method= 2
Unsteady Bridges Friction Slope Method= 1
Parabolic Critical Depth
Global Vel Dist=  1 , 1 , 1
Global Log Level= 0
CheckData=True
Encroach Param= -1, 0, 0, 0
BEGIN DESCRIPTION:
Multiple Run
END DESCRIPTION:

--- WRIGHT CREEK.f01 (steady flow) ---

Flow Title=Multiple
Number of Profiles=7
Profile Names=10-year,25-year,50-year,1pct_min,100-year,1pct_plu,500-year
River Rch & RM= WRIGHT CREEK,Reach-1,19410
     759    1187    1561     990    1975    3941    3128
River Rch & RM= WRIGHT CREEK,Reach-1,17746
    1044    1663    2214    1421    2836    5658    4601
River Rch & RM= WRIGHT CREEK,Reach-1,13316
    1167    1873    2505    1616    3224    6432    5281
River Rch & RM= WRIGHT CREEK,Reach-1,9992
    1479    2407    3251    2117    4223    8426    7046
River Rch & RM= WRIGHT CREEK,Reach-1,6236
    1761    2892    3929    2572    5132   10239    8659
River Rch & RM= WRIGHT CREEK,Reach-1,5927
    1864    3072    4184    2746    5478   10931    9290
Boundary for River Rch & Prof#=WRIGHT CREEK,Reach-1,1
Up Type=0
Dn Type=3
Dn Slope=0.005
Boundary for River Rch & Prof#=WRIGHT CREEK,Reach-1,2
Up Type=0
Dn Type=3
Dn Slope=0.005
Boundary for River Rch & Prof#=WRIGHT CREEK,Reach-1,3
Up Type=0
Dn Type=3
Dn Slope=0.005
Boundary for River Rch & Prof#=WRIGHT CREEK,Reach-1,4
Up Type=0
Dn Type=3
Dn Slope=0.005
Boundary for River Rch & Prof#=WRIGHT CREEK,Reach-1,5
Up Type=0
Dn Type=3
Dn Slope=0.005
Boundary for River Rch & Prof#=WRIGHT CREEK,Reach-1,6
Up Type=0
Dn Type=3
Dn Slope=0.005
Boundary for River Rch & Prof#=WRIGHT CREEK,Reach-1,7
Up Type=0
Dn Type=3
Dn Slope=0.005

--- WRIGHT CREEK.g01 (geometry) ---

Geom Title=Existing Conditions
Program Version=4.10

River Reach=WRIGHT CREEK    ,Reach-1
Reach XY= 30
        2573375.       13495575.      2574375.01     13495667.47
      2575109.92     13495325.18      2575214.63     13495513.91
      2575973.75     13495728.45      2576331.04     13496023.37
      2576873.77     13495971.56      2577404.96     13495625.05
      2577877.45     13495730.46      2578364.29     13496174.28
      2578951.82      13495798.7      2579191.27     13495157.78
       2579684.8     13495064.52      2580318.81     13494232.82
      2581677.45     13493919.53      2582061.43     13493288.47
      2583077.46     13492969.48      2583168.22     13492634.13
       2584123.5     13492471.39      2585277.67     13491919.58
       2585476.5     13491678.46      2585861.84     13491761.27
      2585926.25     13492221.49      2586345.16     13492375.32
      2586881.52     13492282.67      2586930.88     13492723.52
      2587080.66     13492526.96      2587527.48     13492569.53
      2587661.75     13492288.61        2587925.       13492225.

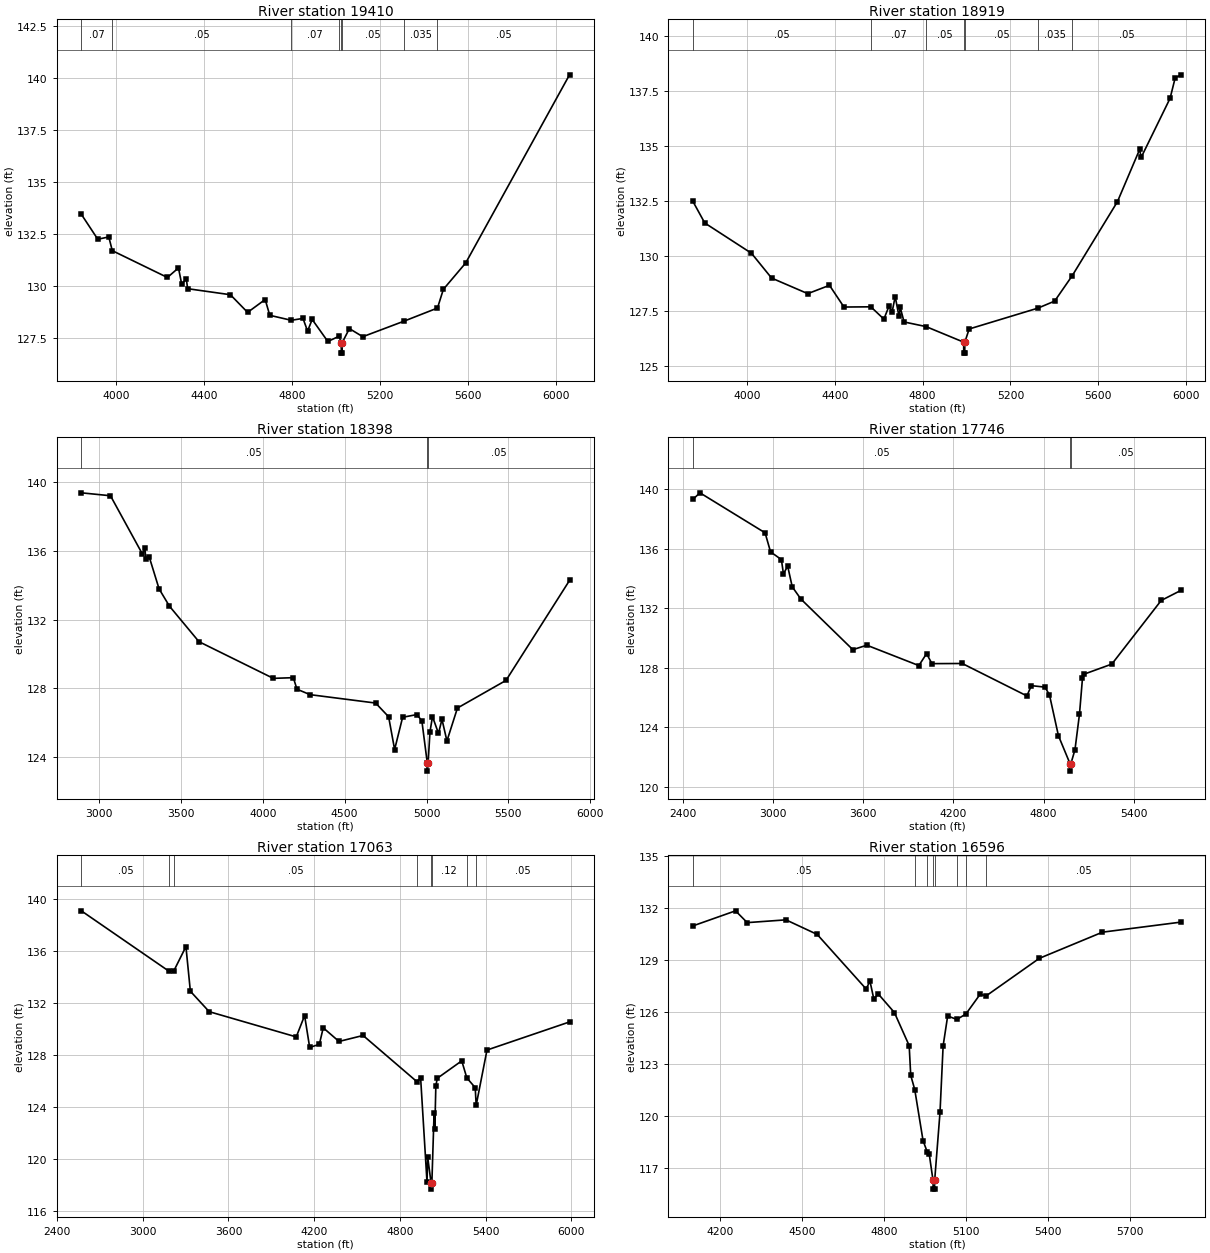
Type RM Length L Ch R = 1 ,19410   ,491,491,491
BEGIN DESCRIPTION:
WRIGHT CREEK 41.0
END DESCRIPTION:
XS GIS Cut Line= 3
       2572950.3      13496565.8        2573625.     13495625.15
      2573429.77     13494581.15
#Sta/Elev= 30
  3842.4  133.45  3917.2  132.25  3967.3  132.36  3983.2   131.7  4233.8  130.41
  4284.1  130.87  4298.7  130.09  4319.7  130.34  4325.9  129.87  4520.2  129.58
  4598.5  128.73  4678.3  129.35  4699.2  128.59  4796.8  128.35  4850.3  128.44
  4871.1  127.83    4892  128.39  4963.3  127.33  5013.9  127.58  5024.4  127.27
  5024.6  126.77  5028.1  126.77  5028.4  127.27  5061.2  127.95  5122.2  127.56
  5307.7   128.3  5461.8  128.94  5488.5  129.84  5590.2  131.11  6062.1  140.16
#Mann= 8 ,-1 , 0
  3842.4     .07       0  3983.2     .05       0  4796.8     .07       0
  5013.9     .05       0  5024.4     .05       0  5028.4     .05       0
  5307.7    .035       0  5461.8     .05       0
Bank Sta=5024.4,5028.4
XS Rating Curve= 0 ,0
Exp/Cntr=0.3,0.1

Type RM Length L Ch R = 1 ,18919   ,521,521,521
BEGIN DESCRIPTION:
Mapping XS 703512d2
END DESCRIPTION:
XS GIS Cut Line= 3
      2573568.38     13496711.62      2574075.33     13495600.49
      2573922.74     13494608.68
#Sta/Elev= 30
  3752.8  132.49  3807.2   131.5  4020.1  130.12  4111.8  128.99  4276.7  128.28
  4375.6  128.66  4441.6  127.67  4564.1  127.68  4623.5  127.12  4646.5   127.7
  4661.4  127.46    4675  128.15  4692.6  127.24  4698.1  127.65  4715.6  126.99
  4815.3  126.78  4987.1  126.07  4987.5  125.57    4992  125.57  4992.5  126.07
  5012.1  126.67  5325.5  127.62  5401.7  127.94    5482   129.1  5687.9  132.47
  5789.1  134.85  5796.2  134.49  5927.8  137.18    5951  138.11  5977.6  138.25
#Mann= 7 ,-1 , 0
  3752.8     .05       0  4564.1     .07       0  4815.3     .05       0
  4987.1     .05       0  4992.5     .05       0  5325.5    .035       0
    5482     .05       0
Bank Sta=4987.1,4992.5
XS Rating Curve= 0 ,0
Exp/Cntr=0.3,0.1

Type RM Length L Ch R = 1 ,18398   ,652,652,652
BEGIN DESCRIPTION:
Mapping XS 693821b5
END DESCRIPTION:
XS GIS Cut Line= 4
       2573722.2     13497329.74      2574707.27     13495857.43
      2574422.55      13495399.1       2574297.6     13494739.66
#Sta/Elev= 30
  2891.3  139.39  3069.3  139.22  3264.5  135.82  3279.5  136.15  3285.5  135.53
  3306.5  135.64  3366.2  133.79  3429.6  132.78  3609.8  130.71  4064.1  128.57
  4186.3  128.61  4208.5  127.94  4288.3  127.62  4689.2  127.13  4768.5  126.33
  4805.1  124.42    4854   126.3  4942.1  126.46  4971.7  126.08  5004.3  123.66
  5004.7  123.16  5009.8  123.66  5021.2  125.46  5036.5  126.34  5073.1  125.36
  5094.4  126.18  5124.7  124.92  5188.9  126.84  5485.5  128.45  5873.5  134.28
#Mann= 3 ,-1 , 0
  2891.3     .05       0  5004.3     .05       0  5009.8     .05       0
Bank Sta=5004.3,5009.8
XS Rating Curve= 0 ,0
Exp/Cntr=0.3,0.1

Type RM Length L Ch R = 1 ,17746   ,683,683,683
BEGIN DESCRIPTION:
Mapping XS ae94dbd7
END DESCRIPTION:
XS GIS Cut Line= 4
      2573982.62     13497538.07      2575047.55     13495926.88
      2575061.44     13495072.71      2574832.28     13494669.94
#Sta/Elev= 30
    2466  139.32  2513.6  139.76    2947  137.07  2983.2  135.79  3055.4  135.27
    3069  134.32  3097.5  134.82  3127.6  133.44  3184.8  132.62  3530.9  129.21
  3624.2  129.51  3970.3  128.14  4021.5  128.94  4057.6  128.27  4259.2  128.28
  4689.2   126.1  4719.2  126.79  4809.3  126.69  4839.3  126.18  4899.3  123.42
  4976.4  121.54  4976.9  121.04  4982.1  121.54  5009.3  122.48  5039.3  124.87
  5059.3  127.29  5069.3  127.56  5254.6  128.24  5583.2  132.52    5715   133.2
#Mann= 3 ,-1 , 0
    2466     .05       0  4976.4     .05       0  4982.1     .05       0
Bank Sta=4976.4,4982.1
XS Rating Curve= 0 ,0
Exp/Cntr=0.3,0.1

Type RM Length L Ch R = 1 ,17063   ,467,467,467
BEGIN DESCRIPTION:
Mapping XS ee16d311
END DESCRIPTION:
XS GIS Cut Line= 4
      2574351.55     13497729.01        2575492.     13495857.43
      2575637.83     13495169.93      2575665.58     13494649.54
#Sta/Elev= 30
  2570.6   139.1  3186.2  134.44  3218.5   134.5  3302.5  136.35  3333.5  132.92
  3465.1  131.35  4074.2  129.41  4132.8  131.05  4168.2   128.6  4235.9  128.84
  4263.1  130.11  4373.5  129.06  4541.9  129.52  4917.3  125.98  4944.5  126.26
  4989.1  118.25  4994.2  120.15  5017.4  118.21  5017.9  117.71  5023.2  118.21
  5038.7  123.57  5043.8  122.32    5051  125.66  5061.2  126.23  5232.2  127.57
  5267.7  126.26  5326.4  125.51  5333.2  124.16  5408.8   128.4  5986.2  130.56
#Mann= 8 ,-1 , 0
  2570.6     .05       0  3186.2     .07       0  3218.5     .05       0
  4917.3     .12       0  5017.4     .05       0  5023.2     .12       0
  5267.7     .07       0  5333.2     .05       0
Bank Sta=5017.4,5023.2
XS Rating Curve= 0 ,0
Exp/Cntr=0.3,0.1

Type RM Length L Ch R = 1 ,16596   ,330,330,330
BEGIN DESCRIPTION:
Mapping XS 94e26d6d
END DESCRIPTION:
XS GIS Cut Line= 4
      2575429.47     13496419.95      2575790.61     13496107.43
        2576117.     13495440.77      2576068.46     13494879.12
#Sta/Elev= 30
  4101.5  130.98  4257.6  131.85  4300.3  131.17  4441.8  131.33  4555.9  130.49
  4734.5  127.35  4748.8  127.79  4762.6  126.78  4779.5  127.05  4837.9  125.99
    4892  124.08  4897.6  122.37  4912.3  121.55  4942.6  118.61  4957.7  117.96
  4965.1  117.85  4979.1  116.31  4979.6  115.81  4984.6  115.81  4985.1  116.31
  5004.6  120.23    5016  124.07  5032.6  125.79    5066  125.59  5099.1   125.9
  5150.7  127.03  5174.3  126.96  5367.3  129.11  5598.2  130.62  5885.1   131.2
#Mann= 8 ,-1 , 0
  4101.5     .05       0  4912.3     .07       0  4957.7     .12       0
  4979.1     .05       0  4985.1     .12       0    5066     .07       0
  5099.1     .12       0  5174.3     .05       0
Bank Sta=4979.1,4985.1
XS Rating Curve= 0 ,0
Exp/Cntr=0.3,0.1

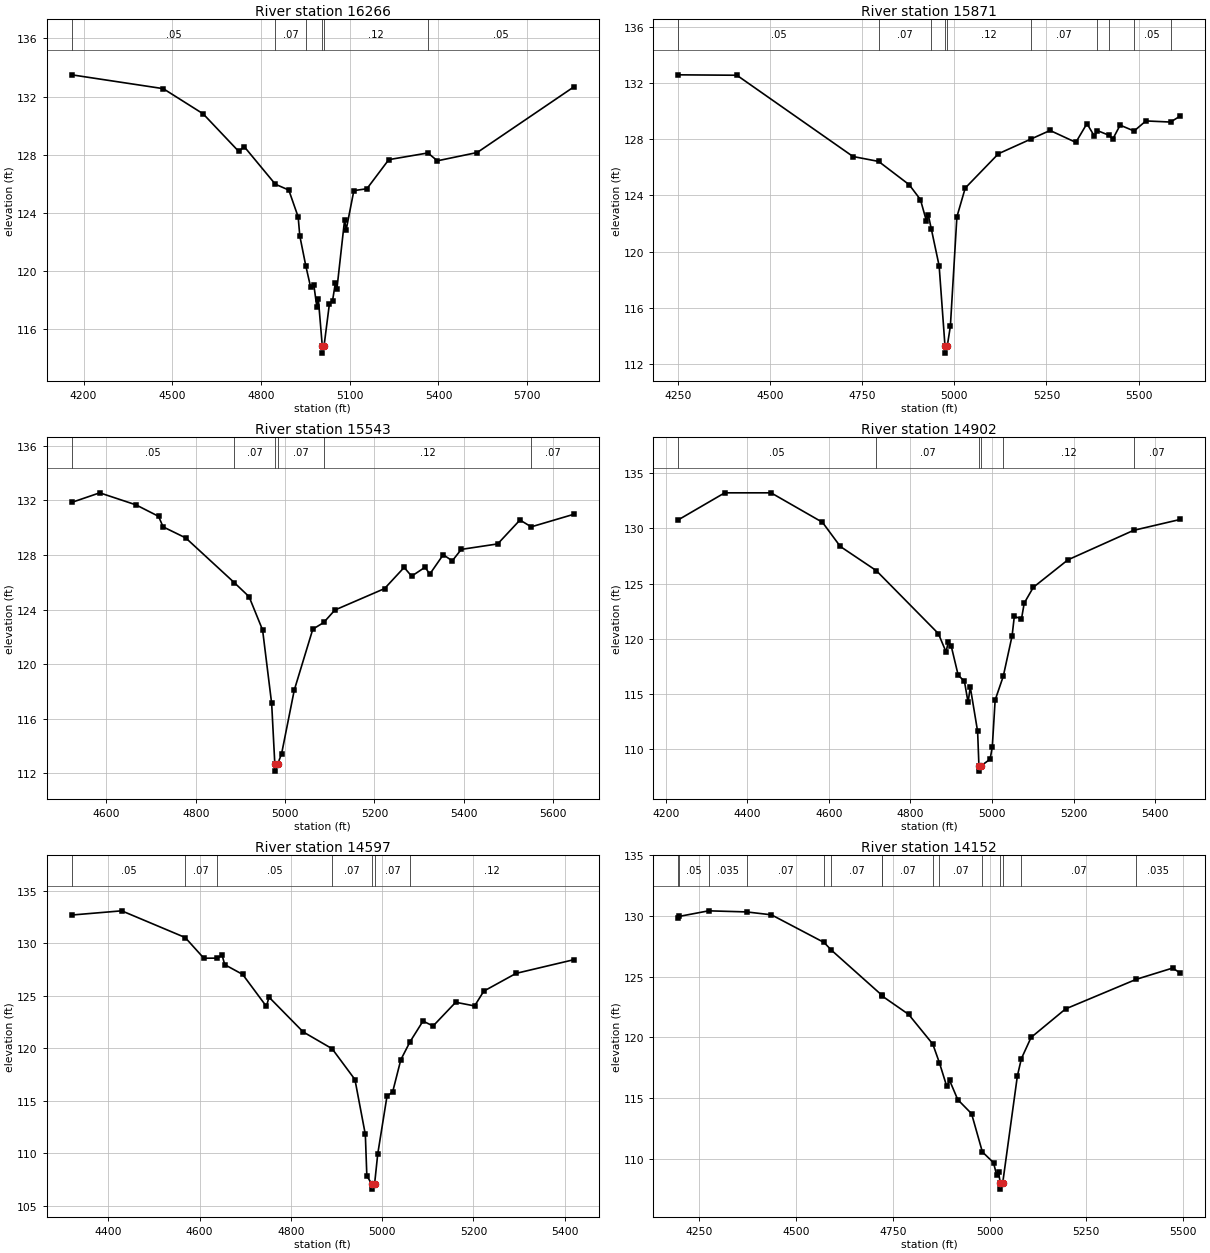
Type RM Length L Ch R = 1 ,16266   ,395,395,395
BEGIN DESCRIPTION:
Mapping XS 280b2d76
END DESCRIPTION:
XS GIS Cut Line= 4
      2575728.09      13496614.4      2576089.22     13496197.71
      2576311.44     13495544.93      2576318.36     13495088.35
#Sta/Elev= 30
  4160.1  133.49  4469.3  132.54  4604.2  130.81  4724.9  128.22  4742.9  128.56
  4848.4  125.97  4893.9  125.57  4925.6  123.72    4931  122.43  4951.6  120.34
  4967.9  118.88  4978.5  119.06  4988.5  117.56  4993.7   118.1  5007.1  114.86
  5007.6  114.36  5013.1  114.86  5031.3  117.76  5041.8  117.95  5051.2  119.17
  5056.5  118.76  5082.5  123.51  5087.8  122.83  5113.9  125.53    5158  125.66
    5232  127.66  5364.3  128.12  5396.2  127.58    5531  128.15  5857.7  132.66
#Mann= 6 ,-1 , 0
  4160.1     .05       0  4848.4     .07       0  4951.6     .12       0
  5007.1     .05       0  5013.1     .12       0  5364.3     .05       0
Bank Sta=5007.1,5013.1
XS Rating Curve= 0 ,0
Exp/Cntr=0.3,0.1

Type RM Length L Ch R = 1 ,15871   ,328,328,328
BEGIN DESCRIPTION:
Mapping XS 9a4ddbed
END DESCRIPTION:
XS GIS Cut Line= 3
      2576390.44     13496711.59      2576524.98     13495965.07
      2576507.62     13495361.77
#Sta/Elev= 30
  4251.1  132.61  4410.2  132.58  4725.2  126.78  4794.7  126.43  4877.6  124.77
  4908.1  123.71  4924.3  122.19  4929.3  122.63  4937.7  121.61  4958.9  118.98
  4974.8  113.25  4975.3  112.75  4980.9  113.25  4989.4  114.67  5007.1  122.48
  5029.7  124.53  5119.8  126.98  5207.4  128.02  5259.8  128.64  5329.8  127.79
  5359.9  129.13  5379.9  128.24  5388.2  128.63  5420.4  128.29  5429.9  128.02
  5449.9  129.02  5487.8   128.6  5519.9  129.32  5586.6  129.24  5613.2  129.67
#Mann= 10 ,-1 , 0
  4251.1     .05       0  4794.7     .07       0  4937.7     .12       0
  4974.8     .05       0  4980.9     .12       0  5207.4     .07       0
  5388.2     .12       0  5420.4     .07       0  5487.8     .05       0
  5586.6     .12       0
Bank Sta=4974.8,4980.9
XS Rating Curve= 0 ,0
Exp/Cntr=0.3,0.1

Type RM Length L Ch R = 1 ,15543   ,641,641,641
BEGIN DESCRIPTION:
Mapping XS a0d34d5c
END DESCRIPTION:
XS GIS Cut Line= 3
      2576893.91     13496446.85      2576820.12     13495986.77
      2576724.63     13495335.69
#Sta/Elev= 30
  4522.4  131.84    4585  132.54  4666.1  131.66  4716.7  130.82  4726.8  130.05
  4777.5  129.24  4886.1  125.97  4919.3  124.94  4949.6   122.5  4969.9  117.12
    4977  112.67  4977.5  112.17  4983.1  112.67  4992.2  113.45  5020.5   118.1
    5062  122.56  5086.5  123.05  5111.4  123.96  5222.6  125.53  5266.5  127.08
  5283.2  126.44  5313.6   127.1  5323.7  126.58    5354  128.01  5374.2  127.56
  5394.4   128.4  5475.9   128.8  5525.8  130.55    5551  130.05  5646.4  130.97
#Mann= 6 ,-1 , 0
  4522.4     .05       0  4886.1     .07       0    4977     .05       0
  4983.1     .07       0  5086.5     .12       0    5551     .07       0
Bank Sta=4977,4983.1
XS Rating Curve= 0 ,0
Exp/Cntr=0.3,0.1

Type RM Length L Ch R = 1 ,14902   ,305,305,305
BEGIN DESCRIPTION:
Mapping XS 5c983dcd
END DESCRIPTION:
XS GIS Cut Line= 4
      2577184.71     13496377.35      2577320.12     13495759.34
      2577233.31     13495540.59      2576979.93     13495280.26
#Sta/Elev= 30
  4230.6  130.78  4344.6  133.23  4458.2  133.23  4584.3  130.56  4628.1  128.37
  4716.1  126.19  4868.5  120.48  4887.4  118.82  4892.8  119.71  4900.2  119.33
  4917.1  116.72  4932.5  116.15  4941.4  114.25  4946.8  115.63  4964.8  111.62
    4968  108.52  4968.5  108.02  4974.1  108.52  4995.4   109.1  5000.8  110.21
  5007.8  114.46  5027.7  116.61  5049.4  120.28  5054.8  122.04  5072.4  121.81
  5079.1  123.24  5101.4  124.67  5186.3  127.16  5347.3  129.83  5461.9  130.82
#Mann= 6 ,-1 , 0
  4230.6     .05       0  4716.1     .07       0    4968     .05       0
  4974.1     .07       0  5027.7     .12       0  5347.3     .07       0
Bank Sta=4968,4974.1
XS Rating Curve= 0 ,0
Exp/Cntr=0.3,0.1

Type RM Length L Ch R = 1 ,14597   ,445,445,445
BEGIN DESCRIPTION:
Mapping XS b9566bbd
END DESCRIPTION:
XS GIS Cut Line= 3
      2577278.45     13496294.08      2577552.76     13495707.26
      2577615.21     13495259.67
#Sta/Elev= 30
  4320.1  132.69  4429.5  133.09  4568.5  130.55  4609.4  128.58    4639  128.59
  4649.5  128.85  4655.1  127.97  4694.4  127.04  4746.5  123.99    4752  124.88
  4826.9  121.57  4890.3  119.97  4940.3  117.04  4963.1  111.81  4966.4  107.86
  4977.2  107.11  4977.7  106.61  4983.4  107.11  4990.3  109.97  5010.5  115.44
    5023  115.87  5040.8  118.92    5061  120.63  5089.4   122.6  5111.5  122.13
    5161  124.39  5202.4  124.04  5222.6  125.45  5293.3  127.14  5419.8  128.44
#Mann= 7 ,-1 , 0
  4320.1     .05       0  4568.5     .07       0    4639     .05       0
  4890.3     .07       0  4977.2     .05       0  4983.4     .07       0
    5061     .12       0
Bank Sta=4977.2,4983.4
XS Rating Curve= 0 ,0
Exp/Cntr=0.3,0.1

Type RM Length L Ch R = 1 ,14152   ,223,223,223
BEGIN DESCRIPTION:
Mapping XS b923ace3
END DESCRIPTION:
XS GIS Cut Line= 3
      2577420.83     13496401.69      2577948.59     13495832.26
      2578070.05     13495325.61
#Sta/Elev= 30
  4195.5  129.87    4198  129.97  4274.1  130.43  4372.1  130.34  4436.4   130.1
  4572.3  127.82  4591.2  127.19  4721.4  123.48  4722.2  123.41  4790.8  121.89
  4853.3  119.44  4870.5  117.89  4889.4  115.95  4896.8  116.44  4917.8  114.86
  4953.5   113.7  4981.4  110.55  5010.2  109.66  5018.1  108.67  5023.2   108.9
  5027.6  107.98  5028.1  107.48  5033.9  107.98  5071.9  116.82  5082.2  118.24
  5107.3  119.99  5196.4  122.34  5378.9  124.78    5473  125.71  5492.9   125.3
#Mann= 15 ,-1 , 0
  4195.5    .035       0    4198     .05       0  4274.1    .035       0
  4372.1     .07       0  4572.3    .035       0  4591.2     .07       0
  4721.4    .035       0  4722.2     .07       0  4853.3     .05       0
  4870.5     .07       0  4981.4     .12       0  5027.6     .05       0
  5033.9     .12       0  5082.2     .07       0  5378.9    .035       0
Bank Sta=5027.6,5033.9
XS Rating Curve= 0 ,0
Exp/Cntr=0.3,0.1

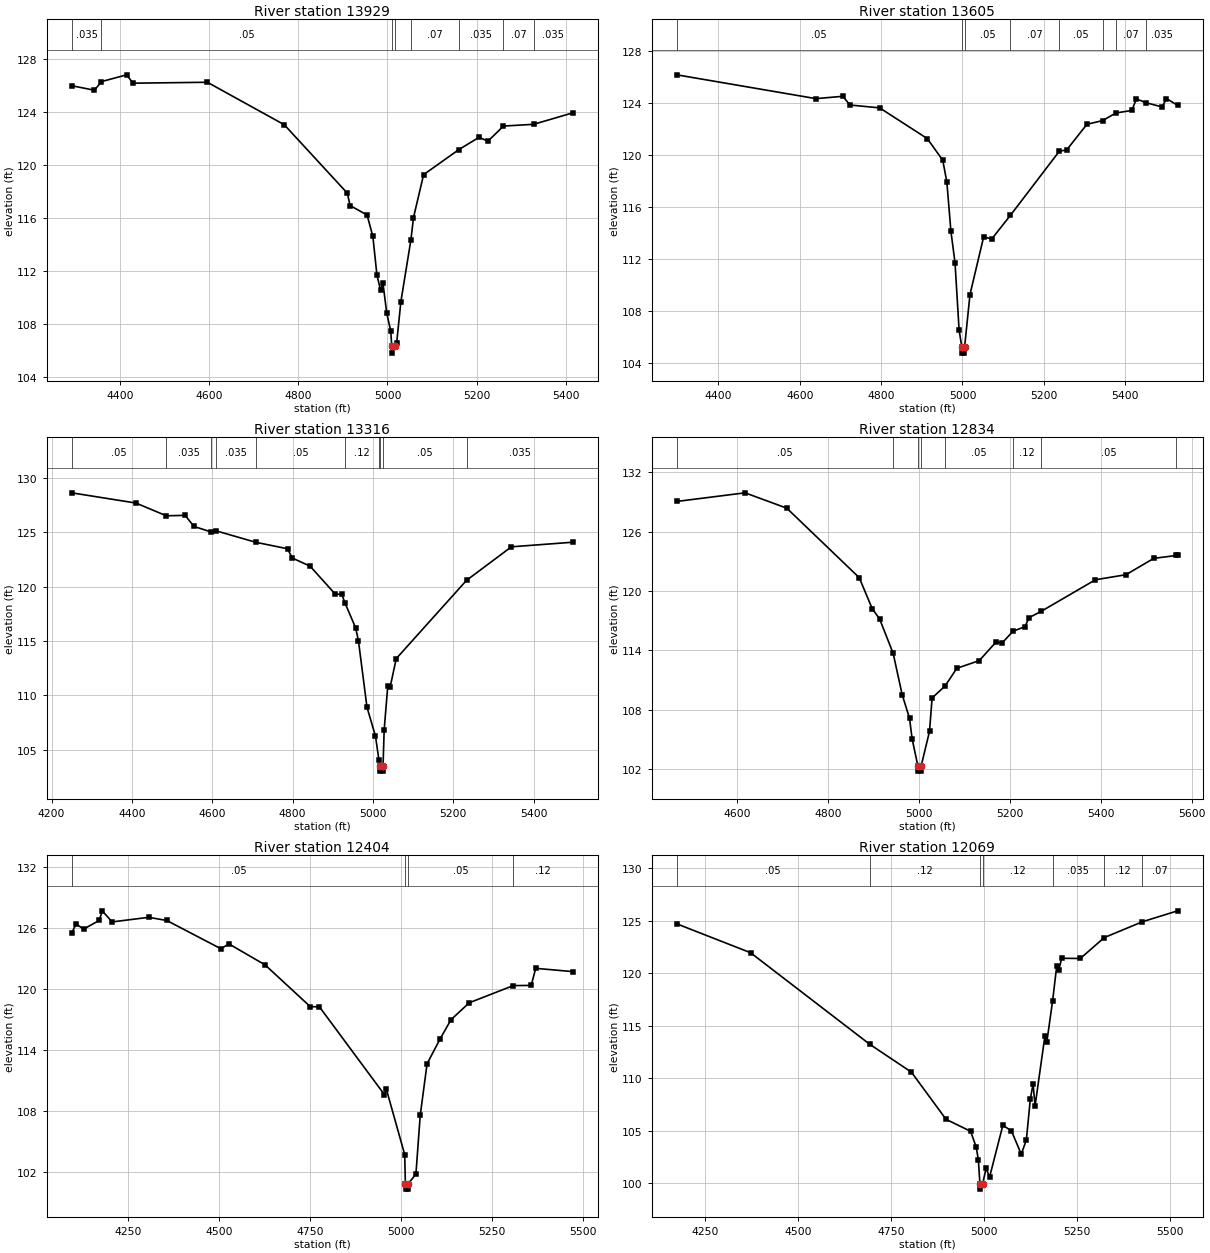
Type RM Length L Ch R = 1 ,13929   ,324,324,324
BEGIN DESCRIPTION:
Mapping XS 2d5dd1fa
END DESCRIPTION:
XS GIS Cut Line= 4
       2577823.6     13496630.84      2577986.79     13496182.96
       2578160.4      13495814.9      2578163.87     13495575.36
#Sta/Elev= 30
  4291.8  125.96  4342.8  125.62  4358.6  126.27  4415.1  126.78  4429.2  126.15
    4596  126.22  4768.5  123.02    4910  117.86  4916.1  116.93  4954.2  116.22
  4967.2   114.6  4976.3   111.7  4984.4  110.56  4989.9  111.07  4998.4  108.81
  5007.2  107.49  5009.6  106.31  5010.1  105.81  5015.9  106.31  5020.5  106.55
    5030  109.68  5052.6  114.36  5058.3  116.02    5081  119.26  5160.3  121.15
  5205.3  122.07  5225.3  121.78  5260.1  122.92  5327.6  123.05    5415  123.91
#Mann= 8 ,-1 , 0
  4291.8    .035       0  4358.6     .05       0  5009.6     .05       0
  5015.9     .05       0  5052.6     .07       0  5160.3    .035       0
  5260.1     .07       0  5327.6    .035       0
Bank Sta=5009.6,5015.9
XS Rating Curve= 0 ,0
Exp/Cntr=0.3,0.1

Type RM Length L Ch R = 1 ,13605   ,289,289,289
BEGIN DESCRIPTION:
Mapping XS f38e8640
END DESCRIPTION:
XS GIS Cut Line= 4
      2578486.79     13496842.67       2578309.7      13496252.4
      2578337.48     13495967.68      2578223.15     13495659.33
#Sta/Elev= 30
  4297.8  126.15  4639.9  124.32    4706   124.5  4723.4  123.83  4796.5  123.61
  4913.5  121.25  4951.6  119.59  4961.7   117.9  4971.7  114.12  4981.8   111.7
  4991.8  106.52  4998.4  105.26  4998.9  104.76  5004.9  104.76  5005.4  105.26
  5018.5  109.26  5052.1  113.69  5072.2  113.54  5117.9  115.35  5238.2  120.28
  5256.3  120.38  5306.1  122.35  5344.5  122.63  5377.5  123.22  5416.3  123.41
  5427.7   124.3  5450.7  124.01    5491  123.68  5501.6  124.33    5529   123.8
#Mann= 8 ,-1 , 0
  4297.8     .05       0  4998.4     .05       0  5005.4     .05       0
  5117.9     .07       0  5238.2     .05       0  5344.5    .035       0
  5377.5     .07       0  5450.7    .035       0
Bank Sta=4998.4,5005.4
XS Rating Curve= 0 ,0
Exp/Cntr=0.3,0.1

Type RM Length L Ch R = 1 ,13316   ,482,482,482
BEGIN DESCRIPTION:
Mapping XS 8c195080
END DESCRIPTION:
XS GIS Cut Line= 4
      2578906.92     13496748.92      2578615.26     13496148.23
      2578490.26     13495950.32      2578285.39     13495672.52
#Sta/Elev= 30
  4250.1  128.61  4410.1  127.67  4485.7   126.5  4532.4  126.54  4554.6  125.52
  4596.9  125.02  4609.4  125.12    4708  124.07  4787.5  123.47  4799.2  122.62
  4843.7  121.87  4905.9  119.32  4922.7  119.27    4931  118.45  4957.2  116.19
  4964.1     115  4985.3  108.91  5006.5  106.25    5015  104.06  5018.3  103.54
  5018.8  103.04  5024.8  103.04  5025.3  103.54  5028.1  106.82    5037  110.85
    5043  110.77  5058.2  113.38  5233.2  120.57  5344.9  123.65  5497.1  124.07
#Mann= 10 ,-1 , 0
  4250.1     .05       0  4485.7    .035       0  4596.9     .05       0
  4609.4    .035       0    4708     .05       0    4931     .12       0
    5015     .05       0  5018.3     .05       0  5025.3     .05       0
  5233.2    .035       0
Bank Sta=5018.3,5025.3
XS Rating Curve= 0 ,0
Exp/Cntr=0.3,0.1

Type RM Length L Ch R = 1 ,12834   ,430,430,430
BEGIN DESCRIPTION:
Mapping XS 4a786005
END DESCRIPTION:
XS GIS Cut Line= 4
      2579313.17     13496176.01      2579090.95      13495877.4
      2578830.54     13495738.51      2578403.45     13495655.18
#Sta/Elev= 30
  4466.7  129.05    4617  129.92  4708.8  128.37  4868.3  121.35  4896.9  118.22
  4913.2  117.18    4943   113.7  4962.8  109.54  4979.1  107.13  4984.7  105.08
  4997.5  102.31    4998  101.81    5004  101.81  5004.5  102.31    5023  105.82
  5028.7   109.2  5057.3  110.41  5083.2   112.2  5132.5  112.97  5170.3  114.89
    5182  114.71  5206.8  115.94  5233.6  116.41  5241.6   117.3  5268.5  117.94
  5388.3  121.14  5455.5  121.65  5516.7   123.3    5566  123.59  5569.2  123.59
#Mann= 8 ,-1 , 0
  4466.7     .05       0    4943     .12       0  4997.5     .05       0
  5004.5     .12       0  5057.3     .05       0  5206.8     .12       0
  5268.5     .05       0    5566    .035       0
Bank Sta=4997.5,5004.5
XS Rating Curve= 0 ,0
Exp/Cntr=0.3,0.1

Type RM Length L Ch R = 1 ,12404   ,335,335,335
BEGIN DESCRIPTION:
Mapping XS 75349fe4
END DESCRIPTION:
XS GIS Cut Line= 4
      2579820.11     13495946.84      2579337.48     13495551.01
      2578955.54     13495412.12      2578611.77     13495394.76
#Sta/Elev= 30
  4096.3  125.47  4108.2  126.38    4129  125.87  4172.1  126.73    4180  127.67
  4207.3  126.58  4307.7  127.03  4357.2  126.72  4505.8  123.94    4528  124.41
  4627.1  122.35  4751.2  118.24  4776.3  118.22  4954.7  109.58    4960  110.12
  5010.4  103.68  5012.3  100.78  5012.8  100.28    5019  100.28  5019.5  100.78
  5041.2  101.76    5053  107.54  5071.8  112.62  5107.7  115.07  5137.4  116.95
  5187.5  118.62  5308.3  120.31  5357.7  120.33    5370  122.01  5471.1  121.69
#Mann= 4 ,-1 , 0
  4096.3     .05       0  5012.3     .05       0  5019.5     .05       0
  5308.3     .12       0
Bank Sta=5012.3,5019.5
XS Rating Curve= 0 ,0
Exp/Cntr=0.3,0.1

Type RM Length L Ch R = 1 ,12069   ,527,527,527
BEGIN DESCRIPTION:
Mapping XS 91851fb8
END DESCRIPTION:
XS GIS Cut Line= 4
       2579809.7     13495700.31      2579386.09     13495294.07
       2579160.4     13495141.29      2578699.34     13494988.76
#Sta/Elev= 30
  4174.9  124.72    4373  121.97  4692.6  113.26  4805.1  110.59    4898   106.1
  4963.9  104.96  4978.8  103.48  4984.8  102.26    4989   99.95  4989.5   99.45
  4996.2   99.95  5005.8  101.45  5014.8  100.58  5050.6  105.53  5073.6     105
  5100.1  102.78  5113.8  104.15  5124.3  108.01  5131.8  109.47  5137.1  107.37
  5163.5  114.02  5168.8  113.49  5184.3   117.4  5195.2  120.68  5200.5  120.28
  5208.6  121.44  5258.7  121.42  5322.9  123.41  5425.5  124.92    5520  125.96
#Mann= 7 ,-1 , 0
  4174.9     .05       0  4692.6     .12       0    4989     .05       0
  4996.2     .12       0  5184.3    .035       0  5322.9     .12       0
  5425.5     .07       0
Bank Sta=4989,4996.2
XS Rating Curve= 0 ,0
Exp/Cntr=0.3,0.1

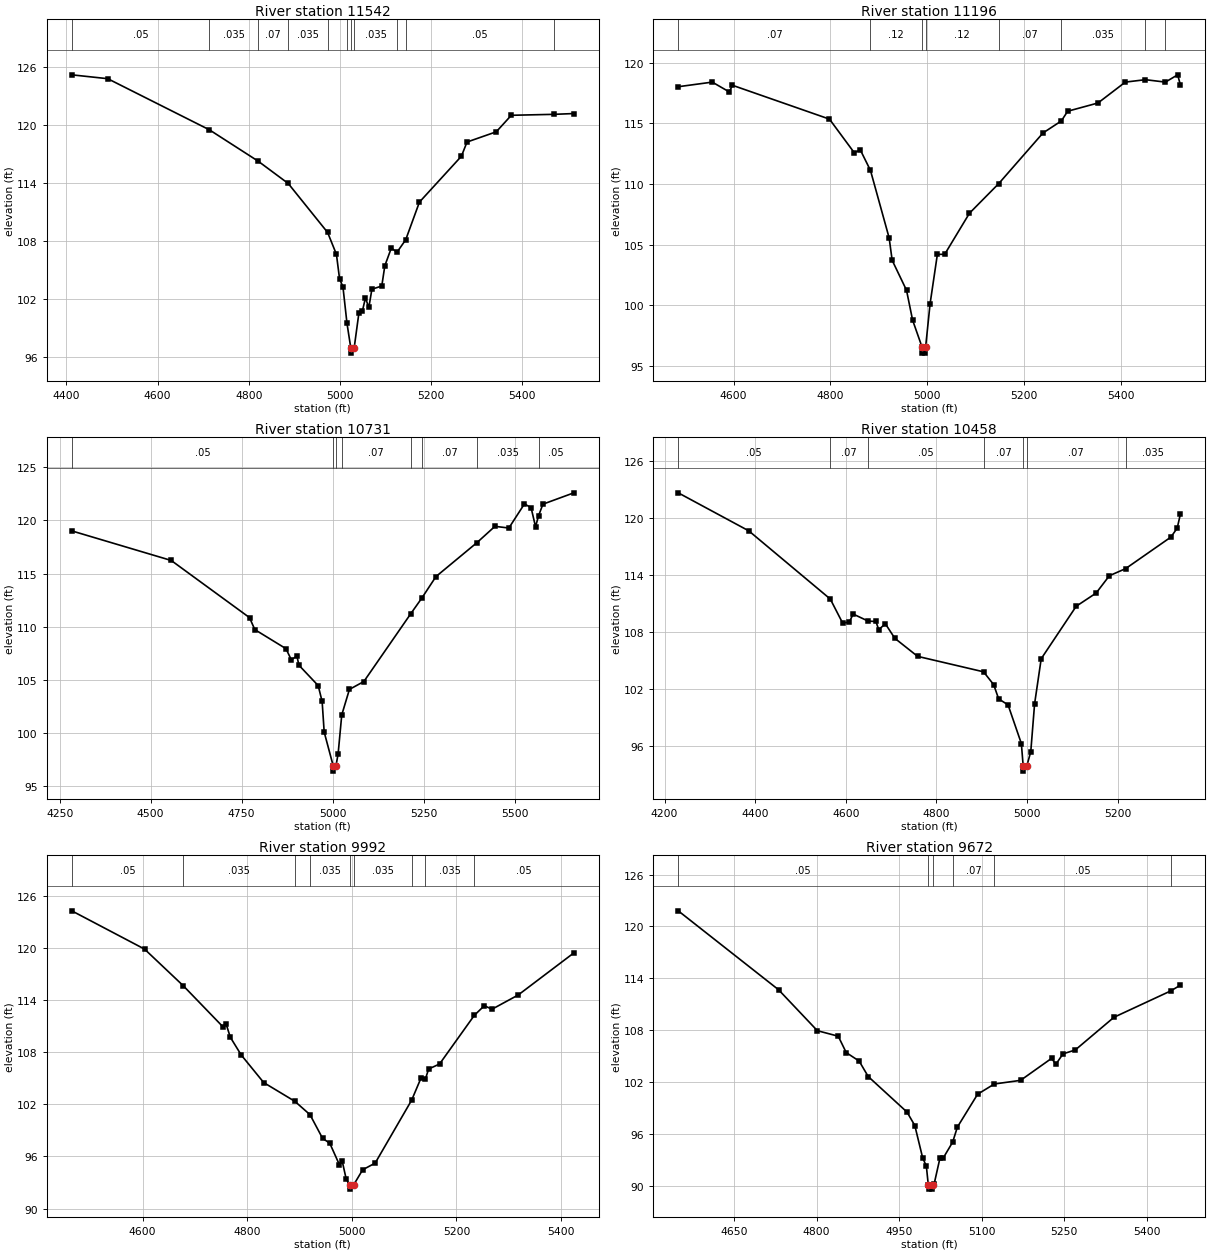
Type RM Length L Ch R = 1 ,11542   ,346,346,346
BEGIN DESCRIPTION:
Mapping XS 540cc569
END DESCRIPTION:
XS GIS Cut Line= 4
      2579983.32     13495557.98      2579823.59      13495189.9
      2579552.76     13494946.84      2579230.59     13494849.85
#Sta/Elev= 30
  4411.6  125.17  4490.5  124.77  4713.4  119.48  4820.5  116.23  4886.5  113.92
  4972.9  108.85  4992.3  106.58  4999.1  104.06  5006.6  103.21  5015.4   99.45
  5023.9   96.85  5024.4   96.35  5031.1   96.85  5041.7  100.55  5049.2   100.7
  5055.9  102.06  5063.4  101.08  5070.1  102.97  5091.8   103.3  5098.5   105.4
  5112.7  107.23  5125.2   106.8  5144.3  108.09  5174.4  111.99  5266.5  116.74
  5278.8  118.21    5343  119.27    5376  120.98  5470.5  121.08  5513.2  121.16
#Mann= 11 ,-1 , 0
  4411.6     .05       0  4713.4    .035       0  4820.5     .07       0
  4886.5    .035       0  4972.9     .07       0  5015.4    .035       0
  5023.9     .05       0  5031.1    .035       0  5125.2     .07       0
  5144.3     .05       0  5470.5    .035       0
Bank Sta=5023.9,5031.1
XS Rating Curve= 0 ,0
Exp/Cntr=0.3,0.1

Type RM Length L Ch R = 1 ,11196   ,465,465,465
BEGIN DESCRIPTION:
Mapping XS e91e2367
END DESCRIPTION:
XS GIS Cut Line= 4
      2580295.79     13495172.51      2580111.79      13494939.9
      2579740.26     13494696.84      2579471.43     13494569.32
#Sta/Elev= 30
  4485.5  118.01  4555.9  118.39  4591.1  117.58  4597.5  118.13  4798.2  115.34
  4849.5  112.57  4861.9  112.81    4883  111.11  4921.6  105.55  4927.8  103.71
  4957.5  101.24    4970   98.79  4989.6   96.56  4990.1   96.06  4996.5   96.06
    4997   96.56  5006.2  100.12  5021.3   104.2  5036.4   104.2  5087.7  107.59
  5148.2  110.03  5239.7   114.2  5277.6  115.19  5290.7  115.99  5353.4  116.67
  5409.9  118.39  5451.5  118.59  5492.8  118.39  5518.1  118.99  5523.6  118.18
#Mann= 8 ,-1 , 0
  4485.5     .07       0    4883     .12       0  4989.6     .05       0
    4997     .12       0  5148.2     .07       0  5277.6    .035       0
  5451.5     .05       0  5492.8    .035       0
Bank Sta=4989.6,4997
XS Rating Curve= 0 ,0
Exp/Cntr=0.3,0.1

Type RM Length L Ch R = 1 ,10731   ,273,273,273
BEGIN DESCRIPTION:
Mapping XS 0d0f998d
END DESCRIPTION:
XS GIS Cut Line= 4
      2580618.74     13494974.63      2580257.62     13494485.04
      2580080.54     13494405.18      2579511.13     13494311.43
#Sta/Elev= 30
  4283.3  119.02  4556.6  116.23  4771.7  110.84  4786.3  109.71  4871.9  107.91
  4886.6  106.86    4902  107.22  4907.5  106.35  4960.4  104.43  4971.3  102.93
  4976.9  100.05  5001.7   96.86  5002.2   96.36  5009.3   96.86  5015.2   97.98
  5025.2  101.66  5046.3  104.07  5085.9  104.81  5214.9  111.21  5245.2  112.68
  5284.1  114.71    5397  117.92  5446.2  119.45  5484.4  119.29  5527.3  121.57
  5545.6   121.2  5557.7  119.41  5566.1  120.45    5578  121.54    5663  122.61
#Mann= 8 ,-1 , 0
  4283.3     .05       0  5001.7     .05       0  5009.3     .05       0
  5025.2     .07       0  5214.9     .05       0  5245.2     .07       0
    5397    .035       0  5566.1     .05       0
Bank Sta=5001.7,5009.3
XS Rating Curve= 0 ,0
Exp/Cntr=0.3,0.1

Type RM Length L Ch R = 1 ,10458   ,466,466,466
BEGIN DESCRIPTION:
Mapping XS b1d6ad5b
END DESCRIPTION:
XS GIS Cut Line= 3
      2580927.72     13494700.29      2580365.26     13494290.59
      2580120.36     13493959.47
#Sta/Elev= 30
  4230.3  122.66    4386  118.65  4565.8  111.46    4593  108.93  4607.7  109.03
  4616.2  109.88  4649.6  109.13  4666.4   109.1  4672.6  108.24  4687.3  108.85
  4708.2  107.32  4758.4  105.42  4903.9  103.79  4926.2  102.44  4937.2  100.94
    4958   100.3  4987.3   96.23  4991.4   93.82  4991.9   93.32  4999.1   93.82
  5008.1   95.38  5016.5  100.41  5031.1  105.17  5108.3   110.7  5152.2  112.09
  5181.5  113.92  5217.4  114.67  5317.1  117.99  5331.1  118.93    5338  120.38
#Mann= 7 ,-1 , 0
  4230.3     .05       0  4565.8     .07       0  4649.6     .05       0
  4903.9     .07       0  4991.4     .05       0  4999.1     .07       0
  5217.4    .035       0
Bank Sta=4991.4,4999.1
XS Rating Curve= 0 ,0
Exp/Cntr=0.3,0.1

Type RM Length L Ch R = 1 ,9992    ,320,320,320
BEGIN DESCRIPTION:
Mapping XS 77393cc7
END DESCRIPTION:
XS GIS Cut Line= 4
      2581049.29      13494564.9       2580785.4     13494224.62
      2580740.26     13494082.26      2580434.73     13493856.58
#Sta/Elev= 30
  4464.7  124.31  4603.8   119.9  4677.8  115.68  4753.3  110.97  4759.6  111.29
  4767.8  109.74  4788.6   107.7  4831.6  104.52  4891.1  102.36  4920.1  100.82
  4944.2   98.09  4957.9   97.53  4976.5   95.03  4981.7   95.47  4989.3    93.4
    4996   92.74  4996.5   92.24  5003.7   92.74  5020.8   94.47  5044.7   95.24
  5114.5   102.5  5132.3  105.04  5140.9  104.96  5146.9  106.08  5167.8  106.66
  5234.3  112.27  5253.4  113.38    5268  112.97  5318.1  114.61  5424.5  119.46
#Mann= 9 ,-1 , 0
  4464.7     .05       0  4677.8    .035       0  4891.1     .05       0
  4920.1    .035       0    4996    .035       0  5003.7    .035       0
  5114.5     .07       0  5140.9    .035       0  5234.3     .05       0
Bank Sta=4996,5003.7
XS Rating Curve= 0 ,0
Exp/Cntr=0.3,0.1

Type RM Length L Ch R = 1 ,9672    ,274,274,274
BEGIN DESCRIPTION:
Mapping XS 78d6c832
END DESCRIPTION:
XS GIS Cut Line= 4
      2581240.25     13494412.11       2581097.9     13494082.26
      2581018.04     13493995.46      2580678.92     13493722.08
#Sta/Elev= 30
  4548.4  121.81  4730.8  112.69  4801.3  107.96  4839.3  107.32  4853.8  105.43
  4877.3  104.45  4893.8  102.66  4964.4   98.55  4978.5      97  4992.7   93.28
  4999.5    92.3    5003   90.15  5003.5   89.65  5010.3   89.65  5010.8   90.15
  5013.7   90.26  5024.2   93.23    5030   93.23  5047.3   95.08  5055.9   96.82
  5092.7  100.62  5123.1   101.8  5170.8  102.22  5227.1  104.76    5235  104.08
  5247.9  105.28  5270.2  105.73  5340.6  109.51  5443.6  112.55  5461.2  113.21
#Mann= 6 ,-1 , 0
  4548.4     .05       0    5003     .05       0  5010.8     .05       0
  5047.3     .07       0  5123.1     .05       0  5443.6    .035       0
Bank Sta=5003,5010.8
XS Rating Curve= 0 ,0
Exp/Cntr=0.3,0.1

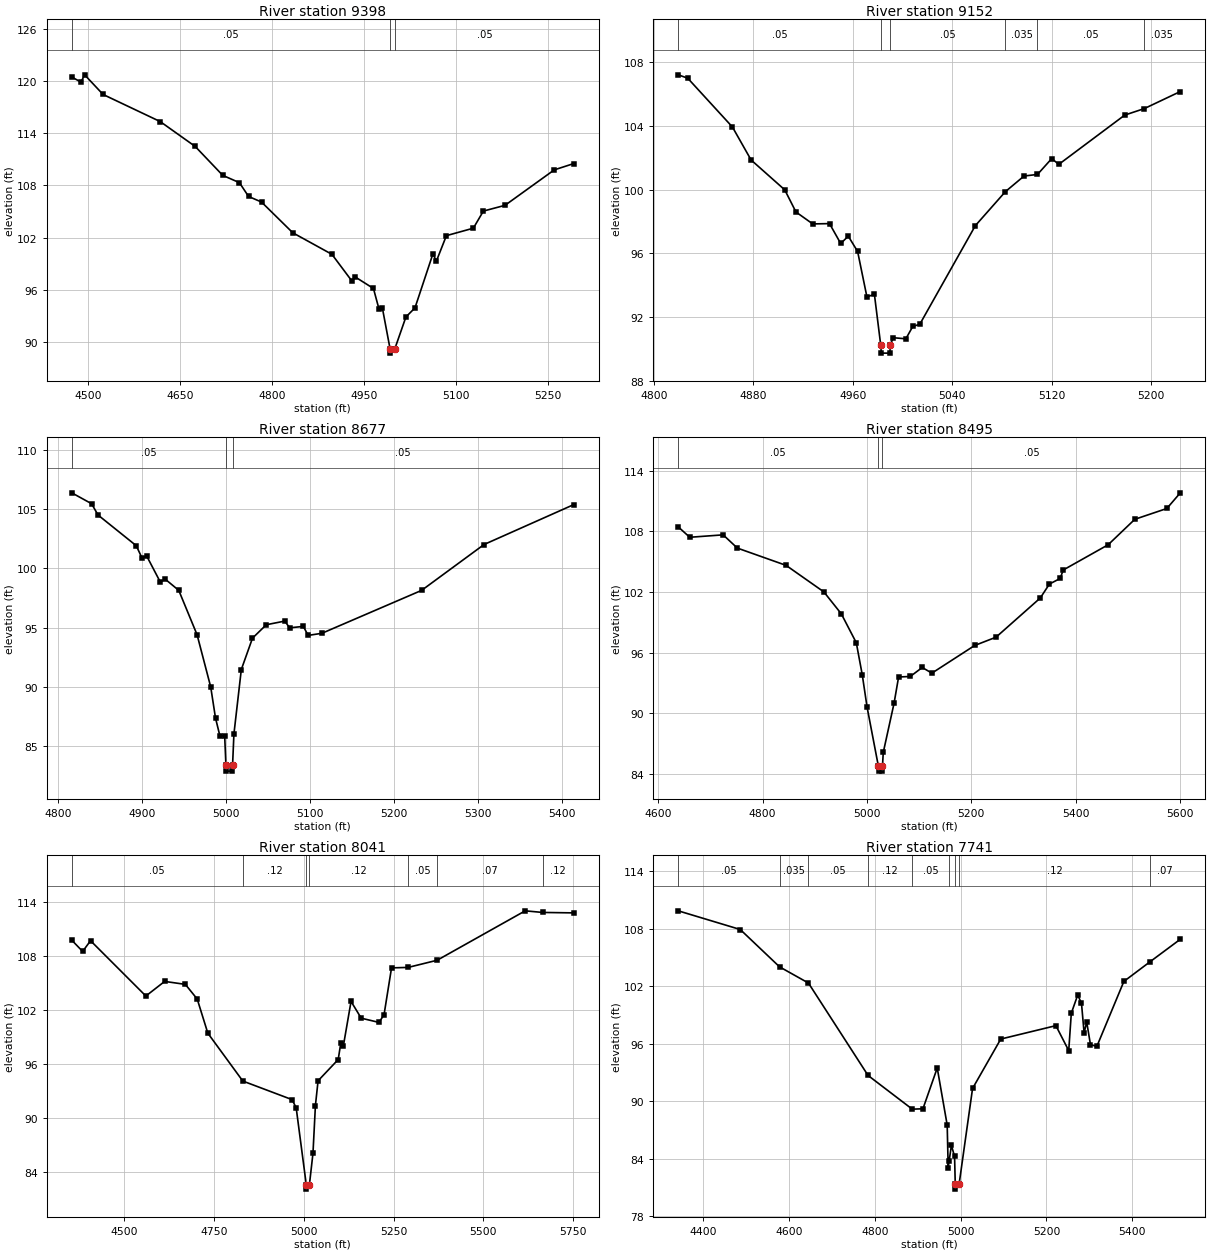
Type RM Length L Ch R = 1 ,9398    ,246,246,246
BEGIN DESCRIPTION:
Mapping XS c1b6b8d0
END DESCRIPTION:
XS GIS Cut Line= 3
      2581559.69     13494370.44      2581340.95     13494040.59
      2581143.04      13493665.6
#Sta/Elev= 30
  4473.1  120.48  4488.1  119.89  4494.1  120.73  4524.2  118.47  4617.5  115.35
  4674.6  112.49  4719.6  109.16  4746.8  108.32  4761.8  106.73  4782.9  106.09
    4834  102.55  4897.9  100.07  4930.6   96.99  4936.3   97.45  4965.7   96.14
  4974.7   93.78  4980.3   93.88  4992.8    89.2  4993.3    88.7  5000.6    89.2
  5018.7   92.86  5033.5   93.91  5062.8  100.13  5068.4   99.28  5084.8  102.22
  5128.8  103.08  5145.2  105.05  5180.5  105.71  5260.9  109.79  5292.9  110.52
#Mann= 3 ,-1 , 0
  4473.1     .05       0  4992.8     .05       0  5000.6     .05       0
Bank Sta=4992.8,5000.6
XS Rating Curve= 0 ,0
Exp/Cntr=0.3,0.1

Type RM Length L Ch R = 1 ,9152    ,475,475,475
BEGIN DESCRIPTION:
WRIGHT CREEK 19.0
END DESCRIPTION:
XS GIS Cut Line= 3
      2581625.03     13494075.04        2581525.       13493925.
      2581425.01     13493725.03
#Sta/Elev= 30
  4819.7  107.22  4827.3  107.01  4863.3  103.94  4878.3  101.87  4905.4   99.99
  4914.4    98.6  4927.9   97.85  4941.4   97.87  4950.4   96.62  4956.5   97.08
    4964   96.12  4971.5   93.26  4977.5   93.43  4982.6   90.23  4983.1   89.73
  4989.9   89.73  4990.4   90.23  4992.5    90.7  5002.8   90.63  5008.4   91.41
    5014   91.54  5058.7   97.74  5082.9   99.88  5097.9  100.86  5108.7  100.96
  5120.2  101.96  5125.8  101.59  5178.9  104.69  5194.7   105.1  5223.6  106.17
#Mann= 6 ,-1 , 0
  4819.7     .05       0  4982.6     .05       0  4990.4     .05       0
  5082.9    .035       0  5108.7     .05       0  5194.7    .035       0
Bank Sta=4982.6,4990.4
XS Rating Curve= 0 ,0
Exp/Cntr=0.3,0.1

Type RM Length L Ch R = 1 ,8677    ,182,182,182
BEGIN DESCRIPTION:
WRIGHT CREEK 18.0
END DESCRIPTION:
XS GIS Cut Line= 3
      2582010.35     13493882.45        2581925.       13493725.
      2581554.59     13493530.85
#Sta/Elev= 30
  4816.6  106.38  4840.2  105.46  4847.8  104.51  4893.3  101.92  4900.1  100.89
  4905.8  101.04    4922   98.84  4927.7    99.1  4943.9   98.15  4965.7    94.4
  4981.9      90  4987.6   87.38  4992.8   85.88  4998.5   85.88    5000    83.4
  5000.5    82.9  5007.4    82.9  5007.9    83.4  5009.5   86.03  5018.3   91.47
  5031.6   94.12    5048   95.25  5070.1   95.56  5075.7   94.99  5092.1   95.11
  5097.8   94.35  5114.2   94.53  5232.8   98.15  5307.1  102.02  5413.9  105.39
#Mann= 3 ,-1 , 0
  4816.6     .05       0    5000     .05       0  5007.9     .05       0
Bank Sta=5000,5007.9
XS Rating Curve= 0 ,0
Exp/Cntr=0.3,0.1

Type RM Length L Ch R = 1 ,8495    ,454,454,454
BEGIN DESCRIPTION:
Mapping XS 48addeba
END DESCRIPTION:
XS GIS Cut Line= 4
      2582257.62     13493752.39      2582136.09     13493599.62
      2581837.48     13493519.76      2581389.82     13493422.59
#Sta/Elev= 30
  4638.3  108.45  4660.4  107.42  4724.4  107.66  4751.6  106.35    4845  104.64
  4917.5  102.01  4950.9   99.84  4979.6   96.98    4991   93.82  5000.3    90.6
  5021.9   84.77  5022.4   84.27  5029.3   84.27  5029.8   84.77  5031.3   86.12
    5052   90.99  5060.7   93.59  5083.1   93.64    5106   94.53  5124.5   93.97
  5206.6   96.71  5247.5   97.53  5332.3  101.41  5349.8  102.79  5370.3  103.34
  5376.3  104.18  5462.4  106.68  5513.5   109.2  5574.9  110.27  5600.7  111.82
#Mann= 3 ,-1 , 0
  4638.3     .05       0  5021.9     .05       0  5029.8     .05       0
Bank Sta=5021.9,5029.8
XS Rating Curve= 0 ,0
Exp/Cntr=0.3,0.1

Type RM Length L Ch R = 1 ,8041    ,300,300,300
BEGIN DESCRIPTION:
Mapping XS 1d173642
END DESCRIPTION:
XS GIS Cut Line= 4
      2582469.41     13493812.53      2582191.65     13493209.27
      2581987.66     13493022.64      2581570.96     13492831.65
#Sta/Elev= 30
  4353.3   109.8  4383.6  108.54  4405.6  109.74  4559.8  103.57  4612.1   105.2
  4669.8  104.87  4702.9  103.23  4732.4   99.43  4829.9   94.09  4967.1   92.02
  4978.6   91.11  5006.7   82.54  5007.2   82.04  5015.5   82.54  5025.4   86.04
  5032.2   91.36  5039.6   94.12  5095.7   96.49  5103.1   98.37  5109.9   97.97
  5131.5  102.97  5159.8   101.1  5209.2  100.63  5223.4  101.48  5244.3  106.71
  5290.4  106.76  5371.4  107.56  5616.8  113.07  5665.1  112.89  5752.3  112.84
#Mann= 7 ,-1 , 0
  4353.3     .05       0  4829.9     .12       0  5006.7     .05       0
  5015.5     .12       0  5290.4     .05       0  5371.4     .07       0
  5665.1     .12       0
Bank Sta=5006.7,5015.5
XS Rating Curve= 0 ,0
Exp/Cntr=0.3,0.1

Type RM Length L Ch R = 1 ,7741    ,353,353,353
BEGIN DESCRIPTION:
Mapping XS d47e7bd4
END DESCRIPTION:
XS GIS Cut Line= 3
      2582649.69     13493714.63      2582483.03     13493110.47
      2582035.12     13492803.19
#Sta/Elev= 30
  4342.1  109.87  4486.6  107.92  4578.2  104.02  4645.5  102.33  4784.4   92.68
  4887.4   89.16  4912.3    89.2  4945.6   93.46  4968.8    87.5  4971.1   83.06
  4973.2   83.71  4978.6   85.38    4986   84.22  4987.6   81.31  4988.1   80.81
  4996.5   81.31  5027.9   91.32  5093.6   96.48  5222.1   97.88    5252   95.27
    5258   99.18  5272.9  101.07  5281.7  100.23  5287.8   97.13  5293.9   98.25
  5302.7   95.89  5317.6   95.72  5380.5   102.5  5441.1  104.54    5512   106.9
#Mann= 9 ,-1 , 0
  4342.1     .05       0  4578.2    .035       0  4645.5     .05       0
  4784.4     .12       0  4887.4     .05       0  4973.2     .12       0
  4987.6     .05       0  4996.5     .12       0  5441.1     .07       0
Bank Sta=4987.6,4996.5
XS Rating Curve= 0 ,0
Exp/Cntr=0.3,0.1