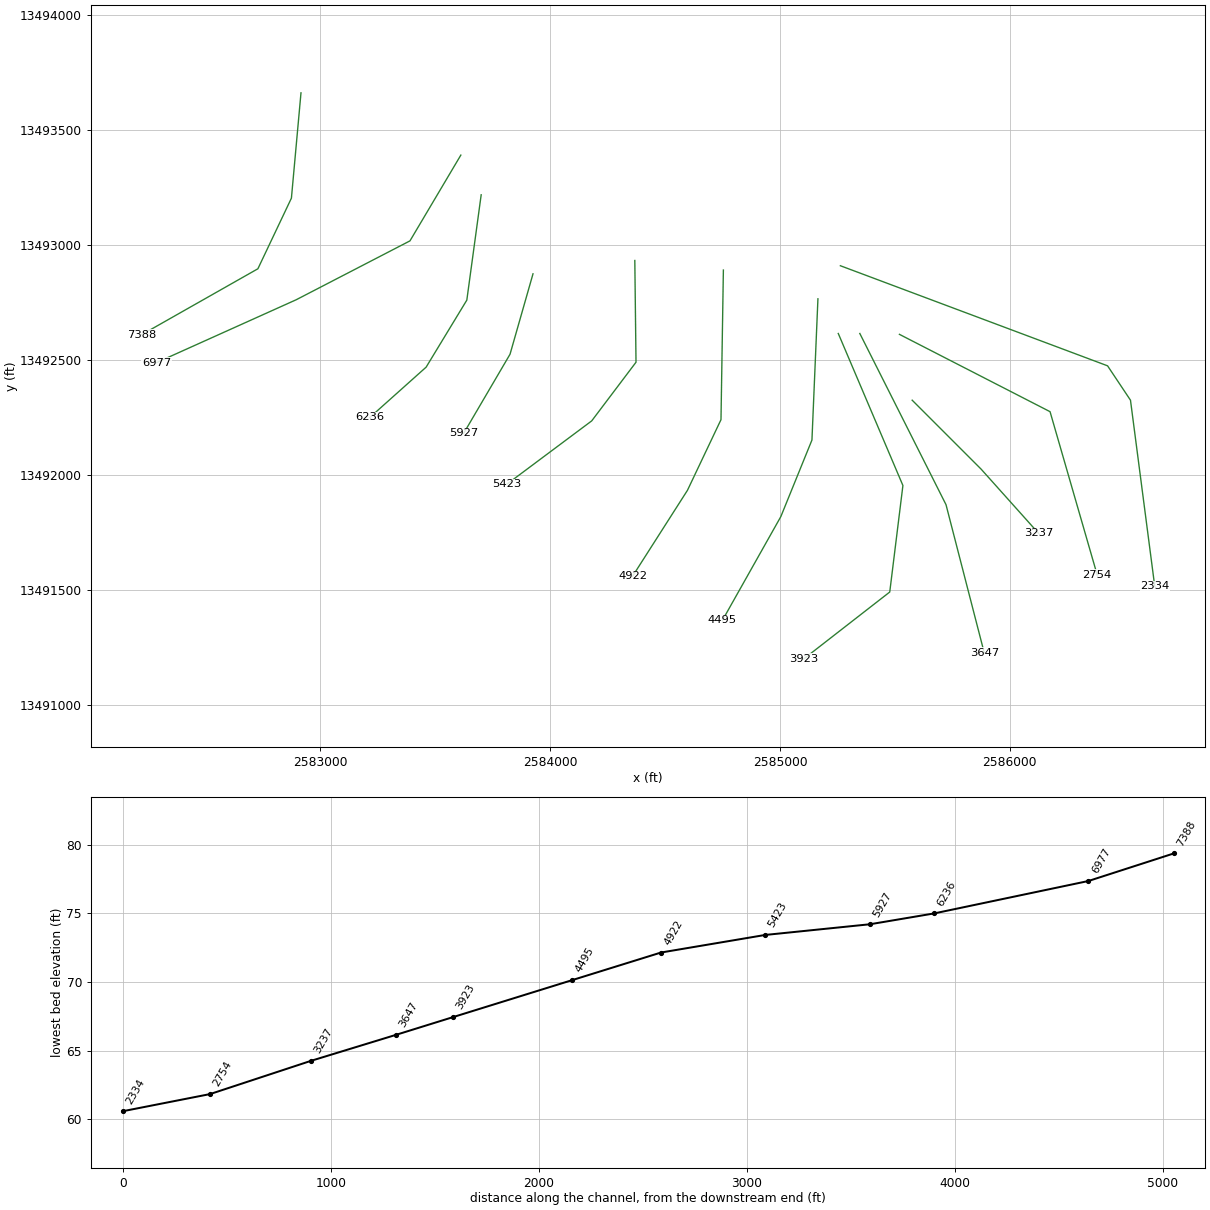
HEC-RAS study WRIGHT CREEK.prj: WRIGHT CREEK Base Level Engineering

--- WRIGHT CREEK.g01 (geometry) --- (continued)

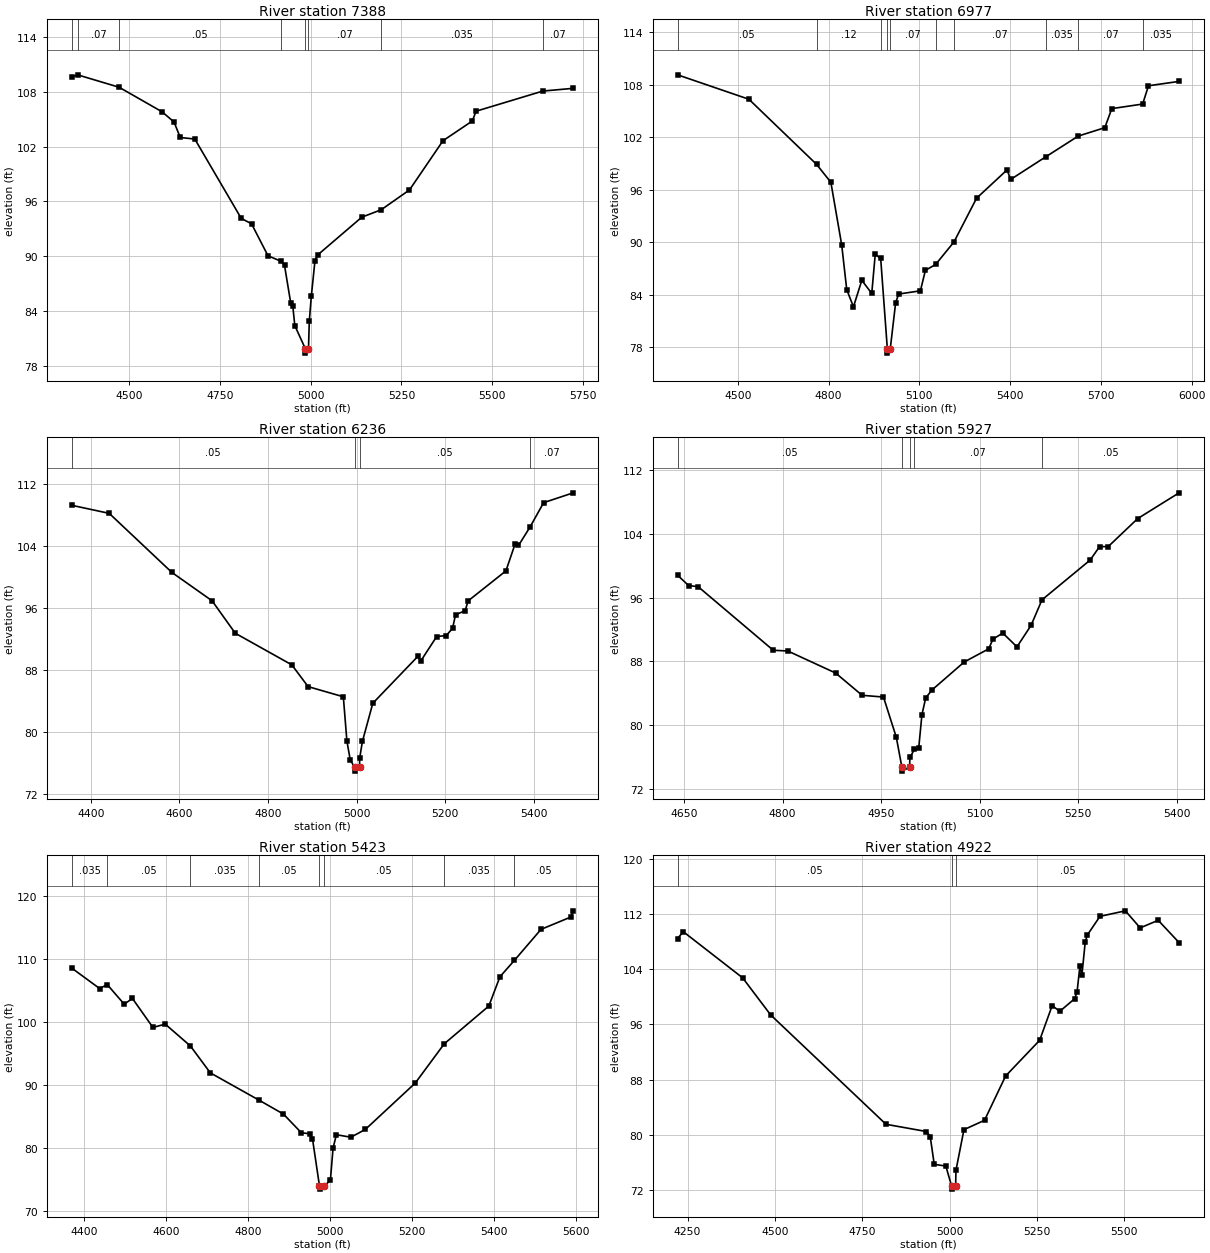
Type RM Length L Ch R = 1 ,7388    ,411,411,411
BEGIN DESCRIPTION:
Mapping XS b6e7b3b9
END DESCRIPTION:
XS GIS Cut Line= 4
      2582915.32     13493662.56      2582873.65     13493204.22
      2582727.82     13492896.93      2582222.64     13492610.49
#Sta/Elev= 30
  4342.2  109.63  4358.2  109.87  4472.6  108.51  4590.8  105.82  4623.9   104.7
    4641     103  4681.1  102.83    4809   94.13  4837.3   93.54  4882.7   90.03
  4918.7   89.43  4928.2   88.97  4945.4   84.82  4950.9   84.55  4956.5   82.38
  4985.3   79.86  4985.8   79.36  4994.2   79.86  4996.4   82.86  5001.9   85.57
  5011.9   89.45  5019.1   90.11  5140.9   94.26  5194.5   95.08  5272.3   97.25
  5364.7  102.65  5445.4  104.81  5455.6  105.88  5639.6  108.09  5723.3  108.39
#Mann= 8 ,-1 , 0
  4342.2     .05       0  4358.2     .07       0  4472.6     .05       0
  4918.7     .07       0  4985.3     .05       0  4994.2     .07       0
  5194.5    .035       0  5639.6     .07       0
Bank Sta=4985.3,4994.2
XS Rating Curve= 0 ,0
Exp/Cntr=0.3,0.1

Type RM Length L Ch R = 1 ,6977    ,741,741,741
BEGIN DESCRIPTION:
Mapping XS ac48af38
END DESCRIPTION:
XS GIS Cut Line= 4
       2583610.9     13493391.52      2583389.56      13493018.3
      2582894.77     13492762.22      2582287.11     13492488.77
#Sta/Elev= 30
  4301.2  109.15  4536.9  106.36  4760.5   98.92  4807.8   96.87  4843.7   89.69
  4860.2   84.61  4882.4   82.64  4910.1   85.67  4942.9   84.17  4954.4   88.63
  4972.4   88.18  4994.4   77.85  4994.9   77.35  5004.1   77.85  5021.8   83.09
  5031.7    84.1  5103.7   84.47  5120.2   86.81    5154   87.48  5214.7   90.06
  5289.3   95.05  5390.2   98.29  5401.7   97.19  5518.8    99.8  5625.2  102.15
  5713.1  103.11  5736.2  105.29  5838.2  105.81  5857.4   107.9  5958.6   108.4
#Mann= 10 ,-1 , 0
  4301.2     .05       0  4760.5     .12       0  4972.4     .07       0
  4994.4     .05       0  5004.1     .07       0    5154     .12       0
  5214.7     .07       0  5518.8    .035       0  5625.2     .07       0
  5838.2    .035       0
Bank Sta=4994.4,5004.1
XS Rating Curve= 0 ,0
Exp/Cntr=0.3,0.1

Type RM Length L Ch R = 1 ,6236    ,309,309,309
BEGIN DESCRIPTION:
Mapping XS ac28642b
END DESCRIPTION:
XS GIS Cut Line= 4
      2583699.47     13493218.86      2583636.96     13492760.48
      2583459.88     13492468.82       2583215.1     13492250.08
#Sta/Elev= 30
  4356.9  109.31  4441.5  108.27  4582.8  100.65  4673.7   96.98  4726.1   92.79
  4853.7   88.71  4890.5    85.9    4970   84.59    4978   78.89  4985.5   76.47
  4995.2   75.49  4995.7   74.99  5006.7   75.49  5006.8   76.66  5013.1   78.83
  5036.5   83.75  5138.6   89.83  5144.4   89.17  5180.7   92.37  5202.4   92.49
  5216.6   93.44  5223.3   95.18    5245    95.7  5251.7   96.97    5337  100.84
  5357.9  104.35  5365.4  104.12  5391.4   106.5  5422.1  109.65    5489  110.92
#Mann= 4 ,-1 , 0
  4356.9     .05       0  4995.2     .05       0  5006.7     .05       0
  5391.4     .07       0
Bank Sta=4995.2,5006.7
XS Rating Curve= 0 ,0
Exp/Cntr=0.3,0.1

Type RM Length L Ch R = 1 ,5927    ,504,504,504
BEGIN DESCRIPTION:
WRIGHT CREEK 12.0
END DESCRIPTION:
XS GIS Cut Line= 3
      2583924.99     13492874.96        2583825.       13492525.
      2583623.14     13492180.67
#Sta/Elev= 30
  4640.2   98.82  4657.1   97.52  4671.4   97.39  4785.8   89.39  4807.9    89.3
  4880.7   86.53    4921   83.73  4953.5   83.51    4973   78.46  4981.5    74.7
    4982    74.2  4993.1    74.7  4993.8   75.94  5000.5   76.92  5007.1   77.08
    5012    81.3  5017.8   83.41  5027.3    84.4  5076.4   87.92  5113.6   89.57
  5120.1    90.8  5135.1   91.55  5156.6   89.82    5178   92.51  5194.7   95.73
    5268  100.73  5282.4  102.43  5295.3  102.41  5340.3  105.94  5403.3  109.18
#Mann= 5 ,-1 , 0
  4640.2     .05       0  4981.5     .05       0  4993.1     .05       0
  5000.5     .07       0  5194.7     .05       0
Bank Sta=4981.5,4993.1
XS Rating Curve= 0 ,0
Exp/Cntr=0.3,0.1

Type RM Length L Ch R = 1 ,5423    ,501,501,501
BEGIN DESCRIPTION:
Mapping XS 26fd6376
END DESCRIPTION:
XS GIS Cut Line= 4
      2584368.01     13492932.95      2584373.22     13492490.25
      2584180.51     13492235.04      2583811.43     13491959.53
#Sta/Elev= 30
  4369.3  108.56  4437.3  105.31  4455.9  105.93  4497.3  102.82  4517.3  103.73
  4567.3   99.12  4597.3   99.65  4658.8   96.17  4707.3    91.9  4826.2   87.56
  4885.6   85.35  4929.3   82.38  4950.2   82.22  4956.4   81.45  4973.5   73.92
    4974   73.42  4985.1   73.92  5000.1   74.83  5006.6   79.92  5014.7   82.07
  5050.1   81.67  5085.5   82.92  5207.2   90.29  5277.9   96.53  5386.5  102.52
  5413.6  107.18  5449.1   109.8  5513.7  114.71  5586.7  116.68  5592.4  117.66
#Mann= 8 ,-1 , 0
  4369.3    .035       0  4455.9     .05       0  4658.8    .035       0
  4826.2     .05       0  4973.5     .05       0  4985.1     .05       0
  5277.9    .035       0  5449.1     .05       0
Bank Sta=4973.5,4985.1
XS Rating Curve= 0 ,0
Exp/Cntr=0.3,0.1

Type RM Length L Ch R = 1 ,4922    ,427,427,427
BEGIN DESCRIPTION:
Mapping XS 0da212e9
END DESCRIPTION:
XS GIS Cut Line= 4
      2584753.42     13492891.25      2584743.01     13492240.25
      2584597.17     13491932.96      2584358.25     13491558.99
#Sta/Elev= 30
  4221.5  108.43  4237.8  109.42  4407.8  102.73  4487.8   97.37  4817.8   81.53
  4933.7   80.48  4944.4   79.75  4955.9   75.73  4989.1   75.48  5005.3   72.64
  5005.8   72.14  5017.1   72.64  5018.1   74.88  5040.9   80.75  5099.8   82.11
  5160.1   88.52  5257.5   93.69  5293.4   98.72    5315   97.88  5357.4    99.7
  5364.6   100.7  5372.6  104.39  5378.5  103.16  5387.8  107.87  5393.7  108.92
  5430.1  111.64  5502.8  112.44  5545.2  109.97  5596.7  111.07  5656.5  107.84
#Mann= 3 ,-1 , 0
  4221.5     .05       0  5005.3     .05       0  5017.1     .05       0
Bank Sta=5005.3,5017.1
XS Rating Curve= 0 ,0
Exp/Cntr=0.3,0.1

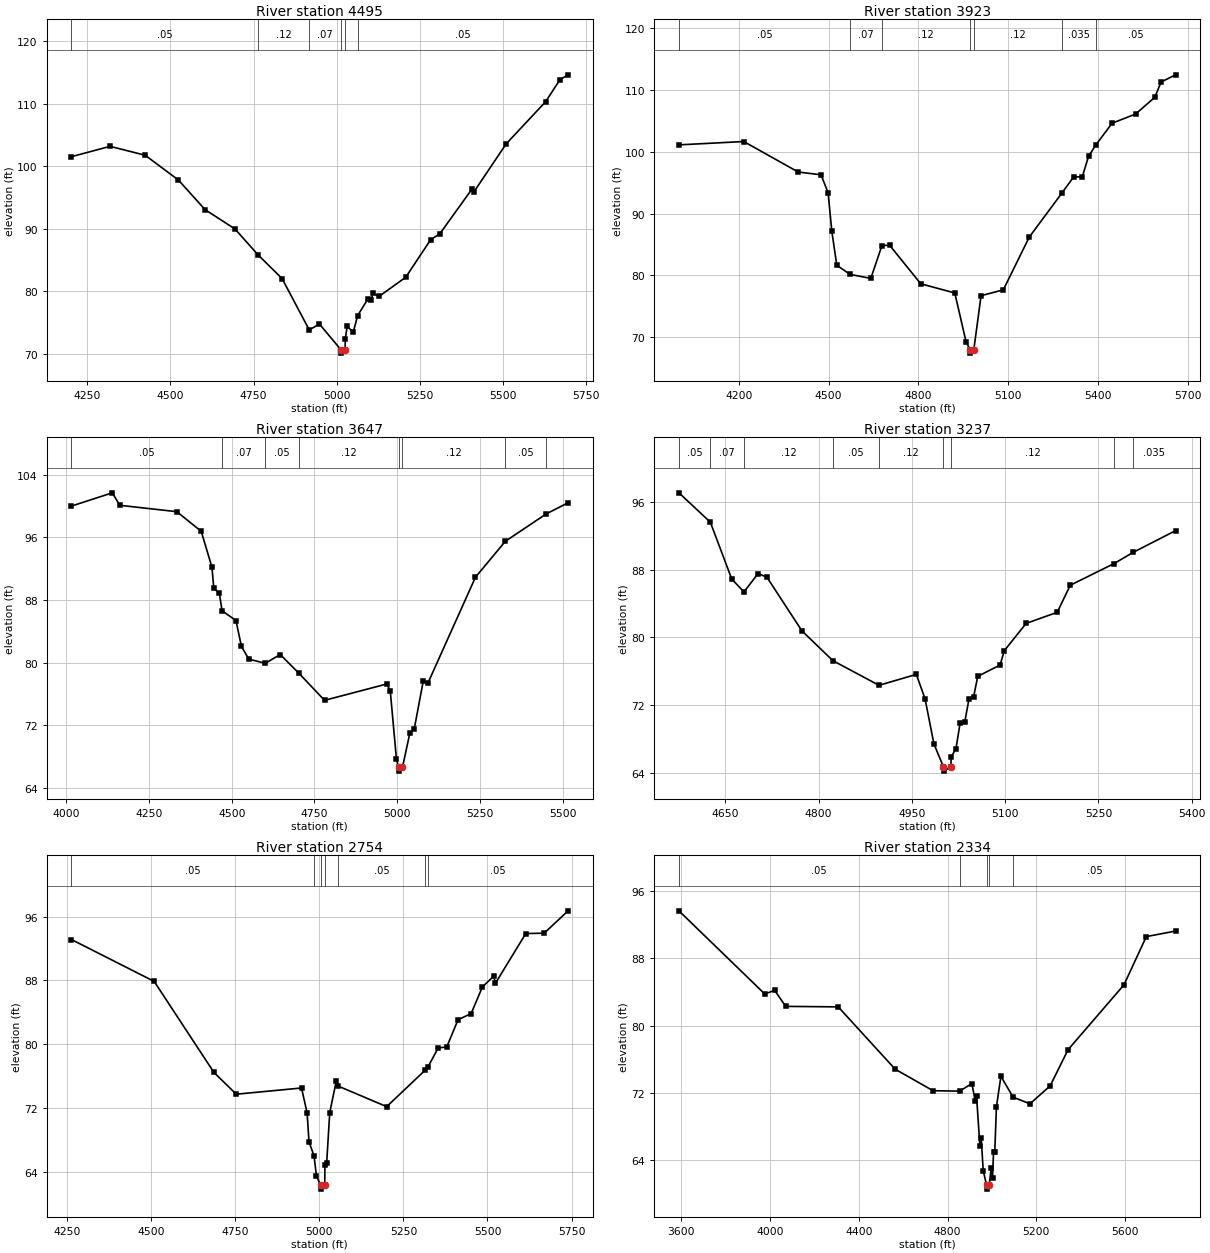
Type RM Length L Ch R = 1 ,4495    ,572,572,572
BEGIN DESCRIPTION:
Mapping XS 82a5288f
END DESCRIPTION:
XS GIS Cut Line= 4
      2585164.88      13492766.3      2585138.84     13492151.71
      2585003.42     13491818.37      2584749.09      13491366.8
#Sta/Elev= 30
  4202.5  101.53  4318.4  103.18    4424  101.76  4524.1   97.79  4604.2   93.06
  4694.2   89.97  4763.8   85.81  4835.7   82.05  4917.3   73.85  4948.2   74.77
  5013.3   70.63  5013.8   70.13  5025.1   70.63  5025.8   72.36  5031.2   74.39
  5049.9   73.52  5062.9   76.14  5094.7   78.86  5103.5   78.58  5108.9   79.68
  5127.1   79.19  5207.4   82.25  5282.6   88.27    5310    89.2  5406.8   96.36
  5412.6   95.91  5509.4  103.57  5627.9   110.3  5671.3  113.84  5695.7  114.61
#Mann= 6 ,-1 , 0
  4202.5     .05       0  4763.8     .12       0  4917.3     .07       0
  5013.3     .05       0  5025.1     .07       0  5062.9     .05       0
Bank Sta=5013.3,5025.1
XS Rating Curve= 0 ,0
Exp/Cntr=0.3,0.1

Type RM Length L Ch R = 1 ,3923    ,276,276,276
BEGIN DESCRIPTION:
Mapping XS df0138de
END DESCRIPTION:
XS GIS Cut Line= 4
      2585253.42     13492615.26      2585534.67     13491953.79
      2585477.38     13491490.25      2585103.27     13491199.27
#Sta/Elev= 30
  3999.8  101.13  4216.5  101.67  4398.3   96.74  4474.7   96.29  4498.3   93.39
  4510.8   87.15  4527.4   81.64  4572.3   80.17  4641.2   79.53  4678.2   84.84
  4703.8    84.9    4808   78.66  4921.8   77.17  4959.2   69.32  4973.4   67.94
  4973.9   67.44  4985.2   67.94  5009.6   76.73    5084   77.68  5170.8   86.22
  5280.8    93.4    5319   95.94    5348   95.96  5368.8   99.28  5393.3  101.12
  5447.5  104.63  5526.2  106.12  5590.5  108.84  5611.3   111.3  5659.6  112.46
#Mann= 7 ,-1 , 0
  3999.8     .05       0  4572.3     .07       0  4678.2     .12       0
  4973.4     .05       0  4985.2     .12       0  5280.8    .035       0
  5393.3     .05       0
Bank Sta=4973.4,4985.2
XS Rating Curve= 0 ,0
Exp/Cntr=0.3,0.1

Type RM Length L Ch R = 1 ,3647    ,410,410,410
BEGIN DESCRIPTION:
Mapping XS 64bea502
END DESCRIPTION:
XS GIS Cut Line= 3
      2585347.17     13492615.26      2585722.17     13491870.46
      2585888.85     13491224.59
#Sta/Elev= 30
  4015.6   99.99    4139  101.68  4161.4  100.09  4334.1   99.27  4407.7   96.76
  4440.1   92.18  4445.7   89.49  4462.4   88.87  4470.7   86.62  4512.6   85.37
  4529.3   82.06  4551.6   80.44  4601.3   79.91  4646.5   81.03    4702   78.68
  4780.4   75.18  4968.7   77.27    4979    76.4  4997.7   67.67  5004.1   66.64
  5004.6   66.14    5016   66.64  5038.4   71.04  5051.3   71.48    5079    77.7
  5092.6   77.36  5236.5    90.9  5326.8   95.49    5450   98.98  5516.5  100.41
#Mann= 8 ,-1 , 0
  4015.6     .05       0  4470.7     .07       0  4601.3     .05       0
    4702     .12       0  5004.1     .05       0    5016     .12       0
  5326.8     .05       0    5450    .035       0
Bank Sta=5004.1,5016
XS Rating Curve= 0 ,0
Exp/Cntr=0.3,0.1

Type RM Length L Ch R = 1 ,3237    ,483,483,483
BEGIN DESCRIPTION:
WRIGHT CREEK 6.0
END DESCRIPTION:
XS GIS Cut Line= 3
      2585574.97     13492325.03        2585875.       13492025.
      2586124.86     13491745.91
#Sta/Elev= 30
  4575.2   97.06  4625.7    93.6  4660.1    86.9  4679.8   85.37  4702.5   87.54
  4716.7   87.11  4773.2   80.77  4822.8   77.27  4897.1   74.36  4957.1   75.65
  4971.2   72.75  4985.4   67.45  5000.7   64.74  5001.2   64.24  5012.6   64.74
  5013.3   65.95  5020.8   66.86  5027.5    69.9    5035   70.03  5041.7   72.71
  5049.2   72.98  5055.9   75.42  5091.8   76.75  5098.6   78.44  5133.7   81.66
  5183.8   82.97  5204.7   86.16  5275.3   88.72  5305.7   90.03  5374.1    92.6
#Mann= 9 ,-1 , 0
  4575.2     .05       0  4625.7     .07       0  4679.8     .12       0
  4822.8     .05       0  4897.1     .12       0  5000.7     .05       0
  5012.6     .12       0  5275.3     .05       0  5305.7    .035       0
Bank Sta=5000.7,5012.6
XS Rating Curve= 0 ,0
Exp/Cntr=0.3,0.1

Type RM Length L Ch R = 1 ,2754    ,420,420,420
BEGIN DESCRIPTION:
WRIGHT CREEK 5.0
END DESCRIPTION:
XS GIS Cut Line= 3
      2585519.59     13492611.48        2586175.       13492275.
      2586380.35       13491564.
#Sta/Elev= 30
  4262.9   93.12  4508.8   87.87  4686.3   76.47  4752.9   73.73    4947   74.51
  4963.5   71.39  4969.2   67.76  4984.2      66  4991.4   63.44  5004.1   62.33
  5004.6   61.83    5016   62.33  5016.5   64.86  5021.7   65.07  5030.9   71.43
  5050.1   75.34  5055.9   74.75  5200.2   72.17  5314.3   76.73  5322.2   77.09
  5353.5   79.54  5378.8   79.65  5412.4   83.06  5451.3   83.84  5484.9   87.18
  5518.5   88.53  5523.7   87.64  5613.8   93.87  5668.7   93.92  5739.7   96.72
#Mann= 7 ,-1 , 0
  4262.9     .05       0  4984.2     .07       0  5004.1     .05       0
    5016     .07       0  5055.9     .05       0  5314.3     .12       0
  5322.2     .05       0
Bank Sta=5004.1,5016
XS Rating Curve= 0 ,0
Exp/Cntr=0.3,0.1

Type RM Length L Ch R = 1 ,2334    ,0,0,0
BEGIN DESCRIPTION:
WRIGHT CREEK 4.0
END DESCRIPTION:
XS GIS Cut Line= 4
      2585262.59     13492910.11      2586425.29     13492474.57
        2586525.       13492325.      2586630.67     13491514.31
#Sta/Elev= 30
  3588.9   93.61  3975.9   83.74  4020.4   84.17  4070.2   82.27  4307.1   82.21
  4563.5   74.82  4734.5   72.26  4854.6   72.21  4909.6   73.11  4924.6   71.03
  4930.6   71.64  4945.7    65.7  4951.7   66.61  4960.7   62.78  4975.7   61.08
  4976.2   60.58  4987.7   61.08  4996.7   63.07  5002.7   61.88  5007.2   64.98
  5012.8   64.98  5020.3   70.35  5040.5   73.97  5095.5   71.49  5171.6   70.71
  5262.4   72.83    5343   77.12  5595.4   84.83    5696   90.55  5827.8   91.21
#Mann= 5 ,-1 , 0
  3588.9     .05       0  4854.6     .12       0  4975.7     .05       0
  4987.7     .12       0  5095.5     .05       0
Bank Sta=4975.7,4987.7
XS Rating Curve= 0 ,0
Exp/Cntr=0.3,0.1

Chan Stop Cuts=-1
Use User Specified Reach Order=0
Composite Channel Slope=5