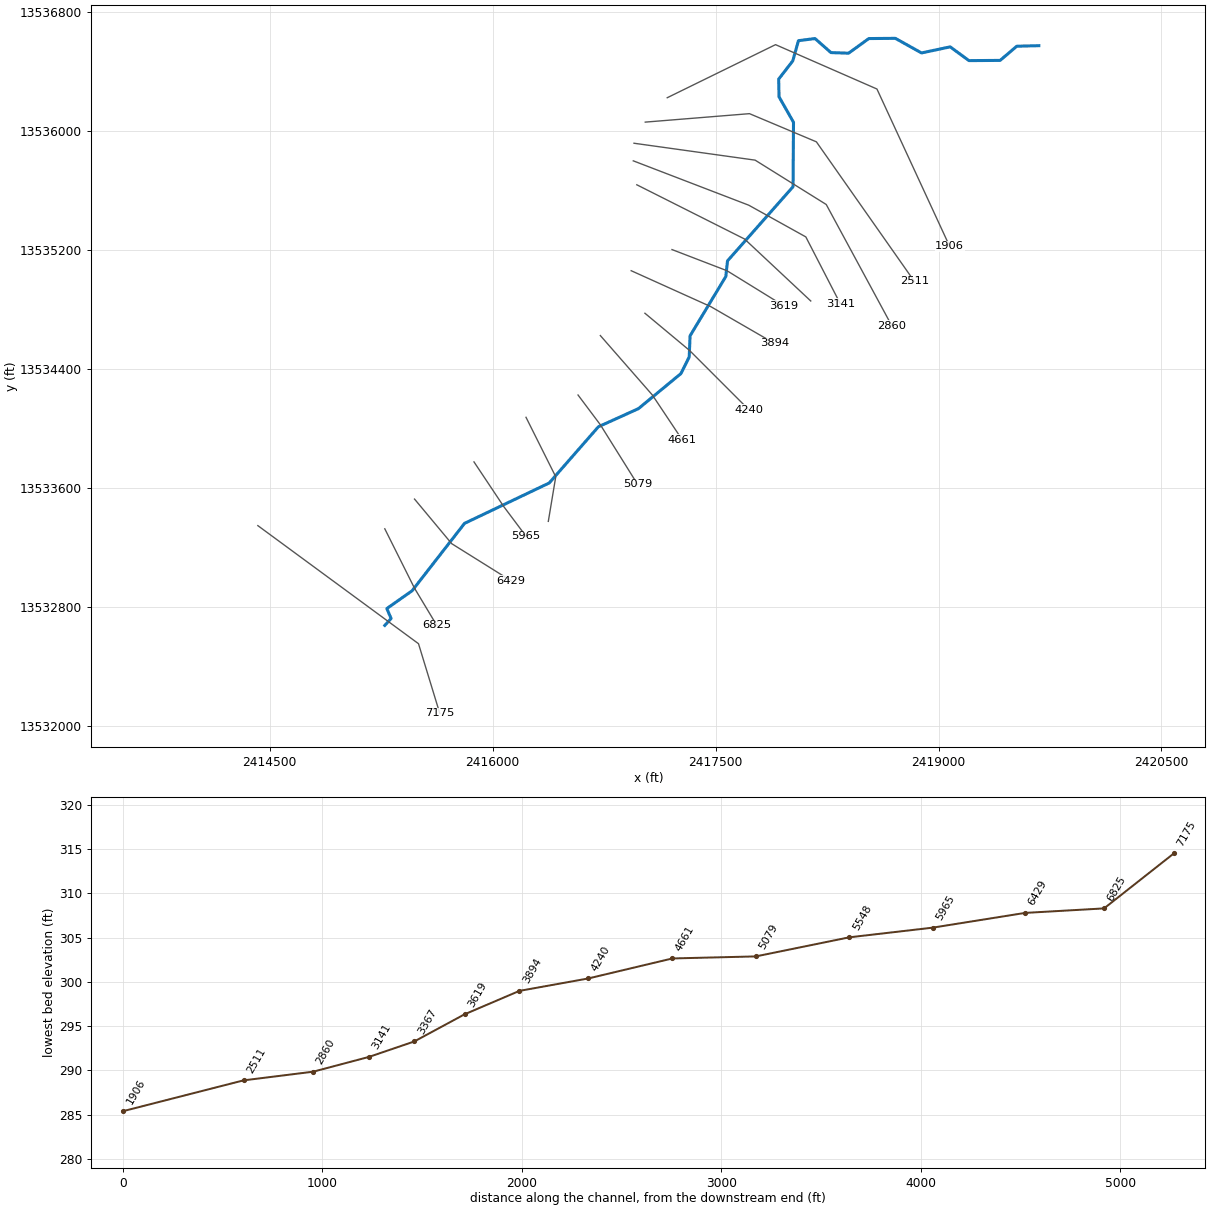
--- BOGGY BRANCH NR THOMAS CR.prj (project) ---

Proj Title=BOGGY BRANCH NR THOMAS CR Base Level Engineering
Current Plan=p01
Default Exp/Contr=0.3,0.1
English Units
Geom File=g01
Flow File=f01
Plan File=p01
BEGIN DESCRIPTION:
BOGGY BRANCH NR THOMAS CR
END DESCRIPTION:

--- BOGGY BRANCH NR THOMAS CR.p01 (plan) ---

Plan Title=Multiple Run
Short Identifier=Multiple
Geom File=g01
Flow File=f01
Subcritical Flow
K Sum by GR= 0
Std Step Tol= 0.01
Critical Tol= 0.01
Num of Std Step Trials= 20
Max Error Tol= 0.3
Flow Tol Ratio= 0.001
Split Flow NTrial= 30
Split Flow Tol= 0.02
Split Flow Ratio= 0.02
Log Output Level= 0
Friction Slope Method= 1
Unsteady Friction Slope Method= 2
Unsteady Bridges Friction Slope Method= 1
Parabolic Critical Depth
Global Vel Dist=  1 , 1 , 1
Global Log Level= 0
CheckData=True
Encroach Param= -1, 0, 0, 0
BEGIN DESCRIPTION:
Multiple Run
END DESCRIPTION:

--- BOGGY BRANCH NR THOMAS CR.f01 (steady flow) ---

Flow Title=Multiple
Number of Profiles=7
Profile Names=10-year,25-year,50-year,1pct_min,100-year,1pct_plu,500-year
River Rch & RM= BOGGY BRANCH NR ,Reach-1,7175
     692    1130    1529    1002    1999    3988    3380
River Rch & RM= BOGGY BRANCH NR ,Reach-1,6825
     949    1577    2160    1430    2854    5694    4936
River Rch & RM= BOGGY BRANCH NR ,Reach-1,5079
    1147    1923    2649    1763    3519    7020    6149
Boundary for River Rch & Prof#=BOGGY BRANCH NR ,Reach-1,1
Up Type=0
Dn Type=3
Dn Slope=0.005
Boundary for River Rch & Prof#=BOGGY BRANCH NR ,Reach-1,2
Up Type=0
Dn Type=3
Dn Slope=0.005
Boundary for River Rch & Prof#=BOGGY BRANCH NR ,Reach-1,3
Up Type=0
Dn Type=3
Dn Slope=0.005
Boundary for River Rch & Prof#=BOGGY BRANCH NR ,Reach-1,4
Up Type=0
Dn Type=3
Dn Slope=0.005
Boundary for River Rch & Prof#=BOGGY BRANCH NR ,Reach-1,5
Up Type=0
Dn Type=3
Dn Slope=0.005
Boundary for River Rch & Prof#=BOGGY BRANCH NR ,Reach-1,6
Up Type=0
Dn Type=3
Dn Slope=0.005
Boundary for River Rch & Prof#=BOGGY BRANCH NR ,Reach-1,7
Up Type=0
Dn Type=3
Dn Slope=0.005

--- BOGGY BRANCH NR THOMAS CR.g01 (geometry) ---

Geom Title=Existing Conditions

River Reach=BOGGY BRANCH NR ,Reach-1
Reach XY= 30
      2415275.00     13532675.00      2415317.48     13532721.67
      2415288.58     13532788.36      2415458.50     13532907.95
      2415811.43     13533361.53      2416381.06     13533633.14
      2416711.78     13534011.38      2416981.05     13534133.16
      2417266.86     13534368.94      2417322.75     13534480.93
      2417328.76     13534623.44      2417569.23     13535022.68
      2417580.52     13535127.43      2418021.46     13535626.46
      2418024.49     13536059.79      2417927.23     13536230.93
      2417924.68     13536350.11      2418019.46     13536472.58
      2418057.79     13536608.79      2418169.10     13536623.03
      2418276.47     13536528.54      2418395.16     13536524.54
      2418530.86     13536622.94      2418709.79     13536624.49
      2418885.50     13536526.19      2419078.41     13536567.19
      2419204.82     13536474.57      2419414.56     13536476.06
      2419526.45     13536571.49      2419675.00     13536575.00

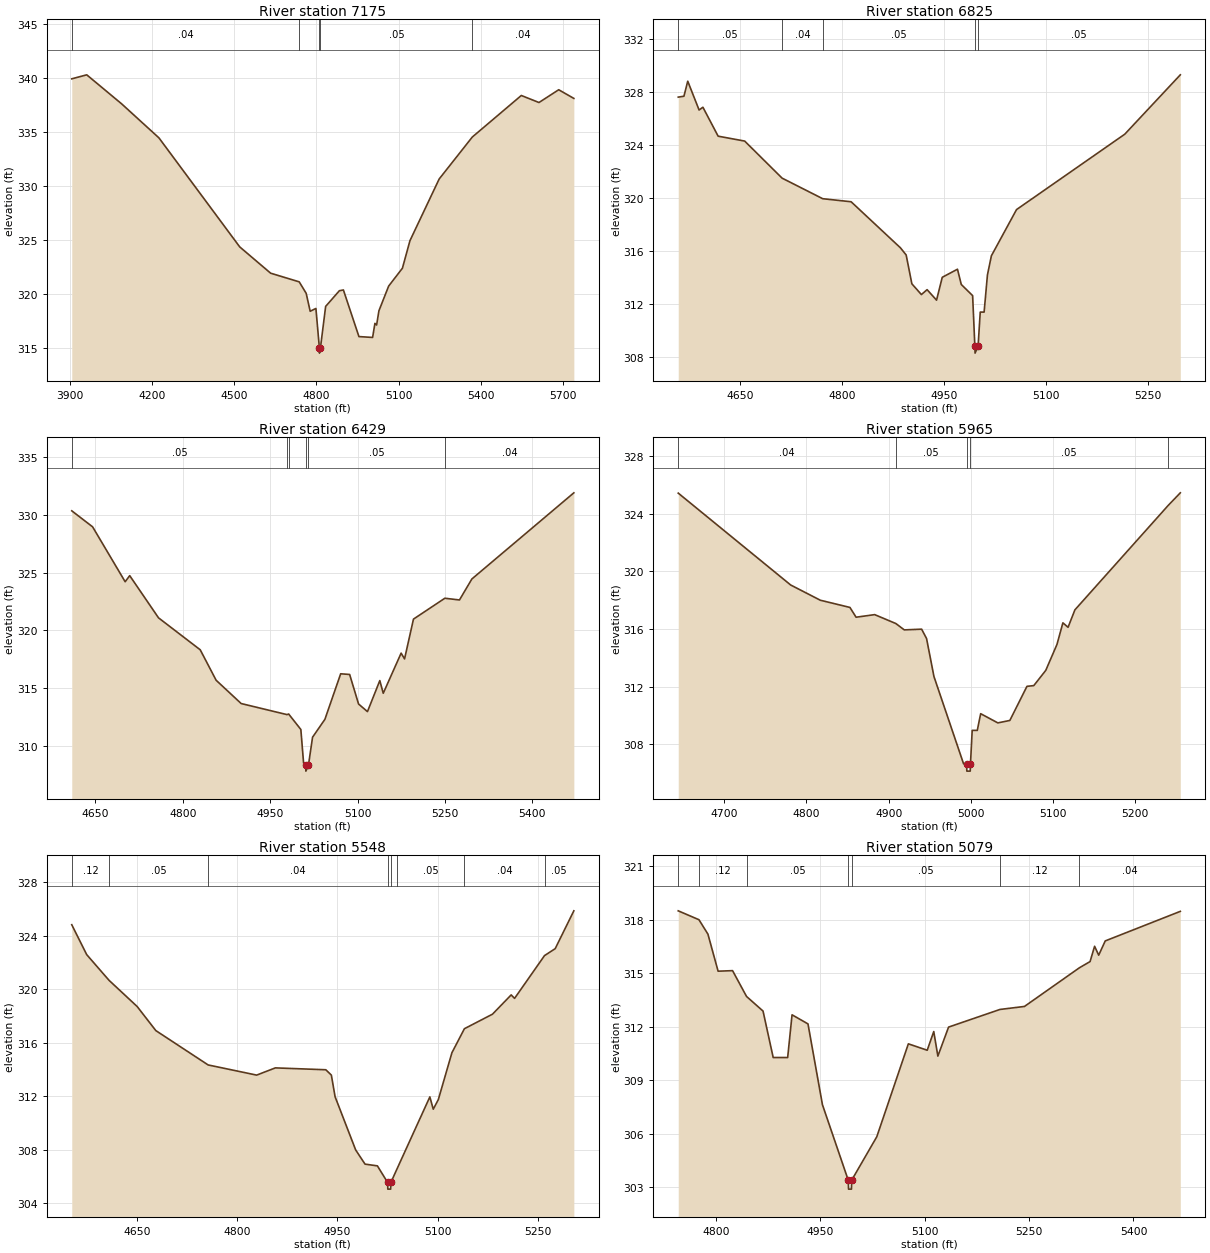
Type RM Length L Ch R = 1,7175,350,350,350
BEGIN DESCRIPTION:
LGII4645
END DESCRIPTION:
XS GIS Cut Line= 3
      2414421.00     13533346.29      2415501.72     13532552.02
      2415644.94     13532083.32
#Sta/Elev= 30
  3907.9  339.89  3962.5  340.26  4090.1  337.57  4225.9  334.43  4520.6  324.35
  4633.3  321.92  4737.5  321.12  4762.9  320.06  4777.5  318.40  4798.4  318.66
  4811.0  315.03  4811.3  314.53  4815.0  315.03  4833.9  318.85  4884.0  320.30
  4898.7  320.37  4955.3  316.06  5005.2  315.98  5013.6  317.28  5019.8  317.13
  5028.3  318.45  5063.8  320.73  5113.9  322.38  5141.5  324.93  5248.0  330.63
  5368.9  334.51  5547.6  338.35  5612.0  337.70  5684.0  338.88  5739.2  338.08
#Mann=5,-1,0
  3907.9    0.04       0  4737.5    0.05       0  4811.0    0.05       0
  4815.0    0.05       0  5368.9    0.04       0
Bank Sta=4811,4815
Exp/Cntr=0.3,0.1

Type RM Length L Ch R = 1,6825,396,396,396
BEGIN DESCRIPTION:
BOGGY BRANCH NEAR THOMAS CREEK 12.0
END DESCRIPTION:
XS GIS Cut Line= 3
      2415275.00     13533325.00      2415475.00     13532925.00
      2415625.02     13532674.97
#Sta/Elev= 30
  4558.7  327.59  4567.1  327.66  4572.7  328.79  4589.4  326.62  4595.0  326.83
  4617.4  324.65  4656.5  324.28  4711.5  321.49  4771.3  319.94  4813.1  319.71
  4885.7  316.24  4894.1  315.70  4902.5  313.53  4916.5  312.72  4924.9  313.09
  4938.8  312.30  4947.2  314.02  4969.6  314.63  4975.2  313.48  4991.9  312.64
  4995.2  308.81  4995.5  308.31  4999.9  308.81  5003.1  311.40  5008.8  311.40
  5013.7  314.20  5019.5  315.64  5056.5  319.12  5215.8  324.80  5297.5  329.27
#Mann=5,-1,0
  4558.7    0.05       0  4711.5    0.04       0  4771.3    0.05       0
  4995.2    0.05       0  4999.9    0.05       0
Bank Sta=4995.2,4999.9
Exp/Cntr=0.3,0.1

Type RM Length L Ch R = 1,6429,464,464,464
BEGIN DESCRIPTION:
BOGGY BRANCH NEAR THOMAS CREEK 11.0
END DESCRIPTION:
XS GIS Cut Line= 3
      2415475.02     13533524.98      2415725.00     13533225.00
      2416125.02     13532974.99
#Sta/Elev= 30
  4609.3  330.37  4645.1  328.98  4701.0  324.22  4708.8  324.75  4758.3  321.09
  4829.9  318.32  4857.2  315.68  4900.2  313.66  4978.9  312.70  4981.8  312.75
  5002.7  311.41  5007.4  308.50  5011.0  308.30  5011.3  307.80  5015.7  308.30
  5022.8  310.74  5044.0  312.29  5071.1  316.24  5086.5  316.18  5101.8  313.62
  5117.1  312.96  5138.3  315.65  5144.2  314.55  5174.9  318.03  5180.8  317.53
  5196.1  320.98  5250.0  322.79  5275.1  322.64  5296.4  324.46  5471.5  331.93
#Mann=6,-1,0
  4609.3    0.05       0  4978.9    0.04       0  4981.8    0.05       0
  5011.0    0.05       0  5015.7    0.05       0  5250.0    0.04       0
Bank Sta=5011,5015.7
Exp/Cntr=0.3,0.1

Type RM Length L Ch R = 1,5965,417,417,417
BEGIN DESCRIPTION:
BOGGY BRANCH NEAR THOMAS CREEK 10.0
END DESCRIPTION:
XS GIS Cut Line= 3
      2415875.00     13533775.00      2416075.00     13533475.00
      2416225.03     13533274.96
#Sta/Elev= 30
  4644.1  325.44  4780.8  319.06  4816.9  318.00  4852.9  317.50  4860.4  316.82
  4883.0  317.00  4908.8  316.38  4919.0  315.94  4940.1  315.99  4946.1  315.34
  4955.1  312.70  4991.1  306.64  4994.7  306.63  4995.1  306.13  4999.2  306.13
  4999.5  306.63  5001.6  308.96  5007.8  308.96  5011.9  310.12  5032.8  309.48
  5047.4  309.65  5068.2  312.02  5076.5  312.07  5091.1  313.13  5104.7  314.93
  5111.9  316.43  5118.2  316.12  5126.5  317.33  5239.9  324.58  5254.7  325.46
#Mann=5,-1,0
  4644.1    0.04       0  4908.8    0.05       0  4994.7    0.05       0
  4999.5    0.05       0  5239.9    0.04       0
Bank Sta=4994.7,4999.5
Exp/Cntr=0.3,0.1

Type RM Length L Ch R = 1,5548,469,469,469
BEGIN DESCRIPTION:
BOGGY BRANCH NEAR THOMAS CREEK 9.0
END DESCRIPTION:
XS GIS Cut Line= 3
      2416224.99     13534075.02      2416425.00     13533675.00
      2416375.00     13533374.98
#Sta/Elev= 30
  4552.4  324.82  4574.8  322.58  4608.2  320.66  4650.3  318.70  4678.2  316.90
  4756.5  314.33  4829.1  313.57  4857.1  314.11  4932.6  313.97  4940.9  313.57
  4946.5  311.95  4977.3  307.97  4991.3  306.91  5009.8  306.78  5025.1  305.54
  5025.4  305.04  5029.6  305.04  5030.0  305.54  5039.5  306.59  5088.3  311.94
  5093.4  311.02  5101.0  311.74  5121.3  315.24  5140.0  317.04  5182.1  318.13
  5210.0  319.57  5215.1  319.31  5259.9  322.51  5275.9  323.03  5303.8  325.86
#Mann=8,-1,0
  4552.4    0.12       0  4608.2    0.05       0  4756.5    0.04       0
  5025.1    0.04       0  5030.0    0.04       0  5039.5    0.05       0
  5140.0    0.04       0  5259.9    0.05       0
Bank Sta=5025.1,5030
Exp/Cntr=0.3,0.1

Type RM Length L Ch R = 1,5079,418,418,418
BEGIN DESCRIPTION:
BOGGY BRANCH NEAR THOMAS CREEK 8.0
END DESCRIPTION:
XS GIS Cut Line= 3
      2416574.99     13534225.01      2416725.00     13534025.00
      2416974.99     13533625.01
#Sta/Elev= 30
  4745.6  318.51  4775.4  318.01  4788.3  317.20  4802.9  315.12  4823.7  315.15
  4843.8  313.70  4867.5  312.88  4882.1  310.27  4902.9  310.27  4909.2  312.67
  4932.1  312.16  4952.9  307.62  4990.0  303.38  4990.4  302.88  4994.6  302.88
  4994.9  303.38  5031.0  305.82  5076.4  311.04  5103.5  310.68  5112.9  311.73
  5118.8  310.35  5134.2  311.98  5208.0  312.97  5243.3  313.14  5322.2  315.31
  5337.6  315.66  5344.1  316.52  5350.0  316.02  5359.4  316.82  5467.3  318.48
#Mann=7,-1,0
  4745.6    0.05       0  4775.4    0.12       0  4843.8    0.05       0
  4990.0    0.05       0  4994.9    0.05       0  5208.0    0.12       0
  5322.2    0.04       0
Bank Sta=4990,4994.9
Exp/Cntr=0.3,0.1

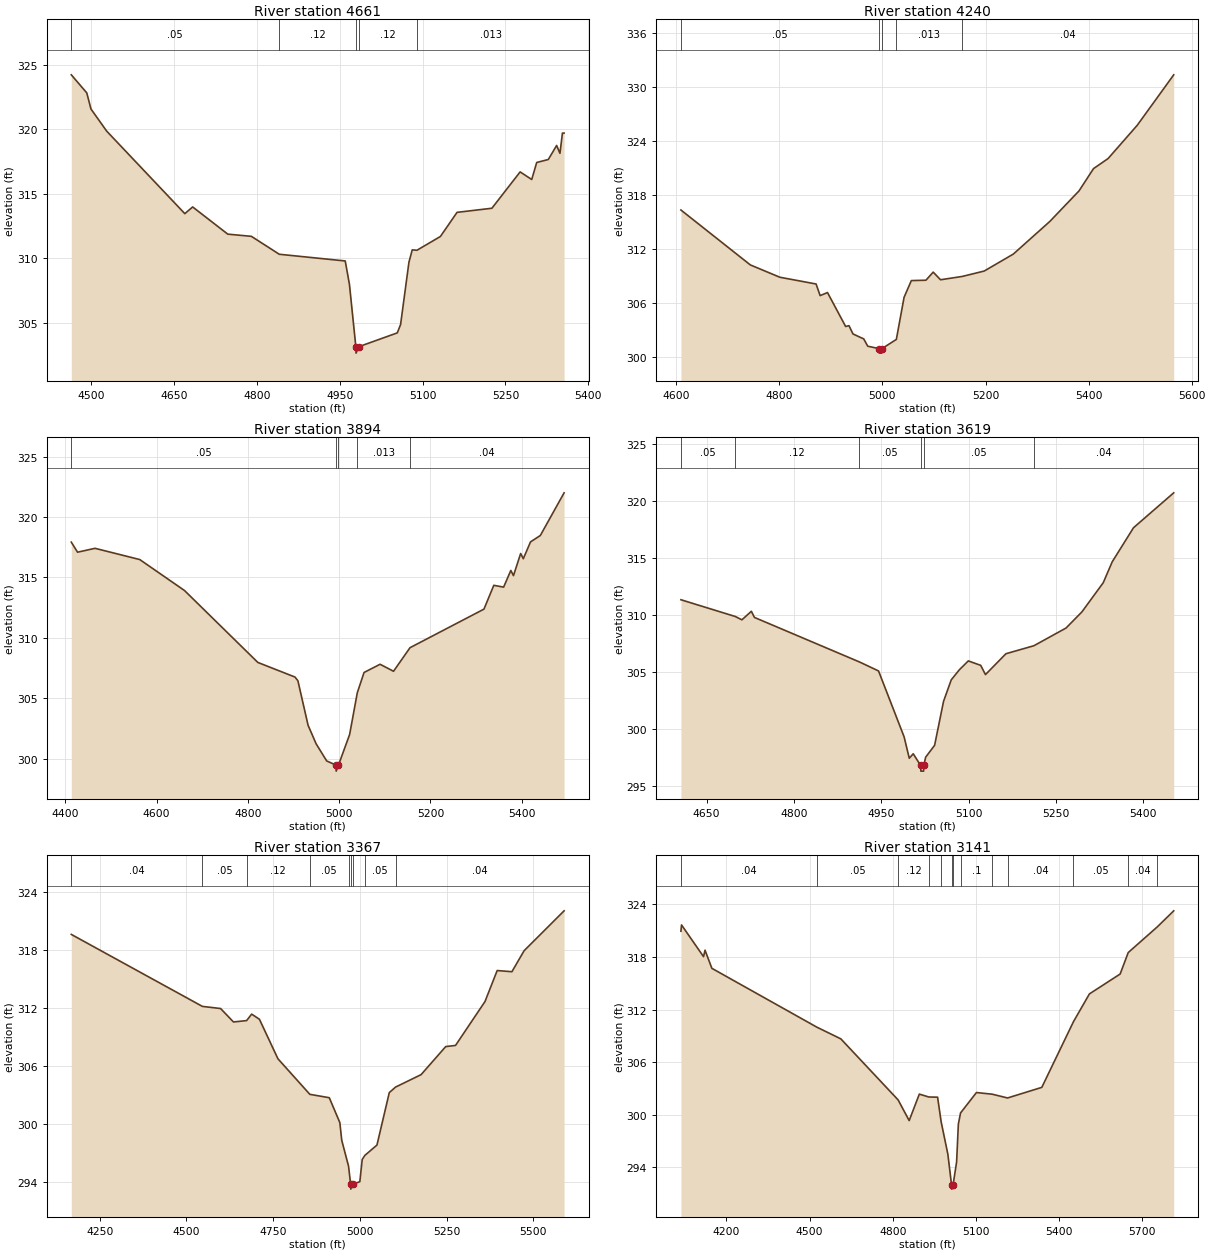
Type RM Length L Ch R = 1,4661,421,421,421
BEGIN DESCRIPTION:
BOGGY BRANCH NEAR THOMAS CREEK 7.0
END DESCRIPTION:
XS GIS Cut Line= 3
      2416724.98     13534625.02      2417075.00     13534225.00
      2417275.01     13533924.99
#Sta/Elev= 30
  4464.0  324.24  4492.0  322.84  4499.6  321.59  4528.1  319.87  4669.5  313.47
  4683.7  313.99  4747.3  311.88  4790.0  311.71  4840.5  310.32  4959.9  309.80
  4967.5  307.99  4979.1  303.15  4979.5  302.65  4984.5  303.15  5054.1  304.22
  5060.1  304.87  5075.2  309.70  5081.2  310.66  5089.7  310.63  5132.2  311.70
  5162.3  313.57  5225.4  313.89  5276.5  316.71  5297.5  316.12  5306.5  317.44
  5327.5  317.67  5342.6  318.76  5348.6  318.15  5353.1  319.72  5356.1  319.72
#Mann=5,-1,0
  4464.0    0.05       0  4840.5    0.12       0  4979.1    0.05       0
  4984.5    0.12       0  5089.7   0.013       0
Bank Sta=4979.1,4984.5
Exp/Cntr=0.3,0.1

Type RM Length L Ch R = 1,4240,346,346,346
BEGIN DESCRIPTION:
BOGGY BRANCH NEAR THOMAS CREEK 6.0
END DESCRIPTION:
XS GIS Cut Line= 3
      2417024.99     13534775.01      2417325.00     13534525.00
      2417724.99     13534125.01
#Sta/Elev= 30
  4609.0  316.29  4743.7  310.19  4801.0  308.82  4871.3  308.07  4879.1  306.78
  4893.4  307.12  4928.6  303.35  4935.1  303.44  4942.9  302.52  4963.7  301.97
  4971.5  301.16  4993.6  300.89  4994.0  300.39  4998.6  300.39  4999.0  300.89
  5027.0  301.91  5042.0  306.59  5056.1  308.45  5084.4  308.49  5098.5  309.39
  5112.7  308.54  5154.9  308.91  5197.5  309.51  5254.1  311.40  5324.8  315.02
  5381.4  318.41  5409.6  320.89  5437.9  322.01  5494.5  325.71  5565.2  331.31
#Mann=5,-1,0
  4609.0    0.05       0  4993.6    0.05       0  4999.0    0.05       0
  5027.0   0.013       0  5154.9    0.04       0
Bank Sta=4993.6,4999
Exp/Cntr=0.3,0.1

Type RM Length L Ch R = 1,3894,275,275,275
BEGIN DESCRIPTION:
Mapping XS 5f1b0d33
END DESCRIPTION:
XS GIS Cut Line= 3
      2416932.47     13535061.31      2417467.77     13534819.71
      2417894.13     13534573.37
#Sta/Elev= 30
  4413.1  317.92  4426.8  317.09  4465.1  317.41  4563.1  316.48  4661.1  313.92
  4821.8  307.97  4903.3  306.76  4909.6  306.45  4931.9  302.77  4949.5  301.24
  4972.7  299.82  4993.0  299.48  4993.5  298.98  4998.5  299.48  5022.9  302.01
  5039.7  305.46  5054.5  307.14  5089.6  307.82  5119.1  307.24  5155.2  309.19
  5317.2  312.38  5338.8  314.35  5360.3  314.20  5376.1  315.58  5381.9  315.15
  5397.6  316.98  5403.4  316.55  5419.2  317.94  5440.7  318.47  5492.8  322.00
#Mann=5,-1,0
  4413.1    0.05       0  4993.0    0.05       0  4998.5    0.05       0
  5039.7   0.013       0  5155.2    0.04       0
Bank Sta=4993,4998.5
Exp/Cntr=0.3,0.1

Type RM Length L Ch R = 1,3619,252,252,252
BEGIN DESCRIPTION:
Mapping XS 7c4ab3fb
END DESCRIPTION:
XS GIS Cut Line= 3
      2417207.19     13535203.45      2417576.73     13535061.32
      2417960.22     13534824.60
#Sta/Elev= 30
  4605.8  311.35  4699.3  309.88  4710.6  309.59  4726.8  310.34  4732.1  309.80
  4912.4  305.90  4945.3  305.11  4989.2  299.34  4998.1  297.46  5004.9  297.85
  5017.6  296.83  5018.0  296.33  5022.7  296.33  5023.1  296.83  5026.2  297.55
  5041.6  298.59  5057.0  302.45  5070.2  304.33  5084.1  305.21  5099.5  305.99
  5120.8  305.60  5129.0  304.79  5164.2  306.62  5212.2  307.32  5267.4  308.87
  5294.6  310.28  5331.3  312.84  5346.7  314.67  5383.3  317.66  5452.4  320.72
#Mann=6,-1,0
  4605.8    0.05       0  4699.3    0.12       0  4912.4    0.05       0
  5017.6    0.05       0  5023.1    0.05       0  5212.2    0.04       0
Bank Sta=5017.6,5023.1
Exp/Cntr=0.3,0.1

Type RM Length L Ch R = 1,3367,226,226,226
BEGIN DESCRIPTION:
Mapping XS d6e1a561
END DESCRIPTION:
XS GIS Cut Line= 3
      2416970.34     13535639.28      2417695.16     13535274.50
      2418140.45     13534857.64
#Sta/Elev= 30
  4167.8  319.62  4545.9  312.17  4598.4  311.95  4635.5  310.56  4673.4  310.70
  4688.0  311.37  4710.4  310.84  4763.8  306.75  4855.8  303.07  4911.9  302.72
  4942.3  300.15  4947.9  298.31  4967.5  295.63  4973.5  293.76  4974.0  293.26
  4979.1  293.76  5000.0  294.03  5006.9  296.33  5014.5  296.75  5049.4  297.82
  5085.0  303.25  5103.1  303.82  5176.8  305.11  5247.7  308.01  5276.0  308.13
  5361.0  312.67  5396.2  315.88  5438.7  315.76  5473.8  317.93  5589.2  322.06
#Mann=9,-1,0
  4167.8    0.04       0  4545.9    0.05       0  4673.4    0.12       0
  4855.8    0.05       0  4967.5    0.12       0  4973.5    0.05       0
  4979.1    0.12       0  5014.5    0.05       0  5103.1    0.04       0
Bank Sta=4973.5,4979.1
Exp/Cntr=0.3,0.1

Type RM Length L Ch R = 1,3141,281,281,281
BEGIN DESCRIPTION:
Mapping XS 3de2fbb6
END DESCRIPTION:
XS GIS Cut Line= 4
      2416946.70     13535800.33      2417723.59     13535501.89
      2418107.32     13535288.71      2418339.08     13534839.37
#Sta/Elev= 30
  4036.3  320.94  4038.5  321.66  4117.9  318.04  4123.2  318.78  4147.9  316.71
  4526.3  310.00  4613.0  308.66  4819.4  301.70  4859.3  299.34  4895.9  302.36
  4930.2  302.03  4961.7  302.01  4974.7  299.18  4998.8  295.50  5012.0  292.02
  5012.5  291.52  5017.7  292.02  5030.3  294.63  5036.6  298.94  5044.5  300.21
  5101.8  302.54  5158.8  302.35  5214.0  301.92  5337.5  303.13  5451.6  310.62
  5509.1  313.79  5619.9  316.06  5649.1  318.51  5753.9  321.44  5813.1  323.27
#Mann=13,-1,0
  4036.3    0.04       0  4526.3    0.05       0  4819.4    0.12       0
  4930.2     0.1       0  4974.7    0.12       0  5012.0    0.05       0
  5017.7    0.12       0  5044.5     0.1       0  5158.8    0.12       0
  5214.0    0.04       0  5451.6    0.05       0  5649.1    0.04       0
  5753.9    0.05       0
Bank Sta=5012,5017.7
Exp/Cntr=0.3,0.1

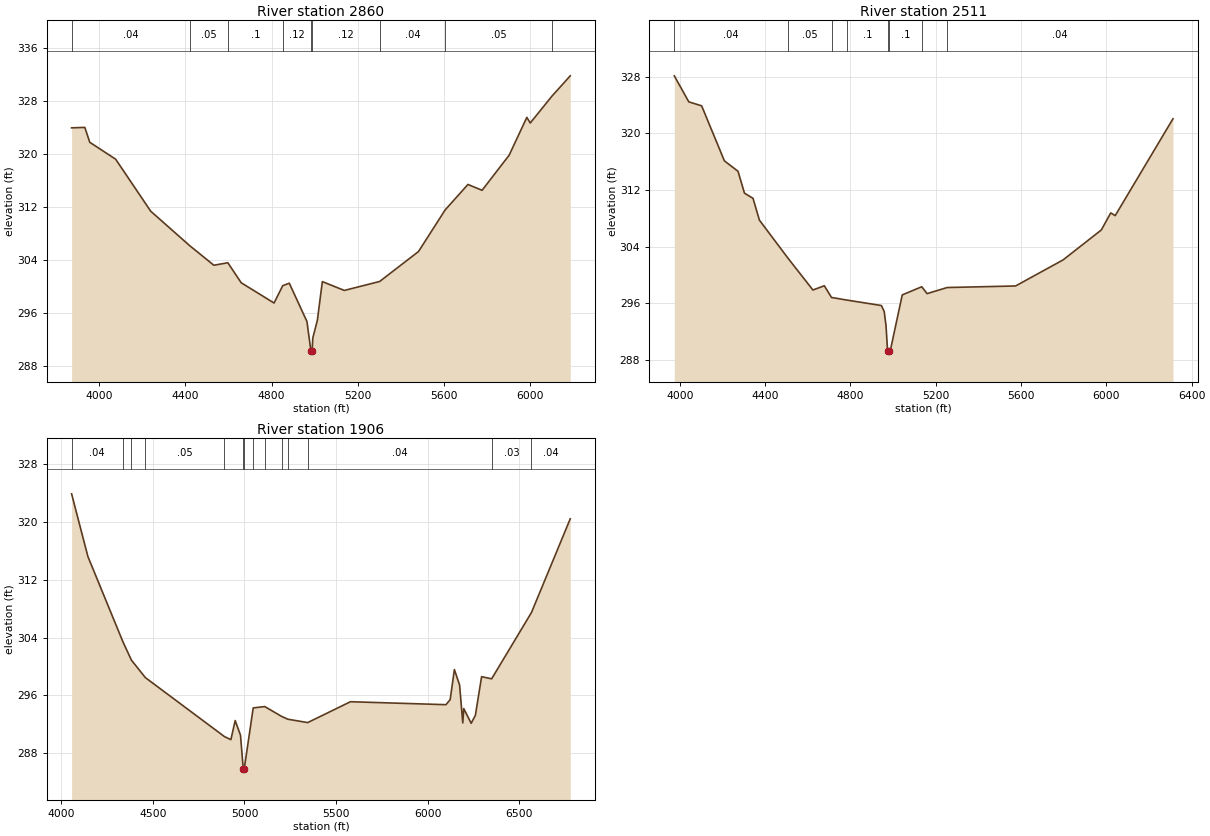
Type RM Length L Ch R = 1,2860,349,349,349
BEGIN DESCRIPTION:
Mapping XS af4fb2b7
END DESCRIPTION:
XS GIS Cut Line= 4
      2416951.43     13535918.78      2417766.23     13535805.08
      2418244.70     13535506.63      2418685.26     13534691.83
#Sta/Elev= 30
  3872.4  323.98  3933.7  324.05  3956.8  321.80  4076.8  319.25  4239.5  311.40
  4419.3  306.23  4532.3  303.25  4597.1  303.63  4659.0  300.61  4811.5  297.55
  4851.8  300.17  4882.2  300.54  4964.0  294.76  4982.4  290.34  4982.9  289.84
  4988.1  290.34  4991.2  292.28  5012.4  294.95  5035.4  300.78  5137.4  299.45
  5301.2  300.80  5481.5  305.32  5604.9  311.59  5710.8  315.44  5776.4  314.56
  5902.0  319.86  5983.9  325.56  5999.8  324.71  6100.5  328.77  6185.3  331.83
#Mann=9,-1,0
  3872.4    0.04       0  4419.3    0.05       0  4597.1     0.1       0
  4851.8    0.12       0  4982.4    0.05       0  4988.1    0.12       0
  5301.2    0.04       0  5604.9    0.05       0  6100.5    0.04       0
Bank Sta=4982.4,4988.1
Exp/Cntr=0.3,0.1

Type RM Length L Ch R = 1,2511,605,605,605
BEGIN DESCRIPTION:
Mapping XS f4b03e53
END DESCRIPTION:
XS GIS Cut Line= 4
      2417027.20     13536060.90      2417728.33     13536117.75
      2418178.38     13535928.26      2418836.87     13534990.26
#Sta/Elev= 30
  3974.5  328.10  4042.5  324.43  4102.7  323.87  4209.4  316.11  4273.3  314.64
  4303.4  311.56  4343.5  310.83  4373.6  307.75  4508.0  302.37  4624.4  297.90
  4677.9  298.50  4711.5  296.85  4784.0  296.48  4945.6  295.71  4958.7  294.86
  4967.3  292.82  4974.2  289.36  4974.6  288.86  4979.9  289.36  4989.0  289.61
  5043.2  297.21  5134.8  298.36  5159.5  297.39  5253.9  298.25  5574.5  298.47
  5797.5  302.15  5976.6  306.37  6020.6  308.77  6041.6  308.39  6312.3  322.04
#Mann=8,-1,0
  3974.5    0.04       0  4508.0    0.05       0  4711.5    0.12       0
  4784.0     0.1       0  4974.2    0.05       0  4979.9     0.1       0
  5134.8    0.05       0  5253.9    0.04       0
Bank Sta=4974.2,4979.9
Exp/Cntr=0.3,0.1

Type RM Length L Ch R = 1,1906,0,0,0
BEGIN DESCRIPTION:
BOGGY BRANCH NEAR THOMAS CREEK 1.0
END DESCRIPTION:
XS GIS Cut Line= 4
      2417175.00     13536225.00      2417903.61     13536582.01
      2418585.79     13536283.56      2419074.99     13535225.02
#Sta/Elev= 30
  4056.2  323.91  4145.3  315.22  4336.4  303.42  4382.7  300.88  4458.9  298.46
  4890.8  290.29  4925.8  289.87  4949.2  292.51  4978.2  290.49  4993.1  285.87
  4993.6  285.37  4998.9  285.87  5047.6  294.26  5110.6  294.45  5203.3  293.08
  5236.3  292.70  5345.0  292.23  5578.6  295.12  6099.9  294.71  6122.8  295.41
  6145.8  299.57  6174.2  297.44  6191.6  292.19  6197.1  294.17  6237.5  292.13
  6260.4  293.24  6294.4  298.59  6349.2  298.29  6566.7  307.48  6778.3  320.45
#Mann=14,-1,0
  4056.2    0.04       0  4336.4    0.05       0  4382.7    0.04       0
  4458.9    0.05       0  4890.8     0.1       0  4993.1    0.05       0
  4998.9     0.1       0  5047.6    0.12       0  5110.6     0.1       0
  5203.3    0.12       0  5236.3    0.05       0  5345.0    0.04       0
  6349.2    0.03       0  6566.7    0.04       0
Bank Sta=4993.1,4998.9
Exp/Cntr=0.3,0.1

Chan Stop Cuts=-1