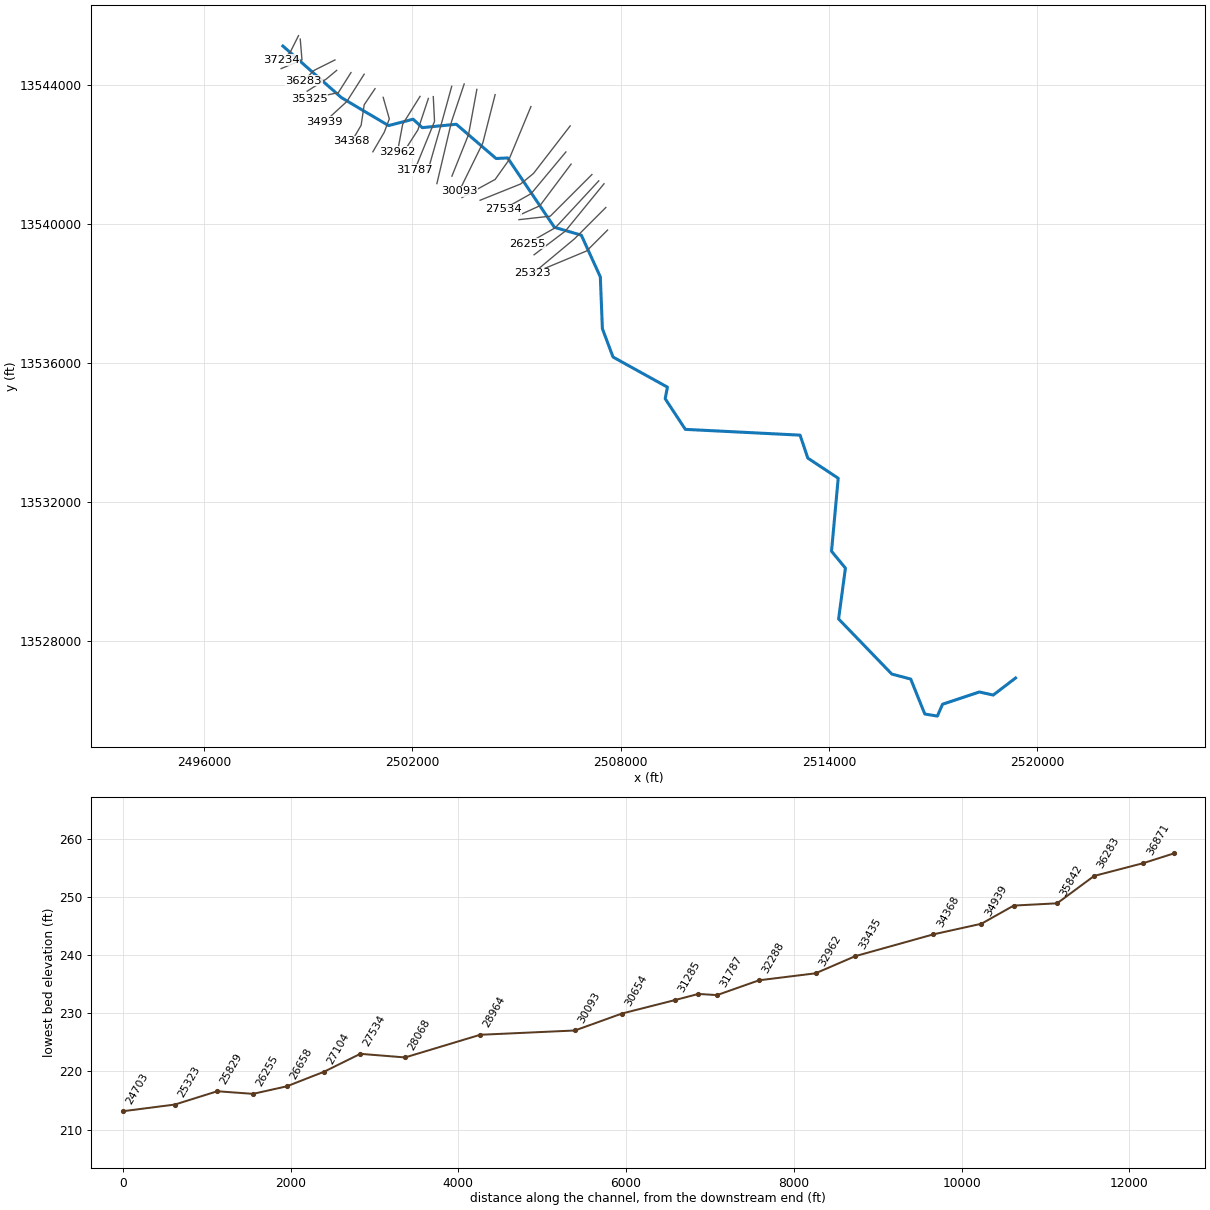
--- BOGGY BRANCH.prj (project) ---

Proj Title=BOGGY BRANCH Base Level Engineering
Current Plan=p01
Default Exp/Contr=0.3,0.1
English Units
Geom File=g01
Flow File=f01
Plan File=p01
Y Axis Title=Elevation
X Axis Title(PF)=Main Channel Distance
X Axis Title(XS)=Station
BEGIN DESCRIPTION:
BOGGY BRANCH
END DESCRIPTION:
DSS Export Rating Curves= 0
DSS Export Rating Curve Sorted= 0
DSS Export Volume Flow Curves= 0
DXF OffsetX= 0
DXF OffsetY= 0
DXF ScaleX= 1
DXF ScaleY= 10

--- BOGGY BRANCH.p01 (plan) ---

Plan Title=Multiple Run
Short Identifier=Multiple
Geom File=g01
Flow File=f01
Subcritical Flow
K Sum by GR= 0
Std Step Tol= 0.01
Critical Tol= 0.01
Num of Std Step Trials= 20
Max Error Tol= 0.3
Flow Tol Ratio= 0.001
Split Flow NTrial= 30
Split Flow Tol= 0.02
Split Flow Ratio= 0.02
Log Output Level= 0
Friction Slope Method= 1
Unsteady Friction Slope Method= 2
Unsteady Bridges Friction Slope Method= 1
Parabolic Critical Depth
Global Vel Dist=  1 , 1 , 1
Global Log Level= 0
CheckData=True
Encroach Param= -1, 0, 0, 0
BEGIN DESCRIPTION:
Multiple Run
END DESCRIPTION:

--- BOGGY BRANCH.f01 (steady flow) ---

Flow Title=Multiple
Number of Profiles=7
Profile Names=10-year,25-year,50-year,1pct_min,100-year,1pct_plu,500-year
River Rch & RM= BOGGY BRANCH,Reach-1,37234
     382     595     782     498     994    1983    1587
River Rch & RM= BOGGY BRANCH,Reach-1,36283
     672    1085    1460     951    1897    3785    3168
River Rch & RM= BOGGY BRANCH,Reach-1,34939
     781    1270    1716    1122    2238    4465    3766
River Rch & RM= BOGGY BRANCH,Reach-1,32962
     993    1636    2229    1467    2927    5841    5000
River Rch & RM= BOGGY BRANCH,Reach-1,30654
    1188    1974    2702    1787    3565    7113    6145
River Rch & RM= BOGGY BRANCH,Reach-1,28964
    1190    1971    2693    1776    3545    7072    6080
River Rch & RM= BOGGY BRANCH,Reach-1,25323
    1388    2317    3183    2110    4209    8399    7292
River Rch & RM= BOGGY BRANCH,Reach-1,24703
    1543    2586    3561    2366    4720    9418    8214
River Rch & RM= BOGGY BRANCH,Reach-1,20935
    2156    3659    5080    3398    6781   13530   11968
River Rch & RM= BOGGY BRANCH,Reach-1,15442
    2480    4216    5862    3925    7832   15626   13845
River Rch & RM= BOGGY BRANCH,Reach-1,10746
    2649    4513    6285    4214    8408   16776   14903
River Rch & RM= BOGGY BRANCH,Reach-1,9362
    2849    4865    6785    4555    9088   18133   16147
River Rch & RM= BOGGY BRANCH,Reach-1,5423
    2934    5009    6985    4688    9354   18664   16612
Boundary for River Rch & Prof#=BOGGY BRANCH,Reach-1,1
Up Type=0
Dn Type=3
Dn Slope=0.005
Boundary for River Rch & Prof#=BOGGY BRANCH,Reach-1,2
Up Type=0
Dn Type=3
Dn Slope=0.005
Boundary for River Rch & Prof#=BOGGY BRANCH,Reach-1,3
Up Type=0
Dn Type=3
Dn Slope=0.005
Boundary for River Rch & Prof#=BOGGY BRANCH,Reach-1,4
Up Type=0
Dn Type=3
Dn Slope=0.005
Boundary for River Rch & Prof#=BOGGY BRANCH,Reach-1,5
Up Type=0
Dn Type=3
Dn Slope=0.005
Boundary for River Rch & Prof#=BOGGY BRANCH,Reach-1,6
Up Type=0
Dn Type=3
Dn Slope=0.005
Boundary for River Rch & Prof#=BOGGY BRANCH,Reach-1,7
Up Type=0
Dn Type=3
Dn Slope=0.005

--- BOGGY BRANCH.g01 (geometry) ---

Geom Title=Existing Conditions

River Reach=BOGGY BRANCH,Reach-1
Reach XY= 30
      2498275.00     13545125.00      2499965.32     13543635.78
      2501318.26     13542834.13      2502024.79     13543018.02
      2502290.36     13542774.89      2503269.07     13542872.75
      2504414.63     13541885.81      2504748.36     13541902.54
      2506094.61     13539904.75      2506869.48     13539677.97
      2507416.96     13538478.32      2507476.20     13536985.50
      2507782.48     13536168.94      2509349.23     13535301.67
      2509284.39     13534968.39      2509865.32     13534085.76
      2513169.38     13533919.38      2513391.65     13533258.33
      2514267.41     13532678.35      2514075.00     13530575.00
      2514475.47     13530090.16      2514278.52     13528626.28
      2515811.35     13527038.19      2516355.73     13526895.07
      2516761.43     13525888.47      2517123.55     13525828.53
      2517272.53     13526169.55      2518330.97     13526522.86
      2518731.67     13526434.29      2519375.00     13526925.00

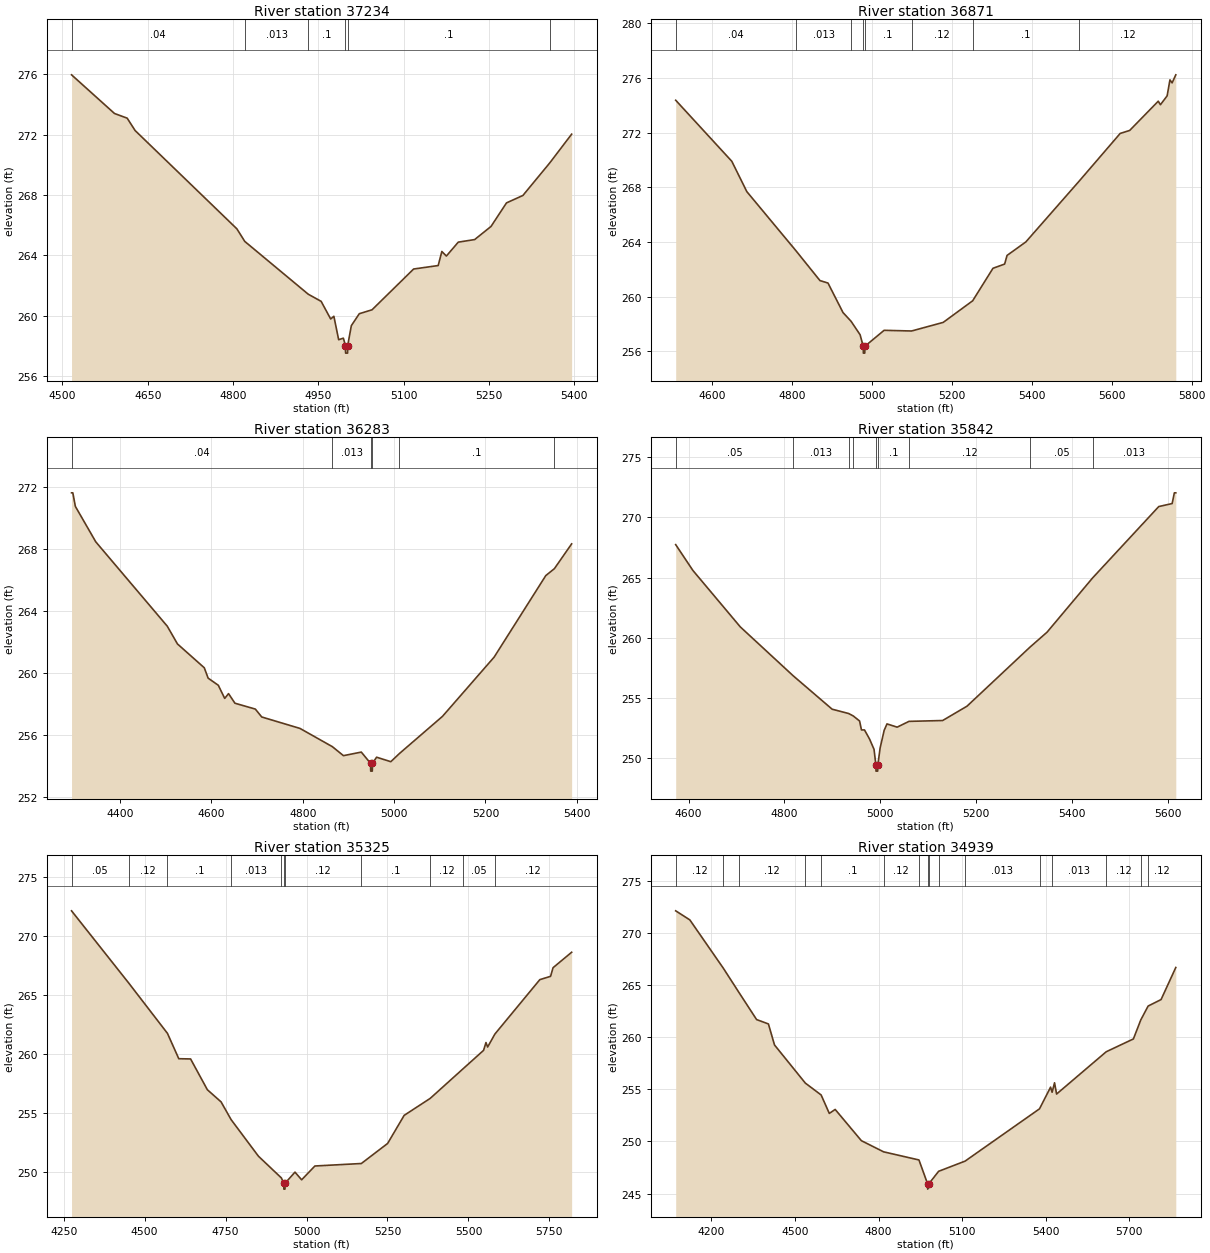
Type RM Length L Ch R = 1,37234,363,363,363
BEGIN DESCRIPTION:
BOGGY BRANCH 70.0
END DESCRIPTION:
XS GIS Cut Line= 3
      2498724.99     13545424.99      2498475.00     13544925.00
      2498224.97     13544724.97
#Sta/Elev= 30
  4516.0  275.96  4591.5  273.40  4613.8  273.09  4627.8  272.27  4806.7  265.76
  4820.5  264.93  4932.2  261.43  4954.8  260.96  4971.6  259.79  4977.2  259.97
  4985.6  258.42  4993.9  258.52  4997.5  258.03  4997.8  257.53  5001.3  257.53
  5001.5  258.03  5007.9  259.35  5021.9  260.14  5044.3  260.40  5117.4  263.10
  5160.6  263.33  5167.0  264.26  5175.0  263.96  5195.9  264.88  5224.7  265.05
  5253.5  265.92  5280.7  267.48  5309.5  267.97  5356.8  270.13  5395.2  272.03
#Mann=6,-1,0
  4516.0    0.04       0  4820.5   0.013       0  4932.2     0.1       0
  4997.5    0.05       0  5001.5     0.1       0  5356.8    0.12       0
Bank Sta=4997.5,5001.5
Exp/Cntr=0.3,0.1

Type RM Length L Ch R = 1,36871,588,588,588
BEGIN DESCRIPTION:
BOGGY BRANCH 69.0
END DESCRIPTION:
XS GIS Cut Line= 3
      2498775.00     13545325.00      2498825.00     13544725.00
      2498224.98     13544474.99
#Sta/Elev= 30
  4508.2  274.37  4648.7  269.90  4686.3  267.68  4809.4  263.35  4869.4  261.17
  4889.5  260.99  4927.1  258.83  4947.3  258.19  4969.8  257.21  4977.8  256.36
  4978.1  255.86  4981.6  255.86  4981.8  256.36  5030.0  257.53  5098.8  257.48
  5178.0  258.11  5251.7  259.69  5302.6  262.07  5331.8  262.38  5337.8  263.01
  5384.9  264.00  5518.4  268.45  5621.1  271.94  5644.9  272.16  5716.4  274.30
  5721.8  274.04  5738.6  274.69  5745.7  275.86  5751.1  275.64  5760.3  276.23
#Mann=8,-1,0
  4508.2    0.04       0  4809.4   0.013       0  4947.3     0.1       0
  4977.8    0.05       0  4981.8     0.1       0  5098.8    0.12       0
  5251.7     0.1       0  5518.4    0.12       0
Bank Sta=4977.8,4981.8
Exp/Cntr=0.3,0.1

Type RM Length L Ch R = 1,36283,441,441,441
BEGIN DESCRIPTION:
BOGGY BRANCH 68.0
END DESCRIPTION:
XS GIS Cut Line= 3
      2499775.01     13544725.01      2499175.00     13544425.00
      2498875.00     13544125.00
#Sta/Elev= 30
  4293.7  271.64  4296.5  271.64  4302.1  270.76  4346.8  268.47  4503.3  263.02
  4525.7  261.87  4584.4  260.33  4592.8  259.66  4615.1  259.20  4629.1  258.35
  4637.5  258.66  4651.5  258.04  4696.2  257.66  4710.2  257.15  4794.0  256.41
  4864.9  255.23  4889.1  254.65  4928.2  254.88  4948.6  254.15  4948.8  253.65
  4952.3  253.65  4952.6  254.15  4961.7  254.55  4992.8  254.26  5011.8  254.79
  5106.0  257.19  5219.1  261.02  5332.2  266.29  5351.1  266.74  5388.8  268.34
#Mann=6,-1,0
  4293.7    0.04       0  4864.9   0.013       0  4948.6    0.03       0
  4952.6   0.013       0  5011.8     0.1       0  5351.1    0.05       0
Bank Sta=4948.6,4952.6
Exp/Cntr=0.3,0.1

Type RM Length L Ch R = 1,35842,517,517,517
BEGIN DESCRIPTION:
BOGGY BRANCH 67.0
END DESCRIPTION:
XS GIS Cut Line= 3
      2499824.98     13544424.99      2499525.00     13544175.00
      2498975.01     13543825.01
#Sta/Elev= 30
  4573.3  267.74  4609.1  265.60  4708.0  260.91  4818.3  256.85  4899.4  254.08
  4933.9  253.72  4943.4  253.52  4956.6  253.10  4960.5  252.36  4966.8  252.36
  4977.3  251.61  4986.7  250.75  4990.6  249.44  4990.8  248.94  4994.3  248.94
  4994.6  249.44  4999.4  250.86  5007.8  252.32  5013.7  252.86  5034.9  252.59
  5059.6  253.07  5129.7  253.14  5180.5  254.33  5312.0  259.24  5347.3  260.47
  5442.4  264.98  5580.2  270.90  5608.1  271.15  5612.7  272.04  5615.7  272.04
#Mann=9,-1,0
  4573.3    0.05       0  4818.3   0.013       0  4933.9    0.12       0
  4943.4     0.1       0  4990.6    0.05       0  4994.6     0.1       0
  5059.6    0.12       0  5312.0    0.05       0  5442.4   0.013       0
Bank Sta=4990.6,4994.6
Exp/Cntr=0.3,0.1

Type RM Length L Ch R = 1,35325,386,386,386
BEGIN DESCRIPTION:
Mapping XS 279b6b01
END DESCRIPTION:
XS GIS Cut Line= 3
      2500236.09     13544361.13      2499871.49     13543782.97
      2499028.86     13543606.13
#Sta/Elev= 30
  4274.2  272.13  4451.7  265.98  4570.4  261.75  4605.4  259.60  4641.9  259.58
  4693.7  256.97  4736.1  255.94  4767.0  254.44  4851.4  251.34  4922.2  249.50
  4929.7  249.05  4929.9  248.55  4933.4  248.55  4933.7  249.05  4964.3  249.99
  4984.8  249.34  5025.8  250.51  5169.2  250.72  5250.4  252.42  5301.5  254.80
  5382.0  256.24  5481.9  258.71  5546.8  260.31  5554.1  260.97  5559.3  260.59
  5581.7  261.69  5720.5  266.30  5753.7  266.58  5761.3  267.31  5818.7  268.62
#Mann=11,-1,0
  4274.2    0.05       0  4451.7    0.12       0  4570.4     0.1       0
  4767.0   0.013       0  4922.2    0.12       0  4929.7    0.05       0
  4933.7    0.12       0  5169.2     0.1       0  5382.0    0.12       0
  5481.9    0.05       0  5581.7    0.12       0
Bank Sta=4929.7,4933.7
Exp/Cntr=0.3,0.1

Type RM Length L Ch R = 1,34939,571,571,571
BEGIN DESCRIPTION:
Mapping XS 0e686695
END DESCRIPTION:
XS GIS Cut Line= 3
      2500616.28     13544314.23      2500116.28     13543527.77
      2499480.87     13542944.44
#Sta/Elev= 30
  4072.2  272.14  4122.9  271.27  4243.1  266.63  4299.5  264.29  4362.5  261.70
  4404.9  261.28  4426.8  259.26  4537.4  255.60  4594.1  254.46  4623.4  252.69
  4644.5  253.07  4738.5  250.07  4818.3  249.00  4945.1  248.22  4976.2  245.92
  4976.4  245.42  4980.2  245.92  5015.6  247.13  5110.7  248.11  5377.7  253.13
  5417.4  255.21  5422.9  254.72  5431.6  255.63  5439.0  254.55  5617.1  258.61
  5714.6  259.84  5741.0  261.66  5767.5  263.00  5813.9  263.62  5866.7  266.70
#Mann=16,-1,0
  4072.2    0.12       0  4243.1    0.05       0  4299.5    0.12       0
  4537.4    0.04       0  4594.1     0.1       0  4818.3    0.12       0
  4945.1   0.013       0  4976.2    0.03       0  4980.2   0.013       0
  5015.6    0.12       0  5110.7   0.013       0  5377.7     0.1       0
  5422.9   0.013       0  5617.1    0.12       0  5741.0    0.05       0
  5767.5    0.12       0
Bank Sta=4976.2,4980.2
Exp/Cntr=0.3,0.1

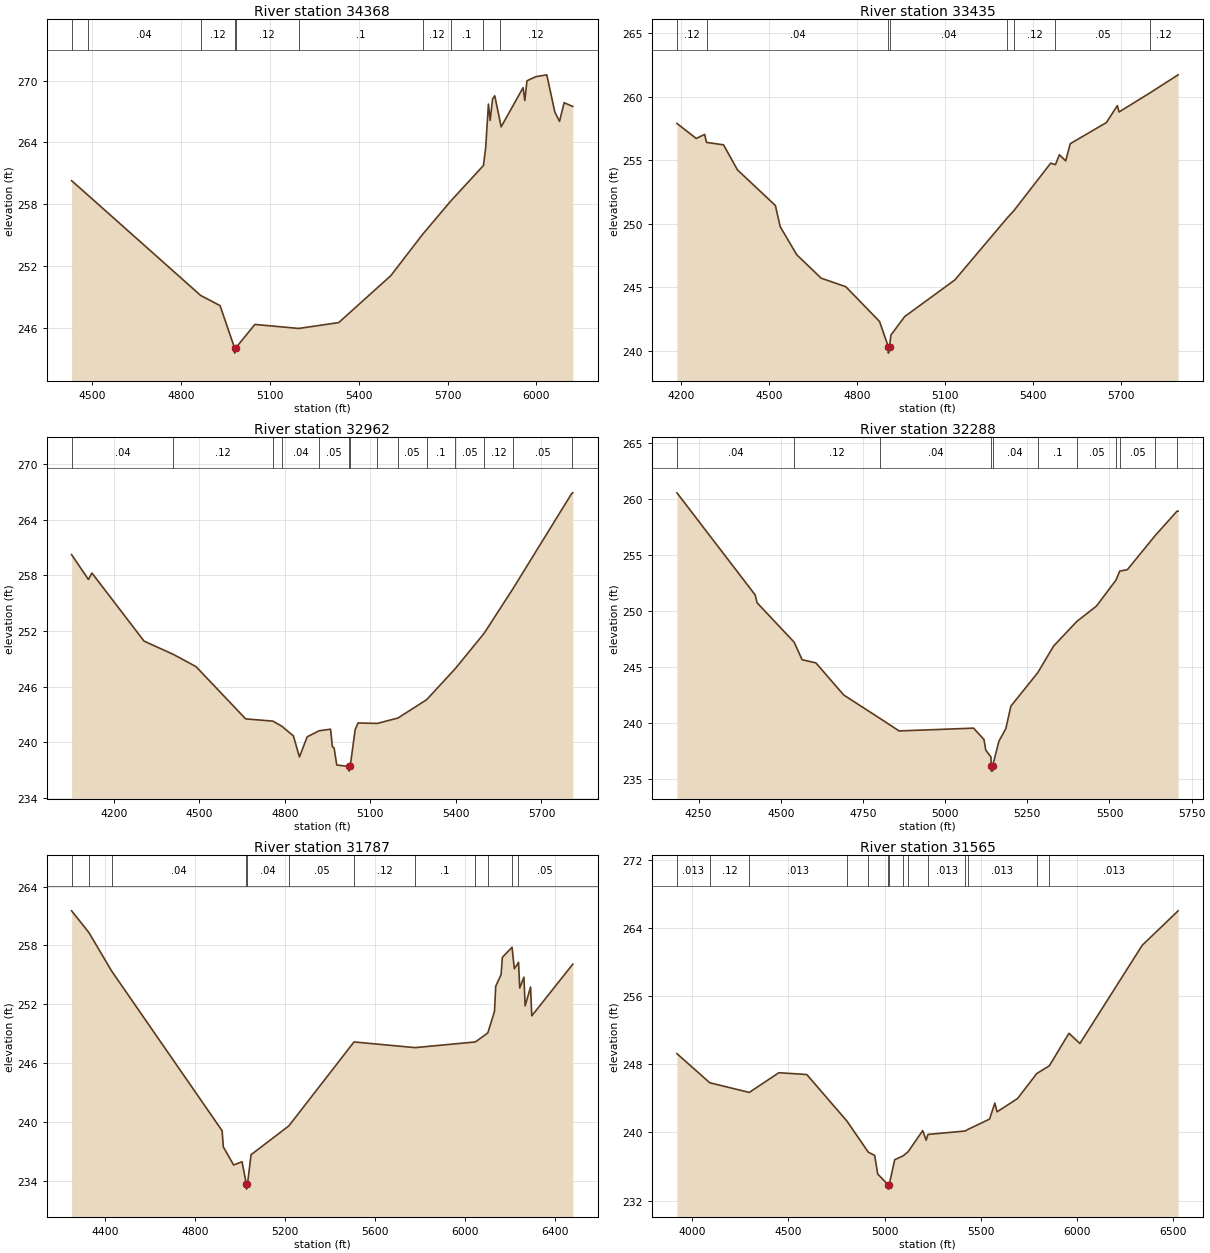
Type RM Length L Ch R = 1,34368,933,933,933
BEGIN DESCRIPTION:
Mapping XS fda747d5
END DESCRIPTION:
XS GIS Cut Line= 4
      2500928.75     13543897.52      2500616.28     13543434.02
      2500527.74     13542840.27      2500256.89     13542381.92
#Sta/Elev= 30
  4430.8  260.30  4485.2  258.92  4866.3  249.19  4931.9  248.20  4980.9  244.10
  4981.1  243.60  4984.9  244.10  5049.5  246.38  5197.5  245.99  5332.6  246.56
  5508.2  251.10  5616.7  255.14  5710.0  258.31  5821.0  261.77  5828.5  263.49
  5837.8  267.72  5843.6  266.14  5851.8  268.22  5859.2  268.52  5876.7  266.10
  5880.7  265.51  5954.8  269.31  5960.6  268.06  5967.9  269.97  5997.7  270.37
  6034.8  270.55  6062.0  266.94  6077.7  266.04  6093.3  267.85  6122.5  267.49
#Mann=10,-1,0
  4430.8    0.12       0  4485.2    0.04       0  4866.3    0.12       0
  4980.9    0.05       0  4984.9    0.12       0  5197.5     0.1       0
  5616.7    0.12       0  5710.0     0.1       0  5821.0    0.05       0
  5876.7    0.12       0
Bank Sta=4980.9,4984.9
Exp/Cntr=0.3,0.1

Type RM Length L Ch R = 1,33435,473,473,473
BEGIN DESCRIPTION:
Mapping XS 29cbf18a
END DESCRIPTION:
XS GIS Cut Line= 4
      2501163.15     13543647.58      2501340.24     13543027.77
      2501194.40     13542642.35      2500866.33     13542079.94
#Sta/Elev= 30
  4185.8  257.89  4251.6  256.71  4280.2  257.03  4286.5  256.40  4344.5  256.21
  4392.0  254.24  4521.3  251.44  4537.6  249.78  4594.1  247.57  4677.3  245.73
  4761.2  245.06  4876.1  242.33  4906.2  240.34  4906.4  239.84  4910.3  240.34
  4914.7  241.25  4961.7  242.71  5132.7  245.59  5311.8  250.48  5333.4  251.02
  5459.4  254.77  5475.6  254.65  5488.9  255.43  5510.4  254.95  5526.1  256.30
  5649.3  257.96  5686.5  259.29  5692.3  258.79  5797.5  260.29  5893.6  261.71
#Mann=8,-1,0
  4185.8    0.12       0  4286.5    0.04       0  4906.2    0.04       0
  4910.3    0.04       0  5311.8    0.05       0  5333.4    0.12       0
  5475.6    0.05       0  5797.5    0.12       0
Bank Sta=4906.2,4910.3
Exp/Cntr=0.3,0.1

Type RM Length L Ch R = 1,32962,674,674,674
BEGIN DESCRIPTION:
BOGGY BRANCH 61.0
END DESCRIPTION:
XS GIS Cut Line= 3
      2502225.00     13543674.99      2501725.00     13542875.00
      2501575.01     13542075.03
#Sta/Elev= 30
  4052.4  260.22  4111.4  257.54  4123.7  258.24  4306.5  250.90  4409.2  249.47
  4488.7  248.15  4662.7  242.52  4758.1  242.28  4789.0  241.74  4830.1  240.69
  4851.3  238.42  4878.5  240.59  4920.3  241.24  4960.4  241.41  4966.9  239.51
  4972.8  239.40  4982.2  237.55  5025.1  237.39  5025.4  236.89  5029.2  237.39
  5046.7  241.37  5056.8  242.08  5124.2  242.03  5196.6  242.61  5297.4  244.59
  5398.2  247.95  5499.0  251.75  5599.8  256.54  5806.0  266.81  5809.7  266.88
#Mann=14,-1,0
  4052.4    0.04       0  4409.2    0.12       0  4758.1    0.05       0
  4789.0    0.04       0  4920.3    0.05       0  5025.1    0.05       0
  5029.2    0.05       0  5124.2    0.04       0  5196.6    0.05       0
  5297.4     0.1       0  5398.2    0.05       0  5499.0    0.12       0
  5599.8    0.05       0  5806.0    0.12       0
Bank Sta=5025.1,5029.2
Exp/Cntr=0.3,0.1

Type RM Length L Ch R = 1,32288,501,501,501
BEGIN DESCRIPTION:
Mapping XS 0302ef11
END DESCRIPTION:
XS GIS Cut Line= 3
      2502465.23     13543616.28      2502163.15     13542710.06
      2501855.85     13542230.87
#Sta/Elev= 30
  4184.4  260.55  4422.6  251.42  4428.2  250.73  4540.9  247.21  4565.2  245.64
  4607.1  245.36  4691.7  242.49  4802.5  240.39  4860.1  239.28  5086.7  239.53
  5118.3  238.52  5123.9  237.56  5139.6  236.95  5140.2  236.19  5140.5  235.69
  5144.6  235.69  5144.9  236.19  5163.7  238.36  5184.9  239.49  5200.1  241.49
  5281.8  244.48  5330.3  246.87  5401.1  249.07  5460.4  250.43  5520.3  252.77
  5531.1  253.56  5554.3  253.68  5639.6  256.75  5705.5  258.91  5708.9  258.91
#Mann=11,-1,0
  4184.4    0.04       0  4540.9    0.12       0  4802.5    0.04       0
  5140.2    0.04       0  5144.9    0.04       0  5281.8     0.1       0
  5401.1    0.05       0  5520.3    0.12       0  5531.1    0.05       0
  5639.6    0.12       0  5705.5    0.05       0
Bank Sta=5140.2,5144.9
Exp/Cntr=0.3,0.1

Type RM Length L Ch R = 1,31787,222,222,222
BEGIN DESCRIPTION:
Mapping XS dd09c8f8
END DESCRIPTION:
XS GIS Cut Line= 3
      2502605.86     13543668.36      2502642.32     13542954.85
      2502069.70     13541554.55
#Sta/Elev= 30
  4250.1  261.52  4326.9  259.31  4427.8  255.39  4919.2  239.09  4924.3  237.45
  4970.2  235.60  5007.6  235.93  5026.8  233.64  5027.2  233.14  5031.6  233.64
  5047.7  236.65  5215.6  239.59  5505.2  248.15  5776.7  247.57  6044.5  248.15
  6099.9  249.07  6129.5  251.27  6134.9  253.82  6158.9  255.02  6164.3  256.77
  6207.6  257.81  6217.7  255.61  6231.8  256.09  6236.3  256.27  6241.7  253.65
  6260.3  254.76  6265.7  251.83  6289.8  253.75  6295.2  250.81  6477.4  256.08
#Mann=12,-1,0
  4250.1    0.12       0  4326.9   0.013       0  4427.8    0.04       0
  5026.8    0.04       0  5031.6    0.04       0  5215.6    0.05       0
  5505.2    0.12       0  5776.7     0.1       0  6044.5    0.12       0
  6099.9   0.013       0  6207.6    0.12       0  6231.8    0.05       0
Bank Sta=5026.8,5031.6
Exp/Cntr=0.3,0.1

Type RM Length L Ch R = 1,31565,280,280,280
BEGIN DESCRIPTION:
Mapping XS 192fc5ad
END DESCRIPTION:
XS GIS Cut Line= 3
      2503137.11     13543965.28      2502855.86     13542944.43
      2502428.77     13541460.03
#Sta/Elev= 30
  3920.9  249.24  4091.6  245.82  4296.7  244.69  4450.2  247.00  4595.4  246.79
  4804.2  241.32  4914.9  237.68  4948.1  237.29  4963.9  235.11  5018.3  233.84
  5018.7  233.34  5023.3  233.84  5052.0  236.79  5094.8  237.23  5121.5  237.72
  5197.7  240.21  5215.6  239.08  5224.9  239.76  5418.6  240.16  5431.8  240.34
  5544.9  241.56  5572.3  243.44  5583.8  242.41  5690.1  243.97  5790.3  246.91
  5855.2  247.81  5957.3  251.63  6014.1  250.43  6338.1  261.96  6524.4  266.00
#Mann=14,-1,0
  3920.9   0.013       0  4091.6    0.12       0  4296.7   0.013       0
  4804.2    0.04       0  4914.9   0.013       0  5018.3    0.03       0
  5023.3   0.013       0  5094.8    0.05       0  5121.5    0.04       0
  5224.9   0.013       0  5418.6    0.04       0  5431.8   0.013       0
  5790.3    0.12       0  5855.2   0.013       0
Bank Sta=5018.3,5023.3
Exp/Cntr=0.3,0.1

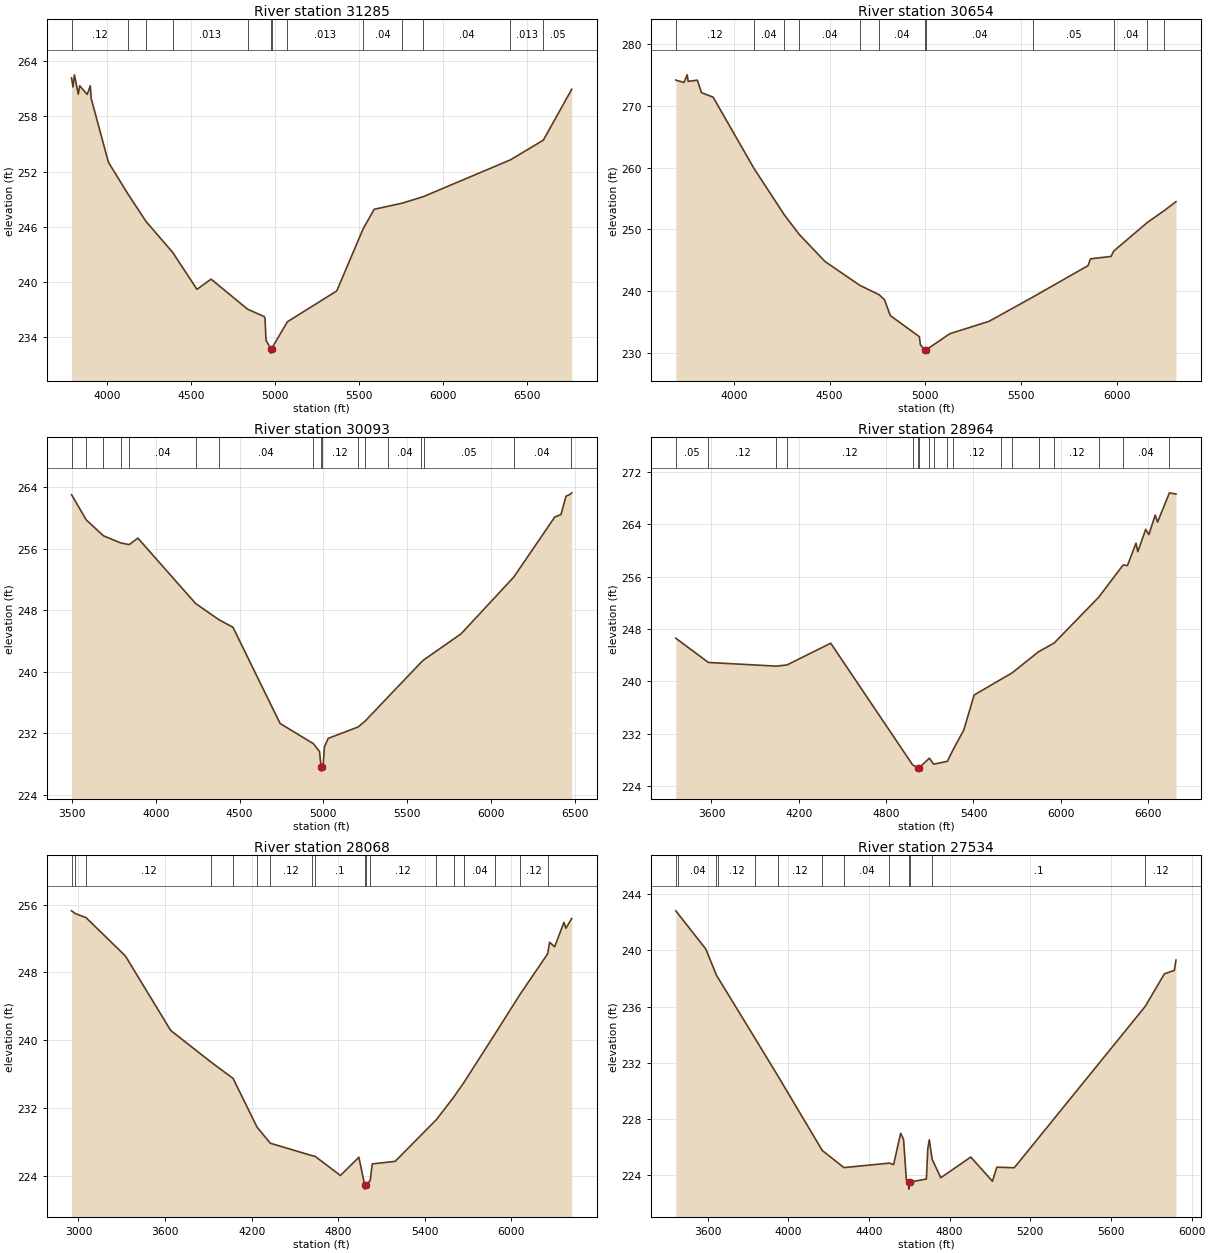
Type RM Length L Ch R = 1,31285,631,631,631
BEGIN DESCRIPTION:
Mapping XS 200ed532
END DESCRIPTION:
XS GIS Cut Line= 3
      2503496.50     13544033.02      2503131.90     13542949.64
      2502710.02     13541163.16
#Sta/Elev= 30
  3790.4  262.19  3798.9  261.20  3807.5  262.52  3830.5  260.41  3839.0  261.33
  3883.3  260.39  3902.0  261.33  3907.2  259.96  4009.9  253.03  4126.7  249.56
  4234.6  246.57  4393.0  243.22  4537.4  239.21  4621.3  240.32  4838.5  237.06
  4937.6  236.25  4942.6  236.07  4948.5  233.67  4976.8  232.78  4977.2  232.28
  4981.9  232.78  5076.1  235.69  5369.8  239.04  5526.7  245.78  5592.6  247.91
  5760.3  248.58  5886.3  249.29  6403.9  253.28  6600.0  255.42  6769.1  260.95
#Mann=13,-1,0
  3790.4    0.12       0  4126.7   0.013       0  4234.6    0.12       0
  4393.0   0.013       0  4838.5    0.04       0  4976.8    0.04       0
  4981.9    0.04       0  5076.1   0.013       0  5526.7    0.04       0
  5760.3   0.013       0  5886.3    0.04       0  6403.9   0.013       0
  6600.0    0.05       0
Bank Sta=4976.8,4981.9
Exp/Cntr=0.3,0.1

Type RM Length L Ch R = 1,30654,561,561,561
BEGIN DESCRIPTION:
Mapping XS 3b3a6222
END DESCRIPTION:
XS GIS Cut Line= 3
      2503861.08     13543876.77      2503621.49     13542574.64
      2503142.98     13541378.38
#Sta/Elev= 30
  3696.3  274.20  3738.8  273.81  3755.8  275.05  3760.9  273.99  3808.8  274.19
  3830.3  272.17  3891.3  271.43  4104.5  259.90  4262.7  252.39  4341.8  249.17
  4475.9  244.81  4657.5  240.95  4758.3  239.43  4786.1  238.64  4816.6  236.06
  4968.6  232.63  4973.7  231.32  4996.9  230.47  4997.3  229.97  5002.3  230.47
  5127.1  233.11  5332.2  235.12  5562.8  239.08  5849.2  244.14  5862.2  245.24
  5969.9  245.64  5983.9  246.51  6159.4  251.14  6244.3  252.99  6308.7  254.50
#Mann=12,-1,0
  3696.3    0.12       0  4104.5    0.04       0  4262.7    0.12       0
  4341.8    0.04       0  4657.5   0.013       0  4758.3    0.04       0
  4996.9    0.04       0  5002.3    0.04       0  5562.8    0.05       0
  5983.9    0.04       0  6159.4    0.05       0  6244.3    0.12       0
Bank Sta=4996.9,5002.3
Exp/Cntr=0.3,0.1

Type RM Length L Ch R = 1,30093,1129,1129,1129
BEGIN DESCRIPTION:
Mapping XS e73a77e5
END DESCRIPTION:
XS GIS Cut Line= 3
      2504387.11     13543725.66      2504032.94     13542335.06
      2503350.64     13540944.41
#Sta/Elev= 30
  3497.8  263.01  3585.6  259.73  3688.0  257.66  3790.5  256.74  3841.2  256.51
  3893.5  257.36  4237.7  248.86  4376.8  246.75  4460.9  245.76  4742.0  233.25
  4940.7  230.62  4977.4  229.59  4986.8  227.55  4987.2  227.05  4992.3  227.55
  4999.7  228.10  5006.4  230.20  5028.9  231.31  5207.3  232.79  5250.2  233.58
  5386.7  236.71  5584.2  241.22  5597.8  241.50  5821.6  244.91  6135.6  252.28
  6380.9  260.11  6417.5  260.42  6447.7  262.81  6474.9  263.09  6481.8  263.25
#Mann=17,-1,0
  3497.8    0.12       0  3585.6    0.05       0  3688.0    0.12       0
  3790.5    0.05       0  3841.2    0.04       0  4237.7    0.05       0
  4376.8    0.04       0  4940.7    0.12       0  4986.8    0.05       0
  4992.3    0.12       0  5207.3    0.04       0  5250.2    0.12       0
  5386.7    0.04       0  5584.2    0.12       0  5597.8    0.05       0
  6135.6    0.04       0  6474.9    0.05       0
Bank Sta=4986.8,4992.3
Exp/Cntr=0.3,0.1

Type RM Length L Ch R = 1,28964,896,896,896
BEGIN DESCRIPTION:
Mapping XS 217835e3
END DESCRIPTION:
XS GIS Cut Line= 4
      2505418.35     13543381.90      2504772.53     13541824.64
      2504387.11     13541282.97      2503433.99     13540762.14
#Sta/Elev= 30
  3354.8  246.60  3578.6  242.90  4046.3  242.34  4118.5  242.52  4419.3  245.84
  4982.4  227.26  5019.5  226.81  5020.0  226.31  5025.6  226.81  5097.5  228.29
  5126.2  227.37  5220.9  227.81  5258.6  229.51  5333.4  232.58  5404.8  237.93
  5591.3  240.35  5664.7  241.30  5847.4  244.53  5955.2  245.88  6260.0  252.85
  6428.3  257.78  6458.3  257.70  6516.9  261.11  6529.5  259.81  6583.6  263.22
  6605.4  262.42  6649.0  265.40  6665.1  264.33  6746.6  268.80  6791.6  268.61
#Mann=18,-1,0
  3354.8    0.05       0  3578.6    0.12       0  4046.3    0.05       0
  4118.5    0.12       0  4982.4    0.05       0  5019.5    0.05       0
  5025.6    0.05       0  5097.5     0.1       0  5126.2    0.05       0
  5220.9     0.1       0  5258.6    0.12       0  5591.3    0.05       0
  5664.7    0.12       0  5847.4    0.05       0  5955.2    0.12       0
  6260.0    0.05       0  6428.3    0.04       0  6746.6    0.05       0
Bank Sta=5019.5,5025.6
Exp/Cntr=0.3,0.1

Type RM Length L Ch R = 1,28068,534,534,534
BEGIN DESCRIPTION:
Mapping XS 338e25aa
END DESCRIPTION:
XS GIS Cut Line= 4
      2506548.55     13542824.61      2505491.28     13541454.85
      2505121.49     13541152.77      2503954.86     13540684.03
#Sta/Elev= 30
  2952.3  255.28  2979.4  254.95  3053.1  254.47  3325.4  249.95  3638.8  241.16
  3918.8  237.41  4071.3  235.49  4237.4  229.73  4329.8  227.83  4619.3  226.36
  4640.3  226.28  4815.1  224.02  4942.9  226.18  4982.9  222.91  4983.4  222.41
  4989.1  222.91  5021.2  223.40  5035.5  225.39  5194.2  225.69  5479.8  230.62
  5599.2  233.26  5671.5  235.03  5883.6  240.68  6058.6  245.39  6250.9  250.21
  6264.1  251.57  6299.1  251.03  6363.4  253.92  6377.1  253.22  6417.4  254.37
#Mann=18,-1,0
  2952.3    0.12       0  2979.4    0.05       0  3053.1    0.12       0
  3918.8    0.05       0  4071.3    0.12       0  4237.4    0.04       0
  4329.8    0.12       0  4619.3    0.05       0  4640.3     0.1       0
  4982.9    0.05       0  4989.1     0.1       0  5021.2    0.12       0
  5479.8    0.04       0  5599.2    0.05       0  5671.5    0.04       0
  5883.6    0.05       0  6058.6    0.12       0  6250.9    0.05       0
Bank Sta=4982.9,4989.1
Exp/Cntr=0.3,0.1

Type RM Length L Ch R = 1,27534,430,430,430
BEGIN DESCRIPTION:
BOGGY BRANCH 50.0
END DESCRIPTION:
XS GIS Cut Line= 3
      2506424.97     13542074.96      2505425.00     13540875.00
      2504624.98     13540424.99
#Sta/Elev= 30
  3442.4  242.81  3455.0  242.58  3591.4  240.09  3643.9  238.23  3650.5  238.08
  3836.9  233.71  3947.6  231.10  4168.5  225.78  4275.9  224.56  4501.5  224.88
  4522.1  224.77  4557.3  227.00  4571.6  226.57  4585.9  223.66  4597.1  223.53
  4597.6  223.03  4603.4  223.53  4684.8  223.75  4692.0  225.94  4699.2  226.54
  4713.3  225.15  4756.4  223.84  4904.8  225.31  5012.4  223.59  5034.0  224.59
  5120.7  224.55  5769.3  236.01  5864.9  238.33  5914.3  238.58  5922.3  239.31
#Mann=13,-1,0
  3442.4    0.12       0  3455.0    0.04       0  3643.9    0.05       0
  3650.5    0.12       0  3836.9    0.05       0  3947.6    0.12       0
  4168.5    0.05       0  4275.9    0.04       0  4501.5    0.05       0
  4597.1    0.05       0  4603.4    0.05       0  4713.3     0.1       0
  5769.3    0.12       0
Bank Sta=4597.1,4603.4
Exp/Cntr=0.3,0.1

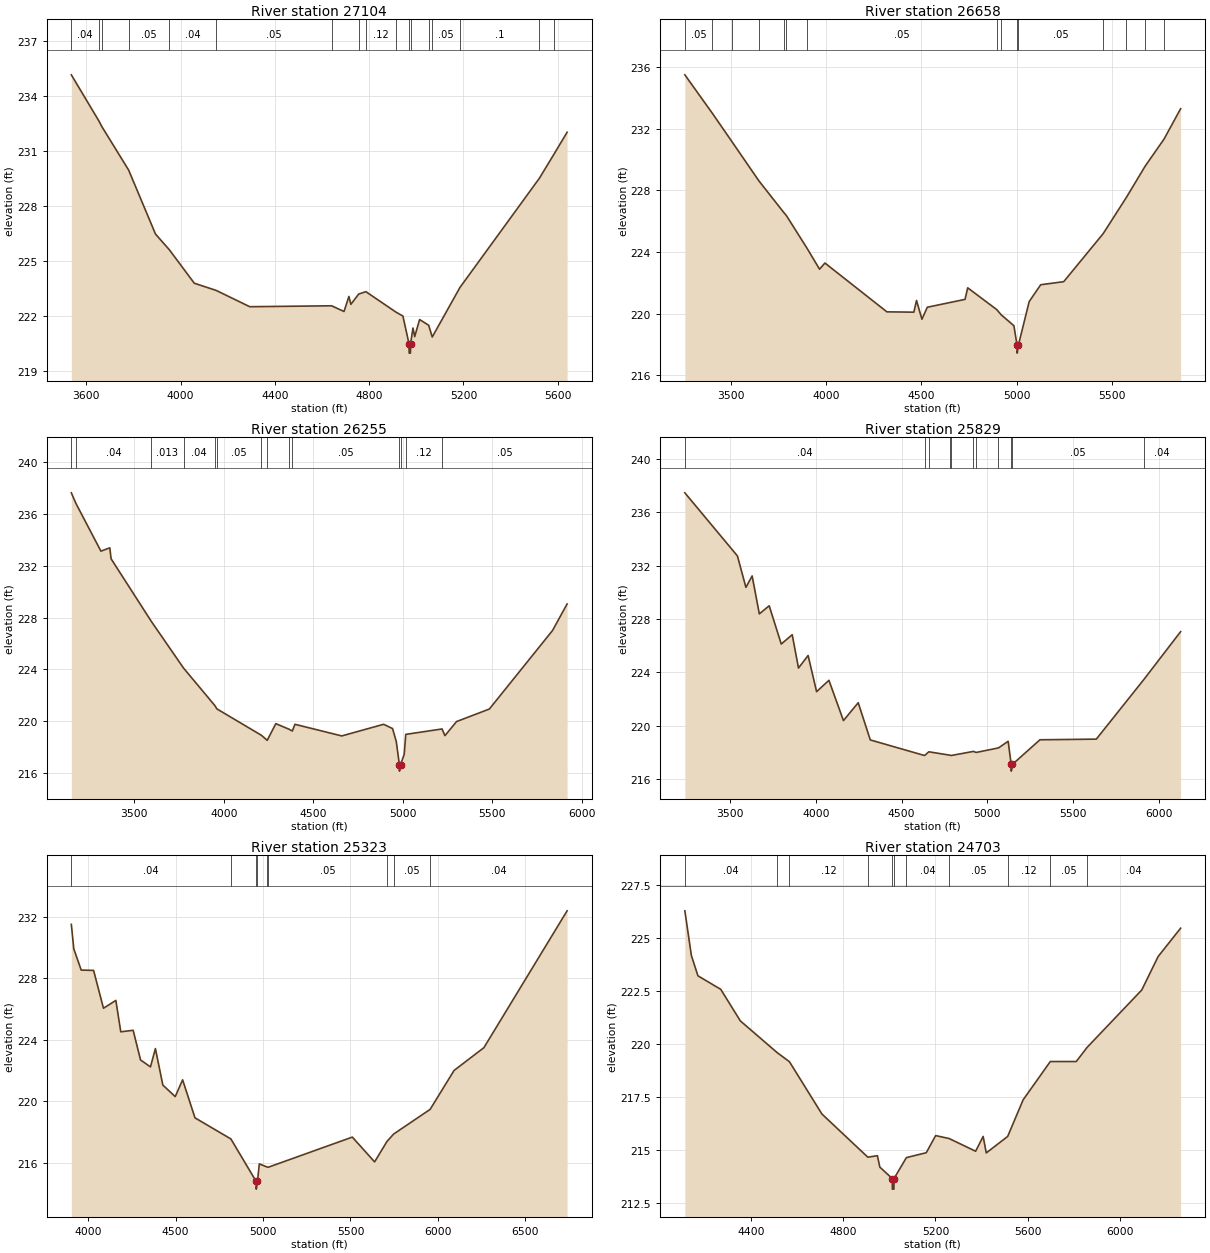
Type RM Length L Ch R = 1,27104,446,446,446
BEGIN DESCRIPTION:
BOGGY BRANCH 49.0
END DESCRIPTION:
XS GIS Cut Line= 3
      2506574.99     13541724.99      2505675.00     13540525.00
      2505125.04     13540275.02
#Sta/Elev= 30
  3536.1  235.13  3653.4  232.61  3666.5  232.29  3779.3  229.94  3893.4  226.45
  3952.4  225.59  4058.0  223.77  4150.6  223.38  4293.4  222.49  4640.9  222.54
  4693.4  222.23  4714.2  223.05  4722.5  222.62  4755.7  223.18  4786.3  223.31
  4912.2  222.21  4943.4  221.98  4969.4  220.46  4969.9  219.96  4975.2  219.96
  4975.7  220.46  4986.1  221.33  4993.4  220.86  5014.2  221.79  5052.6  221.48
  5067.9  220.84  5185.5  223.54  5523.0  229.50  5584.8  230.81  5640.2  232.00
#Mann=17,-1,0
  3536.1    0.04       0  3653.4    0.05       0  3666.5    0.12       0
  3779.3    0.05       0  3952.4    0.04       0  4150.6    0.05       0
  4640.9    0.12       0  4755.7    0.05       0  4786.3    0.12       0
  4912.2    0.05       0  4969.4    0.05       0  4975.7    0.05       0
  5052.6    0.12       0  5067.9    0.05       0  5185.5     0.1       0
  5523.0    0.05       0  5584.8     0.1       0
Bank Sta=4969.4,4975.7
Exp/Cntr=0.3,0.1

Type RM Length L Ch R = 1,26658,403,403,403
BEGIN DESCRIPTION:
BOGGY BRANCH 48.0
END DESCRIPTION:
XS GIS Cut Line= 3
      2507175.01     13541425.01      2505975.00     13540225.00
      2505075.01     13540125.00
#Sta/Elev= 30
  3257.9  235.51  3403.0  233.00  3506.9  231.14  3647.5  228.61  3777.4  226.57
  3791.0  226.37  3899.8  224.24  3965.0  222.89  3993.3  223.29  4318.6  220.12
  4460.0  220.10  4474.1  220.86  4502.4  219.64  4530.7  220.42  4728.7  220.93
  4742.8  221.68  4894.8  220.27  4919.3  219.92  4985.2  219.22  5002.1  217.94
  5002.6  217.44  5008.5  217.94  5065.6  220.79  5126.0  221.88  5246.8  222.08
  5454.0  225.20  5575.7  227.55  5674.3  229.58  5773.0  231.33  5860.5  233.31
#Mann=15,-1,0
  3257.9    0.05       0  3403.0    0.04       0  3506.9    0.12       0
  3647.5    0.04       0  3777.4    0.12       0  3791.0    0.04       0
  3899.8    0.05       0  4894.8    0.12       0  4919.3    0.05       0
  5002.1    0.05       0  5008.5    0.05       0  5454.0     0.1       0
  5575.7    0.05       0  5674.3    0.12       0  5773.0    0.05       0
Bank Sta=5002.1,5008.5
Exp/Cntr=0.3,0.1

Type RM Length L Ch R = 1,26255,426,426,426
BEGIN DESCRIPTION:
Mapping XS 93d6b1fb
END DESCRIPTION:
XS GIS Cut Line= 3
      2507371.59     13541242.11      2506121.59     13539893.15
      2505314.30     13539434.82
#Sta/Elev= 30
  3149.5  237.65  3175.6  236.82  3314.8  233.14  3364.2  233.40  3371.5  232.55
  3595.7  227.72  3776.2  224.10  3950.5  221.21  3962.1  220.95  4210.6  218.91
  4242.9  218.52  4291.1  219.81  4364.5  219.38  4383.3  219.24  4397.7  219.76
  4659.1  218.86  4892.7  219.76  4942.6  219.43  4963.5  218.42  4980.7  216.64
  4981.2  216.14  4987.2  216.64  5007.7  217.44  5016.4  218.98  5219.0  219.40
  5234.9  218.88  5299.8  219.97  5483.0  220.94  5835.6  227.01  5916.9  229.06
#Mann=14,-1,0
  3149.5    0.05       0  3175.6    0.04       0  3595.7   0.013       0
  3776.2    0.04       0  3950.5   0.013       0  3962.1    0.05       0
  4210.6   0.013       0  4242.9    0.05       0  4364.5    0.04       0
  4383.3    0.05       0  4980.7    0.05       0  4987.2    0.05       0
  5016.4    0.12       0  5219.0    0.05       0
Bank Sta=4980.7,4987.2
Exp/Cntr=0.3,0.1

Type RM Length L Ch R = 1,25829,506,506,506
BEGIN DESCRIPTION:
Mapping XS ccff85c2
END DESCRIPTION:
XS GIS Cut Line= 3
      2507522.66     13541158.81      2506408.05     13539794.19
      2505508.51     13539113.04
#Sta/Elev= 30
  3236.3  237.46  3542.7  232.73  3592.3  230.37  3628.6  231.23  3670.5  228.38
  3728.0  228.99  3798.3  226.12  3862.2  226.82  3898.8  224.32  3954.8  225.26
  4004.4  222.55  4076.2  223.40  4160.9  220.38  4247.0  221.72  4317.4  218.93
  4633.7  217.76  4658.4  218.04  4784.0  217.78  4788.7  217.76  4919.0  218.07
  4934.2  217.99  5064.7  218.33  5121.2  218.83  5138.8  217.09  5139.3  216.59
  5145.3  217.09  5306.4  218.94  5635.1  218.99  5912.8  223.47  6126.6  227.05
#Mann=11,-1,0
  3236.3    0.04       0  4633.7    0.05       0  4658.4    0.04       0
  4784.0   0.013       0  4788.7    0.04       0  4919.0    0.05       0
  4934.2    0.04       0  5064.7    0.05       0  5138.8    0.04       0
  5145.3    0.05       0  5912.8    0.04       0
Bank Sta=5138.8,5145.3
Exp/Cntr=0.3,0.1

Type RM Length L Ch R = 1,25323,620,620,620
BEGIN DESCRIPTION:
BOGGY BRANCH 46.0
END DESCRIPTION:
XS GIS Cut Line= 3
      2507575.00     13540475.00      2506675.00     13539575.00
      2505475.03     13538575.02
#Sta/Elev= 30
  3904.0  231.50  3918.1  229.91  3960.6  228.53  4031.3  228.51  4087.8  226.05
  4158.6  226.56  4186.8  224.52  4257.5  224.62  4300.0  222.69  4356.5  222.24
  4384.8  223.43  4427.3  221.06  4498.0  220.31  4540.4  221.40  4611.1  218.93
  4816.4  217.56  4960.9  214.80  4961.4  214.30  4968.4  214.80  4978.8  215.94
  5020.5  215.75  5029.6  215.72  5510.7  217.68  5638.2  216.07  5709.0  217.40
  5747.1  217.88  5955.6  219.48  6092.5  222.01  6263.1  223.49  6738.8  232.38
#Mann=9,-1,0
  3904.0    0.04       0  4816.4    0.05       0  4960.9    0.05       0
  4968.4    0.05       0  5020.5    0.04       0  5029.6    0.05       0
  5709.0    0.12       0  5747.1    0.05       0  5955.6    0.04       0
Bank Sta=4960.9,4968.4
Exp/Cntr=0.3,0.1

Type RM Length L Ch R = 1,24703,450,450,450
BEGIN DESCRIPTION:
BOGGY BRANCH 45.0
END DESCRIPTION:
XS GIS Cut Line= 3
      2507625.00     13539825.00      2507025.00     13539225.00
      2505825.02     13538725.01
#Sta/Elev= 30
  4113.8  226.30  4142.1  224.19  4170.4  223.23  4269.4  222.59  4354.2  221.10
  4513.9  219.60  4567.1  219.17  4707.8  216.70  4906.7  214.66  4948.2  214.73
  4958.8  214.19  5012.6  213.65  5013.1  213.15  5019.8  213.15  5020.3  213.65
  5073.9  214.64  5160.0  214.87  5200.7  215.68  5259.2  215.54  5374.0  214.94
  5406.5  215.64  5420.0  214.86  5512.8  215.64  5579.8  217.37  5697.6  219.18
  5810.0  219.18  5857.2  219.85  6093.9  222.56  6164.8  224.14  6262.3  225.48
#Mann=11,-1,0
  4113.8    0.04       0  4513.9    0.05       0  4567.1    0.12       0
  4906.7    0.05       0  5012.6    0.05       0  5020.3    0.05       0
  5073.9    0.04       0  5259.2    0.05       0  5512.8    0.12       0
  5697.6    0.05       0  5857.2    0.04       0
Bank Sta=5012.6,5020.3
Exp/Cntr=0.3,0.1