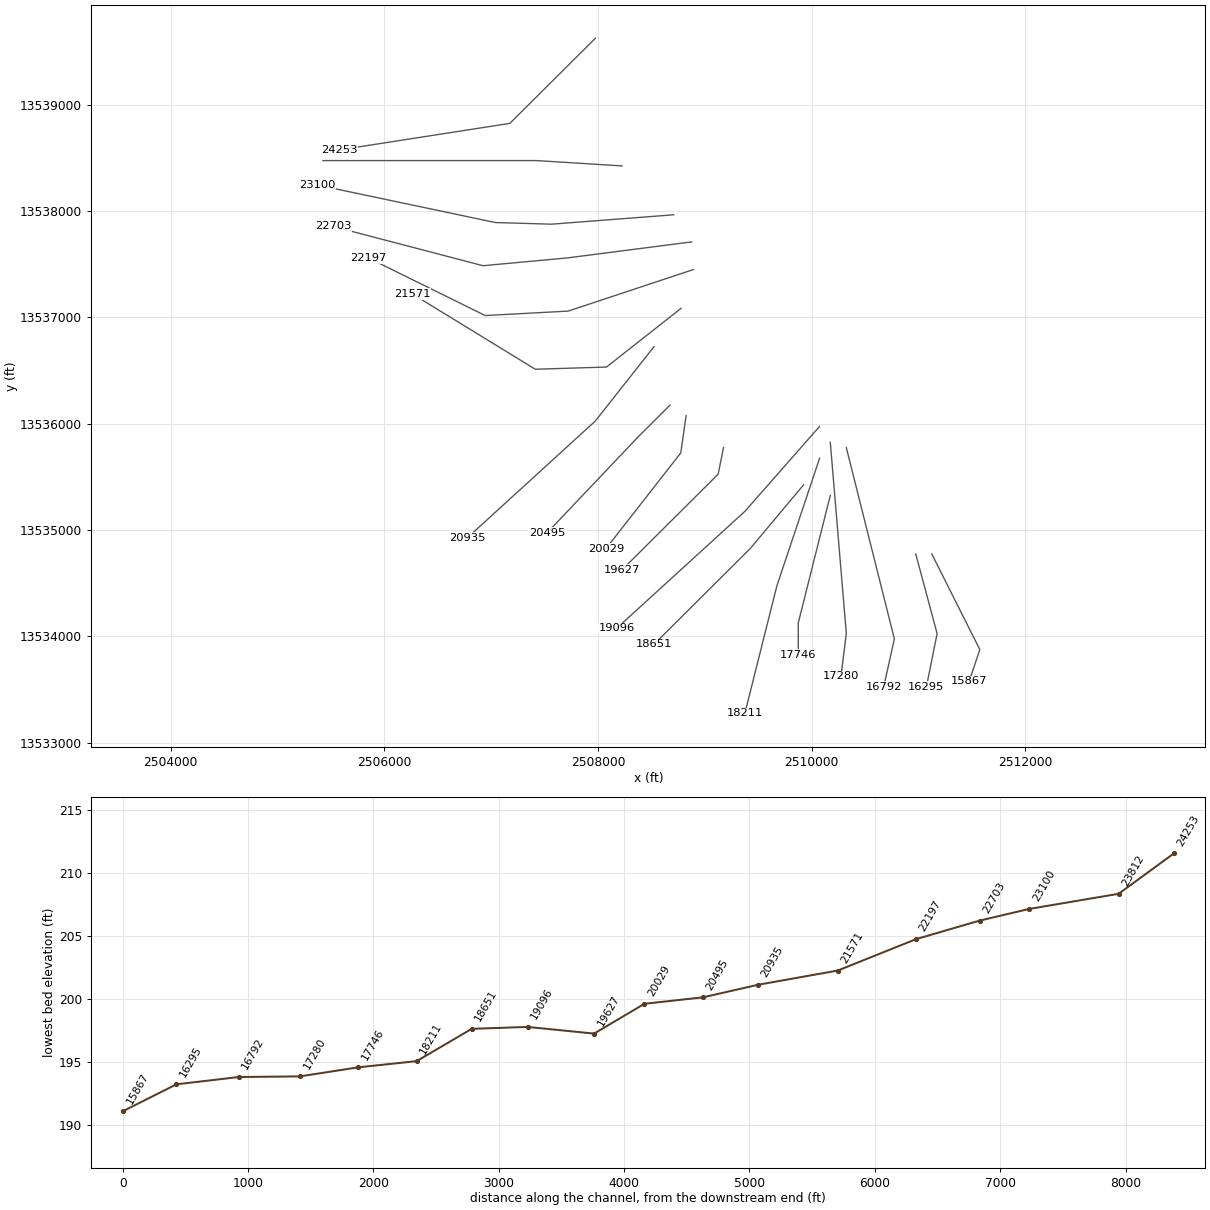
HEC-RAS study BOGGY BRANCH.prj: BOGGY BRANCH Base Level Engineering

--- BOGGY BRANCH.g01 (geometry) --- (continued)

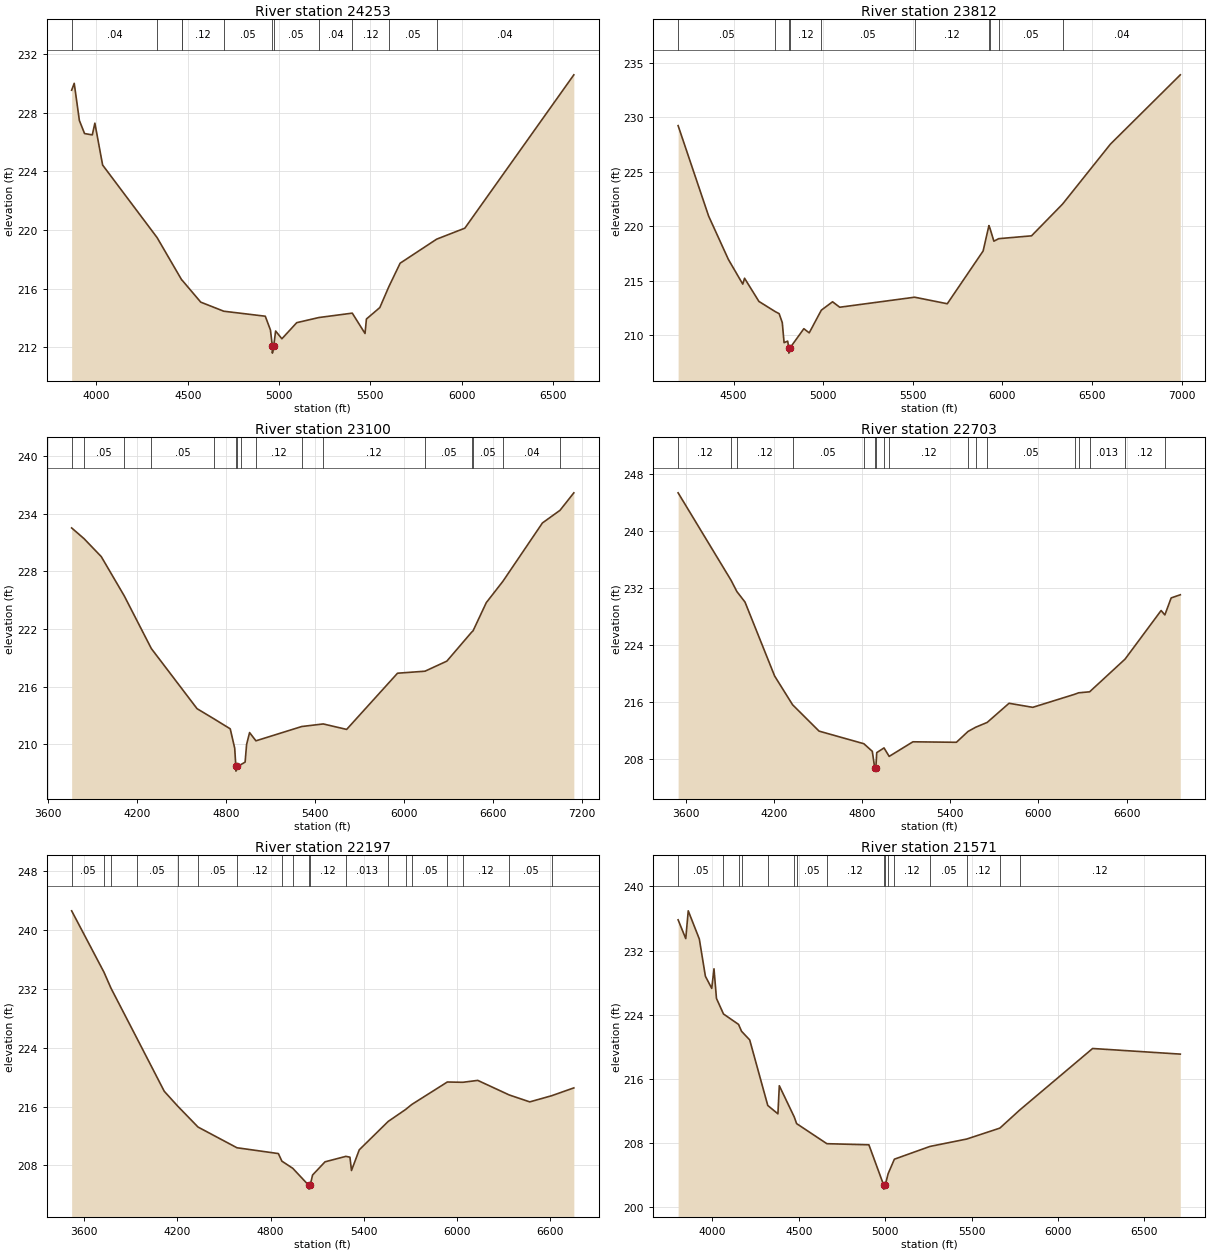
Type RM Length L Ch R = 1,24253,441,441,441
BEGIN DESCRIPTION:
BOGGY BRANCH 44.0
END DESCRIPTION:
XS GIS Cut Line= 3
      2507974.97     13539624.97      2507175.00     13538825.00
      2505575.04     13538575.01
#Sta/Elev= 30
  3863.9  229.54  3878.0  230.01  3906.3  227.47  3934.6  226.58  3977.0  226.49
  3991.1  227.29  4033.6  224.43  4331.8  219.48  4467.1  216.58  4469.0  216.57
  4571.0  215.07  4697.5  214.45  4924.5  214.11  4952.8  213.17  4963.0  212.09
  4963.5  211.59  4970.8  212.09  4981.1  213.10  5015.5  212.57  5096.9  213.67
  5217.9  214.02  5401.0  214.32  5470.9  212.93  5478.5  213.92  5551.9  214.70
  5600.7  216.11  5663.2  217.73  5863.1  219.37  6017.5  220.12  6614.6  230.59
#Mann=11,-1,0
  3863.9    0.04       0  4331.8    0.12       0  4467.1    0.05       0
  4469.0    0.12       0  4697.5    0.05       0  4963.0    0.05       0
  4970.8    0.05       0  5217.9    0.04       0  5401.0    0.12       0
  5600.7    0.05       0  5863.1    0.04       0
Bank Sta=4963,4970.8
Exp/Cntr=0.3,0.1

Type RM Length L Ch R = 1,23812,712,712,712
BEGIN DESCRIPTION:
BOGGY BRANCH 43.0
END DESCRIPTION:
XS GIS Cut Line= 3
      2508225.01     13538425.00      2507425.00     13538475.00
      2505424.97     13538475.00
#Sta/Elev= 30
  4190.9  229.25  4361.2  220.95  4471.5  216.97  4551.6  214.71  4561.6  215.25
  4641.8  213.12  4732.7  212.19  4754.5  212.00  4772.0  211.18  4782.1  209.34
  4802.1  209.48  4808.1  208.88  4808.6  208.38  4816.1  208.88  4892.3  210.62
  4922.3  210.24  4989.8  212.32  5052.5  213.09  5092.5  212.59  5510.7  213.51
  5692.5  212.91  5892.5  217.75  5924.8  220.08  5929.9  219.87  5952.5  218.65
  5979.5  218.88  6162.5  219.14  6335.5  222.05  6602.5  227.55  6992.5  233.91
#Mann=10,-1,0
  4190.9    0.05       0  4732.7    0.12       0  4808.1    0.05       0
  4816.1    0.12       0  4989.8    0.05       0  5510.7    0.12       0
  5924.8    0.05       0  5929.9    0.12       0  5979.5    0.05       0
  6335.5    0.04       0
Bank Sta=4808.1,4816.1
Exp/Cntr=0.3,0.1

Type RM Length L Ch R = 1,23100,397,397,397
BEGIN DESCRIPTION:
Mapping XS 575727a3
END DESCRIPTION:
XS GIS Cut Line= 4
      2508710.02     13537965.27      2507564.19     13537876.72
      2507038.15     13537892.35      2505368.12     13538246.13
#Sta/Elev= 30
  3761.9  232.54  3844.7  231.43  3961.3  229.55  4116.4  225.45  4298.7  219.96
  4606.7  213.69  4720.8  212.63  4830.1  211.59  4860.2  209.57  4867.9  207.68
  4868.4  207.18  4875.9  207.68  4900.8  207.85  4930.3  208.12  4940.3  209.96
  4960.4  211.20  5003.1  210.34  5311.5  211.83  5456.5  212.10  5614.2  211.53
  5956.9  217.39  6141.9  217.60  6289.1  218.65  6456.1  221.67  6465.7  221.81
  6554.8  224.75  6666.5  226.97  6933.0  233.06  7051.6  234.38  7144.5  236.20
#Mann=16,-1,0
  3761.9    0.12       0  3844.7    0.05       0  4116.4    0.12       0
  4298.7    0.05       0  4720.8    0.12       0  4867.9    0.05       0
  4875.9    0.12       0  4900.8    0.05       0  5003.1    0.12       0
  5311.5    0.05       0  5456.5    0.12       0  6141.9    0.05       0
  6456.1    0.12       0  6465.7    0.05       0  6666.5    0.04       0
  7051.6   0.013       0
Bank Sta=4867.9,4875.9
Exp/Cntr=0.3,0.1

Type RM Length L Ch R = 1,22703,506,506,506
BEGIN DESCRIPTION:
Mapping XS 773e114c
END DESCRIPTION:
XS GIS Cut Line= 4
      2508876.70     13537710.06      2507710.03     13537559.02
      2506923.57     13537486.10      2505518.68     13537855.54
#Sta/Elev= 30
  3546.9  245.34  3907.6  233.05  3946.8  231.48  4002.4  229.99  4204.0  219.61
  4326.3  215.57  4506.5  211.87  4811.3  210.10  4869.0  209.03  4884.9  206.75
  4885.4  206.25  4893.1  206.75  4899.1  208.85  4948.8  209.51  4983.8  208.32
  5145.5  210.37  5441.4  210.30  5521.2  211.83  5573.2  212.42  5651.0  213.09
  5799.9  215.78  5961.2  215.21  6246.0  217.04  6273.1  217.25  6348.4  217.39
  6590.0  221.99  6835.2  228.81  6860.6  228.19  6903.6  230.58  6965.8  231.02
#Mann=17,-1,0
  3546.9    0.12       0  3907.6    0.05       0  3946.8    0.12       0
  4326.3    0.05       0  4811.3    0.12       0  4884.9    0.05       0
  4893.1    0.12       0  4948.8    0.05       0  4983.8    0.12       0
  5521.2    0.05       0  5573.2    0.12       0  5651.0    0.05       0
  6246.0   0.013       0  6273.1    0.12       0  6348.4   0.013       0
  6590.0    0.12       0  6860.6    0.04       0
Bank Sta=4884.9,4893.1
Exp/Cntr=0.3,0.1

Type RM Length L Ch R = 1,22197,626,626,626
BEGIN DESCRIPTION:
Mapping XS 8bdbb296
END DESCRIPTION:
XS GIS Cut Line= 4
      2508892.29     13537449.63      2507720.44     13537059.02
      2506944.40     13537017.35      2505850.67     13537559.01
#Sta/Elev= 30
  3518.7  242.58  3726.4  234.26  3771.8  232.08  3938.8  225.27  4114.9  218.07
  4201.2  216.06  4332.4  213.21  4582.7  210.40  4849.5  209.61  4872.1  208.58
  4942.1  207.61  5045.7  205.28  5046.2  204.78  5054.0  205.28  5069.8  206.70
  5149.9  208.49  5284.1  209.23  5310.2  209.12  5320.2  207.31  5370.3  210.12
  5556.8  213.98  5668.1  215.59  5708.4  216.28  5937.2  219.33  6037.3  219.29
  6133.0  219.55  6335.8  217.57  6467.8  216.63  6607.8  217.46  6751.6  218.53
#Mann=19,-1,0
  3518.7    0.05       0  3726.4    0.12       0  3771.8    0.04       0
  3938.8    0.05       0  4201.2    0.04       0  4332.4    0.05       0
  4582.7    0.12       0  4872.1    0.05       0  4942.1    0.12       0
  5045.7    0.05       0  5054.0    0.12       0  5284.1   0.013       0
  5556.8    0.05       0  5668.1    0.12       0  5708.4    0.05       0
  5937.2   0.013       0  6037.3    0.12       0  6335.8    0.05       0
  6607.8    0.12       0
Bank Sta=5045.7,5054
Exp/Cntr=0.3,0.1

Type RM Length L Ch R = 1,21571,636,636,636
BEGIN DESCRIPTION:
BOGGY BRANCH 38.0
END DESCRIPTION:
XS GIS Cut Line= 4
      2508777.71     13537085.04      2508079.82     13536532.97
      2507413.15     13536512.14      2506262.51     13537220.23
#Sta/Elev= 30
  3801.0  235.83  3845.2  233.49  3859.7  236.95  3923.8  233.44  3959.0  228.80
  3995.7  227.29  4008.7  229.73  4023.1  226.04  4063.7  224.10  4151.0  222.80
  4168.1  221.95  4215.5  220.87  4320.2  212.70  4378.9  211.66  4387.0  215.16
  4473.2  211.28  4487.3  210.44  4662.4  207.94  4905.8  207.80  4991.3  202.78
  4991.8  202.28  5000.3  202.78  5017.1  204.20  5053.3  206.01  5259.6  207.60
  5472.2  208.52  5664.0  209.88  5778.8  212.13  6201.1  219.80  6708.9  219.10
#Mann=16,-1,0
  3801.0    0.05       0  4063.7    0.03       0  4151.0    0.05       0
  4168.1   0.013       0  4320.2    0.05       0  4473.2    0.12       0
  4487.3    0.05       0  4662.4    0.12       0  4991.3    0.05       0
  5000.3    0.12       0  5017.1    0.05       0  5053.3    0.12       0
  5259.6    0.05       0  5472.2    0.12       0  5664.0    0.05       0
  5778.8    0.12       0
Bank Sta=4991.3,5000.3
Exp/Cntr=0.3,0.1

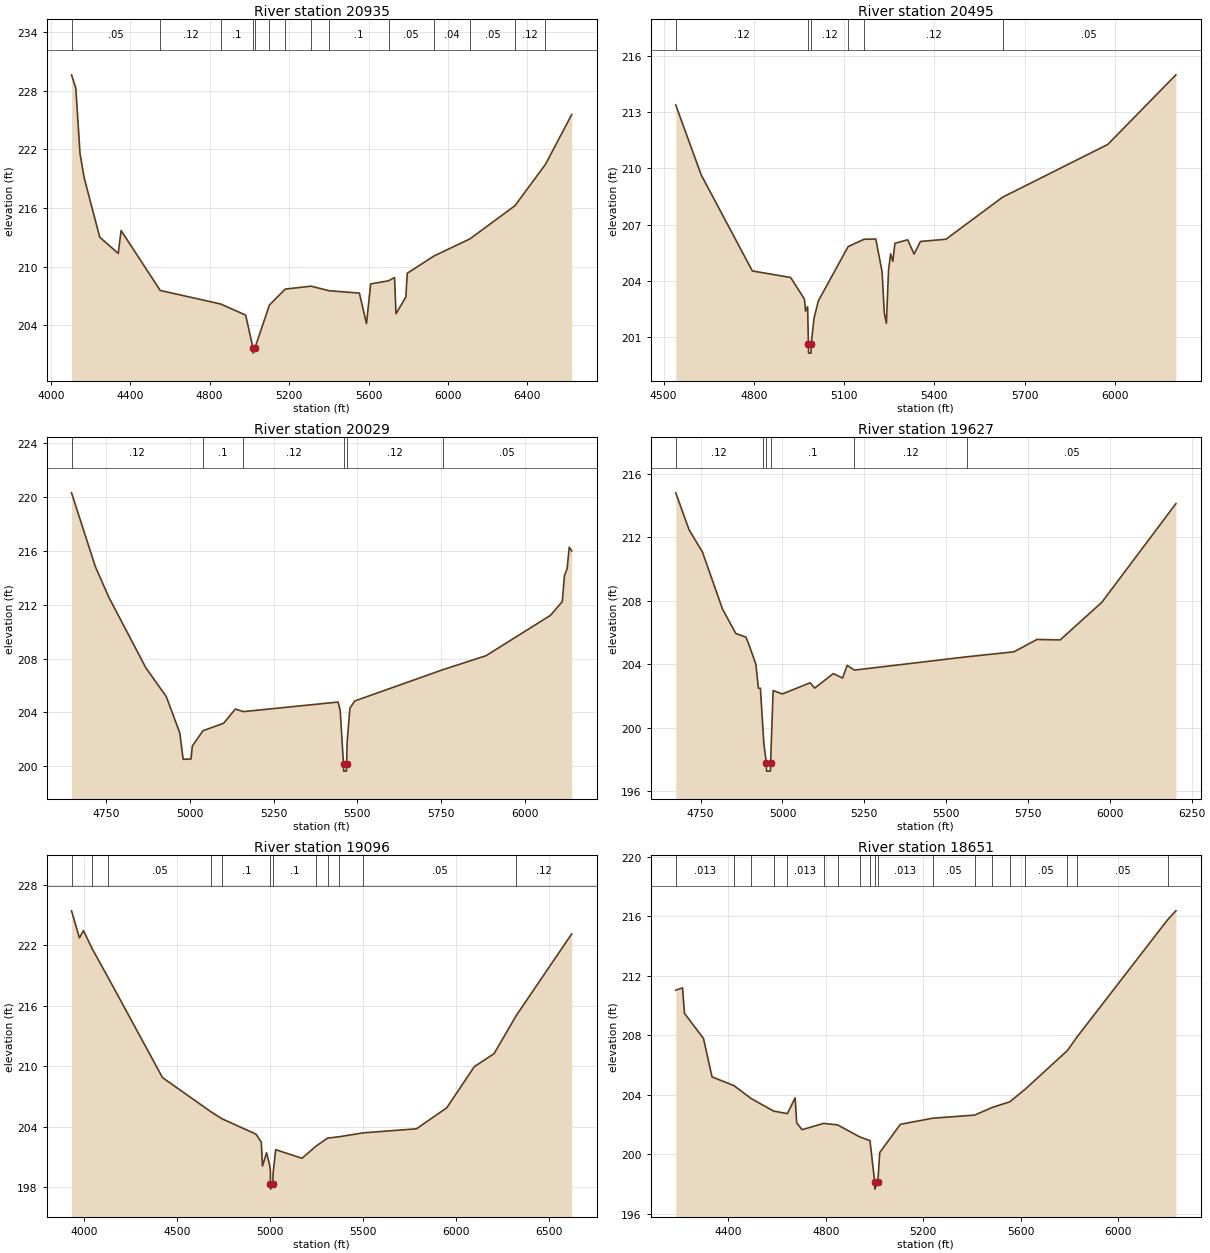
Type RM Length L Ch R = 1,20935,440,440,440
BEGIN DESCRIPTION:
BOGGY BRANCH 37.0
END DESCRIPTION:
XS GIS Cut Line= 3
      2508525.02     13536725.03      2507975.00     13536025.00
      2506775.03     13534925.03
#Sta/Elev= 30
  4104.8  229.62  4126.5  228.23  4147.3  221.58  4168.4  219.08  4246.8  213.01
  4339.8  211.35  4354.3  213.69  4551.4  207.56  4854.8  206.18  4981.5  205.04
  5018.6  201.65  5019.1  201.15  5027.6  201.65  5101.1  206.07  5180.6  207.70
  5310.7  208.00  5402.1  207.53  5554.0  207.29  5589.8  204.17  5610.8  208.23
  5700.8  208.55  5731.0  208.88  5738.4  205.18  5787.7  206.88  5795.1  209.32
  5929.1  211.08  6110.8  212.84  6337.2  216.23  6490.9  220.46  6622.9  225.55
#Mann=14,-1,0
  4104.8    0.05       0  4551.4    0.12       0  4854.8     0.1       0
  5018.6    0.05       0  5027.6     0.1       0  5101.1    0.12       0
  5180.6    0.05       0  5310.7    0.12       0  5402.1     0.1       0
  5700.8    0.05       0  5929.1    0.04       0  6110.8    0.05       0
  6337.2    0.12       0  6490.9    0.05       0
Bank Sta=5018.6,5027.6
Exp/Cntr=0.3,0.1

Type RM Length L Ch R = 1,20495,466,466,466
BEGIN DESCRIPTION:
BOGGY BRANCH 36.0
END DESCRIPTION:
XS GIS Cut Line= 3
      2508674.99     13536174.99      2508375.00     13535875.00
      2507524.99     13534974.99
#Sta/Elev= 30
  4540.4  213.37  4625.2  209.64  4794.9  204.53  4922.2  204.18  4968.1  203.03
  4971.7  202.39  4978.6  202.63  4981.3  200.65  4981.8  200.15  4990.0  200.15
  4990.5  200.65  5000.0  202.01  5014.2  202.93  5113.4  205.83  5166.6  206.22
  5205.2  206.23  5226.2  204.48  5233.5  202.28  5240.4  201.74  5247.6  204.59
  5254.5  205.44  5261.8  205.04  5268.7  206.00  5311.2  206.19  5332.6  205.43
  5353.6  206.10  5438.6  206.22  5626.7  208.46  5976.2  211.27  6202.6  214.98
#Mann=6,-1,0
  4540.4    0.12       0  4981.3    0.05       0  4990.5    0.12       0
  5113.4    0.05       0  5166.6    0.12       0  5626.7    0.05       0
Bank Sta=4981.3,4990.5
Exp/Cntr=0.3,0.1

Type RM Length L Ch R = 1,20029,402,402,402
BEGIN DESCRIPTION:
BOGGY BRANCH 35.0
END DESCRIPTION:
XS GIS Cut Line= 3
      2508825.01     13536075.04      2508775.00     13535725.00
      2508074.98     13534824.98
#Sta/Elev= 30
  4646.7  220.31  4717.5  214.85  4757.9  212.56  4869.0  207.30  4929.6  205.18
  4970.0  202.48  4980.1  200.52  5003.5  200.54  5007.5  201.50  5039.1  202.64
  5100.7  203.19  5136.0  204.25  5160.0  204.06  5442.8  204.77  5449.1  204.15
  5459.0  200.14  5459.5  199.64  5467.7  199.64  5468.2  200.14  5469.9  201.82
  5478.1  204.32  5492.6  204.85  5755.2  207.17  5884.4  208.21  6077.1  211.21
  6112.4  212.23  6118.8  214.15  6126.9  214.68  6133.2  216.27  6140.5  215.99
#Mann=6,-1,0
  4646.7    0.12       0  5039.1     0.1       0  5160.0    0.12       0
  5459.0    0.05       0  5468.2    0.12       0  5755.2    0.05       0
Bank Sta=5459,5468.2
Exp/Cntr=0.3,0.1

Type RM Length L Ch R = 1,19627,531,531,531
BEGIN DESCRIPTION:
BOGGY BRANCH 34.0
END DESCRIPTION:
XS GIS Cut Line= 3
      2509175.00     13535774.99      2509125.00     13535525.00
      2508225.03     13534625.03
#Sta/Elev= 30
  4674.0  214.79  4714.8  212.46  4755.6  211.06  4816.8  207.47  4857.6  205.93
  4888.2  205.71  4898.3  205.19  4918.7  204.00  4926.4  202.49  4932.5  202.49
  4940.4  199.89  4943.1  199.00  4950.8  197.77  4951.3  197.27  4963.1  197.27
  4963.6  197.77  4971.4  202.34  4999.7  202.13  5084.5  202.83  5098.6  202.50
  5155.2  203.41  5183.5  203.13  5197.6  203.93  5219.6  203.63  5563.8  204.47
  5706.8  204.78  5777.5  205.56  5848.2  205.53  5975.5  207.90  6201.7  214.11
#Mann=6,-1,0
  4674.0    0.12       0  4940.4     0.1       0  4950.8    0.05       0
  4963.6     0.1       0  5219.6    0.12       0  5563.8    0.05       0
Bank Sta=4950.8,4963.6
Exp/Cntr=0.3,0.1

Type RM Length L Ch R = 1,19096,445,445,445
BEGIN DESCRIPTION:
BOGGY BRANCH 33.0
END DESCRIPTION:
XS GIS Cut Line= 3
      2510075.02     13535975.02      2509375.00     13535175.00
      2508175.01     13534075.01
#Sta/Elev= 30
  3932.7  225.39  3975.0  222.71  3996.8  223.43  4044.0  221.62  4127.1  218.86
  4422.0  208.86  4684.1  205.45  4742.7  204.77  4925.0  203.25  4953.5  202.47
  4960.1  200.09  4982.0  201.41  4999.1  200.13  5002.8  199.54  5003.1  198.30
  5003.6  197.80  5016.1  198.30  5017.0  199.37  5031.2  201.71  5172.4  200.86
  5248.6  202.07  5310.5  202.86  5371.5  202.99  5503.3  203.38  5788.4  203.78
  5951.2  205.86  6099.8  209.94  6205.9  211.23  6326.5  215.04  6623.6  223.10
#Mann=12,-1,0
  3932.7   0.013       0  4044.0    0.12       0  4127.1    0.05       0
  4684.1    0.12       0  4742.7     0.1       0  5003.1    0.05       0
  5016.1     0.1       0  5248.6    0.12       0  5310.5    0.05       0
  5371.5    0.12       0  5503.3    0.05       0  6326.5    0.12       0
Bank Sta=5003.1,5016.1
Exp/Cntr=0.3,0.1

Type RM Length L Ch R = 1,18651,440,440,440
BEGIN DESCRIPTION:
BOGGY BRANCH 32.0
END DESCRIPTION:
XS GIS Cut Line= 3
      2509924.97     13535424.97      2509425.00     13534825.00
      2508524.98     13533924.98
#Sta/Elev= 30
  4183.6  211.03  4211.5  211.19  4219.4  209.48  4297.5  207.78  4332.6  205.20
  4422.8  204.61  4493.5  203.74  4585.4  202.90  4642.0  202.73  4673.7  203.79
  4680.2  202.11  4702.3  201.65  4790.6  202.07  4848.3  201.97  4939.2  201.16
  4981.1  200.91  5000.5  198.15  5001.0  197.65  5013.5  198.15  5021.2  200.11
  5106.0  202.01  5238.5  202.42  5411.4  202.63  5482.4  203.14  5554.9  203.52
  5617.7  204.36  5791.8  206.97  5831.6  207.89  6203.4  215.77  6237.4  216.37
#Mann=19,-1,0
  4183.6   0.013       0  4422.8    0.12       0  4493.5   0.013       0
  4585.4    0.12       0  4642.0   0.013       0  4790.6    0.12       0
  4848.3   0.013       0  4939.2    0.12       0  4981.1   0.013       0
  5000.5    0.03       0  5013.5   0.013       0  5238.5    0.05       0
  5411.4   0.013       0  5482.4    0.05       0  5554.9   0.013       0
  5617.7    0.05       0  5791.8   0.013       0  5831.6    0.05       0
  6203.4    0.04       0
Bank Sta=5000.5,5013.5
Exp/Cntr=0.3,0.1

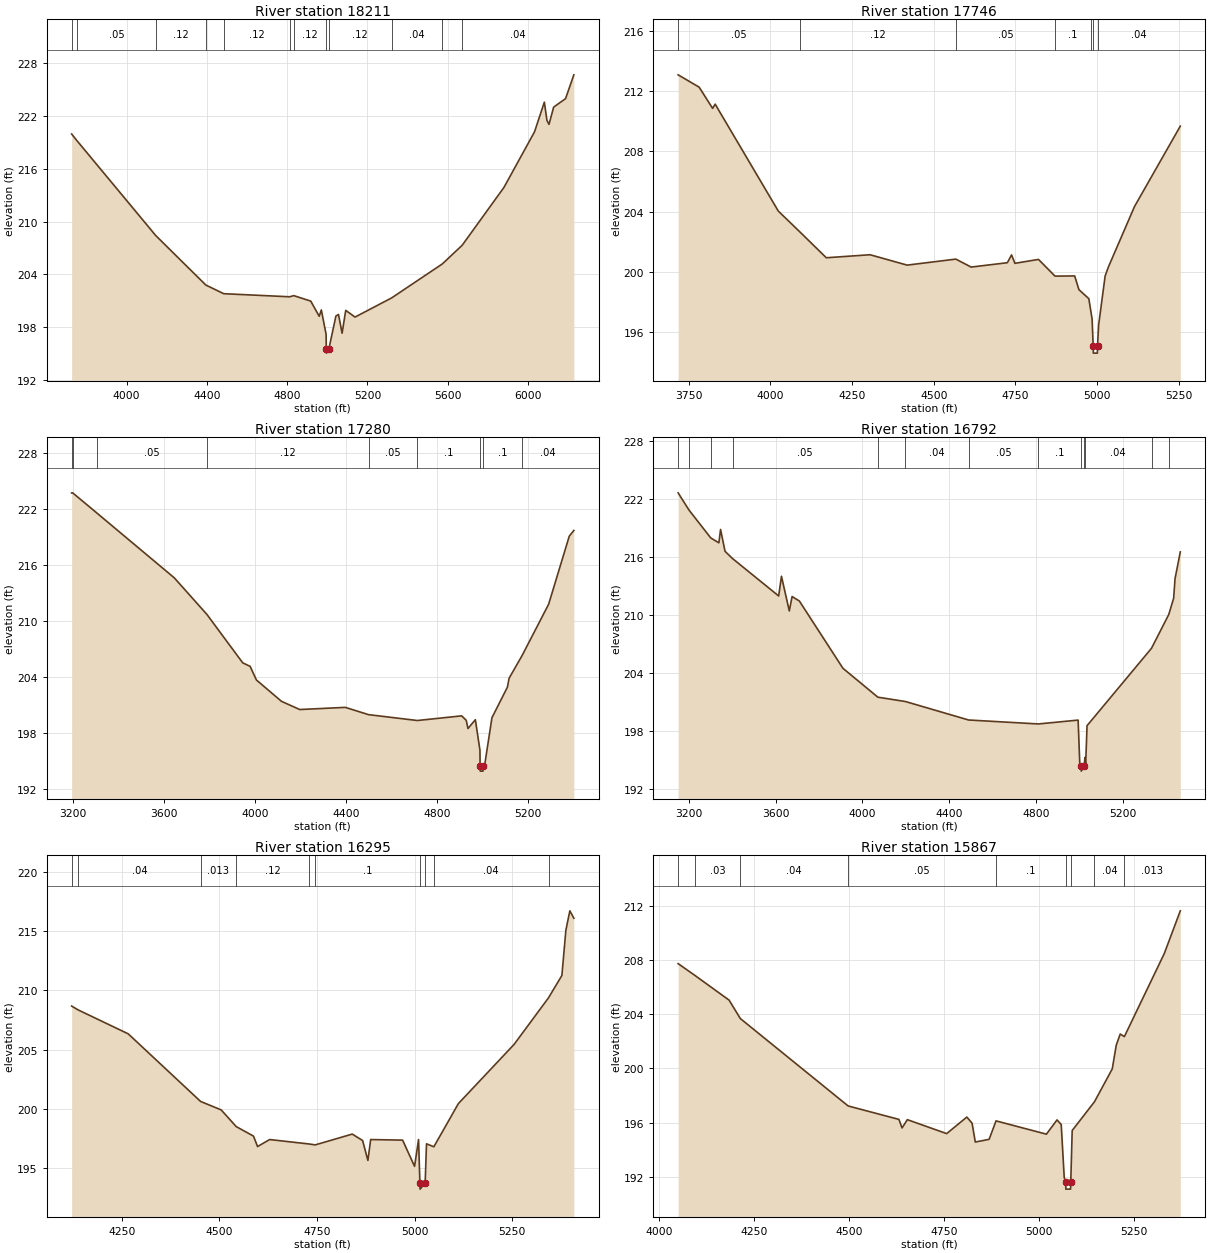
Type RM Length L Ch R = 1,18211,465,465,465
BEGIN DESCRIPTION:
BOGGY BRANCH 31.0
END DESCRIPTION:
XS GIS Cut Line= 3
      2510074.99     13535674.98      2509675.00     13534475.00
      2509375.00     13533275.02
#Sta/Elev= 30
  3726.7  219.93  3753.6  219.16  4145.8  208.41  4395.2  202.80  4484.3  201.82
  4812.1  201.47  4833.5  201.60  4917.8  200.98  4960.0  199.26  4970.5  199.98
  4994.2  197.23  4995.4  195.58  4995.9  195.08  5008.4  195.58  5043.1  199.28
  5056.0  199.47  5074.0  197.34  5092.1  199.93  5138.5  199.17  5320.7  201.34
  5573.0  205.19  5672.2  207.31  5880.6  213.88  6032.7  220.18  6081.6  223.54
  6094.5  221.48  6104.8  221.02  6128.0  222.98  6187.3  223.94  6228.5  226.64
#Mann=12,-1,0
  3726.7   0.013       0  3753.6    0.05       0  4145.8    0.12       0
  4395.2    0.05       0  4484.3    0.12       0  4812.1    0.05       0
  4833.5    0.12       0  4995.4    0.05       0  5008.4    0.12       0
  5320.7    0.04       0  5573.0    0.05       0  5672.2    0.04       0
Bank Sta=4995.4,5008.4
Exp/Cntr=0.3,0.1

Type RM Length L Ch R = 1,17746,466,466,466
BEGIN DESCRIPTION:
BOGGY BRANCH 30.0
END DESCRIPTION:
XS GIS Cut Line= 3
      2510175.00     13535325.00      2509875.00     13534125.00
      2509875.00     13533825.03
#Sta/Elev= 30
  3717.8  213.09  3782.2  212.27  3823.4  210.86  3831.2  211.14  4024.5  204.03
  4089.9  202.66  4171.3  200.93  4305.3  201.13  4418.7  200.44  4567.7  200.84
  4614.6  200.31  4725.4  200.60  4738.3  201.12  4748.6  200.56  4820.7  200.82
  4871.2  199.71  4931.5  199.72  4944.4  198.81  4974.7  198.21  4982.0  197.23
  4984.7  196.87  4988.1  195.09  4988.6  194.59  5000.9  194.59  5001.4  195.09
  5004.7  196.45  5024.7  199.72  5034.7  200.32  5114.7  204.34  5254.7  209.68
#Mann=7,-1,0
  3717.8    0.05       0  4089.9    0.12       0  4567.7    0.05       0
  4871.2     0.1       0  4982.0    0.04       0  4988.1    0.04       0
  5001.4    0.04       0
Bank Sta=4988.1,5001.4
Exp/Cntr=0.3,0.1

Type RM Length L Ch R = 1,17280,488,488,488
BEGIN DESCRIPTION:
BOGGY BRANCH 29.0
END DESCRIPTION:
XS GIS Cut Line= 3
      2510175.00     13535824.96      2510325.00     13534025.00
      2510275.00     13533625.01
#Sta/Elev= 30
  3193.8  223.72  3198.1  223.73  3306.4  221.53  3645.3  214.61  3789.0  210.68
  3946.4  205.49  3979.0  205.11  4006.6  203.65  4116.9  201.36  4197.2  200.48
  4397.9  200.71  4499.9  199.93  4714.9  199.30  4909.7  199.80  4929.8  199.32
  4937.3  198.44  4969.9  199.39  4990.0  196.12  4990.8  194.37  4991.3  193.87
  5003.6  193.87  5004.1  194.37  5010.1  194.41  5042.8  199.60  5110.9  202.88
  5118.4  203.84  5175.0  206.25  5292.3  211.78  5383.0  219.08  5403.1  219.69
#Mann=9,-1,0
  3193.8    0.03       0  3198.1   0.013       0  3306.4    0.05       0
  3789.0    0.12       0  4499.9    0.05       0  4714.9     0.1       0
  4990.8    0.05       0  5004.1     0.1       0  5175.0    0.04       0
Bank Sta=4990.8,5004.1
Exp/Cntr=0.3,0.1

Type RM Length L Ch R = 1,16792,497,497,497
BEGIN DESCRIPTION:
BOGGY BRANCH 28.0
END DESCRIPTION:
XS GIS Cut Line= 3
      2510325.01     13535774.96      2510775.00     13533975.00
      2510675.01     13533525.03
#Sta/Elev= 30
  3149.9  222.61  3199.7  220.84  3300.6  217.94  3338.0  217.44  3345.7  218.82
  3366.3  216.56  3401.5  215.80  3613.7  211.94  3626.6  213.98  3662.7  210.39
  3675.6  211.88  3709.1  211.42  3910.1  204.46  4071.2  201.47  4198.5  201.02
  4489.6  199.11  4811.4  198.70  4994.9  199.10  5002.7  194.51  5008.8  194.32
  5009.3  193.82  5022.2  194.32  5026.4  195.23  5029.6  194.43  5036.0  198.52
  5333.4  206.53  5412.9  210.02  5435.5  211.70  5441.9  213.73  5466.2  216.50
#Mann=13,-1,0
  3149.9    0.03       0  3199.7   0.013       0  3300.6    0.03       0
  3401.5    0.05       0  4071.2    0.12       0  4198.5    0.04       0
  4489.6    0.05       0  4811.4     0.1       0  5008.8    0.05       0
  5022.2     0.1       0  5026.4    0.04       0  5333.4    0.05       0
  5412.9    0.04       0
Bank Sta=5008.8,5022.2
Exp/Cntr=0.3,0.1

Type RM Length L Ch R = 1,16295,428,428,428
BEGIN DESCRIPTION:
BOGGY BRANCH 27.0
END DESCRIPTION:
XS GIS Cut Line= 3
      2510975.00     13534774.99      2511175.00     13534025.00
      2511075.00     13533525.00
#Sta/Elev= 30
  4121.6  208.67  4138.1  208.35  4266.5  206.33  4451.9  200.63  4504.5  199.92
  4543.1  198.51  4587.3  197.71  4597.7  196.83  4628.7  197.42  4728.6  197.05
  4745.6  196.97  4840.2  197.88  4866.7  197.34  4880.3  195.66  4887.4  197.42
  4969.2  197.37  4999.8  195.16  5010.0  197.42  5013.5  193.74  5014.0  193.24
  5026.9  193.74  5030.4  197.06  5049.2  196.81  5112.0  200.45  5254.7  205.44
  5342.9  209.37  5377.1  211.25  5387.3  215.07  5397.5  216.70  5407.7  216.08
#Mann=10,-1,0
  4121.6    0.03       0  4138.1    0.04       0  4451.9   0.013       0
  4543.1    0.12       0  4728.6   0.013       0  4745.6     0.1       0
  5013.5    0.05       0  5026.9     0.1       0  5049.2    0.04       0
  5342.9     0.1       0
Bank Sta=5013.5,5026.9
Exp/Cntr=0.3,0.1

Type RM Length L Ch R = 1,15867,425,425,425
BEGIN DESCRIPTION:
BOGGY BRANCH 26.0
END DESCRIPTION:
XS GIS Cut Line= 3
      2511125.00     13534775.00      2511575.00     13533875.00
      2511474.99     13533574.96
#Sta/Elev= 30
  4049.9  207.72  4093.1  206.87  4184.1  205.03  4213.8  203.67  4497.6  197.23
  4631.3  196.24  4639.7  195.61  4653.6  196.22  4757.1  195.19  4810.2  196.41
  4824.1  195.96  4832.5  194.57  4868.9  194.77  4887.1  196.13  5019.8  195.15
  5047.7  196.20  5058.8  195.86  5066.7  191.97  5070.5  191.60  5071.0  191.10
  5083.4  191.10  5083.9  191.60  5087.7  195.42  5146.4  197.54  5193.2  199.96
  5203.7  201.71  5214.2  202.53  5225.1  202.34  5330.2  208.46  5372.4  211.61
#Mann=9,-1,0
  4049.9    0.04       0  4093.1    0.03       0  4213.8    0.04       0
  4497.6    0.05       0  4887.1     0.1       0  5070.5    0.05       0
  5083.9     0.1       0  5146.4    0.04       0  5225.1   0.013       0
Bank Sta=5070.5,5083.9
Exp/Cntr=0.3,0.1