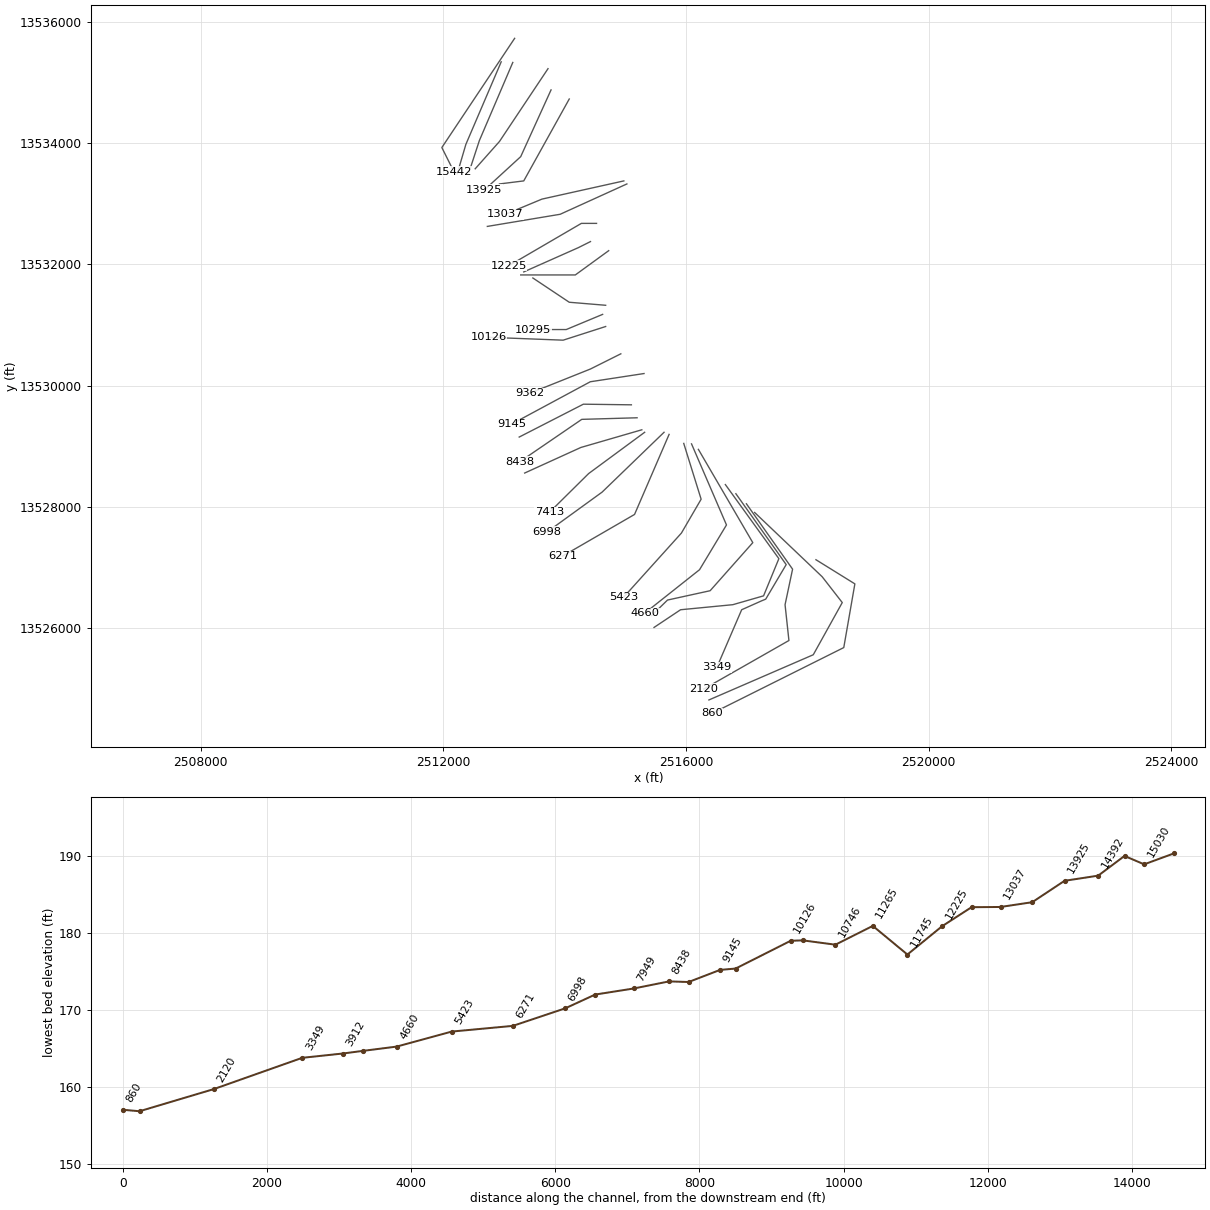
HEC-RAS study BOGGY BRANCH.prj: BOGGY BRANCH Base Level Engineering

--- BOGGY BRANCH.g01 (geometry) --- (continued)

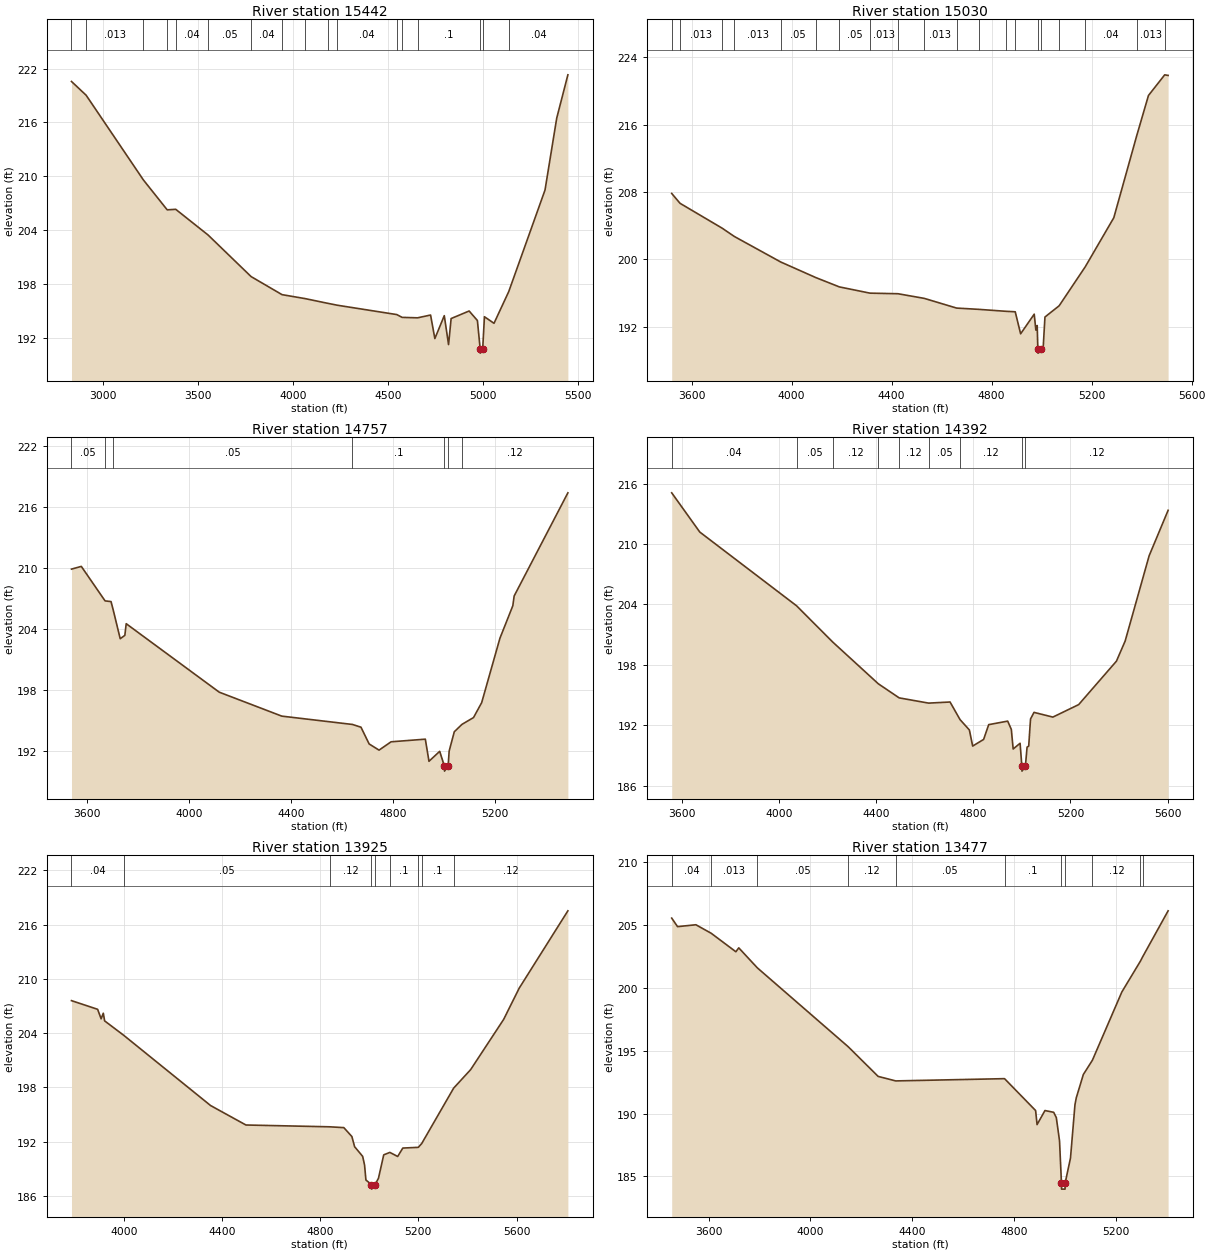
Type RM Length L Ch R = 1,15442,412,412,412
BEGIN DESCRIPTION:
BOGGY BRANCH 25.0
END DESCRIPTION:
XS GIS Cut Line= 3
      2513174.97     13535724.96      2511975.00     13533925.00
      2512175.00     13533525.00
#Sta/Elev= 30
  2836.7  220.56  2913.7  219.03  3214.8  209.60  3340.1  206.27  3384.9  206.33
  3555.0  203.47  3781.3  198.84  3943.9  196.83  4065.2  196.39  4185.4  195.86
  4235.3  195.65  4547.6  194.61  4575.4  194.30  4656.7  194.25  4725.1  194.56
  4747.6  191.94  4797.2  194.49  4819.7  191.27  4833.2  194.17  4927.9  195.01
  4971.4  193.95  4985.8  190.82  4986.3  190.32  4999.2  190.82  5008.4  194.37
  5058.7  193.64  5136.2  197.17  5327.0  208.48  5388.5  216.48  5447.2  221.30
#Mann=17,-1,0
  2836.7    0.05       0  2913.7   0.013       0  3214.8    0.04       0
  3340.1   0.013       0  3384.9    0.04       0  3555.0    0.05       0
  3781.3    0.04       0  3943.9    0.05       0  4065.2    0.04       0
  4185.4    0.05       0  4235.3    0.04       0  4547.6    0.05       0
  4575.4    0.04       0  4656.7     0.1       0  4985.8    0.05       0
  4999.2     0.1       0  5136.2    0.04       0
Bank Sta=4985.8,4999.2
Exp/Cntr=0.3,0.1

Type RM Length L Ch R = 1,15030,273,273,273
BEGIN DESCRIPTION:
BOGGY BRANCH 24.0
END DESCRIPTION:
XS GIS Cut Line= 3
      2512953.57     13535337.99      2512370.95     13533976.87
      2512228.45     13533492.47
#Sta/Elev= 30
  3520.3  207.83  3553.6  206.66  3722.1  203.71  3770.7  202.73  3956.5  199.70
  4096.3  197.86  4190.9  196.75  4313.4  196.01  4425.4  195.94  4530.5  195.39
  4659.8  194.24  4747.6  194.09  4856.1  193.86  4894.3  193.80  4915.9  191.19
  4970.3  193.52  4976.8  191.63  4982.2  192.17  4984.7  189.40  4985.2  188.90
  4999.3  189.40  5006.1  189.52  5013.2  193.18  5069.9  194.51  5174.3  199.13
  5288.6  204.95  5380.7  214.72  5427.2  219.44  5492.2  221.89  5505.8  221.82
#Mann=20,-1,0
  3520.3    0.04       0  3553.6   0.013       0  3722.1    0.04       0
  3770.7   0.013       0  3956.5    0.05       0  4096.3   0.013       0
  4190.9    0.05       0  4313.4   0.013       0  4425.4    0.05       0
  4530.5   0.013       0  4659.8     0.1       0  4747.6    0.05       0
  4856.1   0.013       0  4894.3     0.1       0  4984.7    0.05       0
  4999.3     0.1       0  5069.9   0.013       0  5174.3    0.04       0
  5380.7   0.013       0  5492.2    0.04       0
Bank Sta=4984.7,4999.3
Exp/Cntr=0.3,0.1

Type RM Length L Ch R = 1,14757,365,365,365
BEGIN DESCRIPTION:
Mapping XS f56c90a2
END DESCRIPTION:
XS GIS Cut Line= 3
      2513144.25     13535327.52      2512593.03     13534038.46
      2512423.76     13533521.96
#Sta/Elev= 30
  3539.0  209.90  3577.5  210.17  3670.6  206.77  3694.0  206.70  3702.3  205.90
  3730.0  203.04  3748.1  203.37  3753.5  204.52  4118.2  197.77  4363.3  195.41
  4640.1  194.59  4673.6  194.32  4705.5  192.67  4744.4  192.06  4791.6  192.88
  4925.8  193.14  4940.1  190.96  4982.1  191.94  5000.5  190.49  5001.0  189.99
  5015.1  190.49  5019.2  191.97  5039.3  193.87  5069.5  194.60  5114.7  195.27
  5146.6  196.74  5218.2  203.09  5268.7  206.29  5273.9  207.25  5484.5  217.42
#Mann=7,-1,0
  3539.0    0.05       0  3670.6   0.013       0  3702.3    0.05       0
  4640.1     0.1       0  5000.5    0.05       0  5015.1     0.1       0
  5069.5    0.12       0
Bank Sta=5000.5,5015.1
Exp/Cntr=0.3,0.1

Type RM Length L Ch R = 1,14392,467,467,467
BEGIN DESCRIPTION:
BOGGY BRANCH 23.0
END DESCRIPTION:
XS GIS Cut Line= 3
      2513724.99     13535224.99      2512925.00     13534025.00
      2512524.99     13533574.99
#Sta/Elev= 30
  3557.9  215.09  3673.6  211.19  4072.2  203.86  4220.5  200.27  4408.8  196.11
  4494.7  194.71  4615.9  194.19  4704.2  194.30  4745.3  192.55  4783.8  191.52
  4797.3  189.92  4842.4  190.58  4863.4  192.05  4941.5  192.40  4956.5  191.58
  4964.1  189.63  4992.6  190.20  4999.9  187.93  5000.4  187.43  5014.5  187.93
  5021.4  189.82  5028.1  189.91  5035.6  192.61  5049.9  193.27  5127.6  192.80
  5233.8  194.04  5389.4  198.36  5425.3  200.36  5524.0  208.83  5602.2  213.35
#Mann=9,-1,0
  3557.9    0.04       0  4072.2    0.05       0  4220.5    0.12       0
  4408.8    0.05       0  4494.7    0.12       0  4615.9    0.05       0
  4745.3    0.12       0  4999.9    0.05       0  5014.5    0.12       0
Bank Sta=4999.9,5014.5
Exp/Cntr=0.3,0.1

Type RM Length L Ch R = 1,13925,448,448,448
BEGIN DESCRIPTION:
BOGGY BRANCH 22.0
END DESCRIPTION:
XS GIS Cut Line= 3
      2513775.01     13534875.01      2513275.00     13533775.00
      2512674.97     13533224.97
#Sta/Elev= 30
  3787.0  207.60  3893.6  206.64  3907.8  205.59  3916.6  206.21  3922.1  205.36
  3999.7  203.77  4353.8  196.00  4497.7  193.85  4838.4  193.65  4896.5  193.56
  4929.4  192.57  4940.4  191.45  4973.3  190.38  4981.0  189.42  4986.5  187.77
  5009.2  187.26  5009.7  186.76  5023.9  187.26  5037.6  187.96  5059.1  190.55
  5083.9  190.82  5115.9  190.37  5136.8  191.30  5199.9  191.38  5214.0  191.81
  5344.0  197.93  5413.1  199.97  5547.5  205.52  5611.0  208.98  5809.3  217.53
#Mann=9,-1,0
  3787.0    0.04       0  3999.7    0.05       0  4838.4    0.12       0
  5009.2    0.05       0  5023.9    0.12       0  5083.9     0.1       0
  5199.9    0.12       0  5214.0     0.1       0  5344.0    0.12       0
Bank Sta=5009.2,5023.9
Exp/Cntr=0.3,0.1

Type RM Length L Ch R = 1,13477,440,440,440
BEGIN DESCRIPTION:
BOGGY BRANCH 21.0
END DESCRIPTION:
XS GIS Cut Line= 3
      2514075.00     13534725.00      2513325.00     13533375.00
      2512924.96     13533324.99
#Sta/Elev= 30
  3455.6  205.57  3478.5  204.89  3550.5  205.04  3610.7  204.36  3707.3  202.89
  3718.7  203.20  3791.4  201.61  4148.2  195.32  4265.5  192.96  4334.5  192.60
  4761.4  192.78  4883.3  190.24  4889.0  189.12  4919.9  190.24  4954.2  190.10
  4964.5  189.68  4977.1  187.83  4984.6  184.48  4985.1  183.98  4998.8  183.98
  4999.3  184.48  5020.1  186.45  5037.7  190.71  5042.8  191.25  5070.5  193.11
  5106.1  194.25  5221.7  199.69  5294.7  202.15  5303.6  202.50  5403.1  206.15
#Mann=11,-1,0
  3455.6    0.04       0  3610.7   0.013       0  3791.4    0.05       0
  4148.2    0.12       0  4334.5    0.05       0  4761.4     0.1       0
  4984.6    0.05       0  4999.3     0.1       0  5106.1    0.12       0
  5294.7    0.04       0  5303.6    0.12       0
Bank Sta=4984.6,4999.3
Exp/Cntr=0.3,0.1

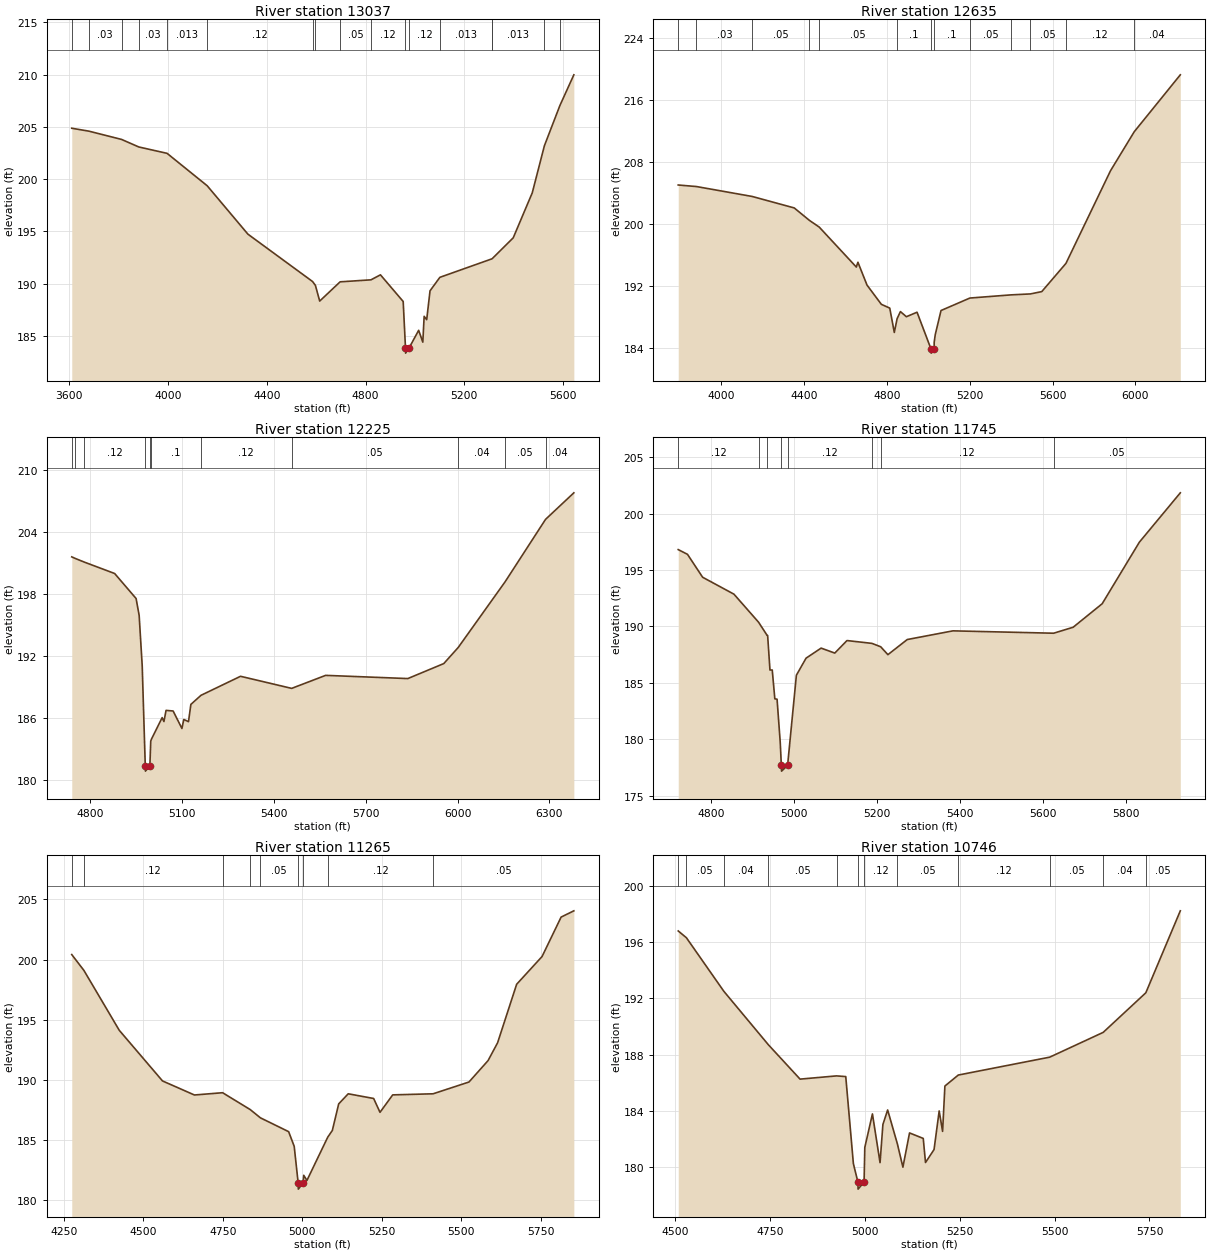
Type RM Length L Ch R = 1,13037,402,402,402
BEGIN DESCRIPTION:
BOGGY BRANCH 20.0
END DESCRIPTION:
XS GIS Cut Line= 3
      2514974.99     13533375.00      2513625.00     13533075.00
      2513025.02     13532825.01
#Sta/Elev= 30
  3610.5  204.87  3680.2  204.59  3812.3  203.80  3881.8  203.08  3996.4  202.47
  4158.8  199.37  4323.7  194.74  4585.4  190.21  4597.0  189.84  4614.4  188.34
  4697.1  190.18  4822.0  190.37  4860.3  190.85  4952.4  188.30  4961.7  183.86
  4962.2  183.36  4976.4  183.86  5015.1  185.54  5031.9  184.41  5037.3  186.88
  5047.6  186.56  5061.1  189.32  5100.9  190.61  5310.7  192.37  5313.5  192.41
  5398.0  194.39  5475.0  198.69  5524.1  203.19  5586.7  207.03  5643.4  209.98
#Mann=17,-1,0
  3610.5    0.04       0  3680.2    0.03       0  3812.3    0.04       0
  3881.8    0.03       0  3996.4   0.013       0  4158.8    0.12       0
  4585.4    0.05       0  4597.0    0.12       0  4697.1    0.05       0
  4822.0    0.12       0  4961.7    0.05       0  4976.4    0.12       0
  5100.9   0.013       0  5310.7    0.12       0  5313.5   0.013       0
  5524.1    0.04       0  5586.7   0.013       0
Bank Sta=4961.7,4976.4
Exp/Cntr=0.3,0.1

Type RM Length L Ch R = 1,12635,410,410,410
BEGIN DESCRIPTION:
BOGGY BRANCH 19.0
END DESCRIPTION:
XS GIS Cut Line= 3
      2515025.03     13533325.01      2513925.00     13532825.00
      2512724.99     13532625.00
#Sta/Elev= 30
  3791.6  205.03  3879.7  204.83  4148.9  203.55  4351.8  202.07  4425.4  200.46
  4472.5  199.60  4651.7  194.44  4659.4  195.06  4703.4  192.11  4772.6  189.63
  4813.2  189.14  4835.2  186.00  4848.7  187.78  4864.8  188.69  4893.4  188.03
  4945.0  188.61  5012.9  183.83  5013.4  183.33  5027.6  183.83  5027.8  184.72
  5032.9  185.71  5060.8  188.83  5200.3  190.44  5399.4  190.85  5492.3  190.97
  5547.4  191.27  5664.1  194.91  5879.4  206.87  5994.1  211.91  6216.5  219.25
#Mann=13,-1,0
  3791.6    0.04       0  3879.7    0.03       0  4148.9    0.05       0
  4425.4    0.12       0  4472.5    0.05       0  4848.7     0.1       0
  5012.9    0.05       0  5027.6     0.1       0  5200.3    0.05       0
  5399.4    0.12       0  5492.3    0.05       0  5664.1    0.12       0
  5994.1    0.04       0
Bank Sta=5012.9,5027.6
Exp/Cntr=0.3,0.1

Type RM Length L Ch R = 1,12225,480,480,480
BEGIN DESCRIPTION:
BOGGY BRANCH 18.0
END DESCRIPTION:
XS GIS Cut Line= 3
      2514525.01     13532675.00      2514275.00     13532675.00
      2513074.96     13531974.98
#Sta/Elev= 30
  4740.5  201.59  4750.9  201.45  4781.8  201.08  4880.5  199.98  4950.5  197.56
  4960.5  195.93  4970.5  191.05  4980.5  181.35  4981.0  180.85  4995.5  181.35
  4998.4  183.76  5000.6  183.94  5035.6  186.03  5041.4  185.65  5048.4  186.73
  5071.5  186.67  5100.1  184.98  5106.3  185.85  5121.6  185.64  5129.4  187.31
  5162.5  188.19  5291.5  190.03  5458.5  188.86  5569.4  190.12  5837.7  189.81
  5955.1  191.26  6002.3  192.82  6155.2  199.17  6287.4  205.22  6379.8  207.79
#Mann=11,-1,0
  4740.5    0.12       0  4750.9    0.05       0  4781.8    0.12       0
  4980.5    0.05       0  4995.5    0.12       0  5000.6     0.1       0
  5162.5    0.12       0  5458.5    0.05       0  6002.3    0.04       0
  6155.2    0.05       0  6287.4    0.04       0
Bank Sta=4980.5,4995.5
Exp/Cntr=0.3,0.1

Type RM Length L Ch R = 1,11745,480,480,480
BEGIN DESCRIPTION:
BOGGY BRANCH 17.0
END DESCRIPTION:
XS GIS Cut Line= 3
      2514424.97     13532374.98      2514225.00     13532275.00
      2513324.96     13531874.98
#Sta/Elev= 30
  4721.4  196.81  4743.7  196.39  4780.1  194.36  4855.5  192.86  4914.7  190.38
  4935.5  189.20  4936.6  189.20  4942.2  186.14  4947.7  186.14  4953.9  183.59
  4959.3  183.55  4966.9  179.74  4969.6  177.68  4970.1  177.18  4984.6  177.68
  5005.8  185.68  5029.1  187.19  5065.3  188.08  5098.2  187.64  5127.6  188.75
  5187.6  188.50  5208.7  188.20  5226.1  187.50  5272.6  188.84  5382.7  189.61
  5625.0  189.40  5672.0  189.93  5741.8  192.01  5831.4  197.47  5929.9  201.84
#Mann=8,-1,0
  4721.4    0.12       0  4914.7     0.1       0  4935.5    0.12       0
  4969.6    0.05       0  4984.6    0.12       0  5187.6    0.05       0
  5208.7    0.12       0  5625.0    0.05       0
Bank Sta=4969.6,4984.6
Exp/Cntr=0.3,0.1

Type RM Length L Ch R = 1,11265,519,519,519
BEGIN DESCRIPTION:
BOGGY BRANCH 16.0
END DESCRIPTION:
XS GIS Cut Line= 3
      2514724.98     13532224.98      2514175.00     13531825.00
      2513275.04     13531825.00
#Sta/Elev= 30
  4274.7  200.41  4313.0  199.09  4424.2  194.11  4560.2  189.90  4660.7  188.73
  4749.3  188.92  4836.1  187.52  4868.4  186.83  4957.2  185.68  4974.7  184.46
  4987.2  181.40  4987.7  180.90  5002.3  181.40  5004.7  182.05  5014.7  181.62
  5080.2  185.22  5094.7  185.78  5114.7  187.99  5144.7  188.83  5224.7  188.44
  5244.7  187.29  5284.7  188.74  5411.8  188.83  5524.7  189.81  5584.7  191.59
  5614.7  193.07  5674.7  197.94  5754.7  200.25  5814.7  203.53  5854.7  204.05
#Mann=9,-1,0
  4274.7    0.05       0  4313.0    0.12       0  4749.3    0.05       0
  4836.1    0.12       0  4868.4    0.05       0  4987.2    0.05       0
  5002.3    0.05       0  5080.2    0.12       0  5411.8    0.05       0
Bank Sta=4987.2,5002.3
Exp/Cntr=0.3,0.1

Type RM Length L Ch R = 1,10746,451,451,451
BEGIN DESCRIPTION:
BOGGY BRANCH 15.0
END DESCRIPTION:
XS GIS Cut Line= 3
      2514675.02     13531325.00      2514075.00     13531375.00
      2513475.01     13531775.00
#Sta/Elev= 30
  4508.1  196.79  4529.6  196.31  4628.5  192.50  4745.7  188.71  4829.2  186.27
  4925.2  186.50  4949.6  186.45  4969.7  180.27  4981.6  178.96  4982.1  178.46
  4997.9  178.96  4999.8  181.42  5019.9  183.80  5040.0  180.34  5047.5  183.05
  5060.0  184.08  5085.8  181.66  5100.2  180.02  5117.7  182.45  5153.8  182.06
  5159.8  180.35  5182.3  181.27  5195.8  184.01  5204.8  182.56  5210.9  185.78
  5246.2  186.56  5487.1  187.83  5628.1  189.59  5740.4  192.40  5831.3  198.22
#Mann=12,-1,0
  4508.1    0.04       0  4529.6    0.05       0  4628.5    0.04       0
  4745.7    0.05       0  4925.2    0.12       0  4981.6    0.05       0
  4997.9    0.12       0  5085.8    0.05       0  5246.2    0.12       0
  5487.1    0.05       0  5628.1    0.04       0  5740.4    0.05       0
Bank Sta=4981.6,4997.9
Exp/Cntr=0.3,0.1

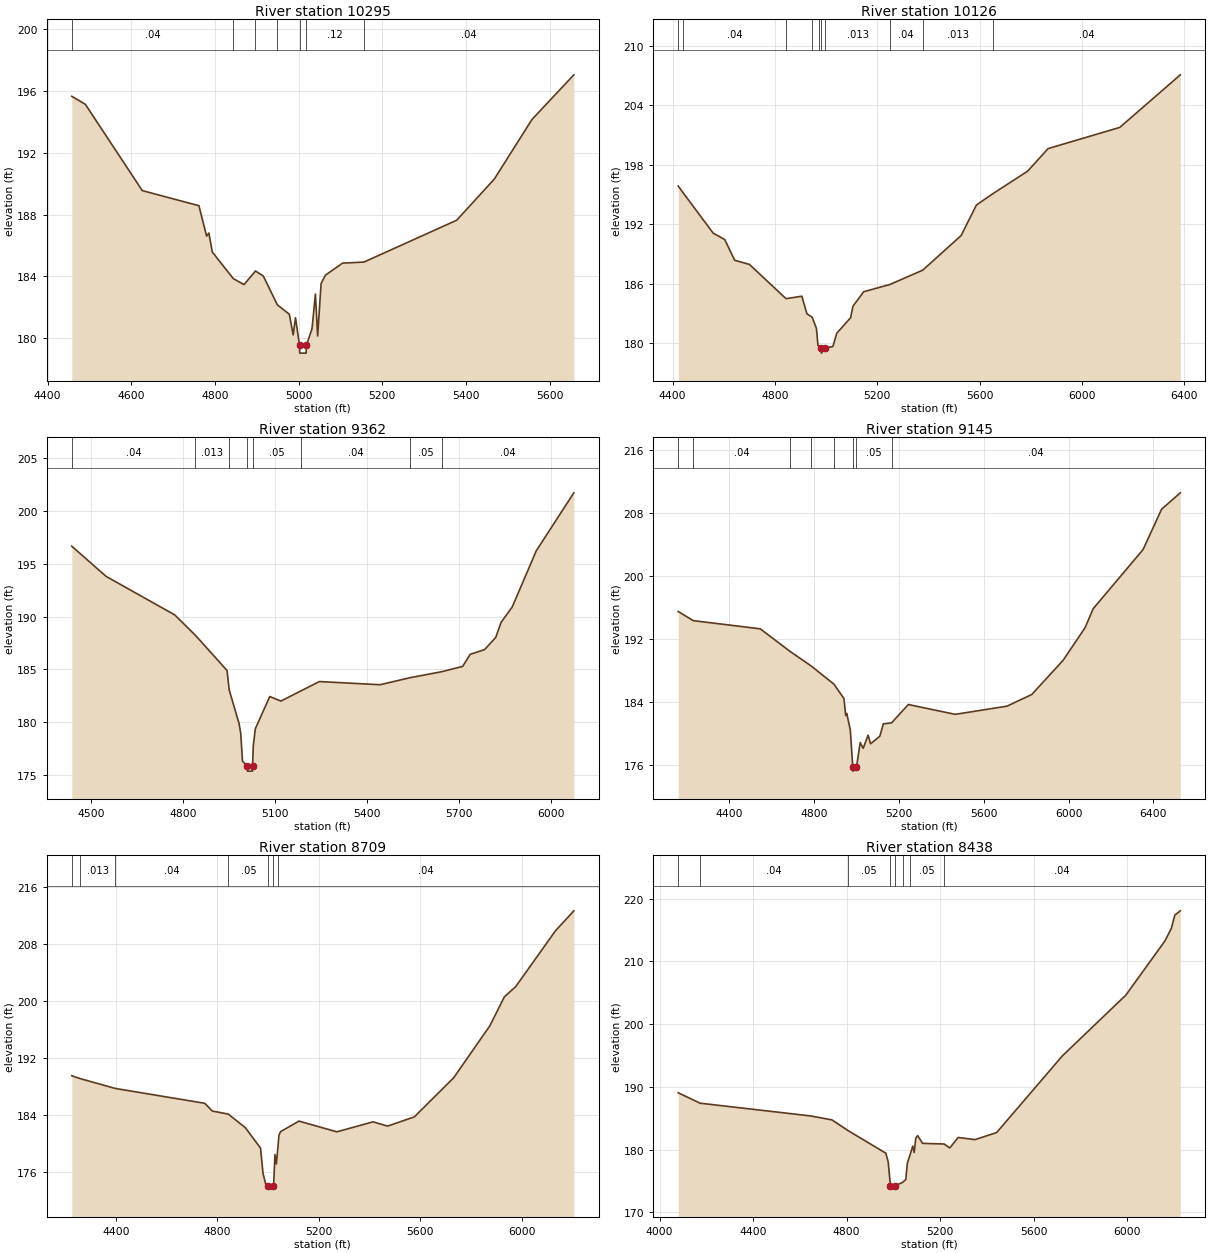
Type RM Length L Ch R = 1,10295,169,169,169
BEGIN DESCRIPTION:
BOGGY BRANCH 14.0
END DESCRIPTION:
XS GIS Cut Line= 3
      2514625.03     13531175.01      2514025.00     13530925.00
      2513475.04     13530925.00
#Sta/Elev= 30
  4457.9  195.66  4490.4  195.14  4626.4  189.55  4761.8  188.57  4780.2  186.60
  4785.6  186.80  4793.8  185.57  4843.9  183.85  4869.6  183.46  4897.0  184.34
  4915.6  184.02  4949.2  182.15  4977.9  181.54  4987.1  180.20  4992.6  181.31
  5002.3  179.52  5002.8  179.02  5018.1  179.02  5018.6  179.52  5032.1  180.60
  5040.2  182.85  5045.6  180.13  5053.8  183.53  5064.1  184.07  5105.2  184.85
  5156.3  184.92  5377.9  187.63  5467.9  190.30  5557.9  194.16  5657.9  197.05
#Mann=7,-1,0
  4457.9    0.04       0  4843.9    0.12       0  4897.0    0.05       0
  4949.2    0.12       0  5002.3    0.05       0  5018.6    0.12       0
  5156.3    0.04       0
Bank Sta=5002.3,5018.6
Exp/Cntr=0.3,0.1

Type RM Length L Ch R = 1,10126,764,764,764
BEGIN DESCRIPTION:
BOGGY BRANCH 13.0
END DESCRIPTION:
XS GIS Cut Line= 3
      2514675.03     13530975.01      2513974.60     13530750.00
      2512748.69     13530797.03
#Sta/Elev= 30
  4422.3  195.85  4440.8  195.19  4558.9  191.09  4604.2  190.44  4642.9  188.35
  4700.5  187.93  4843.7  184.47  4905.5  184.72  4925.2  182.95  4946.1  182.59
  4962.5  181.46  4968.5  179.75  4971.4  179.69  4981.2  179.47  4981.7  178.97
  4997.5  179.47  5026.7  179.64  5042.0  180.98  5096.2  182.55  5105.1  183.70
  5147.1  185.17  5249.5  185.90  5378.0  187.35  5527.9  190.84  5587.9  193.93
  5653.7  195.10  5788.1  197.35  5868.1  199.63  6148.3  201.77  6384.8  207.08
#Mann=10,-1,0
  4422.3    0.03       0  4440.8    0.04       0  4843.7    0.12       0
  4946.1    0.05       0  4971.4   0.013       0  4981.2    0.03       0
  4997.5   0.013       0  5249.5    0.04       0  5378.0   0.013       0
  5653.7    0.04       0
Bank Sta=4981.2,4997.5
Exp/Cntr=0.3,0.1

Type RM Length L Ch R = 1,9362,217,217,217
BEGIN DESCRIPTION:
BOGGY BRANCH 12.0
END DESCRIPTION:
XS GIS Cut Line= 3
      2514925.04     13530525.02      2514425.00     13530275.00
      2513424.99     13529875.00
#Sta/Elev= 30
  4436.8  196.68  4548.6  193.82  4772.3  190.17  4839.9  188.23  4942.8  184.90
  4949.8  183.06  4981.9  179.88  4987.5  178.92  4993.1  176.30  5008.7  175.86
  5009.2  175.36  5025.6  175.36  5026.1  175.86  5028.2  177.71  5034.9  179.37
  5082.0  182.43  5118.4  182.00  5185.2  182.99  5243.6  183.85  5441.5  183.55
  5539.5  184.22  5641.7  184.78  5710.7  185.29  5735.0  186.43  5782.1  186.88
  5818.4  188.04  5835.9  189.47  5872.3  190.93  5950.4  196.24  6072.9  201.74
#Mann=8,-1,0
  4436.8    0.04       0  4839.9   0.013       0  4949.8    0.05       0
  5008.7    0.05       0  5026.1    0.05       0  5185.2    0.04       0
  5539.5    0.05       0  5641.7    0.04       0
Bank Sta=5008.7,5026.1
Exp/Cntr=0.3,0.1

Type RM Length L Ch R = 1,9145,436,436,436
BEGIN DESCRIPTION:
Mapping XS 068ab7c2
END DESCRIPTION:
XS GIS Cut Line= 3
      2515307.57     13530199.94      2514422.13     13530064.52
      2513125.24     13529366.60
#Sta/Elev= 30
  4158.2  195.45  4229.2  194.29  4545.2  193.25  4685.9  190.38  4785.0  188.54
  4892.2  186.24  4939.8  184.40  4948.2  182.23  4953.2  182.51  4970.1  180.38
  4981.6  175.68  4982.1  175.18  4999.0  175.68  5016.7  178.81  5030.8  178.08
  5053.9  179.75  5065.6  178.65  5109.4  179.62  5125.6  181.18  5164.6  181.31
  5243.7  183.64  5464.8  182.39  5709.3  183.43  5825.9  184.91  5973.5  189.24
  6077.4  193.39  6115.5  195.80  6350.8  203.31  6438.5  208.44  6526.7  210.52
#Mann=8,-1,0
  4158.2    0.03       0  4229.2    0.04       0  4685.9   0.013       0
  4785.0    0.04       0  4892.2    0.05       0  4981.6    0.05       0
  4999.0    0.05       0  5164.6    0.04       0
Bank Sta=4981.6,4999
Exp/Cntr=0.3,0.1

Type RM Length L Ch R = 1,8709,271,271,271
BEGIN DESCRIPTION:
Mapping XS fd4af72d
END DESCRIPTION:
XS GIS Cut Line= 3
      2515099.24     13529684.32      2514307.55     13529694.73
      2513250.29     13529153.08
#Sta/Elev= 30
  4225.7  189.50  4258.6  189.10  4397.0  187.72  4750.0  185.64  4780.0  184.55
  4842.5  184.13  4910.0  182.23  4970.0  179.36  4980.0  175.78  4990.0  174.38
  5001.3  174.11  5001.8  173.61  5018.7  174.11  5021.7  174.23  5026.9  178.45
  5032.5  177.13  5037.1  178.94  5042.8  181.18  5049.1  181.67  5121.5  183.14
  5271.1  181.64  5413.6  183.04  5470.9  182.44  5576.3  183.73  5731.7  189.22
  5874.3  196.50  5931.5  200.56  5976.0  201.98  6132.7  209.80  6205.4  212.61
#Mann=7,-1,0
  4225.7    0.04       0  4258.6   0.013       0  4397.0    0.04       0
  4842.5    0.05       0  5001.3    0.05       0  5018.7    0.05       0
  5037.1    0.04       0
Bank Sta=5001.3,5018.7
Exp/Cntr=0.3,0.1

Type RM Length L Ch R = 1,8438,489,489,489
BEGIN DESCRIPTION:
Mapping XS 5591eade
END DESCRIPTION:
XS GIS Cut Line= 3
      2515192.95     13529470.77      2514281.51     13529444.73
      2513260.69     13528746.82
#Sta/Elev= 30
  4079.4  189.05  4173.1  187.39  4647.6  185.35  4737.6  184.72  4805.3  183.04
  4967.7  179.42  4977.7  178.05  4987.6  174.19  4988.1  173.69  5005.0  174.19
  5040.5  174.79  5053.2  175.23  5059.7  177.83  5070.3  179.03  5083.0  180.55
  5089.1  179.54  5096.0  181.83  5104.0  182.22  5125.0  180.99  5217.3  180.88
  5241.4  180.26  5277.4  181.93  5349.1  181.58  5441.9  182.71  5723.0  194.93
  5995.2  204.64  6162.0  213.26  6189.5  215.26  6204.4  217.39  6227.8  218.06
#Mann=8,-1,0
  4079.4   0.013       0  4173.1    0.04       0  4805.3    0.05       0
  4987.6    0.05       0  5005.0    0.05       0  5040.5     0.1       0
  5070.3    0.05       0  5217.3    0.04       0
Bank Sta=4987.6,5005
Exp/Cntr=0.3,0.1

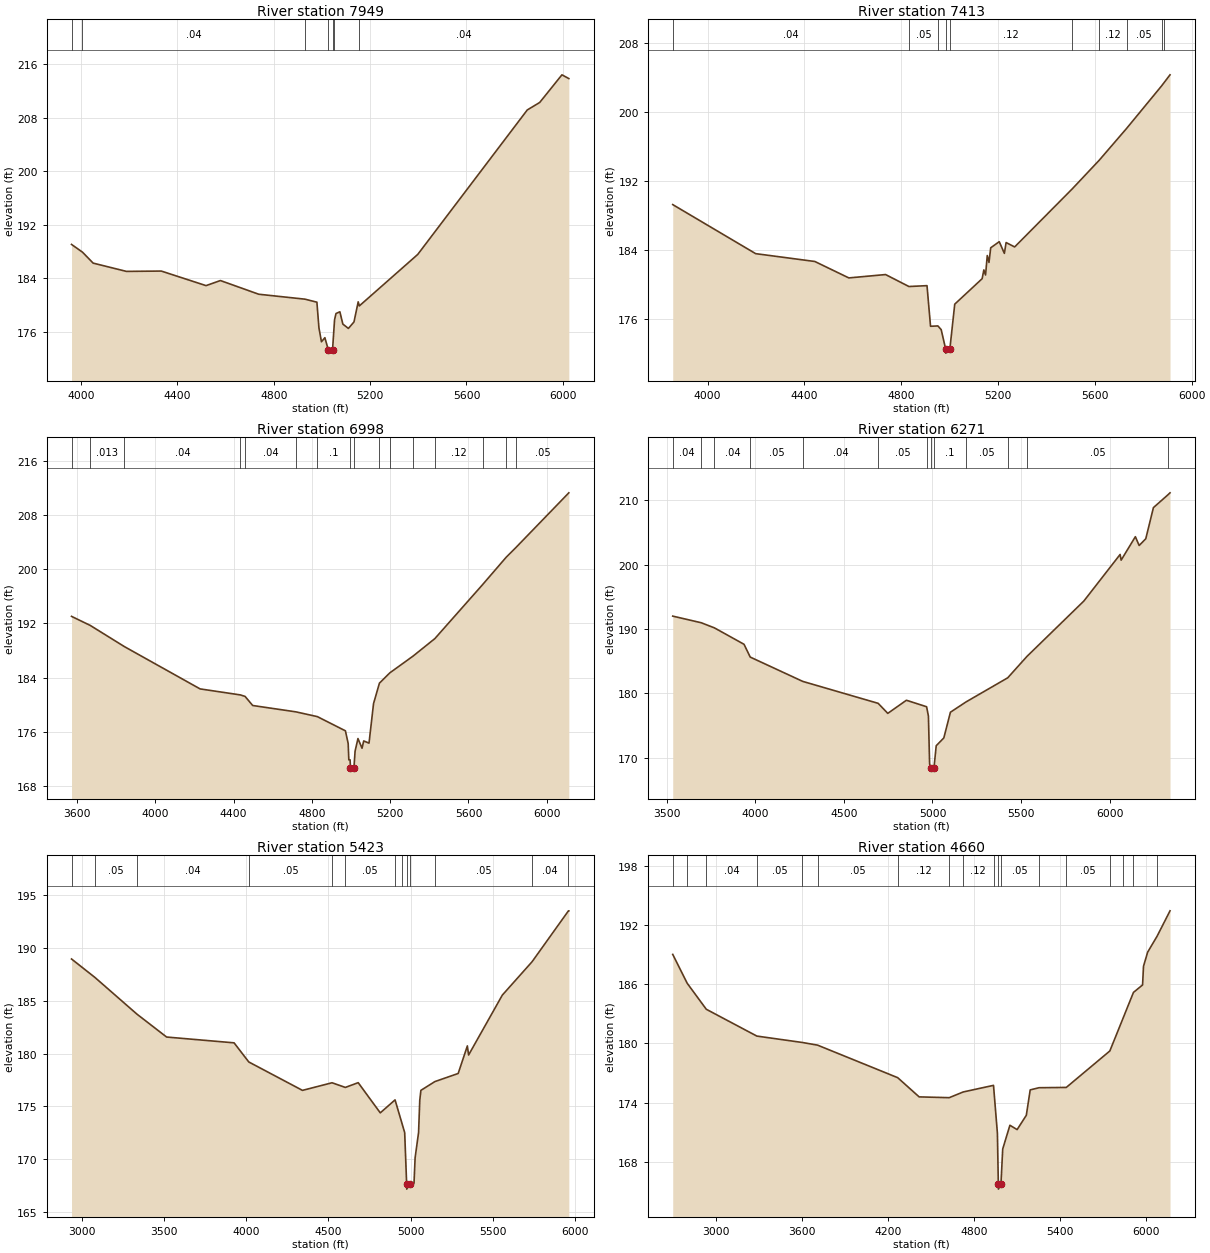
Type RM Length L Ch R = 1,7949,536,536,536
BEGIN DESCRIPTION:
Mapping XS 7b4a4604
END DESCRIPTION:
XS GIS Cut Line= 3
      2515271.13     13529272.87      2514265.88     13528981.19
      2513340.14     13528559.92
#Sta/Elev= 30
  3961.0  189.05  4006.5  187.89  4050.7  186.25  4188.9  185.01  4333.6  185.06
  4519.2  182.88  4578.9  183.64  4737.9  181.59  4929.9  180.85  4979.3  180.40
  4987.8  176.55  4998.2  174.47  5012.4  175.08  5026.6  173.27  5027.1  172.77
  5044.2  173.27  5048.8  175.73  5052.6  177.76  5058.5  178.70  5074.6  178.96
  5087.0  177.12  5110.1  176.47  5133.2  177.44  5150.7  180.45  5155.4  179.84
  5397.8  187.55  5852.4  209.19  5904.0  210.31  5996.2  214.45  6024.8  213.89
#Mann=7,-1,0
  3961.0   0.013       0  4006.5    0.04       0  4929.9     0.1       0
  5026.6    0.05       0  5044.2     0.1       0  5048.8    0.12       0
  5155.4    0.04       0
Bank Sta=5026.6,5044.2
Exp/Cntr=0.3,0.1

Type RM Length L Ch R = 1,7413,415,415,415
BEGIN DESCRIPTION:
Mapping XS e0379b8a
END DESCRIPTION:
XS GIS Cut Line= 3
      2515317.97     13529231.62      2514394.36     13528551.07
      2513749.24     13527912.89
#Sta/Elev= 30
  3855.9  189.24  4198.5  183.54  4442.9  182.63  4583.5  180.72  4735.3  181.11
  4831.8  179.72  4906.5  179.82  4921.1  175.10  4951.5  175.14  4965.1  174.71
  4983.3  172.48  4983.8  171.98  5001.0  172.48  5021.1  177.67  5134.3  180.63
  5141.4  181.65  5148.4  181.06  5155.5  183.32  5162.6  182.52  5169.7  184.22
  5205.0  184.93  5226.2  183.57  5233.3  184.83  5268.7  184.32  5507.1  191.08
  5617.9  194.39  5731.1  198.09  5875.4  203.02  5887.0  203.45  5910.6  204.32
#Mann=10,-1,0
  3855.9    0.04       0  4831.8    0.05       0  4951.5    0.12       0
  4983.3    0.04       0  5001.0    0.12       0  5507.1    0.05       0
  5617.9    0.12       0  5731.1    0.05       0  5875.4    0.03       0
  5887.0    0.05       0
Bank Sta=4983.3,5001
Exp/Cntr=0.3,0.1

Type RM Length L Ch R = 1,6998,727,727,727
BEGIN DESCRIPTION:
Mapping XS 2512698d
END DESCRIPTION:
XS GIS Cut Line= 3
      2515637.40     13529231.61      2514616.58     13528245.51
      2513708.45     13527586.95
#Sta/Elev= 30
  3571.7  193.04  3667.5  191.70  3841.5  188.58  4228.6  182.33  4435.0  181.44
  4458.5  181.22  4497.4  179.88  4718.5  178.94  4827.6  178.24  4971.3  176.14
  4985.4  174.25  4988.6  171.86  4995.1  171.86  4997.1  170.69  4997.6  170.19
  5014.9  170.69  5020.6  173.13  5035.3  175.00  5056.2  173.57  5064.7  174.65
  5091.8  174.32  5115.0  180.17  5145.1  183.18  5198.2  184.70  5317.2  187.18
  5428.4  189.76  5672.0  197.72  5793.4  201.79  5844.0  203.25  6112.8  211.28
#Mann=16,-1,0
  3571.7    0.04       0  3667.5   0.013       0  3841.5    0.04       0
  4435.0    0.05       0  4458.5    0.04       0  4718.5    0.05       0
  4827.6     0.1       0  4997.1    0.05       0  5014.9     0.1       0
  5145.1    0.04       0  5198.2     0.1       0  5317.2    0.05       0
  5428.4    0.12       0  5672.0    0.05       0  5793.4    0.03       0
  5844.0    0.05       0
Bank Sta=4997.1,5014.9
Exp/Cntr=0.3,0.1

Type RM Length L Ch R = 1,6271,848,848,848
BEGIN DESCRIPTION:
Mapping XS e7dda626
END DESCRIPTION:
XS GIS Cut Line= 3
      2515720.75     13529196.92      2515151.30     13527877.46
      2513963.85     13527189.99
#Sta/Elev= 30
  3532.7  192.01  3693.8  190.98  3768.4  190.18  3935.4  187.63  3970.5  185.64
  4267.3  181.86  4693.1  178.45  4747.6  176.89  4852.7  178.93  4966.8  177.92
  4977.1  176.46  4983.8  169.03  4990.6  168.41  4991.1  167.91  5008.4  168.41
  5021.1  171.86  5064.1  173.07  5101.4  177.07  5190.2  178.68  5425.2  182.42
  5533.5  185.74  5855.3  194.36  6060.0  201.60  6065.7  200.71  6146.1  204.36
  6167.6  202.99  6204.9  204.04  6248.1  208.88  6331.7  210.91  6341.9  211.18
#Mann=13,-1,0
  3532.7    0.04       0  3693.8   0.013       0  3768.4    0.04       0
  3970.5    0.05       0  4267.3    0.04       0  4693.1    0.05       0
  4966.8     0.1       0  4990.6    0.05       0  5008.4     0.1       0
  5190.2    0.05       0  5425.2    0.04       0  5533.5    0.05       0
  6331.7    0.03       0
Bank Sta=4990.6,5008.4
Exp/Cntr=0.3,0.1

Type RM Length L Ch R = 1,5423,763,763,763
BEGIN DESCRIPTION:
Mapping XS 1640d200
END DESCRIPTION:
XS GIS Cut Line= 4
      2515962.30     13529048.10      2516248.71     13528128.56
      2515923.82     13527570.56      2514972.46     13526515.03
#Sta/Elev= 30
  2934.5  188.96  3077.3  187.21  3332.9  183.74  3513.8  181.57  3924.9  181.02
  4014.5  179.21  4341.5  176.52  4521.7  177.24  4602.7  176.80  4681.1  177.25
  4815.6  174.39  4905.6  175.62  4948.1  173.38  4964.3  172.52  4976.2  167.67
  4976.7  167.17  4994.3  167.67  5021.1  167.73  5027.8  170.14  5048.9  172.53
  5056.2  175.58  5063.0  176.52  5147.9  177.35  5290.2  178.12  5346.2  180.73
  5353.7  179.87  5559.2  185.54  5740.4  188.70  5962.1  193.52  5964.3  193.52
#Mann=13,-1,0
  2934.5    0.04       0  3077.3    0.05       0  3332.9    0.04       0
  4014.5    0.05       0  4521.7    0.12       0  4602.7    0.05       0
  4905.6    0.12       0  4948.1     0.1       0  4976.2    0.05       0
  4994.3     0.1       0  5147.9    0.05       0  5740.4    0.04       0
  5962.1    0.05       0
Bank Sta=4976.2,4994.3
Exp/Cntr=0.3,0.1

Type RM Length L Ch R = 1,4660,470,470,470
BEGIN DESCRIPTION:
Mapping XS 4de588ba
END DESCRIPTION:
XS GIS Cut Line= 4
      2516090.43     13529040.55      2516666.59     13527704.47
      2516222.43     13526966.40      2515319.83     13526251.25
#Sta/Elev= 30
  2697.4  189.04  2798.3  186.11  2931.5  183.47  3284.0  180.75  3601.6  180.10
  3707.6  179.83  4266.2  176.53  4415.9  174.58  4625.4  174.50  4723.3  175.08
  4934.4  175.75  4961.6  170.89  4968.1  165.72  4968.6  165.22  4986.3  165.72
  4998.6  169.29  5048.8  171.70  5099.1  171.26  5163.2  172.71  5190.3  175.29
  5251.9  175.51  5442.0  175.54  5745.7  179.24  5836.7  182.52  5910.3  185.18
  5974.0  185.94  5980.4  187.83  6009.2  189.26  6075.0  190.88  6165.4  193.46
#Mann=18,-1,0
  2697.4    0.04       0  2798.3    0.05       0  2931.5    0.04       0
  3284.0    0.05       0  3601.6    0.04       0  3707.6    0.05       0
  4266.2    0.12       0  4625.4    0.05       0  4723.3    0.12       0
  4934.4    0.05       0  4968.1    0.05       0  4986.3    0.05       0
  5251.9    0.12       0  5442.0    0.05       0  5745.7   0.013       0
  5836.7    0.05       0  5910.3   0.013       0  6075.0    0.04       0
Bank Sta=4968.1,4986.3
Exp/Cntr=0.3,0.1

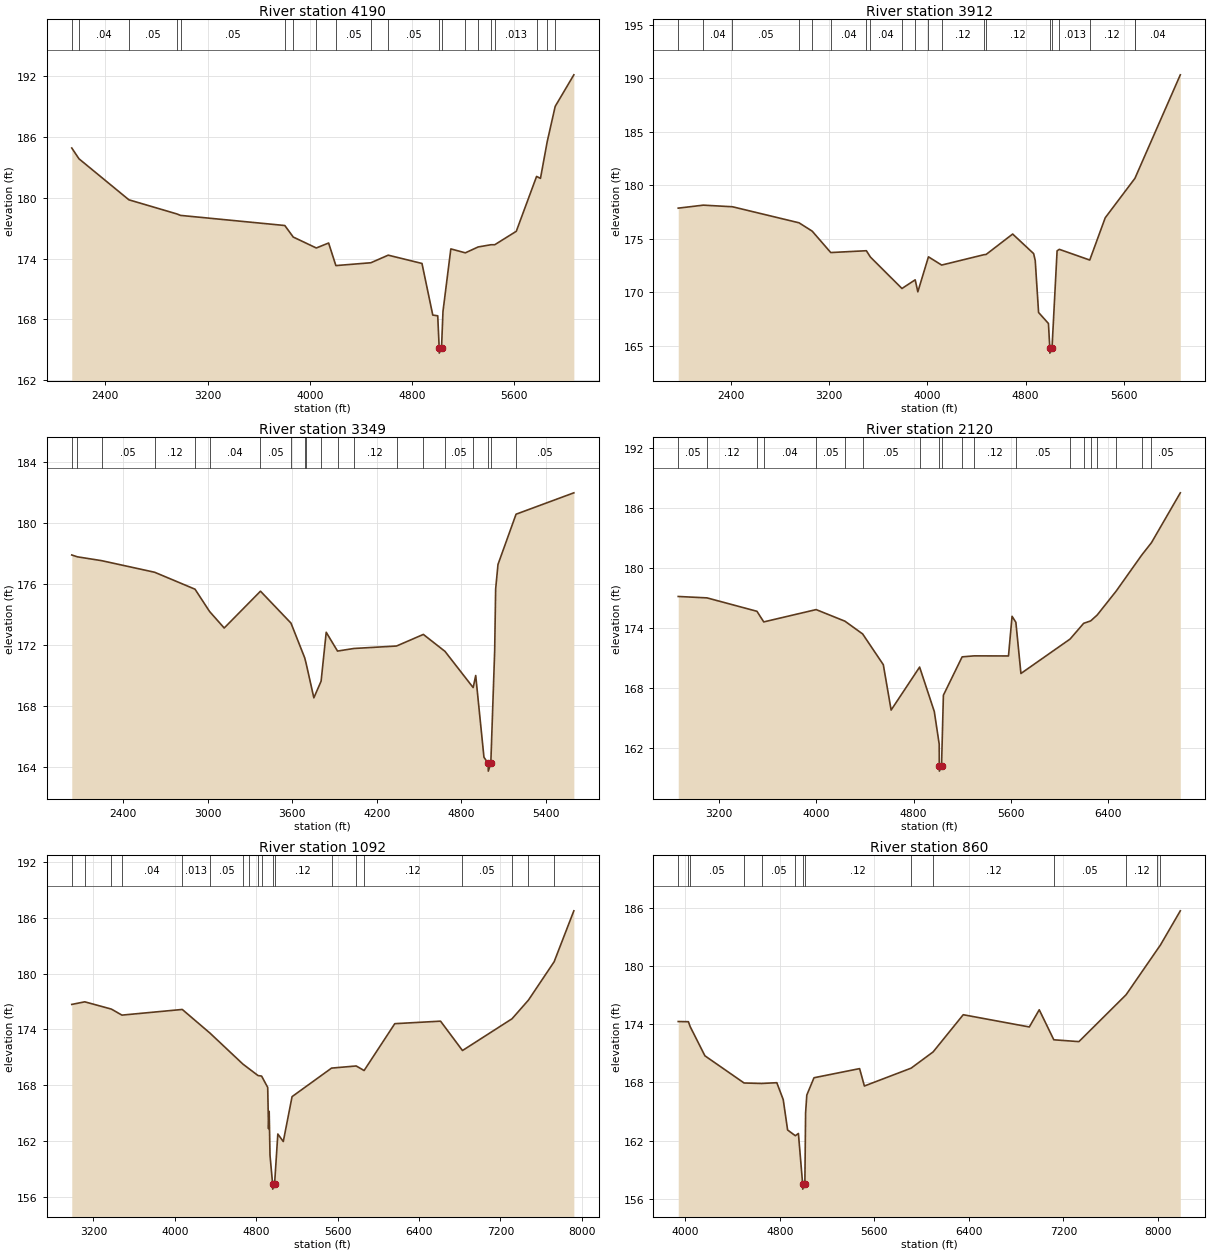
Type RM Length L Ch R = 1,4190,278,278,278
BEGIN DESCRIPTION:
Mapping XS f246a913
END DESCRIPTION:
XS GIS Cut Line= 5
      2516203.51     13528950.07      2517100.42     13527412.52
      2516397.23     13526620.36      2515694.66     13526466.40
      2515431.08     13526209.76
#Sta/Elev= 30
  2138.3  184.93  2194.9  183.86  2585.1  179.81  2961.3  178.41  2988.7  178.27
  3804.3  177.27  3870.3  176.13  4050.7  175.05  4147.0  175.54  4203.7  173.31
  4477.4  173.59  4613.1  174.34  4877.1  173.52  4961.5  168.42  5000.3  168.35
  5011.7  165.16  5012.2  164.66  5029.9  165.16  5041.3  168.78  5102.7  174.96
  5216.1  174.57  5316.2  175.15  5416.2  175.37  5446.0  175.37  5614.6  176.70
  5773.3  182.12  5803.7  181.93  5856.5  185.56  5918.8  189.04  6064.7  192.16
#Mann=20,-1,0
  2138.3    0.05       0  2194.9    0.04       0  2585.1    0.05       0
  2961.3    0.04       0  2988.7    0.05       0  3804.3    0.12       0
  3870.3    0.05       0  4050.7    0.12       0  4203.7    0.05       0
  4477.4    0.12       0  4613.1    0.05       0  5011.7    0.05       0
  5029.9    0.05       0  5216.1    0.12       0  5316.2    0.05       0
  5416.2    0.12       0  5446.0   0.013       0  5773.3    0.05       0
  5856.5   0.013       0  5918.8    0.04       0
Bank Sta=5011.7,5029.9
Exp/Cntr=0.3,0.1

Type RM Length L Ch R = 1,3912,563,563,563
BEGIN DESCRIPTION:
Mapping XS ede60d4a
END DESCRIPTION:
XS GIS Cut Line= 6
      2516648.21     13528369.71      2517530.04     13527148.72
      2517277.99     13526535.84      2516771.05     13526390.01
      2515909.93     13526306.67      2515472.41     13526014.99
#Sta/Elev= 30
  1972.9  177.87  2177.4  178.15  2414.2  178.00  2956.3  176.50  3063.5  175.72
  3214.5  173.72  3504.5  173.89  3537.3  173.30  3794.2  170.36  3901.9  171.17
  3923.5  170.05  4009.8  173.32  4117.6  172.55  4462.3  173.52  4479.2  173.54
  4695.4  175.45  4866.2  173.62  4879.1  172.98  4906.4  168.12  4986.7  167.09
  4997.7  164.82  4998.2  164.32  5015.9  164.82  5057.1  173.88  5075.2  174.02
  5323.0  173.02  5448.9  176.97  5689.7  180.64  5690.9  180.66  6060.2  190.33
#Mann=20,-1,0
  1972.9    0.05       0  2177.4    0.04       0  2414.2    0.05       0
  2956.3    0.12       0  3063.5    0.05       0  3214.5    0.04       0
  3504.5    0.05       0  3537.3    0.04       0  3794.2    0.05       0
  3901.9   0.013       0  4009.8    0.05       0  4117.6    0.12       0
  4462.3    0.05       0  4479.2    0.12       0  4997.7    0.05       0
  5015.9    0.12       0  5075.2   0.013       0  5323.0    0.12       0
  5689.7    0.05       0  5690.9    0.04       0
Bank Sta=4997.7,5015.9
Exp/Cntr=0.3,0.1

Type RM Length L Ch R = 1,3349,1229,1229,1229
BEGIN DESCRIPTION:
Mapping XS bdb53778
END DESCRIPTION:
XS GIS Cut Line= 6
      2516821.55     13528218.99      2517650.64     13527050.73
      2517313.19     13526481.23      2517243.27     13526452.51
      2516916.88     13526306.67      2516507.14     13525355.25
#Sta/Elev= 30
  2035.3  177.91  2075.2  177.79  2246.6  177.54  2623.5  176.78  2910.2  175.67
  3013.5  174.21  3117.2  173.13  3374.7  175.54  3591.2  173.45  3688.5  171.18
  3699.0  170.80  3753.5  168.56  3805.0  169.65  3841.2  172.85  3921.5  171.62
  4038.1  171.79  4340.3  171.95  4530.7  172.71  4684.3  171.60  4884.2  169.23
  4902.3  170.02  4960.8  164.67  4991.1  164.26  4991.6  163.76  5009.4  164.26
  5036.9  171.63  5043.8  175.68  5060.4  177.29  5188.7  180.58  5598.8  181.98
#Mann=20,-1,0
  2035.3    0.05       0  2075.2    0.04       0  2246.6    0.05       0
  2623.5    0.12       0  2910.2    0.05       0  3013.5    0.04       0
  3374.7    0.05       0  3591.2    0.04       0  3688.5   0.013       0
  3699.0    0.04       0  3805.0   0.013       0  3921.5    0.05       0
  4038.1    0.12       0  4340.3    0.05       0  4530.7    0.12       0
  4684.3    0.05       0  4884.2    0.12       0  4991.1    0.05       0
  5009.4    0.12       0  5188.7    0.05       0
Bank Sta=4991.1,5009.4
Exp/Cntr=0.3,0.1

Type RM Length L Ch R = 1,2120,1028,1028,1028
BEGIN DESCRIPTION:
Mapping XS 75fa139b
END DESCRIPTION:
XS GIS Cut Line= 5
      2516994.88     13528053.21      2517756.16     13526975.36
      2517632.16     13526390.01      2517695.75     13525799.54
      2516293.94     13525000.61
#Sta/Elev= 30
  2865.8  177.13  3102.2  176.99  3512.6  175.65  3568.4  174.59  3998.8  175.82
  4235.9  174.66  4380.9  173.39  4550.8  170.32  4615.1  165.79  4849.1  170.08
  4969.8  165.64  5010.0  162.39  5010.9  160.19  5011.4  159.69  5029.2  160.19
  5044.5  167.27  5198.5  171.10  5297.3  171.20  5579.3  171.19  5608.7  175.15
  5640.0  174.55  5681.6  169.44  6085.6  172.88  6197.0  174.45  6254.8  174.69
  6308.3  175.28  6464.3  177.67  6673.8  181.26  6753.9  182.50  6991.1  187.48
#Mann=20,-1,0
  2865.8    0.05       0  3102.2    0.12       0  3512.6    0.05       0
  3568.4    0.04       0  3998.8    0.05       0  4235.9   0.013       0
  4380.9    0.05       0  4849.1    0.12       0  5010.9    0.05       0
  5029.2    0.12       0  5198.5   0.013       0  5297.3    0.12       0
  5640.0    0.05       0  6085.6   0.013       0  6197.0    0.04       0
  6254.8   0.013       0  6308.3    0.04       0  6464.3   0.013       0
  6673.8   0.013       0  6753.9    0.05       0
Bank Sta=5010.9,5029.2
Exp/Cntr=0.3,0.1

Type RM Length L Ch R = 1,1092,232,232,232
BEGIN DESCRIPTION:
BOGGY BRANCH 2.0
END DESCRIPTION:
XS GIS Cut Line= 5
      2517130.58     13527909.96      2518244.37     13526850.09
      2518575.00     13526425.00      2518097.16     13525564.89
      2516376.87     13524819.72
#Sta/Elev= 30
  2987.4  176.69  3115.1  176.97  3376.2  176.19  3480.4  175.54  4073.5  176.15
  4346.4  173.60  4669.7  170.27  4731.1  169.76  4818.0  169.04  4853.3  168.98
  4913.2  167.76  4921.3  163.32  4927.7  165.19  4935.8  160.46  4961.9  157.32
  4962.4  156.82  4980.4  157.32  5012.7  162.75  5066.3  161.94  5152.6  166.77
  5540.8  169.84  5783.0  170.07  5860.7  169.58  6162.2  174.62  6612.0  174.89
  6827.7  171.73  7314.8  175.15  7475.5  177.15  7728.4  181.28  7922.1  186.76
#Mann=19,-1,0
  2987.4    0.05       0  3115.1    0.12       0  3376.2    0.05       0
  3480.4    0.04       0  4073.5   0.013       0  4346.4    0.05       0
  4669.7    0.04       0  4731.1    0.05       0  4818.0    0.04       0
  4853.3    0.12       0  4961.9    0.05       0  4980.4    0.12       0
  5540.8   0.013       0  5783.0    0.05       0  5860.7    0.12       0
  6827.7    0.05       0  7314.8    0.04       0  7475.5    0.05       0
  7728.4    0.12       0
Bank Sta=4961.9,4980.4
Exp/Cntr=0.3,0.1

Type RM Length L Ch R = 1,860,0,0,0
BEGIN DESCRIPTION:
BOGGY BRANCH 1.0
END DESCRIPTION:
XS GIS Cut Line= 4
      2518141.46     13527130.95      2518782.67     13526733.18
      2518599.83     13525683.01      2516428.74     13524598.55
#Sta/Elev= 30
  3941.6  174.27  4027.6  174.25  4042.9  173.74  4167.3  170.74  4498.6  167.94
  4646.6  167.89  4775.5  167.97  4829.8  166.23  4866.9  163.10  4932.2  162.51
  4958.2  162.74  4994.3  157.51  4994.8  157.01  5012.8  157.51  5019.1  164.87
  5029.3  166.70  5090.2  168.48  5475.9  169.42  5516.5  167.63  5912.1  169.47
  6097.8  171.14  6352.6  174.97  6911.7  173.71  6995.6  175.48  7118.8  172.39
  7331.1  172.20  7730.5  177.03  7992.3  181.65  8020.4  182.14  8189.0  185.67
#Mann=14,-1,0
  3941.6    0.05       0  4027.6   0.013       0  4042.9    0.05       0
  4498.6    0.04       0  4646.6    0.05       0  4932.2    0.12       0
  4994.3    0.05       0  5012.8    0.12       0  5912.1    0.05       0
  6097.8    0.12       0  7118.8    0.05       0  7730.5    0.12       0
  7992.3    0.05       0  8020.4    0.12       0
Bank Sta=4994.3,5012.8
Exp/Cntr=0.3,0.1

Chan Stop Cuts=-1