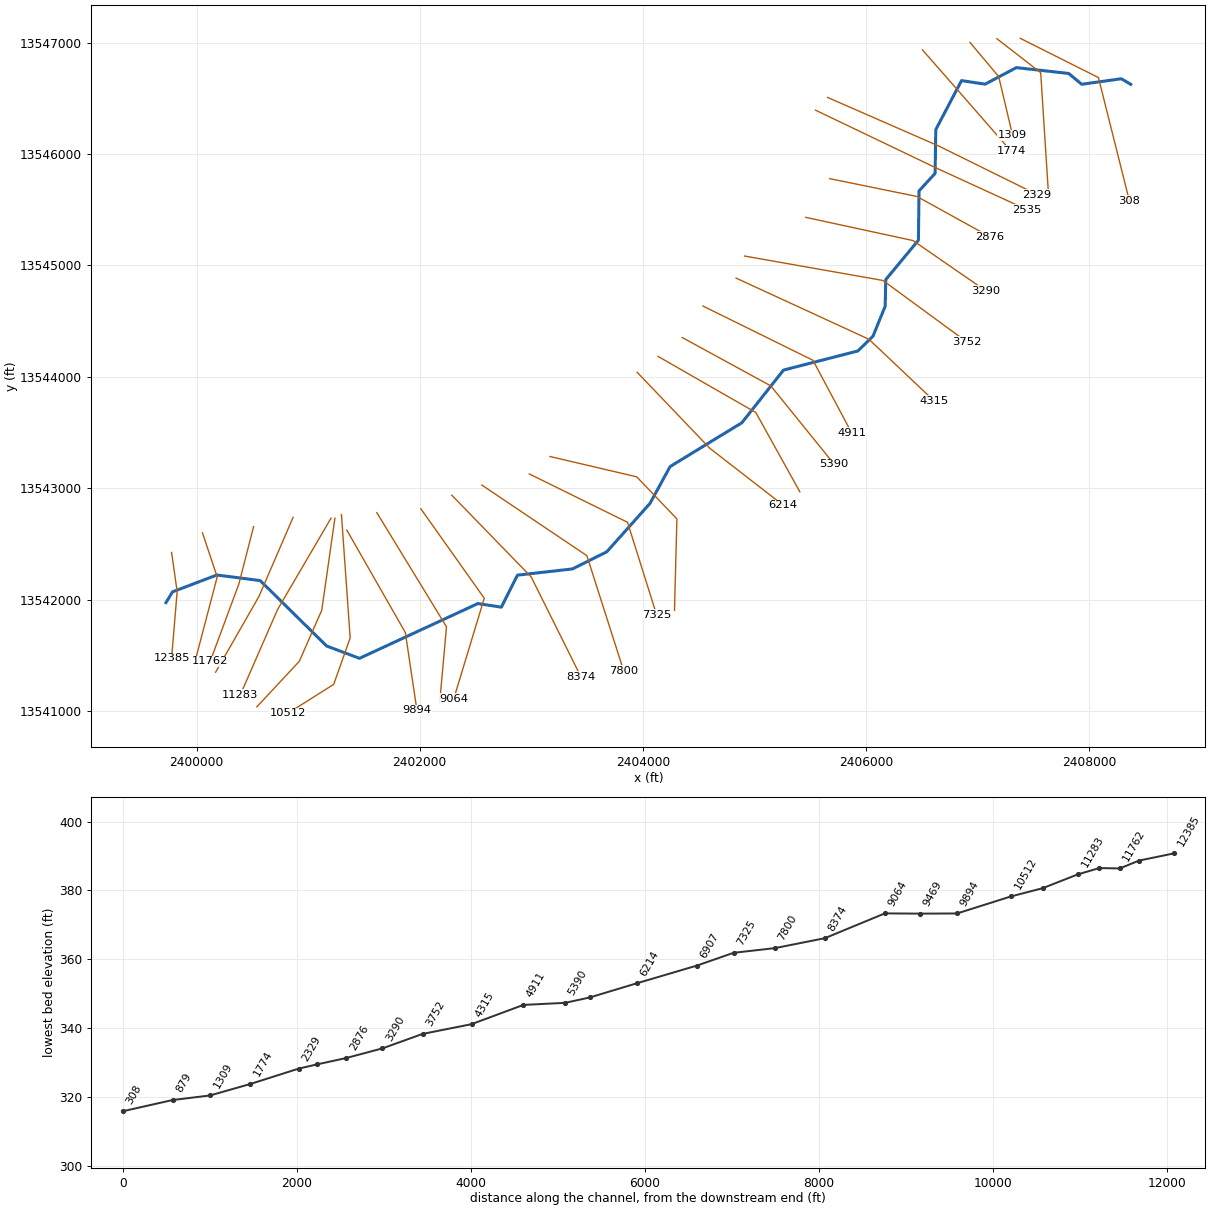
--- BUTLER CREEK.prj (project) ---

Proj Title=BUTLER CREEK Base Level Engineering
Current Plan=p01
Default Exp/Contr=0.3,0.1
English Units
Geom File=g01
Flow File=f01
Plan File=p01
BEGIN DESCRIPTION:
BUTLER CREEK
END DESCRIPTION:

--- BUTLER CREEK.p01 (plan) ---

Plan Title=Multiple Run
Short Identifier=Multiple
Geom File=g01
Flow File=f01
Subcritical Flow
K Sum by GR= 0
Std Step Tol= 0.01
Critical Tol= 0.01
Num of Std Step Trials= 20
Max Error Tol= 0.3
Flow Tol Ratio= 0.001
Split Flow NTrial= 30
Split Flow Tol= 0.02
Split Flow Ratio= 0.02
Log Output Level= 0
Friction Slope Method= 1
Unsteady Friction Slope Method= 2
Unsteady Bridges Friction Slope Method= 1
Parabolic Critical Depth
Global Vel Dist=  1 , 1 , 1
Global Log Level= 0
CheckData=True
Encroach Param= -1, 0, 0, 0
BEGIN DESCRIPTION:
Multiple Run
END DESCRIPTION:

--- BUTLER CREEK.f01 (steady flow) ---

Flow Title=Multiple
Number of Profiles=7
Profile Names=10-year,25-year,50-year,1pct_min,100-year,1pct_plu,500-year
River Rch & RM= BUTLER CREEK,Reach-1,12385
     507     812    1084     701    1399    2791    2305
River Rch & RM= BUTLER CREEK,Reach-1,9894
     757    1243    1687    1107    2209    4408    3755
River Rch & RM= BUTLER CREEK,Reach-1,9469
     911    1509    2061    1361    2715    5417    4667
River Rch & RM= BUTLER CREEK,Reach-1,6214
    1320    2224    3073    2050    4089    8160    7179
River Rch & RM= BUTLER CREEK,Reach-1,3290
    1510    2561    3554    2380    4748    9474    8403
Boundary for River Rch & Prof#=BUTLER CREEK,Reach-1,1
Up Type=0
Dn Type=3
Dn Slope=0.005
Boundary for River Rch & Prof#=BUTLER CREEK,Reach-1,2
Up Type=0
Dn Type=3
Dn Slope=0.005
Boundary for River Rch & Prof#=BUTLER CREEK,Reach-1,3
Up Type=0
Dn Type=3
Dn Slope=0.005
Boundary for River Rch & Prof#=BUTLER CREEK,Reach-1,4
Up Type=0
Dn Type=3
Dn Slope=0.005
Boundary for River Rch & Prof#=BUTLER CREEK,Reach-1,5
Up Type=0
Dn Type=3
Dn Slope=0.005
Boundary for River Rch & Prof#=BUTLER CREEK,Reach-1,6
Up Type=0
Dn Type=3
Dn Slope=0.005
Boundary for River Rch & Prof#=BUTLER CREEK,Reach-1,7
Up Type=0
Dn Type=3
Dn Slope=0.005

--- BUTLER CREEK.g01 (geometry) ---

Geom Title=Existing Conditions

River Reach=BUTLER CREEK,Reach-1
Reach XY= 30
      2399725.00     13541975.00      2399783.34     13542071.57
      2400180.93     13542222.76      2400569.14     13542172.93
      2401165.32     13541585.76      2401459.61     13541475.09
      2402521.77     13541966.76      2402731.75     13541934.14
      2402876.44     13542221.46      2403369.07     13542277.25
      2403677.30     13542430.83      2404064.37     13542865.00
      2404245.15     13543195.91      2404888.22     13543588.62
      2405261.78     13544061.38      2405928.34     13544232.99
      2406064.24     13544365.31      2406173.78     13544635.50
      2406178.54     13544873.54      2406471.45     13545226.47
      2406477.00     13545669.32      2406621.26     13545826.52
      2406627.24     13546219.07      2406857.94     13546658.94
      2407069.11     13546626.97      2407350.00     13546775.40
      2407819.14     13546722.93      2407935.44     13546626.04
      2408290.17     13546675.41      2408375.00     13546625.00

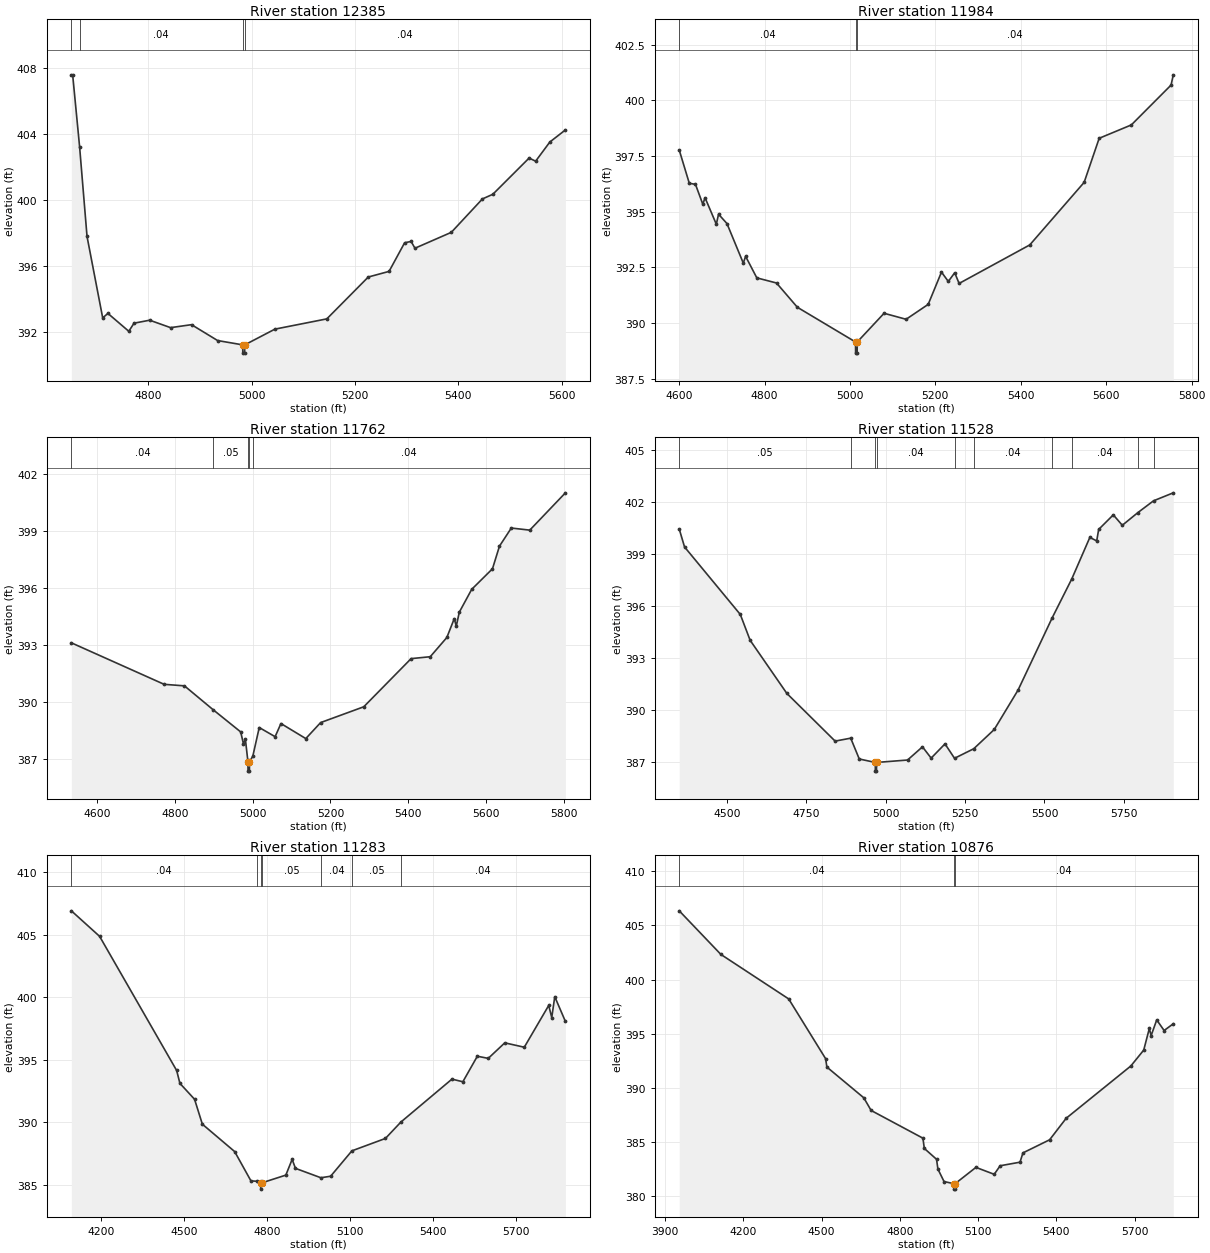
Type RM Length L Ch R = 1,12385,401,401,401
BEGIN DESCRIPTION:
BUTLER CREEK 26.0
END DESCRIPTION:
XS GIS Cut Line= 3
      2399775.00     13542425.02      2399825.00     13542075.00
      2399775.00     13541475.05
#Sta/Elev= 30
  4651.5  407.56  4654.0  407.56  4667.4  403.22  4681.8  397.79  4712.1  392.87
  4722.2  393.14  4762.6  392.06  4772.7  392.55  4803.0  392.73  4843.4  392.28
  4883.9  392.46  4934.4  391.50  4982.9  391.24  4983.1  390.74  4986.6  390.74
  4986.9  391.24  5045.2  392.19  5145.6  392.81  5225.8  395.34  5266.0  395.68
  5296.1  397.41  5308.6  397.49  5316.1  397.08  5386.4  398.04  5446.6  400.06
  5466.7  400.34  5536.9  402.53  5549.5  402.34  5577.0  403.50  5607.1  404.23
#Mann=4,-1,0
  4651.5    0.03       0  4667.4    0.04       0  4982.9    0.04       0
  4986.9    0.04       0
Bank Sta=4982.9,4986.9
Exp/Cntr=0.3,0.1

Type RM Length L Ch R = 1,11984,222,222,222
BEGIN DESCRIPTION:
Mapping XS b5e6e7b4
END DESCRIPTION:
XS GIS Cut Line= 3
      2400052.13     13542601.02      2400184.06     13542205.21
      2399996.58     13541489.99
#Sta/Elev= 30
  4600.4  397.77  4623.9  396.28  4638.4  396.23  4655.5  395.34  4660.8  395.63
  4687.2  394.44  4692.4  394.89  4712.1  394.47  4750.4  392.69  4755.7  393.00
  4782.0  392.03  4828.1  391.80  4876.9  390.71  5013.1  389.15  5013.3  388.65
  5016.8  388.65  5017.1  389.15  5079.9  390.44  5131.5  390.17  5183.2  390.84
  5214.3  392.29  5230.3  391.87  5245.3  392.26  5255.6  391.78  5421.0  393.51
  5548.3  396.32  5583.5  398.30  5658.8  398.90  5751.8  400.69  5757.0  401.15
#Mann=3,-1,0
  4600.4    0.04       0  5013.1    0.04       0  5017.1    0.04       0
Bank Sta=5013.1,5017.1
Exp/Cntr=0.3,0.1

Type RM Length L Ch R = 1,11762,234,234,234
BEGIN DESCRIPTION:
Mapping XS a2157f80
END DESCRIPTION:
XS GIS Cut Line= 3
      2400510.45     13542656.59      2400378.51     13542142.71
      2400121.88     13541449.12
#Sta/Elev= 30
  4534.0  393.11  4772.5  390.93  4824.7  390.85  4898.8  389.59  4969.3  388.43
  4976.3  387.81  4981.4  388.04  4987.9  386.87  4988.2  386.37  4991.7  386.37
  4991.9  386.87  5000.4  387.15  5017.0  388.66  5057.8  388.18  5072.8  388.87
  5136.7  388.08  5174.8  388.92  5285.7  389.75  5407.4  392.28  5456.6  392.38
  5499.3  393.39  5518.3  394.38  5523.6  393.99  5531.3  394.72  5563.2  395.92
  5616.6  397.00  5634.6  398.19  5665.0  399.14  5712.5  399.03  5804.1  400.99
#Mann=5,-1,0
  4534.0    0.04       0  4898.8    0.05       0  4987.9    0.05       0
  4991.9    0.05       0  5000.4    0.04       0
Bank Sta=4987.9,4991.9
Exp/Cntr=0.3,0.1

Type RM Length L Ch R = 1,11528,245,245,245
BEGIN DESCRIPTION:
Mapping XS 22b1fcb5
END DESCRIPTION:
XS GIS Cut Line= 3
      2400864.63     13542739.94      2400559.06     13542031.60
      2400170.16     13541351.02
#Sta/Elev= 30
  4350.3  400.44  4367.0  399.41  4542.5  395.52  4573.5  394.03  4689.0  390.97
  4841.0  388.22  4890.1  388.39  4917.0  387.19  4967.5  386.99  4967.7  386.49
  4971.2  386.49  4971.5  386.99  5069.0  387.13  5116.0  387.89  5143.3  387.24
  5186.9  388.06  5216.9  387.23  5277.4  387.78  5342.0  388.89  5416.9  391.16
  5524.2  395.32  5586.1  397.57  5642.9  399.96  5664.5  399.76  5670.7  400.42
  5716.7  401.26  5745.1  400.66  5794.1  401.39  5843.4  402.07  5905.6  402.53
#Mann=10,-1,0
  4350.3    0.05       0  4890.1    0.04       0  4967.5    0.04       0
  4971.5    0.04       0  5216.9   0.013       0  5277.4    0.04       0
  5524.2   0.013       0  5586.1    0.04       0  5794.1   0.013       0
  5843.4    0.04       0
Bank Sta=4967.5,4971.5
Exp/Cntr=0.3,0.1

Type RM Length L Ch R = 1,11283,407,407,407
BEGIN DESCRIPTION:
Mapping XS 1a70a20e
END DESCRIPTION:
XS GIS Cut Line= 3
      2401204.87     13542732.94      2400725.73     13541913.54
      2400392.46     13541149.80
#Sta/Elev= 30
  4094.4  406.90  4196.3  404.86  4474.3  394.14  4486.1  393.11  4538.9  391.84
  4567.0  389.85  4683.6  387.66  4742.3  385.32  4762.4  385.29  4777.4  385.16
  4777.7  384.66  4781.4  385.16  4868.2  385.78  4891.0  387.04  4902.9  386.32
  4994.6  385.57  5029.8  385.69  5106.6  387.72  5227.5  388.71  5283.3  390.02
  5467.5  393.45  5506.9  393.24  5559.1  395.28  5598.5  395.11  5658.2  396.35
  5728.5  396.00  5816.7  399.34  5827.6  398.37  5838.5  400.04  5876.9  398.06
#Mann=7,-1,0
  4094.4    0.04       0  4762.4    0.05       0  4777.4    0.04       0
  4781.4    0.05       0  4994.6    0.04       0  5106.6    0.05       0
  5283.3    0.04       0
Bank Sta=4777.4,4781.4
Exp/Cntr=0.3,0.1

Type RM Length L Ch R = 1,10876,364,364,364
BEGIN DESCRIPTION:
Mapping XS 67020ebf
END DESCRIPTION:
XS GIS Cut Line= 4
      2401239.62     13542732.96      2401121.56     13541906.60
      2400920.17     13541448.26      2400539.81     13541040.23
#Sta/Elev= 30
  3954.8  406.35  4114.4  402.32  4374.1  398.21  4515.6  392.69  4520.6  391.91
  4662.0  389.07  4690.1  387.90  4888.5  385.34  4894.0  384.39  4940.7  383.39
  4946.1  382.48  4969.5  381.33  5007.8  381.13  5008.0  380.63  5011.5  380.63
  5011.8  381.13  5091.7  382.64  5161.8  382.00  5184.5  382.79  5260.6  383.12
  5271.9  383.98  5374.1  385.19  5437.6  387.18  5685.3  392.01  5734.7  393.48
  5756.2  395.48  5763.0  394.81  5784.5  396.27  5812.8  395.29  5848.0  395.91
#Mann=3,-1,0
  3954.8    0.04       0  5007.8    0.04       0  5011.8    0.04       0
Bank Sta=5007.8,5011.8
Exp/Cntr=0.3,0.1

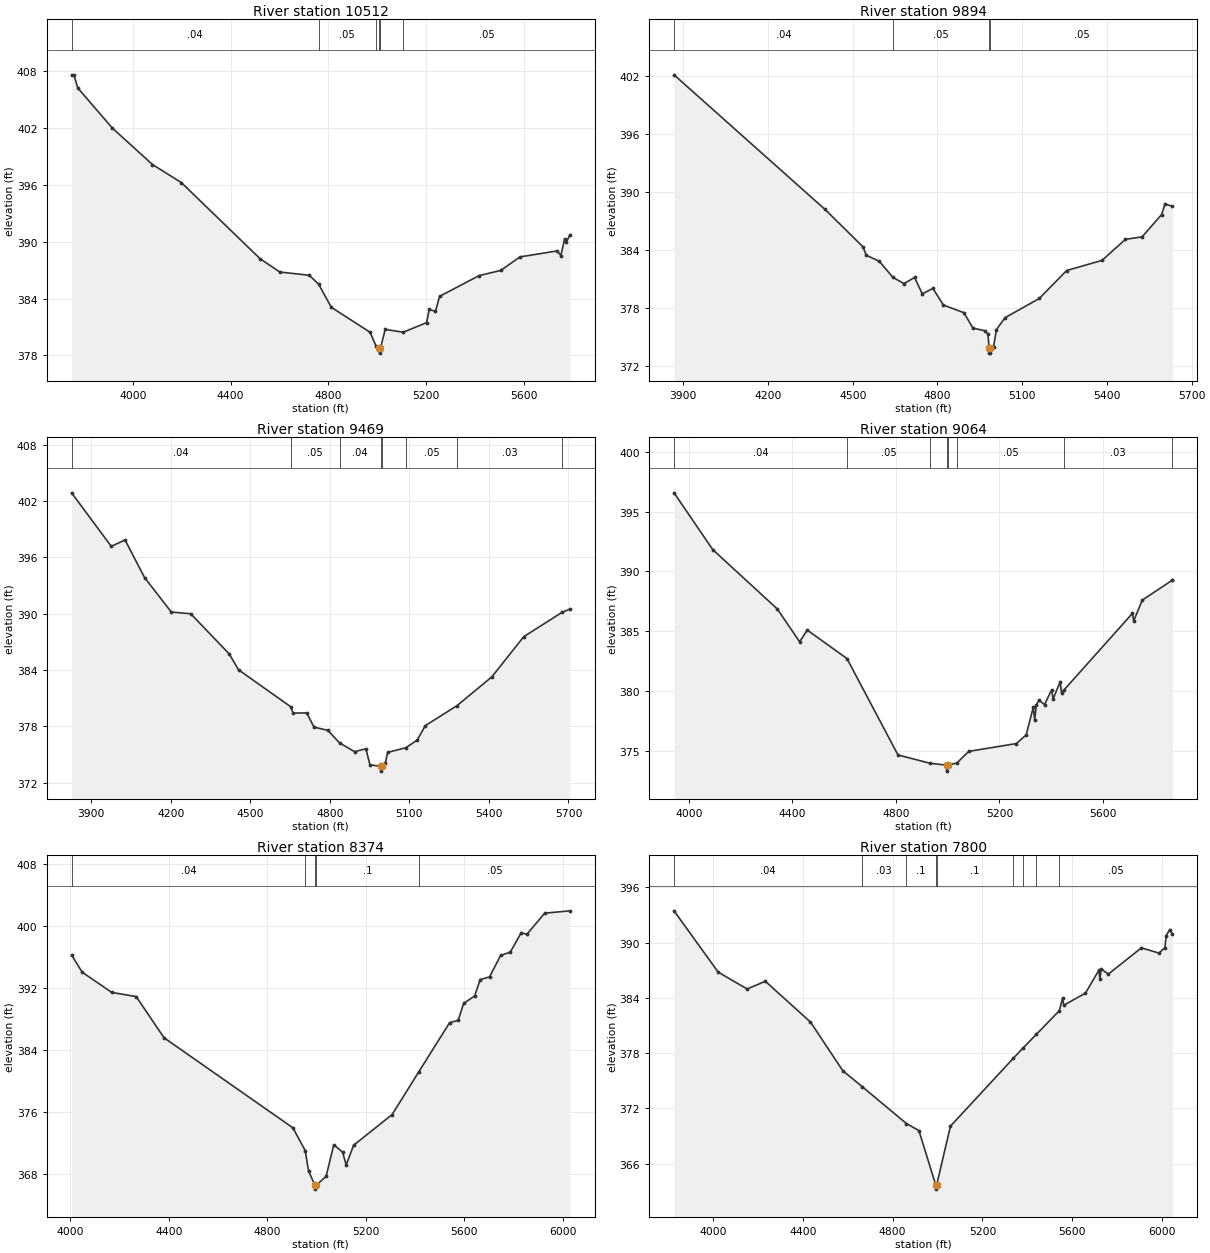
Type RM Length L Ch R = 1,10512,618,618,618
BEGIN DESCRIPTION:
Mapping XS 7d27013b
END DESCRIPTION:
XS GIS Cut Line= 4
      2401298.22     13542765.07      2401376.34     13541658.33
      2401228.77     13541241.67      2400816.44     13540981.25
#Sta/Elev= 30
  3749.1  407.62  3759.2  407.57  3774.3  406.24  3915.5  402.01  4080.0  398.15
  4197.9  396.25  4521.1  388.19  4601.3  386.80  4721.6  386.46  4759.7  385.52
  4811.8  383.08  4970.5  380.44  4994.6  378.99  5008.6  378.74  5008.9  378.24
  5012.6  378.74  5032.3  380.74  5106.1  380.45  5201.6  381.46  5212.3  382.85
  5237.9  382.65  5254.6  384.23  5416.8  386.43  5505.0  386.97  5583.8  388.40
  5735.6  389.03  5750.9  388.54  5766.2  390.30  5772.1  389.92  5788.3  390.74
#Mann=6,-1,0
  3749.1    0.04       0  4759.7    0.05       0  4994.6    0.04       0
  5008.6    0.04       0  5012.6    0.04       0  5106.1    0.05       0
Bank Sta=5008.6,5012.6
Exp/Cntr=0.3,0.1

Type RM Length L Ch R = 1,9894,425,425,425
BEGIN DESCRIPTION:
Mapping XS 0bcd2ee6
END DESCRIPTION:
XS GIS Cut Line= 3
      2401345.95     13542626.23      2401871.13     13541706.08
      2401975.09     13541008.66
#Sta/Elev= 30
  3867.4  402.07  4402.2  388.15  4536.1  384.30  4548.2  383.41  4594.2  382.80
  4642.0  381.14  4681.5  380.49  4719.0  381.12  4746.3  379.43  4783.8  379.99
  4821.2  378.27  4893.6  377.48  4925.7  375.89  4968.4  375.61  4978.5  375.29
  4983.1  373.80  4983.4  373.30  4987.3  373.30  4987.6  373.80  4998.7  373.97
  5008.9  375.74  5039.2  376.96  5160.5  378.95  5257.5  381.84  5382.9  382.89
  5465.4  385.06  5524.5  385.32  5593.8  387.63  5605.4  388.71  5632.0  388.48
#Mann=4,-1,0
  3867.4    0.04       0  4642.0    0.05       0  4983.1    0.05       0
  4987.6    0.05       0
Bank Sta=4983.1,4987.6
Exp/Cntr=0.3,0.1

Type RM Length L Ch R = 1,9469,405,405,405
BEGIN DESCRIPTION:
Mapping XS f1f300c3
END DESCRIPTION:
XS GIS Cut Line= 3
      2401615.06     13542782.45      2402240.05     13541758.16
      2402179.29     13541081.09
#Sta/Elev= 30
  3826.1  402.86  3975.6  397.17  4027.8  397.84  4101.4  393.84  4202.1  390.18
  4275.6  389.99  4420.6  385.72  4455.7  384.03  4653.1  380.09  4660.9  379.43
  4713.1  379.44  4740.3  377.93  4792.5  377.59  4837.2  376.24  4893.3  375.32
  4936.0  375.63  4951.3  373.93  4992.3  373.75  4992.6  373.25  4996.9  373.75
  5009.4  374.10  5018.0  375.24  5086.7  375.74  5129.6  376.55  5159.7  378.08
  5279.7  380.22  5410.7  383.27  5531.2  387.55  5676.6  390.16  5705.8  390.49
#Mann=8,-1,0
  3826.1    0.04       0  4653.1    0.05       0  4837.2    0.04       0
  4992.3    0.04       0  4996.9    0.04       0  5086.7    0.05       0
  5279.7    0.03       0  5676.6    0.04       0
Bank Sta=4992.3,4996.9
Exp/Cntr=0.3,0.1

Type RM Length L Ch R = 1,9064,690,690,690
BEGIN DESCRIPTION:
Mapping XS 1e235e91
END DESCRIPTION:
XS GIS Cut Line= 3
      2402010.02     13542817.19      2402578.60     13542014.24
      2402305.15     13541111.42
#Sta/Elev= 30
  3942.0  396.56  4091.7  391.82  4341.4  386.86  4427.6  384.12  4457.1  385.10
  4610.7  382.72  4807.9  374.67  4931.7  373.98  4995.9  373.82  4996.2  373.32
  5000.5  373.82  5035.7  374.00  5081.8  374.97  5265.3  375.62  5303.5  376.34
  5331.2  378.66  5336.4  377.58  5343.0  378.87  5353.5  379.25  5374.5  378.87
  5402.2  380.12  5407.5  379.35  5435.2  380.77  5440.4  379.84  5451.2  380.13
  5714.2  386.49  5719.4  385.87  5752.4  387.60  5866.8  389.24  5869.2  389.24
#Mann=8,-1,0
  3942.0    0.04       0  4610.7    0.05       0  4931.7     0.1       0
  4995.9    0.05       0  5000.5     0.1       0  5035.7    0.05       0
  5451.2    0.03       0  5866.8    0.04       0
Bank Sta=4995.9,5000.5
Exp/Cntr=0.3,0.1

Type RM Length L Ch R = 1,8374,574,574,574
BEGIN DESCRIPTION:
Mapping XS 888aec10
END DESCRIPTION:
XS GIS Cut Line= 3
      2402287.82     13542938.69      2402999.60     13542205.21
      2403445.86     13541308.37
#Sta/Elev= 30
  4005.6  396.28  4048.7  394.07  4168.8  391.46  4267.9  390.93  4381.0  385.62
  4904.3  374.01  4954.3  371.07  4968.0  368.42  4993.8  366.61  4994.2  366.11
  4998.9  366.61  5039.1  367.76  5070.2  371.83  5106.1  370.88  5120.6  369.23
  5150.8  371.77  5307.1  375.72  5415.6  381.24  5540.5  387.56  5575.2  387.86
  5597.5  390.05  5642.2  391.01  5664.6  393.11  5702.8  393.47  5747.6  396.23
  5786.8  396.65  5831.6  399.17  5854.0  398.95  5926.8  401.68  6029.4  401.98
#Mann=5,-1,0
  4005.6    0.04       0  4954.3     0.1       0  4993.8    0.05       0
  4998.9     0.1       0  5415.6    0.05       0
Bank Sta=4993.8,4998.9
Exp/Cntr=0.3,0.1

Type RM Length L Ch R = 1,7800,475,475,475
BEGIN DESCRIPTION:
Mapping XS 550e00a3
END DESCRIPTION:
XS GIS Cut Line= 3
      2402556.89     13543029.86      2403498.73     13542396.18
      2403828.58     13541363.24
#Sta/Elev= 30
  3826.5  393.46  4023.2  386.80  4152.2  384.97  4233.1  385.81  4434.1  381.38
  4578.1  376.09  4664.1  374.37  4861.5  370.35  4917.0  369.59  4991.3  363.73
  4991.7  363.23  4996.5  363.73  5057.4  370.07  5336.9  377.43  5379.1  378.52
  5439.5  380.03  5542.0  382.61  5556.8  383.97  5562.0  383.20  5658.6  384.52
  5717.7  386.98  5723.0  386.10  5729.2  387.13  5760.7  386.59  5907.7  389.44
  5985.7  388.87  6012.6  389.46  6017.9  390.76  6033.7  391.42  6046.0  390.93
#Mann=9,-1,0
  3826.5    0.04       0  4664.1    0.03       0  4861.5     0.1       0
  4991.3    0.05       0  4996.5     0.1       0  5336.9    0.12       0
  5379.1     0.1       0  5439.5    0.12       0  5542.0    0.05       0
Bank Sta=4991.3,4996.5
Exp/Cntr=0.3,0.1

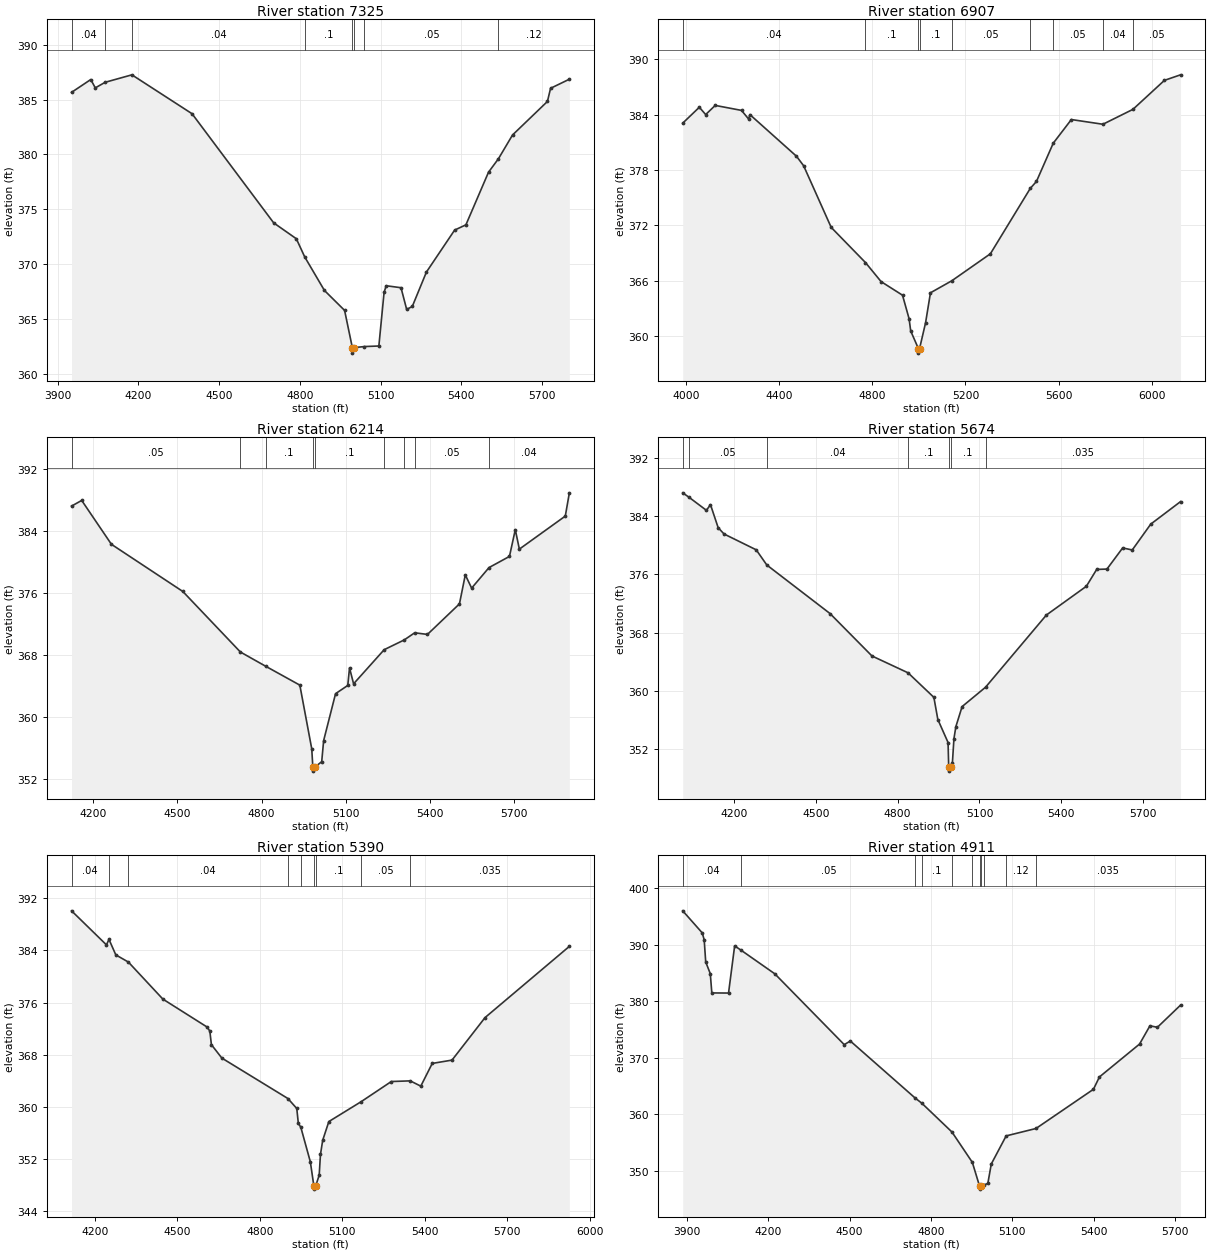
Type RM Length L Ch R = 1,7325,418,418,418
BEGIN DESCRIPTION:
Mapping XS 726dd2e8
END DESCRIPTION:
XS GIS Cut Line= 3
      2402982.27     13543129.67      2403863.32     13542695.66
      2404123.20     13541868.36
#Sta/Elev= 30
  3951.8  385.67  4023.1  386.84  4040.0  386.08  4076.8  386.59  4176.0  387.27
  4399.4  383.72  4702.6  373.76  4786.8  372.31  4818.0  370.65  4891.2  367.59
  4966.1  365.77  4994.9  362.37  4995.3  361.87  5000.2  362.37  5039.7  362.47
  5093.4  362.52  5112.8  367.41  5120.6  368.02  5175.7  367.84  5196.7  365.86
  5217.6  366.13  5270.1  369.27  5374.9  373.10  5416.8  373.58  5500.7  378.38
  5537.6  379.61  5590.0  381.78  5719.6  384.84  5731.3  386.04  5801.1  386.87
#Mann=8,-1,0
  3951.8    0.04       0  4076.8    0.05       0  4176.0    0.04       0
  4818.0     0.1       0  4994.9    0.05       0  5000.2     0.1       0
  5039.7    0.05       0  5537.6    0.12       0
Bank Sta=4994.9,5000.2
Exp/Cntr=0.3,0.1

Type RM Length L Ch R = 1,6907,693,693,693
BEGIN DESCRIPTION:
Mapping XS e58004ac
END DESCRIPTION:
XS GIS Cut Line= 4
      2403168.88     13543285.94      2403945.78     13543103.65
      2404306.03     13542726.04      2404284.32     13541905.72
#Sta/Elev= 30
  3984.1  383.07  4055.5  384.79  4082.8  384.00  4123.9  384.99  4236.9  384.45
  4267.7  383.51  4272.8  384.00  4473.2  379.49  4504.0  378.46  4622.5  371.79
  4770.0  367.98  4837.1  365.92  4929.2  364.45  4957.5  361.90  4964.4  360.58
  4997.3  358.68  4997.7  358.18  5002.6  358.68  5028.3  361.46  5049.4  364.71
  5141.1  366.01  5307.0  368.93  5478.6  376.01  5505.1  376.76  5577.3  380.90
  5655.2  383.46  5790.9  382.95  5919.8  384.56  6055.3  387.70  6124.6  388.30
#Mann=9,-1,0
  3984.1    0.04       0  4770.0     0.1       0  4997.3    0.05       0
  5002.6     0.1       0  5141.1    0.05       0  5478.6   0.013       0
  5577.3    0.05       0  5790.9    0.04       0  5919.8    0.05       0
Bank Sta=4997.3,5002.6
Exp/Cntr=0.3,0.1

Type RM Length L Ch R = 1,6214,540,540,540
BEGIN DESCRIPTION:
Mapping XS 89648969
END DESCRIPTION:
XS GIS Cut Line= 3
      2403950.13     13544041.14      2404601.16     13543359.72
      2405258.90     13542849.11
#Sta/Elev= 30
  4122.3  387.20  4158.5  387.93  4264.5  382.27  4519.0  376.19  4724.4  368.38
  4814.3  366.55  4936.3  364.11  4978.8  355.89  4982.7  353.52  4983.2  353.02
  4989.3  353.52  5014.3  354.24  5021.2  356.96  5063.7  363.01  5107.2  364.07
  5113.5  366.33  5128.0  364.28  5237.0  368.68  5308.6  369.94  5345.9  370.86
  5391.4  370.65  5505.5  374.59  5526.3  378.33  5548.9  376.62  5610.9  379.27
  5683.8  380.71  5704.6  384.16  5719.1  381.65  5882.9  385.91  5897.4  388.91
#Mann=9,-1,0
  4122.3    0.05       0  4724.4    0.12       0  4814.3     0.1       0
  4982.7    0.05       0  4989.3     0.1       0  5237.0    0.05       0
  5308.6   0.035       0  5345.9    0.05       0  5610.9    0.04       0
Bank Sta=4982.7,4989.3
Exp/Cntr=0.3,0.1

Type RM Length L Ch R = 1,5674,284,284,284
BEGIN DESCRIPTION:
Mapping XS 78d99ccf
END DESCRIPTION:
XS GIS Cut Line= 3
      2404136.76     13544184.37      2405013.49     13543680.90
      2405408.19     13542969.58
#Sta/Elev= 30
  4012.5  387.24  4034.8  386.65  4099.3  384.83  4114.3  385.61  4142.4  382.44
  4164.0  381.57  4281.9  379.39  4320.7  377.30  4552.5  370.61  4706.1  364.77
  4838.4  362.45  4933.0  359.07  4947.6  356.02  4985.0  352.85  4987.4  349.41
  4987.9  348.91  4994.1  349.41  5000.8  349.99  5006.6  353.39  5013.7  355.05
  5036.5  357.80  5122.5  360.47  5345.4  370.41  5491.9  374.37  5529.7  376.69
  5567.4  376.74  5624.9  379.65  5660.1  379.37  5727.9  382.93  5837.0  386.03
#Mann=7,-1,0
  4012.5    0.04       0  4034.8    0.05       0  4320.7    0.04       0
  4838.4     0.1       0  4987.4    0.05       0  4994.1     0.1       0
  5122.5   0.035       0
Bank Sta=4987.4,4994.1
Exp/Cntr=0.3,0.1

Type RM Length L Ch R = 1,5390,479,479,479
BEGIN DESCRIPTION:
Mapping XS d63f8f1e
END DESCRIPTION:
XS GIS Cut Line= 3
      2404353.76     13544353.65      2405148.04     13543919.62
      2405716.63     13543216.47
#Sta/Elev= 30
  4116.0  390.09  4242.8  384.86  4252.0  385.70  4276.9  383.32  4322.5  382.22
  4447.9  376.53  4608.2  372.25  4618.6  371.62  4624.3  369.53  4662.3  367.47
  4902.3  361.26  4934.6  359.73  4940.3  357.43  4949.2  356.86  4983.9  351.54
  4996.7  347.84  4997.2  347.34  5003.4  347.84  5016.1  349.48  5020.7  352.66
  5028.9  354.85  5051.2  357.72  5168.5  360.77  5278.3  363.87  5347.1  363.97
  5385.4  363.16  5427.0  366.65  5498.9  367.16  5618.9  373.69  5925.4  384.63
#Mann=9,-1,0
  4116.0    0.04       0  4252.0    0.05       0  4322.5    0.04       0
  4902.3    0.05       0  4949.2     0.1       0  4996.7    0.05       0
  5003.4     0.1       0  5168.5    0.05       0  5347.1   0.035       0
Bank Sta=4996.7,5003.4
Exp/Cntr=0.3,0.1

Type RM Length L Ch R = 1,4911,596,596,596
BEGIN DESCRIPTION:
Mapping XS 229b916f
END DESCRIPTION:
XS GIS Cut Line= 3
      2404540.38     13544635.77      2405525.64     13544149.65
      2405872.48     13543499.33
#Sta/Elev= 30
  3884.7  395.99  3956.8  392.08  3963.9  390.86  3969.5  386.94  3986.4  384.87
  3992.0  381.46  4053.7  381.44  4076.2  389.79  4101.4  388.97  4224.4  384.84
  4480.3  372.31  4502.8  372.95  4742.3  362.84  4766.3  361.95  4877.5  356.85
  4952.7  351.48  4979.5  347.24  4980.0  346.74  4986.4  347.24  4994.1  347.45
  5009.8  347.74  5022.6  351.19  5077.4  356.16  5187.4  357.47  5399.3  364.41
  5421.3  366.59  5569.3  372.41  5607.6  375.64  5635.2  375.38  5720.4  379.30
#Mann=11,-1,0
  3884.7    0.04       0  4101.4    0.05       0  4742.3    0.12       0
  4766.3     0.1       0  4877.5    0.05       0  4952.7    0.12       0
  4979.5    0.05       0  4986.4    0.12       0  4994.1    0.05       0
  5077.4    0.12       0  5187.4   0.035       0
Bank Sta=4979.5,4986.4
Exp/Cntr=0.3,0.1

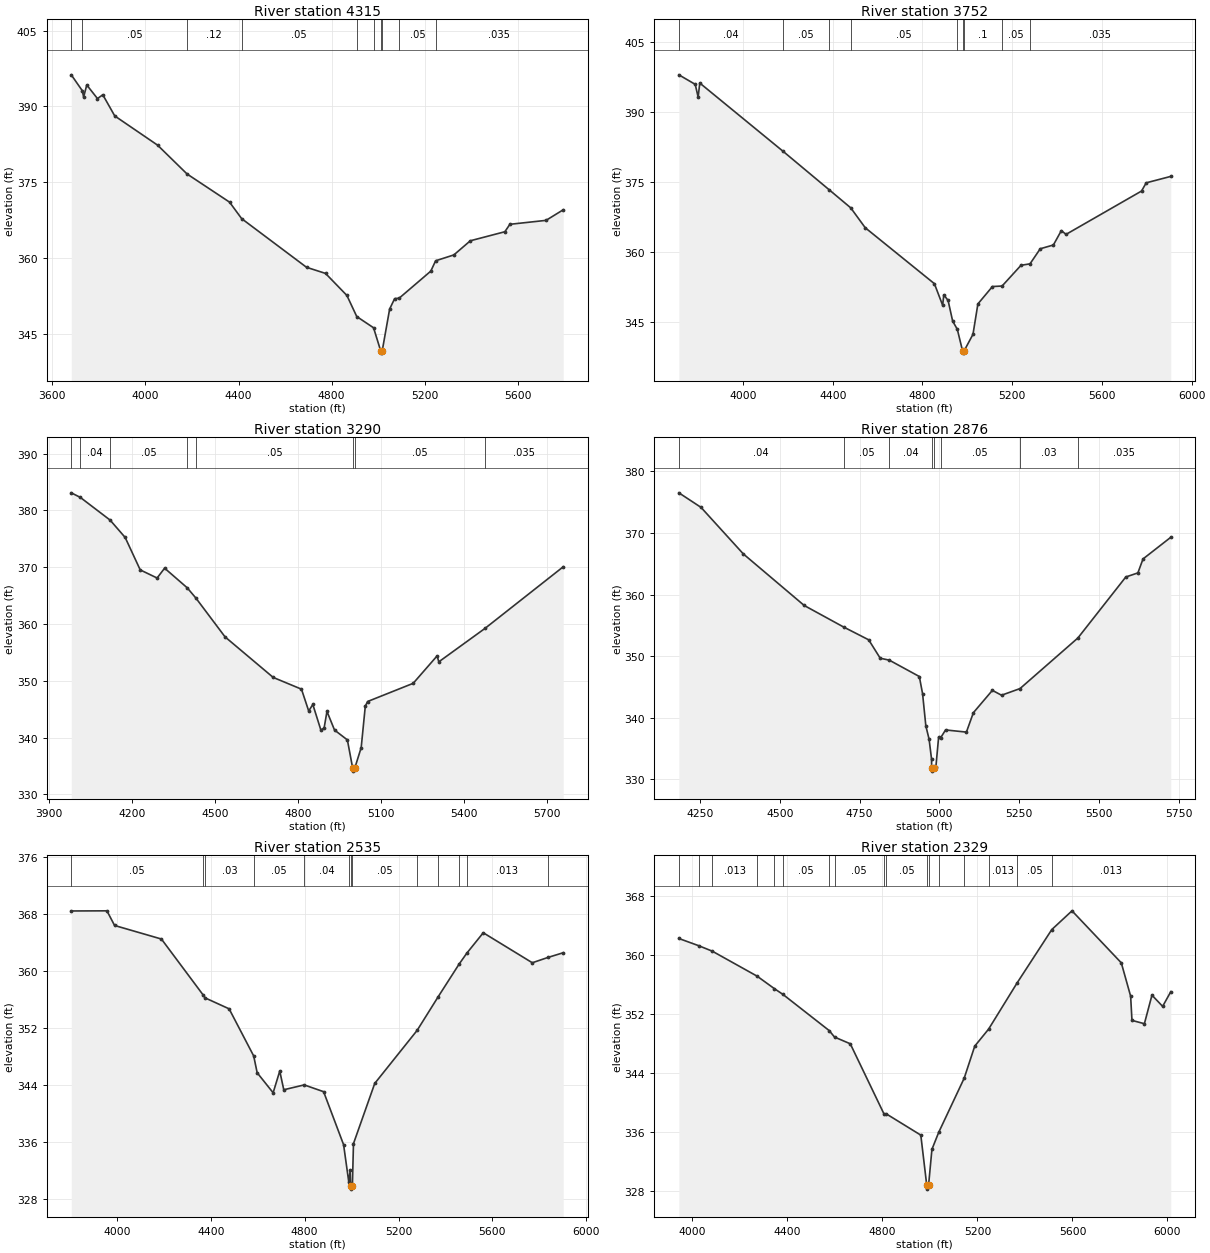
Type RM Length L Ch R = 1,4315,563,563,563
BEGIN DESCRIPTION:
Mapping XS edd195ef
END DESCRIPTION:
XS GIS Cut Line= 3
      2404836.80     13544886.65      2406027.81     13544338.02
      2406610.59     13543786.46
#Sta/Elev= 30
  3681.2  396.24  3728.7  393.09  3734.3  391.83  3747.8  394.23  3793.8  391.54
  3816.7  392.29  3868.1  388.10  4051.8  382.33  4178.8  376.61  4361.3  371.04
  4413.4  367.77  4692.1  358.14  4773.7  356.93  4865.5  352.57  4907.9  348.39
  4980.1  346.17  5010.4  341.65  5010.9  341.15  5017.5  341.65  5049.2  349.88
  5070.6  351.93  5090.2  352.03  5226.0  357.38  5246.8  359.43  5325.1  360.59
  5395.9  363.39  5544.3  365.18  5565.8  366.65  5721.1  367.43  5794.9  369.52
#Mann=10,-1,0
  3681.2    0.04       0  3728.7    0.05       0  4178.8    0.12       0
  4413.4    0.05       0  4907.9    0.12       0  4980.1     0.1       0
  5010.4    0.05       0  5017.5     0.1       0  5090.2    0.05       0
  5246.8   0.035       0
Bank Sta=5010.4,5017.5
Exp/Cntr=0.3,0.1

Type RM Length L Ch R = 1,3752,462,462,462
BEGIN DESCRIPTION:
Mapping XS fc939531
END DESCRIPTION:
XS GIS Cut Line= 3
      2404913.19     13545084.55      2406152.81     13544865.80
      2406906.32     13544313.69
#Sta/Elev= 30
  3714.1  397.91  3787.0  395.87  3800.0  393.14  3807.3  396.15  4179.2  381.51
  4382.7  373.35  4480.3  369.42  4544.7  365.17  4853.2  353.18  4890.0  348.55
  4895.0  350.80  4914.2  349.59  4934.5  345.18  4955.3  343.41  4978.6  338.81
  4979.1  338.31  4985.8  338.81  5025.2  342.34  5047.1  348.85  5111.9  352.57
  5154.9  352.68  5239.3  357.12  5279.4  357.43  5325.0  360.66  5383.6  361.47
  5419.1  364.55  5440.0  363.74  5776.5  373.02  5797.4  374.78  5907.0  376.16
#Mann=9,-1,0
  3714.1    0.04       0  4179.2    0.05       0  4382.7    0.04       0
  4480.3    0.05       0  4955.3     0.1       0  4978.6    0.05       0
  4985.8     0.1       0  5154.9    0.05       0  5279.4   0.035       0
Bank Sta=4978.6,4985.8
Exp/Cntr=0.3,0.1

Type RM Length L Ch R = 1,3290,414,414,414
BEGIN DESCRIPTION:
Mapping XS c4331ae7
END DESCRIPTION:
XS GIS Cut Line= 3
      2405461.83     13545431.77      2406423.65     13545223.44
      2407076.45     13544772.03
#Sta/Elev= 30
  3979.7  383.08  4012.3  382.28  4120.1  378.28  4174.6  375.22  4228.9  369.52
  4289.9  368.09  4317.1  369.82  4398.7  366.37  4430.3  364.55  4535.5  357.73
  4709.4  350.60  4811.7  348.53  4837.8  344.69  4852.7  345.84  4881.9  341.32
  4893.6  341.72  4903.8  344.62  4931.1  341.34  4977.6  339.60  4996.8  334.61
  4997.3  334.11  5004.1  334.61  5027.5  338.25  5042.3  345.53  5050.6  346.36
  5215.4  349.56  5301.9  354.39  5308.0  353.34  5474.8  359.22  5757.5  370.06
#Mann=8,-1,0
  3979.7    0.05       0  4012.3    0.04       0  4120.1    0.05       0
  4398.7    0.04       0  4430.3    0.05       0  4996.8    0.05       0
  5004.1    0.05       0  5474.8   0.035       0
Bank Sta=4996.8,5004.1
Exp/Cntr=0.3,0.1

Type RM Length L Ch R = 1,2876,341,341,341
BEGIN DESCRIPTION:
Mapping XS b7b9c1d5
END DESCRIPTION:
XS GIS Cut Line= 3
      2405677.07     13545779.00      2406458.37     13545619.27
      2407108.91     13545259.40
#Sta/Elev= 30
  4183.9  376.53  4253.2  374.17  4385.9  366.60  4576.5  358.23  4699.6  354.74
  4778.5  352.65  4814.6  349.66  4843.0  349.35  4937.1  346.69  4947.3  343.89
  4957.5  338.67  4967.7  336.50  4975.3  333.30  4975.8  331.82  4976.3  331.32
  4983.2  331.82  4988.9  331.98  4997.6  336.87  5003.6  336.72  5019.3  338.01
  5084.6  337.66  5106.4  340.81  5165.9  344.44  5194.6  343.65  5252.5  344.73
  5433.8  352.95  5583.9  362.86  5621.7  363.52  5637.8  365.79  5724.8  369.31
#Mann=8,-1,0
  4183.9    0.04       0  4699.6    0.05       0  4843.0    0.04       0
  4975.8    0.04       0  4983.2    0.04       0  5003.6    0.05       0
  5252.5    0.03       0  5433.8   0.035       0
Bank Sta=4975.8,4983.2
Exp/Cntr=0.3,0.1

Type RM Length L Ch R = 1,2535,206,206,206
BEGIN DESCRIPTION:
Mapping XS 5857159e
END DESCRIPTION:
XS GIS Cut Line= 3
      2405548.64     13546393.58      2406635.45     13545872.74
      2407444.46     13545501.22
#Sta/Elev= 30
  3806.0  368.38  3957.9  368.40  3990.5  366.35  4190.1  364.45  4368.0  356.61
  4376.2  356.21  4478.4  354.68  4583.1  348.08  4597.9  345.73  4665.9  342.93
  4694.1  345.97  4711.2  343.35  4798.2  344.03  4880.9  343.08  4966.0  335.66
  4988.2  330.42  4994.2  332.08  4996.0  329.94  4996.5  329.44  5003.5  329.94
  5008.1  335.81  5098.7  344.24  5279.4  351.67  5368.5  356.35  5457.8  360.93
  5490.6  362.46  5560.9  365.33  5769.9  361.13  5837.0  361.88  5901.4  362.53
#Mann=13,-1,0
  3806.0    0.05       0  4368.0   0.013       0  4376.2    0.03       0
  4583.1    0.05       0  4798.2    0.04       0  4988.2    0.05       0
  4996.0    0.05       0  5003.5    0.05       0  5279.4    0.03       0
  5368.5    0.05       0  5457.8   0.035       0  5490.6   0.013       0
  5837.0   0.035       0
Bank Sta=4996,5003.5
Exp/Cntr=0.3,0.1

Type RM Length L Ch R = 1,2329,555,555,555
BEGIN DESCRIPTION:
Mapping XS 072dbeca
END DESCRIPTION:
XS GIS Cut Line= 3
      2405656.31     13546508.15      2406656.29     13546070.66
      2407534.73     13545636.64
#Sta/Elev= 30
  3942.7  362.21  4025.7  361.24  4083.5  360.49  4271.9  357.11  4344.9  355.41
  4380.6  354.64  4575.6  349.73  4598.1  348.85  4664.4  347.94  4806.2  338.44
  4815.5  338.45  4961.4  335.56  4986.5  328.74  4987.0  328.24  4994.0  328.74
  5008.2  333.63  5036.7  335.93  5144.1  343.28  5188.5  347.62  5246.9  349.93
  5366.7  356.18  5512.9  363.42  5598.0  365.96  5805.6  358.91  5844.9  354.39
  5850.5  351.11  5902.8  350.66  5934.7  354.53  5979.6  353.01  6014.0  355.00
#Mann=17,-1,0
  3942.7   0.013       0  4025.7    0.05       0  4083.5   0.013       0
  4271.9    0.05       0  4344.9   0.013       0  4380.6    0.05       0
  4575.6   0.013       0  4598.1    0.05       0  4806.2   0.013       0
  4815.5    0.05       0  4986.5    0.05       0  4994.0    0.05       0
  5036.7   0.013       0  5144.1    0.05       0  5246.9   0.013       0
  5366.7    0.05       0  5512.9   0.013       0
Bank Sta=4986.5,4994
Exp/Cntr=0.3,0.1

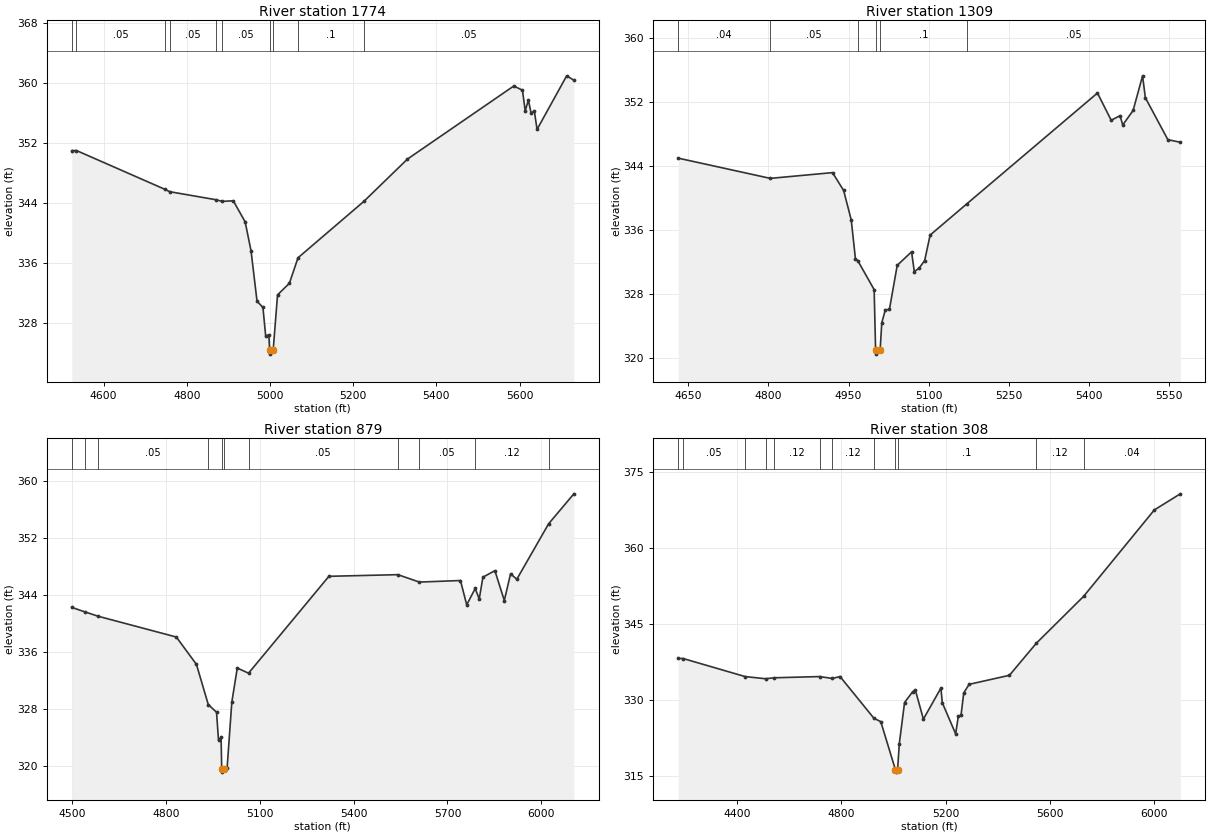
Type RM Length L Ch R = 1,1774,465,465,465
BEGIN DESCRIPTION:
Mapping XS d93cc70e
END DESCRIPTION:
XS GIS Cut Line= 3
      2406506.99     13546935.24      2406826.42     13546570.66
      2407301.05     13546026.75
#Sta/Elev= 30
  4523.7  350.94  4534.9  350.96  4746.7  345.80  4759.3  345.46  4871.3  344.38
  4885.0  344.17  4911.9  344.25  4940.4  341.43  4954.6  337.55  4968.9  330.85
  4983.1  330.01  4989.8  326.17  4997.3  326.38  4999.3  324.28  4999.8  323.78
  5007.7  324.28  5018.2  331.69  5046.7  333.24  5067.4  336.64  5225.5  344.16
  5330.5  349.82  5585.9  359.57  5606.8  359.01  5613.4  356.26  5621.0  357.69
  5627.7  355.94  5635.3  356.24  5641.9  353.78  5713.1  360.93  5730.3  360.35
#Mann=10,-1,0
  4523.7    0.04       0  4534.9    0.05       0  4746.7     0.1       0
  4759.3    0.05       0  4871.3     0.1       0  4885.0    0.05       0
  4999.3    0.05       0  5007.7    0.05       0  5067.4     0.1       0
  5225.5    0.05       0
Bank Sta=4999.3,5007.7
Exp/Cntr=0.3,0.1

Type RM Length L Ch R = 1,1309,430,430,430
BEGIN DESCRIPTION:
Mapping XS 22969321
END DESCRIPTION:
XS GIS Cut Line= 3
      2406934.05     13547001.23      2407191.01     13546695.66
      2407315.75     13546168.98
#Sta/Elev= 30
  4631.0  344.96  4803.4  342.43  4920.0  343.15  4940.8  340.92  4955.1  337.22
  4962.9  332.39  4967.2  332.15  4998.0  328.51  5000.7  320.94  5001.2  320.44
  5009.2  320.94  5012.3  324.36  5018.9  325.98  5026.6  326.03  5041.2  331.55
  5068.1  333.24  5073.2  330.77  5082.3  331.20  5092.6  332.15  5102.9  335.34
  5171.0  339.21  5416.3  353.11  5442.0  349.70  5458.6  350.27  5463.7  349.11
  5483.1  350.93  5500.8  355.26  5506.0  352.52  5548.2  347.27  5571.5  346.95
#Mann=6,-1,0
  4631.0    0.04       0  4803.4    0.05       0  4967.2     0.1       0
  5000.7    0.05       0  5009.2     0.1       0  5171.0    0.05       0
Bank Sta=5000.7,5009.2
Exp/Cntr=0.3,0.1

Type RM Length L Ch R = 1,879,571,571,571
BEGIN DESCRIPTION:
Mapping XS 28a719d5
END DESCRIPTION:
XS GIS Cut Line= 3
      2407175.08     13547034.71      2407567.76     13546730.05
      2407638.86     13545622.94
#Sta/Elev= 30
  4497.9  342.22  4539.3  341.60  4582.1  340.98  4832.5  338.06  4896.8  334.22
  4934.6  328.59  4961.1  327.51  4967.4  323.58  4975.6  324.00  4977.6  319.61
  4978.1  319.11  4986.1  319.61  4994.9  319.68  5010.0  328.94  5027.5  333.71
  5063.5  332.99  5320.6  346.58  5541.3  346.81  5610.0  345.77  5741.5  345.99
  5761.5  342.58  5788.7  344.87  5801.6  343.40  5813.4  346.46  5851.7  347.37
  5881.8  343.18  5901.8  346.93  5921.9  346.17  6023.6  353.95  6104.3  358.15
#Mann=11,-1,0
  4497.9    0.05       0  4539.3    0.04       0  4582.1    0.05       0
  4934.6     0.1       0  4977.6    0.05       0  4986.1     0.1       0
  5063.5    0.05       0  5541.3    0.12       0  5610.0    0.05       0
  5788.7    0.12       0  6023.6    0.05       0
Bank Sta=4977.6,4986.1
Exp/Cntr=0.3,0.1

Type RM Length L Ch R = 1,308,0,0,0
BEGIN DESCRIPTION:
BUTLER CREEK 1.0
END DESCRIPTION:
XS GIS Cut Line= 3
      2407384.94     13547038.13      2408085.74     13546686.04
      2408363.23     13545579.47
#Sta/Elev= 30
  4174.4  338.24  4193.4  338.22  4430.7  334.67  4509.3  334.24  4542.4  334.43
  4717.0  334.67  4765.7  334.29  4794.7  334.68  4924.6  326.47  4951.0  325.79
  5007.0  316.36  5007.5  315.86  5015.5  316.36  5022.0  321.45  5042.2  329.56
  5073.2  331.68  5083.5  332.03  5114.4  326.29  5181.6  332.41  5186.7  329.54
  5238.1  323.39  5248.4  326.89  5258.7  327.05  5269.1  331.45  5289.7  333.14
  5444.3  334.92  5547.4  341.23  5728.4  350.44  5999.9  367.47  6099.5  370.64
#Mann=12,-1,0
  4174.4    0.04       0  4193.4    0.05       0  4430.7     0.1       0
  4509.3    0.05       0  4542.4    0.12       0  4717.0     0.1       0
  4765.7    0.12       0  4924.6     0.1       0  5007.0    0.05       0
  5015.5     0.1       0  5547.4    0.12       0  5728.4    0.04       0
Bank Sta=5007,5015.5
Exp/Cntr=0.3,0.1

Chan Stop Cuts=-1