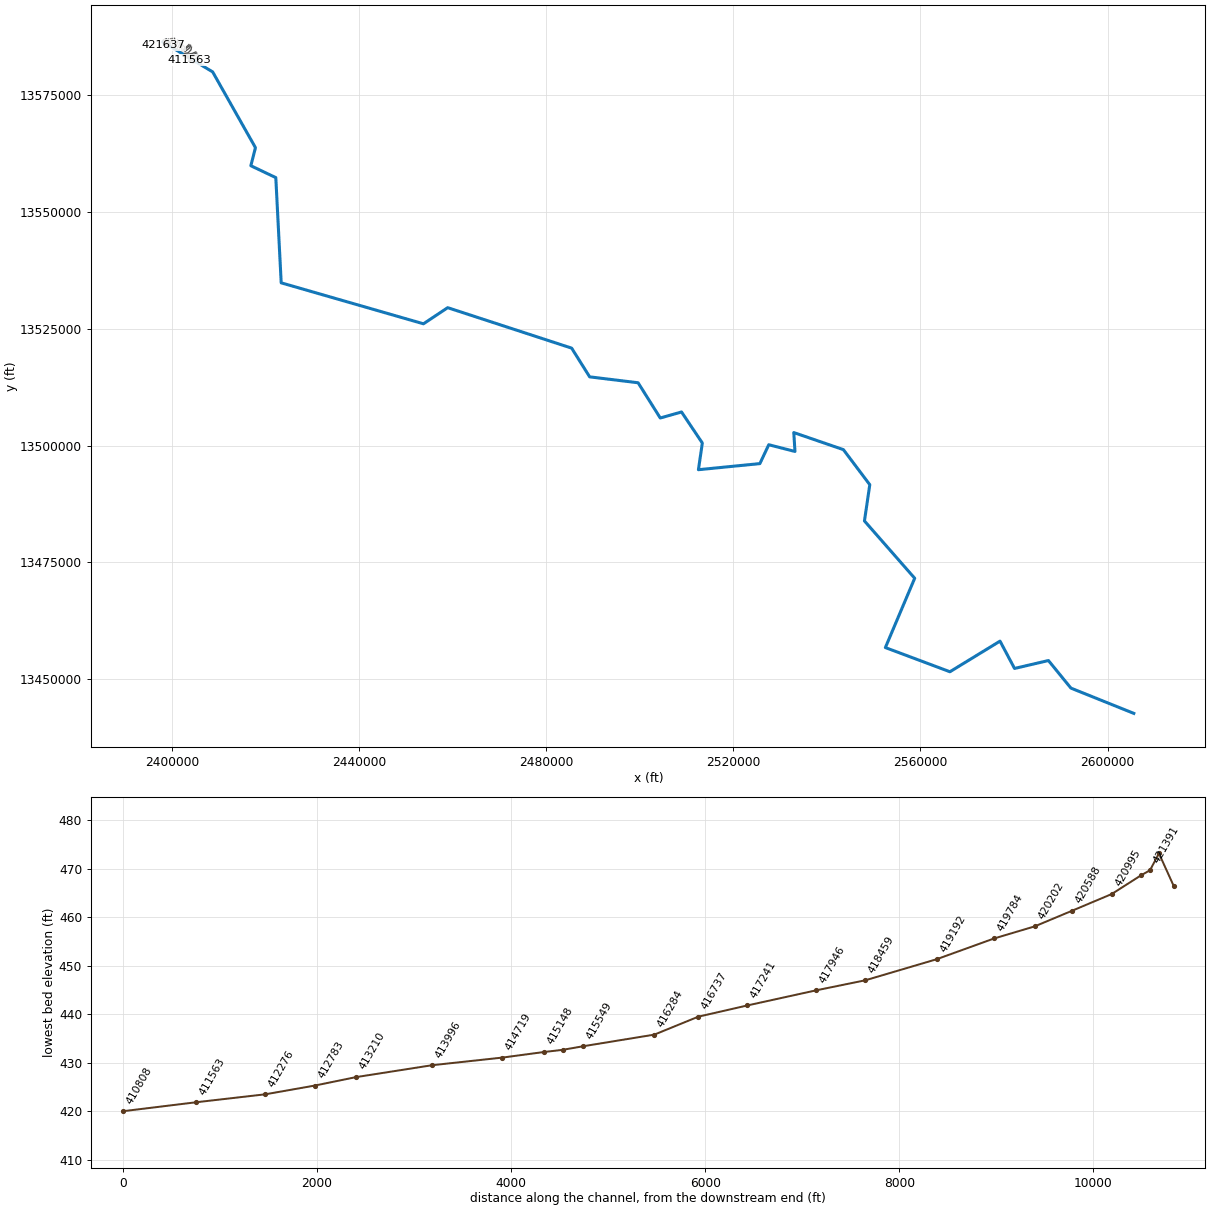
--- COLETO CREEK.prj (project) ---

Proj Title=COLETO CREEK Base Level Engineering
Current Plan=p01
Default Exp/Contr=0.3,0.1
English Units
Geom File=g01
Flow File=f01
Plan File=p01
Y Axis Title=Elevation
X Axis Title(PF)=Main Channel Distance
X Axis Title(XS)=Station
BEGIN DESCRIPTION:
COLETO CREEK
END DESCRIPTION:
DSS Export Rating Curves= 0
DSS Export Rating Curve Sorted= 0
DSS Export Volume Flow Curves= 0
DXF OffsetX= 0
DXF OffsetY= 0
DXF ScaleX= 1
DXF ScaleY= 10

--- COLETO CREEK.p01 (plan) ---

Plan Title=Multiple Run
Short Identifier=Multiple
Geom File=g01
Flow File=f01
Subcritical Flow
K Sum by GR= 0
Std Step Tol= 0.01
Critical Tol= 0.01
Num of Std Step Trials= 20
Max Error Tol= 0.3
Flow Tol Ratio= 0.001
Split Flow NTrial= 30
Split Flow Tol= 0.02
Split Flow Ratio= 0.02
Log Output Level= 0
Friction Slope Method= 1
Unsteady Friction Slope Method= 2
Unsteady Bridges Friction Slope Method= 1
Parabolic Critical Depth
Global Vel Dist=  1 , 1 , 1
Global Log Level= 0
CheckData=True
Encroach Param= -1, 0, 0, 0
BEGIN DESCRIPTION:
Multiple Run
END DESCRIPTION:

--- COLETO CREEK.f01 (steady flow) ---

Flow Title=Multiple
Program Version=4.10
Number of Profiles= 7
Profile Names=10-year,25-year,50-year,1pct_min,100-year,1pct_plu,500-year
River Rch & RM=COLETO CREEK,Reach-1         ,421637
     487     788    1061     694    1385    2764    2337
River Rch & RM=COLETO CREEK,Reach-1         ,420588
     705    1162    1584    1046    2087    4164    3591
River Rch & RM=COLETO CREEK,Reach-1         ,415338
    1050    1768    2444    1634    3261    6507    5761
River Rch & RM=COLETO CREEK,Reach-1         ,413210
    1336    2272    3162    2127    4244    8469    7587
River Rch & RM=COLETO CREEK,Reach-1         ,409743
    2169    3767    5316    3620    7222   14410   13232
River Rch & RM=COLETO CREEK,Reach-1         ,405830
    2300    4004    5657    3856    7693   15350   14126
River Rch & RM=COLETO CREEK,Reach-1         ,403969
    2655    4646    6588    4505    8989   17936   16612
River Rch & RM=COLETO CREEK,Reach-1         ,403047
    2699    4716    6682    4564    9106   18169   16788
River Rch & RM=COLETO CREEK,Reach-1         ,399888
    2757    4815    6817    4652    9282   18520   17084
River Rch & RM=COLETO CREEK,Reach-1         ,396489
    2863    5000    7079    4830    9638   19230   17732
River Rch & RM=COLETO CREEK,Reach-1         ,393417
    3017    5273    7471    5100   10176   20303   18738
River Rch & RM=COLETO CREEK,Reach-1         ,390986
    3133    5485    7778    5314   10603   21155   19558
River Rch & RM=COLETO CREEK,Reach-1         ,389189
    3485    6117    8689    5945   11862   23668   21942
River Rch & RM=COLETO CREEK,Reach-1         ,384986
    3557    6243    8870    6068   12108   24159   22396
River Rch & RM=COLETO CREEK,Reach-1         ,382566
    3599    6315    8969    6133   12238   24417   22617
River Rch & RM=COLETO CREEK,Reach-1         ,378246
    3782    6628    9407    6426   12821   25582   23642
River Rch & RM=COLETO CREEK,Reach-1         ,370262
    5492    9717   13885    9543   19042   37993   35522
River Rch & RM=COLETO CREEK,Reach-1         ,366890
    5590    9892   14137    9718   19390   38688   36178
River Rch & RM=COLETO CREEK,Reach-1         ,366006
    5807   10285   14705   10112   20175   40255   37670
River Rch & RM=COLETO CREEK,Reach-1         ,363954
    5596    9909   14164    9736   19425   38758   36252
River Rch & RM=COLETO CREEK,Reach-1         ,356501
    5723   10134   14485    9956   19864   39634   37065
River Rch & RM=COLETO CREEK,Reach-1         ,353253
    6734   11932   17060   11717   23379   46647   43496
River Rch & RM=COLETO CREEK,Reach-1         ,348744
    6815   12079   17275   11868   23679   47246   44075
River Rch & RM=COLETO CREEK,Reach-1         ,348282
    6560   11637   16649   11441   22827   45546   42532
River Rch & RM=COLETO CREEK,Reach-1         ,343063
    6533   11582   16564   11377   22701   45295   42262
River Rch & RM=COLETO CREEK,Reach-1         ,341620
    6725   11921   17046   11705   23356   46600   43458
River Rch & RM=COLETO CREEK,Reach-1         ,335773
   10868   19511   28150   19491   38889   77594   73519
River Rch & RM=COLETO CREEK,Reach-1         ,332395
   10938   19630   28318   19603   39114   78042   73913
River Rch & RM=COLETO CREEK,Reach-1         ,329408
   11472   20595   29716   20573   41048   81902   77579
River Rch & RM=COLETO CREEK,Reach-1         ,325229
   11932   21376   30808   21306   42511   84821   80131
River Rch & RM=COLETO CREEK,Reach-1         ,324618
   12177   21815   31439   21740   43377   86548   81743
River Rch & RM=COLETO CREEK,Reach-1         ,322317
   12210   21862   31497   21772   43441   86676   81804
River Rch & RM=COLETO CREEK,Reach-1         ,318942
   12222   21869   31491   21757   43412   86618   81666
River Rch & RM=COLETO CREEK,Reach-1         ,315561
   12237   21885   31503   21757   43411   86615   81599
River Rch & RM=COLETO CREEK,Reach-1         ,314154
   12426   22227   32000   22104   44102   87996   82920
River Rch & RM=COLETO CREEK,Reach-1         ,311147
   12922   23115   33282   22989   45869   91520   86234
River Rch & RM=COLETO CREEK,Reach-1         ,306145
   12934   23126   33286   22983   45858   91498   86152
River Rch & RM=COLETO CREEK,Reach-1         ,303712
   12954   23143   33294   22975   45842   91467   86021
River Rch & RM=COLETO CREEK,Reach-1         ,298692
   13212   23613   33978   23454   46797   93371   87855
River Rch & RM=COLETO CREEK,Reach-1         ,297564
   13260   23695   34094   23531   46951   93679   88126
River Rch & RM=COLETO CREEK,Reach-1         ,295532
   13215   23599   33940   23414   46717   93212   87600
River Rch & RM=COLETO CREEK,Reach-1         ,292012
   13233   23627   33976   23435   46759   93296   87655
River Rch & RM=COLETO CREEK,Reach-1         ,290890
   13213   23583   33904   23379   46647   93074   87398
River Rch & RM=COLETO CREEK,Reach-1         ,288320
   13205   23557   33855   23337   46564   92907   87178
River Rch & RM=COLETO CREEK,Reach-1         ,284404
   13183   23507   33772   23272   46434   92649   86877
River Rch & RM=COLETO CREEK,Reach-1         ,282096
   13173   23483   33732   23240   46370   92521   86725
River Rch & RM=COLETO CREEK,Reach-1         ,278671
   13229   23572   33850   23314   46518   92815   86944
River Rch & RM=COLETO CREEK,Reach-1         ,275581
   17344   31048   44743   30916   61686  123079  115988
River Rch & RM=COLETO CREEK,Reach-1         ,272588
   17403   31141   44865   30992   61838  123382  116208
River Rch & RM=COLETO CREEK,Reach-1         ,266468
   17388   31099   44788   30928   61709  123125  115880
River Rch & RM=COLETO CREEK,Reach-1         ,264478
   17304   30924   44511   30718   61290  122291  114958
River Rch & RM=COLETO CREEK,Reach-1         ,260966
   18287   32601   46859   32293   64432  128559  120447
River Rch & RM=COLETO CREEK,Reach-1         ,252452
   18311   32639   46909   32323   64493  128681  120533
River Rch & RM=COLETO CREEK,Reach-1         ,250591
   18349   32685   46956   32341   64529  128752  120489
River Rch & RM=COLETO CREEK,Reach-1         ,245272
   18295   32575   46783   32212   64271  128238  119934
River Rch & RM=COLETO CREEK,Reach-1         ,241979
   19292   34351   49338   33972   67783  135244  126476
River Rch & RM=COLETO CREEK,Reach-1         ,235491
   19358   34433   49421   34004   67846  135371  126401
River Rch & RM=COLETO CREEK,Reach-1         ,227492
   19518   34684   49750   34207   68252  136180  126983
River Rch & RM=COLETO CREEK,Reach-1         ,219000
   20153   35689   51081   35045   69925  139518  129469
River Rch & RM=COLETO CREEK,Reach-1         ,203538
   20295   35915   51381   35235   70302  140271  130037
River Rch & RM=COLETO CREEK,Reach-1         ,193879
   23322   41431   59433   40860   81526  162666  151586
River Rch & RM=COLETO CREEK,Reach-1         ,188361
   23990   42498   60859   41769   83341  166287  154365
River Rch & RM=COLETO CREEK,Reach-1         ,180450
   24028   42555   60930   41810   83423  166450  154459
River Rch & RM=COLETO CREEK,Reach-1         ,177434
   24236   42848   61277   41997   83794  167191  154754
River Rch & RM=COLETO CREEK,Reach-1         ,157784
   31779   56220   80493   55225  110188  219855  203754
River Rch & RM=COLETO CREEK,Reach-1         ,152888
   31970   56548   80955   55536  110809  221092  204853
River Rch & RM=COLETO CREEK,Reach-1         ,147080
   31938   56466   80811   55420  110577  220629  204291
River Rch & RM=COLETO CREEK,Reach-1         ,142100
   31694   55982   80066   54872  109483  218447  201995
River Rch & RM=COLETO CREEK,Reach-1         ,135359
   31842   56223   80391   55081  109900  219280  202659
River Rch & RM=COLETO CREEK,Reach-1         ,132031
   31628   55795   79731   54594  108928  217341  200611
River Rch & RM=COLETO CREEK,Reach-1         ,125531
   32074   56561   80807   55317  110371  220220  203162
River Rch & RM=COLETO CREEK,Reach-1         ,122352
   31970   56338   80452   55047  109834  219147  201978
River Rch & RM=COLETO CREEK,Reach-1         ,116077
   33215   58423   83340   56964  113658  226778  208488
River Rch & RM=COLETO CREEK,Reach-1         ,114865
   32115   56566   80750   55232  110202  219881  202507
River Rch & RM=COLETO CREEK,Reach-1         ,111378
   33097   58165   82923   56644  113019  225503  207057
River Rch & RM=COLETO CREEK,Reach-1         ,107805
   32996   57958   82600   56403  112539  224544  206029
River Rch & RM=COLETO CREEK,Reach-1         ,106516
   32906   57759   82277   56155  112043  223556  204917
River Rch & RM=COLETO CREEK,Reach-1         ,98393
   32799   57544   81943   55907  111550  222572  203873
River Rch & RM=COLETO CREEK,Reach-1         ,92895
   32680   57300   81560   55622  110980  221434  202652
River Rch & RM=COLETO CREEK,Reach-1         ,88801
   32511   56967   81052   55250  110237  219952  201111
River Rch & RM=COLETO CREEK,Reach-1         ,83973
   32417   56880   80990   55248  110234  219946  201467
River Rch & RM=COLETO CREEK,Reach-1         ,77651
   34316   60260   85871   58629  116981  233408  214088
River Rch & RM=COLETO CREEK,Reach-1         ,75199
   36063   63639   90973   62307  124318  248047  229074
River Rch & RM=COLETO CREEK,Reach-1         ,73387
   37273   65625   93690   64084  127864  255122  234895
River Rch & RM=COLETO CREEK,Reach-1         ,68189
   38409   67482   96222   65735  131160  261698  240264
River Rch & RM=COLETO CREEK,Reach-1         ,65187
   38360   67368   96031   65586  130861  261101  239570
River Rch & RM=COLETO CREEK,Reach-1         ,60146
   37574   66086   94281   64442  128578  256546  235854
River Rch & RM=COLETO CREEK,Reach-1         ,55393
   38613   67744   96504   65864  131415  262208  240248
River Rch & RM=COLETO CREEK,Reach-1         ,45830
   38470   67374   95861   65343  130376  260133  237745
River Rch & RM=COLETO CREEK,Reach-1         ,24362
   40077   70063   99587   67817  135313  269986  246169
River Rch & RM=COLETO CREEK,Reach-1         ,19494
   39982   69806   99135   67448  134576  268515  244376
Boundary for River Rch & Prof#=COLETO CREEK,Reach-1         , 1
Up Type= 0
Dn Type= 3
Dn Slope=0.005
Boundary for River Rch & Prof#=COLETO CREEK,Reach-1         , 2
Up Type= 0
Dn Type= 3
Dn Slope=0.005
Boundary for River Rch & Prof#=COLETO CREEK,Reach-1         , 3
Up Type= 0
Dn Type= 3
Dn Slope=0.005
Boundary for River Rch & Prof#=COLETO CREEK,Reach-1         , 4
Up Type= 0
Dn Type= 3
Dn Slope=0.005
Boundary for River Rch & Prof#=COLETO CREEK,Reach-1         , 5
Up Type= 0
Dn Type= 3
Dn Slope=0.005
Boundary for River Rch & Prof#=COLETO CREEK,Reach-1         , 6
Up Type= 0
Dn Type= 3
Dn Slope=0.005
Boundary for River Rch & Prof#=COLETO CREEK,Reach-1         , 7
Up Type= 0
Dn Type= 3
Dn Slope=0.005
Set Internal Change=COLETO CREEK    ,Reach-1         ,75082   , 5 , 3 ,100
DSS Import GetInterval= 0
DSS Import GetPeak= 0
DSS Import FillOption= 0

--- COLETO CREEK.g01 (geometry) ---

Geom Title=Existing Conditions
Program Version=4.10

River Reach=COLETO CREEK    ,Reach-1
Reach XY= 30
        2398025.       13586275.      2408661.64     13579888.34
      2417815.68     13563681.66      2416830.46       13559822.
      2422166.02     13557281.72      2423318.93     13534783.13
       2453735.5     13526026.22      2458919.15     13529472.94
      2485423.44     13520821.24      2489272.69     13514680.82
      2499634.68     13513414.24      2504372.71     13505880.81
      2508919.74     13507169.53      2513367.38     13500528.33
      2512530.46     13494826.69      2525673.42     13496128.82
      2527571.69     13500166.98      2533173.57     13498728.07
      2532921.66     13502768.04      2543527.44     13499119.53
      2549172.83     13491619.56      2548030.46     13483872.55
      2558773.79     13471615.41      2552504.96     13456794.19
      2566304.79     13451624.79      2577019.56     13458173.34
      2580122.71     13452330.81      2587373.35     13454021.83
      2592172.55     13448130.48        2605625.       13442725.

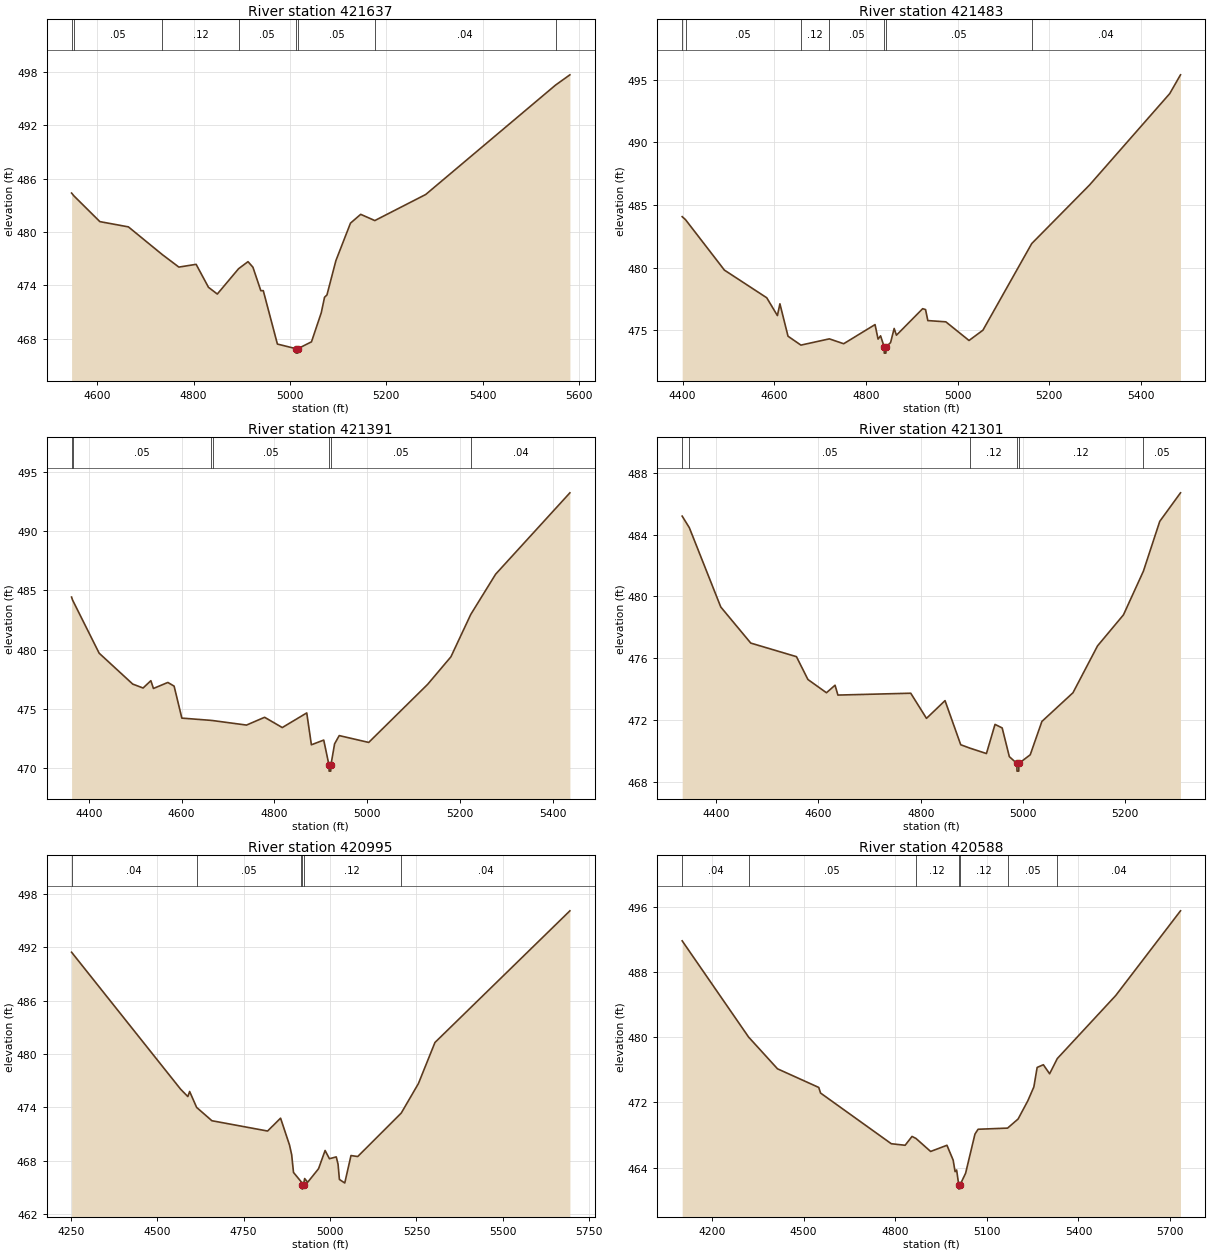
Type RM Length L Ch R = 1 ,421637  ,154,154,154
BEGIN DESCRIPTION:
SALT CREEK 142.0
END DESCRIPTION:
XS GIS Cut Line= 3
       2398163.8     13586652.28       2398249.2     13586267.99
      2398156.68     13585634.58
#Sta/Elev= 30
    4547  484.37  4552.1  484.04  4605.7  481.16  4664.9  480.57  4735.1  477.46
  4769.6  476.05  4805.4  476.36    4831  473.78  4849.3  473.02  4893.5  475.87
    4913  476.66  4923.2  476.04  4939.6   473.4  4944.7   473.4    4974   467.4
  5012.4  466.88  5012.7  466.38  5016.2  466.38  5016.4  466.88  5044.7  467.65
    5065  470.92  5071.8  472.66  5076.8  472.92  5095.3  476.77  5125.6  480.99
  5146.8  481.98  5176.1  481.28  5281.7  484.21  5551.1  496.51  5580.8  497.66
#Mann= 8 ,-1 , 0
    4547     .04       0  4552.1     .05       0  4735.1     .12       0
  4893.5     .05       0  5012.4     .05       0  5016.4     .05       0
  5176.1     .04       0  5551.1     .05       0
Bank Sta=5012.4,5016.4
XS Rating Curve= 0 ,0
Exp/Cntr=0.3,0.1

Type RM Length L Ch R = 1 ,421483  ,92,92,92
BEGIN DESCRIPTION:
Mapping XS 5ffe367d
END DESCRIPTION:
XS GIS Cut Line= 3
      2398184.81     13586659.16      2398371.44     13586242.49
      2398276.15     13585618.78
#Sta/Elev= 30
    4399  484.07  4406.3  483.83  4491.2   479.8  4583.6  477.59  4606.8  476.17
  4612.3  477.11    4630  474.52  4658.1  473.81  4720.2  474.31  4751.4  473.92
  4819.9  475.45  4826.5  474.29    4832  474.55  4839.8  473.67  4840.1  473.17
  4843.6  473.17  4843.8  473.67  4853.8  474.01  4861.6  475.14  4866.6   474.6
  4923.8  476.72  4930.1  476.65  4935.1  475.77  4974.4  475.67    5025  474.18
  5055.3     475  5161.8  481.92    5288   486.6    5463   493.9  5486.5   495.4
#Mann= 7 ,-1 , 0
    4399     .04       0  4406.3     .05       0  4658.1     .12       0
  4720.2     .05       0  4839.8     .05       0  4843.8     .05       0
  5161.8     .04       0
Bank Sta=4839.8,4843.8
XS Rating Curve= 0 ,0
Exp/Cntr=0.3,0.1

Type RM Length L Ch R = 1 ,421391  ,90,90,90
BEGIN DESCRIPTION:
Mapping XS a2c6f991
END DESCRIPTION:
XS GIS Cut Line= 4
       2398211.7     13586660.05      2398427.86     13586232.95
      2398433.07     13586071.49      2398396.64     13585639.56
#Sta/Elev= 30
  4362.8  484.44  4364.9  484.19  4422.2  479.69  4494.6  477.07  4516.9  476.74
  4533.6  477.36  4539.2   476.7  4570.2  477.21  4583.7   476.9  4600.4  474.19
  4662.5     474  4667.4  473.98  4739.7   473.6  4778.7  474.26  4816.8  473.39
  4869.5  474.63  4879.5  471.93  4906.1  472.33  4917.5   470.2  4917.7   469.7
  4921.2   469.7  4921.5   470.2  4929.5  472.01  4939.5  472.71    5003  472.13
    5130  477.05  5180.1  479.38  5222.9  482.97  5276.5  486.38  5436.5  493.27
#Mann= 7 ,-1 , 0
  4362.8     .04       0  4364.9     .05       0  4662.5     .12       0
  4667.4     .05       0  4917.5     .05       0  4921.5     .05       0
  5222.9     .04       0
Bank Sta=4917.5,4921.5
XS Rating Curve= 0 ,0
Exp/Cntr=0.3,0.1

Type RM Length L Ch R = 1 ,421301  ,306,306,306
BEGIN DESCRIPTION:
SALT CREEK 141.0
END DESCRIPTION:
XS GIS Cut Line= 3
        2398225.     13586674.99        2398525.       13586075.
      2398474.99     13585774.95
#Sta/Elev= 30
  4333.3  485.21  4347.3  484.46  4408.8  479.32  4467.5  476.98  4556.9   476.1
  4579.3  474.62  4615.6  473.76  4632.4  474.25    4638  473.61  4780.5  473.73
  4811.3   472.1  4847.6  473.25  4878.3  470.39  4896.3  470.17  4928.6  469.82
  4945.4  471.71  4959.4  471.48  4973.4  469.62  4988.1  469.18  4988.4  468.68
  4991.9  468.68  4992.1  469.18  5014.3  469.74  5037.1   471.9  5097.9  473.76
    5146   476.8  5196.7  478.81  5235.7  481.64  5267.7  484.87  5308.3  486.72
#Mann= 6 ,-1 , 0
  4333.3     .04       0  4347.3     .05       0  4896.3     .12       0
  4988.1     .05       0  4992.1     .12       0  5235.7     .05       0
Bank Sta=4988.1,4992.1
XS Rating Curve= 0 ,0
Exp/Cntr=0.3,0.1

Type RM Length L Ch R = 1 ,420995  ,407,407,407
BEGIN DESCRIPTION:
Mapping XS e1769500
END DESCRIPTION:
XS GIS Cut Line= 3
      2398576.42      13586865.7      2398812.35     13586125.14
      2398662.05      13585478.2
#Sta/Elev= 30
  4252.4  491.45    4568  476.02  4588.7   475.2  4593.9  475.77  4614.1  473.98
  4658.3  472.48  4819.4  471.32  4856.9  472.77  4882.8  469.74  4889.1  468.64
  4894.3  466.66  4917.1  465.58  4919.3  465.28  4919.6  464.78  4923.3  465.28
  4926.6  465.97  4935.3  465.55  4966.8  467.08  4985.7  469.13  4998.3   468.2
    5018  468.41  5023.2  467.58  5027.1  465.87  5042.6  465.47  5060.6  468.56
  5080.1  468.45  5205.9  473.34  5255.6  476.66  5303.5  481.29  5693.8  496.11
#Mann= 6 ,-1 , 0
  4252.4     .04       0  4614.1     .05       0  4917.1     .12       0
  4919.3     .05       0  4923.3     .12       0  5205.9     .04       0
Bank Sta=4919.3,4923.3
XS Rating Curve= 0 ,0
Exp/Cntr=0.3,0.1

Type RM Length L Ch R = 1 ,420588  ,386,386,386
BEGIN DESCRIPTION:
Mapping XS f82e0091
END DESCRIPTION:
XS GIS Cut Line= 3
      2398792.69     13586937.81      2399159.71     13586177.57
      2399008.97     13585404.22
#Sta/Elev= 30
  4102.1  491.87  4319.7  480.04  4414.3  476.14  4549.4  473.85  4555.4  473.16
    4787  466.93  4832.3  466.74  4854.9  467.83  4867.8  467.58  4915.8  465.98
  4969.3  466.74  4989.7  464.91  4995.9   463.5    5001   463.7    5008  461.85
  5008.3  461.35    5012  461.85  5030.4  463.31    5061  468.11  5071.2  468.71
  5167.8  468.85  5202.3  469.97  5234.2  472.21  5253.9  473.91  5264.7  476.31
  5285.1  476.64  5305.5  475.53  5330.7   477.4  5522.1  485.15  5734.2  495.56
#Mann= 7 ,-1 , 0
  4102.1     .04       0  4319.7     .05       0  4867.8     .12       0
    5008     .05       0    5012     .12       0  5167.8     .05       0
  5330.7     .04       0
Bank Sta=5008,5012
XS Rating Curve= 0 ,0
Exp/Cntr=0.3,0.1

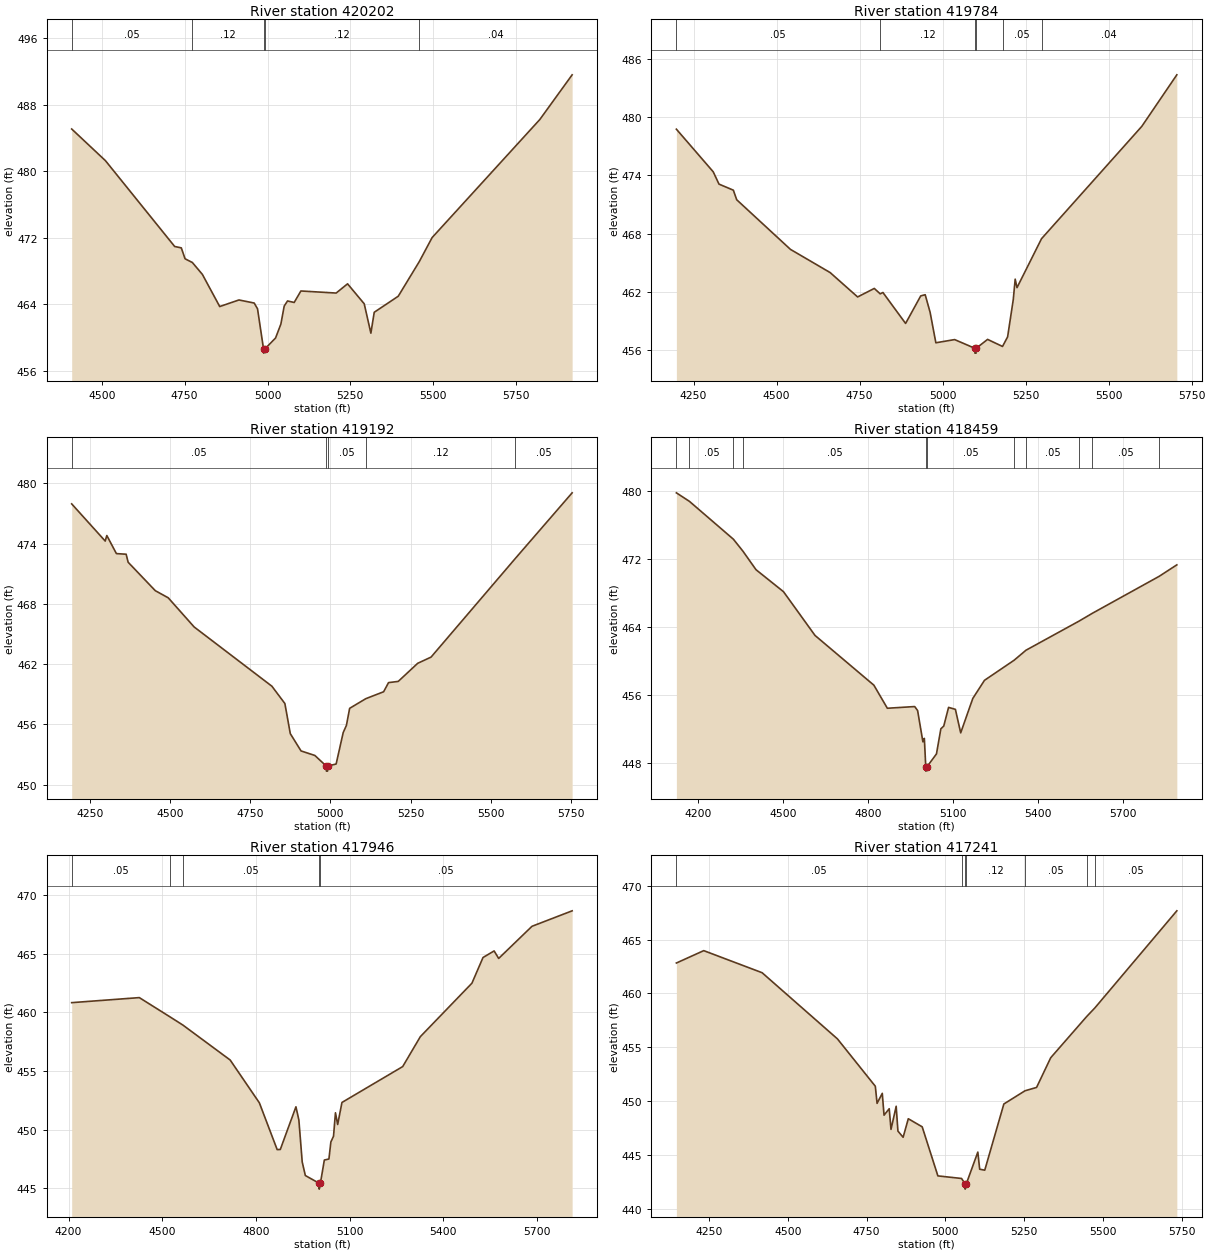
Type RM Length L Ch R = 1 ,420202  ,418,418,418
BEGIN DESCRIPTION:
Mapping XS 3e1dcc04
END DESCRIPTION:
XS GIS Cut Line= 4
      2399251.45     13586891.97      2399408.75     13586380.74
      2399356.32     13585902.31      2399186.48     13585438.51
#Sta/Elev= 30
  4409.1  485.06    4511  481.25  4719.8  470.94  4739.9  470.77  4751.2  469.46
  4773.3  469.01  4803.5  467.58  4855.8  463.72  4913.8  464.51  4959.8  464.14
  4969.9  463.44    4988  458.62  4988.3  458.12    4992  458.62  5024.3  459.94
  5040.3  461.61  5050.4  463.78  5060.4  464.39  5080.5  464.21  5100.7  465.59
  5207.1  465.34  5241.5  466.45  5291.8  464.05  5311.9  460.52    5322  463.03
  5394.5  464.96  5458.1  469.13  5496.7  472.01  5821.7   486.2  5919.2  491.57
#Mann= 5 ,-1 , 0
  4409.1     .05       0  4773.3     .12       0    4988     .05       0
    4992     .12       0  5458.1     .04       0
Bank Sta=4988,4992
XS Rating Curve= 0 ,0
Exp/Cntr=0.3,0.1

Type RM Length L Ch R = 1 ,419784  ,592,592,592
BEGIN DESCRIPTION:
Mapping XS 25df723a
END DESCRIPTION:
XS GIS Cut Line= 3
      2399690.57     13586924.72      2399782.32      13586315.2
      2399402.42     13585509.56
#Sta/Elev= 30
  4198.3  478.79  4309.3  474.38  4326.6  473.11  4369.9  472.48    4380  471.49
  4541.8  466.36  4661.4  463.96  4744.1  461.44  4794.3  462.32  4812.1  461.76
  4820.3   461.9  4888.6   458.7  4934.2  461.55  4947.6  461.67  4962.5  459.84
  4979.7   456.7  5036.3  457.03  5097.2  456.13  5097.4  455.63  5100.9  455.63
  5101.2  456.13  5135.5  457.05  5180.5  456.32  5195.8  457.31  5212.9  461.18
  5218.6  463.28  5224.1   462.4  5297.9  467.46  5599.9  479.08  5705.4  484.41
#Mann= 6 ,-1 , 0
  4198.3     .05       0  4812.1     .12       0  5097.2     .05       0
  5101.2     .12       0  5180.5     .05       0  5297.9     .04       0
Bank Sta=5097.2,5101.2
XS Rating Curve= 0 ,0
Exp/Cntr=0.3,0.1

Type RM Length L Ch R = 1 ,419192  ,733,733,733
BEGIN DESCRIPTION:
Mapping XS d8cd8f54
END DESCRIPTION:
XS GIS Cut Line= 3
      2399985.48     13587023.06      2400110.01     13586131.69
      2400018.52     13585478.19
#Sta/Elev= 30
  4193.9  477.95  4298.4  474.25  4303.4   474.8  4333.3     473  4363.6  472.94
  4369.9  472.14  4454.5  469.31  4494.9   468.6  4575.6   465.7    4818   459.8
  4858.4  458.08  4875.3  455.08  4908.8  453.36  4951.8  452.91  4987.6  451.85
  4987.9  451.35  4991.4  451.35  4991.6  451.85  5018.2  452.06  5040.1  455.18
  5050.2   455.9  5060.3   457.6  5110.6  458.56  5166.2  459.25  5181.5  460.16
  5211.8  460.28  5272.3  462.08  5314.1   462.7  5576.5  472.51  5753.8  479.05
#Mann= 5 ,-1 , 0
  4193.9     .05       0  4987.6     .05       0  4991.6     .05       0
  5110.6     .12       0  5576.5     .05       0
Bank Sta=4987.6,4991.6
XS Rating Curve= 0 ,0
Exp/Cntr=0.3,0.1

Type RM Length L Ch R = 1 ,418459  ,513,513,513
BEGIN DESCRIPTION:
Mapping XS b2cce486
END DESCRIPTION:
XS GIS Cut Line= 4
      2400503.23     13587062.37      2400699.86     13586256.22
      2400601.55     13585830.22      2400457.36     13585351.76
#Sta/Elev= 30
  4123.2  479.82  4169.5  478.81  4324.6  474.35    4358  472.95  4404.3  470.76
  4501.3  468.17  4612.7  463.01  4820.4  457.15    4868  454.43  4964.5  454.63
  4974.8  454.16  4993.5  450.47  4998.6  450.88  5003.6  447.52  5003.8  447.02
  5007.6  447.52  5041.4  449.05  5056.9  452.01  5067.1  452.33  5084.1  454.53
  5108.2   454.3  5126.9  451.53  5169.7  455.59  5210.8  457.72  5315.5  460.09
  5357.4  461.27  5544.7   464.7  5592.1  465.63  5827.6  469.98  5889.9  471.33
#Mann= 11 ,-1 , 0
  4123.2     .12       0  4169.5     .05       0  4324.6     .12       0
    4358     .05       0  5003.6     .05       0  5007.6     .05       0
  5315.5     .12       0  5357.4     .05       0  5544.7     .12       0
  5592.1     .05       0  5827.6     .12       0
Bank Sta=5003.6,5007.6
XS Rating Curve= 0 ,0
Exp/Cntr=0.3,0.1

Type RM Length L Ch R = 1 ,417946  ,705,705,705
BEGIN DESCRIPTION:
Mapping XS 036eeaa0
END DESCRIPTION:
XS GIS Cut Line= 3
      2401165.18     13586760.88      2401106.19     13585980.96
      2400621.59     13585319.54
#Sta/Elev= 30
  4210.2  460.82  4426.7  461.25  4524.8  459.61  4566.1  458.91  4717.5  455.93
    4811  452.28    4868  448.29    4878   448.3  4928.1  451.94  4937.5  450.81
  4948.2  447.23  4958.2  446.08  5002.4  445.42  5002.6  444.92  5006.4  445.42
    5019   447.4  5033.7  447.49  5039.9  448.94  5048.4  449.43  5054.6  451.43
  5061.7  450.43  5075.4  452.31  5269.9  455.37  5326.3  457.92  5491.5  462.48
    5527  464.67  5562.5  465.23  5577.1  464.59  5683.7  467.33  5812.3  468.65
#Mann= 5 ,-1 , 0
  4210.2     .05       0  4524.8     .12       0  4566.1     .05       0
  5002.4     .05       0  5006.4     .05       0
Bank Sta=5002.4,5006.4
XS Rating Curve= 0 ,0
Exp/Cntr=0.3,0.1

Type RM Length L Ch R = 1 ,417241  ,504,504,504
BEGIN DESCRIPTION:
Mapping XS 63cecfe5
END DESCRIPTION:
XS GIS Cut Line= 3
      2401460.11     13586288.95      2401578.07     13585817.11
      2401066.87     13584840.59
#Sta/Elev= 30
  4146.3  462.83  4233.2  463.98  4418.4  461.93  4657.6  455.78  4777.8  451.38
  4783.4  449.79  4799.9  450.72  4805.5  448.69  4821.9  449.29  4827.6  447.37
    4844  449.52  4849.6  447.21  4866.1  446.64  4882.5  448.36  4926.6  447.61
  4976.4  443.05  5051.5  442.81  5062.7  442.32  5062.9  441.82  5066.7  442.32
  5103.2  445.26  5109.1  443.67  5125.2  443.58  5185.8  449.73  5253.1  450.96
  5289.7  451.27  5334.6  454.03  5449.1  457.87  5474.8  458.66  5734.9  467.68
#Mann= 7 ,-1 , 0
  4146.3     .05       0  5051.5     .12       0  5062.7     .05       0
  5066.7     .12       0  5253.1     .05       0  5449.1     .12       0
  5474.8     .05       0
Bank Sta=5062.7,5066.7
XS Rating Curve= 0 ,0
Exp/Cntr=0.3,0.1

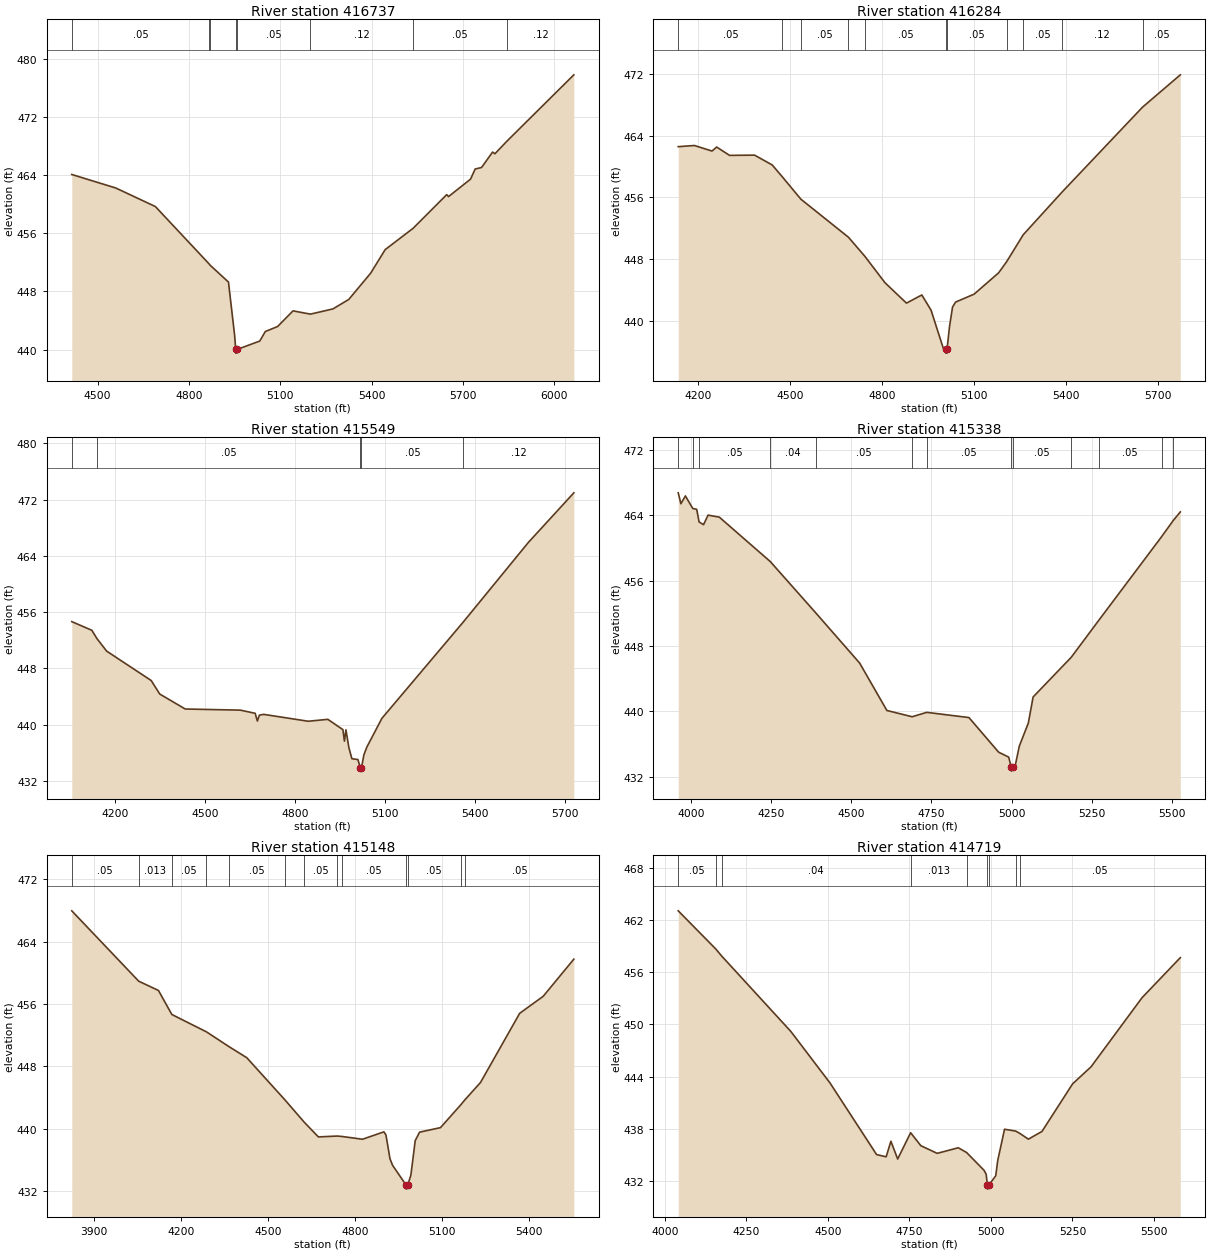
Type RM Length L Ch R = 1 ,416737  ,453,453,453
BEGIN DESCRIPTION:
Mapping XS b4971aae
END DESCRIPTION:
XS GIS Cut Line= 4
      2401669.82     13586033.39      2401768.13     13585712.25
      2401656.71     13584906.13      2401382.52      13584488.3
#Sta/Elev= 30
  4414.9  464.07  4559.6  462.21  4689.6  459.66  4866.4  451.76  4869.3   451.6
  4929.7  449.28  4949.9  441.96  4953.6  440.01  4953.8  439.51  4957.3  439.51
  4957.6  440.01  5032.5  441.17  5050.8  442.48  5091.2  443.17  5141.7  445.32
    5199  444.87  5272.9  445.59  5324.9  446.89  5396.8   450.5  5444.5  453.74
  5536.2  456.67  5646.7   461.3  5652.6  461.03    5725  463.43  5740.1  464.82
  5761.1  465.03  5797.3  467.15  5805.1  466.92  5845.2  468.68  6064.3  477.77
#Mann= 8 ,-1 , 0
  4414.9     .05       0  4866.4     .12       0  4869.3     .05       0
  4953.6     .05       0  4957.6     .05       0    5199     .12       0
  5536.2     .05       0  5845.2     .12       0
Bank Sta=4953.6,4957.6
XS Rating Curve= 0 ,0
Exp/Cntr=0.3,0.1

Type RM Length L Ch R = 1 ,416284  ,735,735,735
BEGIN DESCRIPTION:
Mapping XS 50bbab4d
END DESCRIPTION:
XS GIS Cut Line= 3
      2401800.88     13586013.76      2402049.94      13585633.6
      2402095.82     13584453.88
#Sta/Elev= 30
  4136.6  462.57  4189.3  462.72  4246.6     462  4261.7  462.52  4303.8  461.44
  4385.3  461.47  4442.6   460.2    4476  458.64  4536.1  455.76    4691  450.83
  4744.4  448.36  4809.8  444.94  4879.9  442.29  4929.9  443.35    4960  441.37
    5000  436.42    5008  436.31  5008.3  435.81  5011.8  435.81    5012  436.31
    5020  439.23    5030  441.79    5040  442.43  5100.1  443.45  5180.1  446.22
  5206.6  447.69  5260.1  451.15  5385.8  456.65  5648.7  467.69  5771.7  471.88
#Mann= 11 ,-1 , 0
  4136.6     .05       0    4476     .12       0  4536.1     .05       0
    4691     .12       0  4744.4     .05       0    5008     .05       0
    5012     .05       0  5206.6     .12       0  5260.1     .05       0
  5385.8     .12       0  5648.7     .05       0
Bank Sta=5008,5012
XS Rating Curve= 0 ,0
Exp/Cntr=0.3,0.1

Type RM Length L Ch R = 1 ,415549  ,211,211,211
BEGIN DESCRIPTION:
Mapping XS 4cf10243
END DESCRIPTION:
XS GIS Cut Line= 4
      2402064.48     13585798.78      2402678.55     13585236.28
      2402682.56     13585024.45      2402352.45     13584488.36
#Sta/Elev= 30
    4056  454.66    4123  453.43  4139.8  452.26  4172.3  450.47  4320.9  446.29
  4349.3  444.37  4434.4  442.24  4618.1  442.08  4667.5  441.63  4674.9  440.53
  4681.6  441.36  4695.8  441.48  4844.4   440.5    4910  440.77  4960.1  439.31
  4965.2  437.67  4970.2  439.28  4980.1  436.74  4990.1  435.17  5010.1  435.06
  5018.1  433.91  5018.3  433.41  5021.8  433.41  5022.1  433.91  5030.1  435.73
  5040.1  436.84  5090.1  440.91  5361.6  454.61    5579  465.94  5730.2  472.97
#Mann= 5 ,-1 , 0
    4056     .12       0  4139.8     .05       0  5018.1     .05       0
  5022.1     .05       0  5361.6     .12       0
Bank Sta=5018.1,5022.1
XS Rating Curve= 0 ,0
Exp/Cntr=0.3,0.1

Type RM Length L Ch R = 1 ,415338  ,190,190,190
BEGIN DESCRIPTION:
Mapping XS 8a3243f7
END DESCRIPTION:
XS GIS Cut Line= 4
      2403592.27      13585729.3      2402967.28     13585125.15
      2402835.34     13585034.87      2402529.89     13584590.58
#Sta/Elev= 30
    3959  466.76  3967.3  465.42  3981.4  466.38  4004.4  464.84  4016.7  464.74
  4024.2  463.19    4038  462.86  4052.2  464.03  4087.4  463.78  4246.3  458.35
  4388.5  452.06  4525.8   445.9  4610.7   440.1  4689.7  439.33  4735.2  439.87
  4867.1  439.23  4959.8  434.99  4991.1  434.39  4999.3  433.17  4999.7  432.67
  5004.5  433.17  5010.7  433.17  5024.4  435.73  5052.6  438.56  5067.5  441.75
  5186.7  446.62  5272.4  451.13  5468.7  461.38  5505.4  463.38  5527.3  464.42
#Mann= 13 ,-1 , 0
    3959     .05       0  4004.4    .013       0  4024.2     .05       0
  4246.3     .04       0  4388.5     .05       0  4689.7    .013       0
  4735.2     .05       0  4999.3     .05       0  5004.5     .05       0
  5186.7     .12       0  5272.4     .05       0  5468.7     .12       0
  5505.4     .05       0
Bank Sta=4999.3,5004.5
XS Rating Curve= 0 ,0
Exp/Cntr=0.3,0.1

Type RM Length L Ch R = 1 ,415148  ,429,429,429
BEGIN DESCRIPTION:
Mapping XS 374416f1
END DESCRIPTION:
XS GIS Cut Line= 3
      2403944.01     13585587.73      2403052.68     13585030.65
      2402673.58     13584468.54
#Sta/Elev= 30
  3824.2  467.94  4054.8  458.91  4122.8  457.72  4168.8  454.64  4288.1  452.41
  4364.6  450.54    4427  449.09  4559.3  443.64  4624.5  440.83  4673.5  438.93
  4738.5  439.04  4754.2  438.99  4825.6  438.63  4899.1  439.58  4906.2  439.19
  4920.1  436.13    4929  435.29    4976  432.73  4976.4  432.23  4981.2  432.73
  4992.1  434.04    5007  438.45    5022  439.54    5094  440.12  5163.7  443.04
  5178.8  443.72  5231.8  445.91  5366.8  454.79  5447.7  456.97  5553.3  461.74
#Mann= 13 ,-1 , 0
  3824.2     .05       0  4054.8    .013       0  4168.8     .05       0
  4288.1     .04       0  4364.6     .05       0  4559.3     .04       0
  4624.5     .05       0  4738.5    .013       0  4754.2     .05       0
    4976     .05       0  4981.2     .05       0  5163.7     .12       0
  5178.8     .05       0
Bank Sta=4976,4981.2
XS Rating Curve= 0 ,0
Exp/Cntr=0.3,0.1

Type RM Length L Ch R = 1 ,414719  ,723,723,723
BEGIN DESCRIPTION:
Mapping XS f96c86d4
END DESCRIPTION:
XS GIS Cut Line= 3
      2403924.34     13585319.02      2403590.09     13584886.47
      2402790.56     13584296.65
#Sta/Elev= 30
  4040.9  463.05  4156.5  458.65  4174.6  457.84  4386.2   449.2  4506.6  443.27
  4649.4  435.05  4678.7  434.79  4693.3  436.58  4714.1  434.54  4753.8  437.56
  4785.1  436.07  4835.2  435.19    4900  435.83  4925.4  435.29  4979.1  433.24
  4985.6  432.78  4989.2  431.58  4989.6  431.08  4994.5  431.58  5014.9  432.62
  5021.1  434.38  5041.9  437.96  5076.1  437.75  5089.2  437.47  5115.1  436.82
  5156.8  437.71  5250.8  443.18  5307.2  445.13  5463.7  453.07  5581.1  457.67
#Mann= 9 ,-1 , 0
  4040.9     .05       0  4156.5    .013       0  4174.6     .04       0
  4753.8    .013       0  4925.4     .05       0  4989.2     .05       0
  4994.5     .05       0  5076.1     .12       0  5089.2     .05       0
Bank Sta=4989.2,4994.5
XS Rating Curve= 0 ,0
Exp/Cntr=0.3,0.1

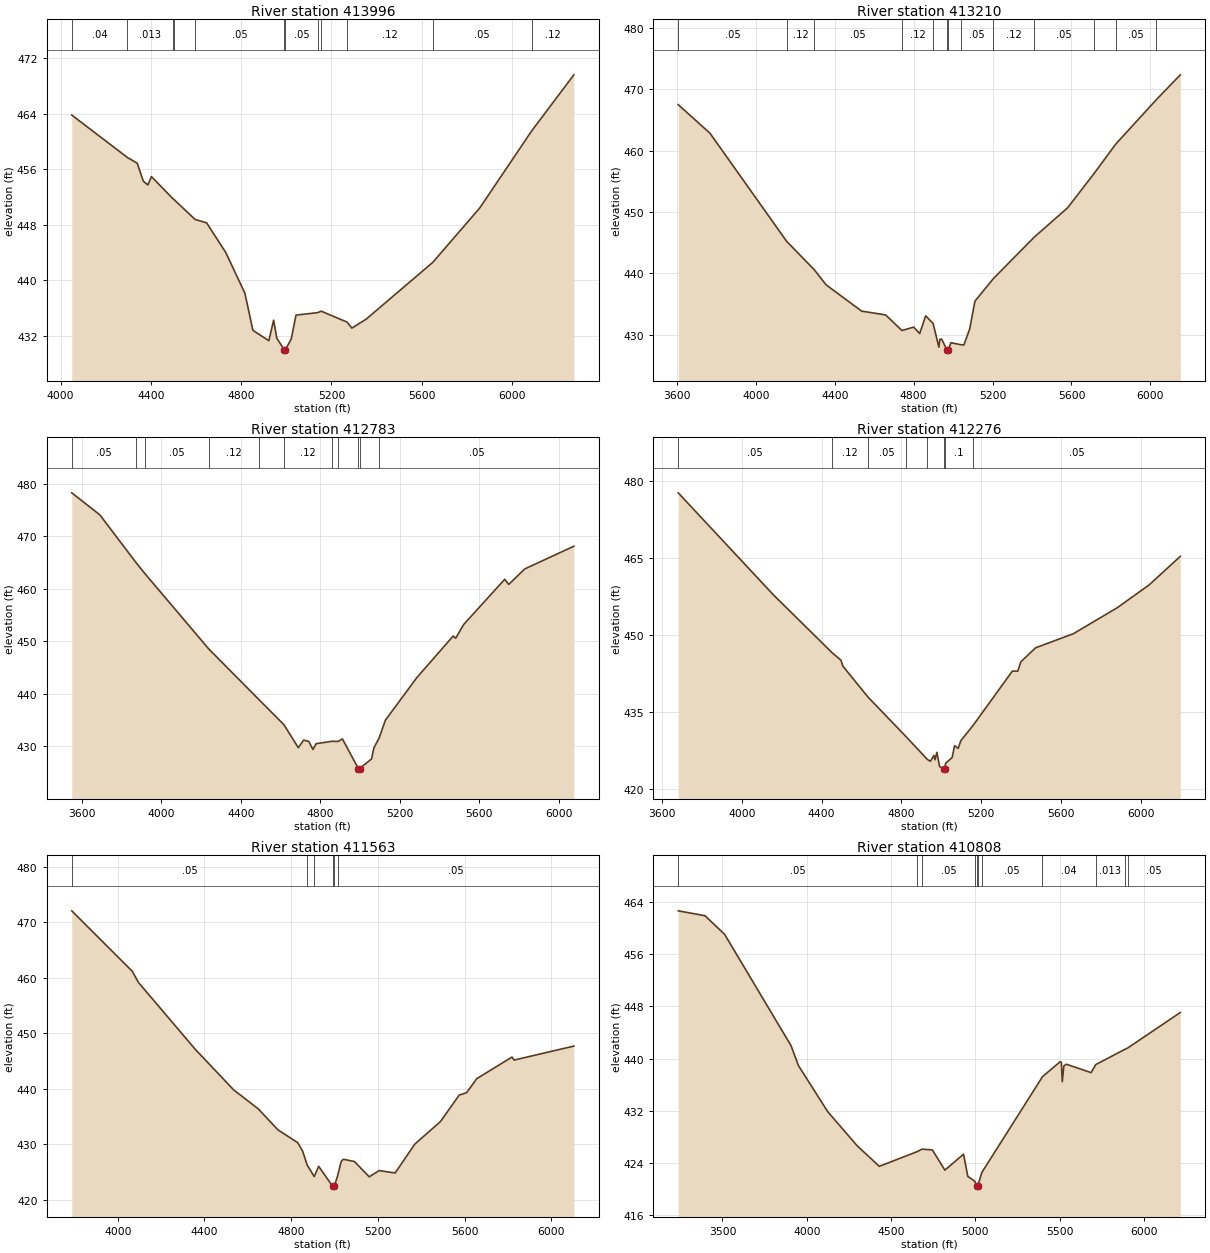
Type RM Length L Ch R = 1 ,413996  ,786,786,786
BEGIN DESCRIPTION:
Mapping XS f006e918
END DESCRIPTION:
XS GIS Cut Line= 4
      2404134.06     13585168.25      2404048.86     13584617.76
      2403413.14     13583955.82      2402672.59     13583844.41
#Sta/Elev= 30
  4049.9  463.83  4296.1  457.72  4339.8  456.89  4366.9  454.29  4387.1  453.76
  4402.8  454.96  4496.4  451.82  4501.5  451.68  4596.6  448.77    4647   448.3
  4731.9  444.02  4816.8  438.14  4852.1   432.8  4922.8   431.3  4943.9  434.26
  4958.1  431.65  4990.9  430.01  4991.3  429.51  4996.3  430.01  5021.9  431.54
    5043  434.99  5139.2  435.35  5154.6  435.56  5269.4  433.98  5290.5  433.12
  5354.3  434.42    5649   442.6  5856.5  450.42  6086.6  461.53  6273.6  469.63
#Mann= 12 ,-1 , 0
  4049.9     .04       0  4296.1    .013       0  4496.4     .05       0
  4501.5     .04       0  4596.6     .05       0  4990.9     .05       0
  4996.3     .05       0  5139.2     .12       0  5154.6     .05       0
  5269.4     .12       0    5649     .05       0  6086.6     .12       0
Bank Sta=4990.9,4996.3
XS Rating Curve= 0 ,0
Exp/Cntr=0.3,0.1

Type RM Length L Ch R = 1 ,413210  ,427,427,427
BEGIN DESCRIPTION:
Mapping XS bcc0900b
END DESCRIPTION:
XS GIS Cut Line= 3
      2405058.14     13584152.43      2404297.91      13583831.3
        2402602.     13583549.74
#Sta/Elev= 30
  3607.1  467.46  3767.7  462.82  4156.6  445.23  4296.9   440.6  4356.4  438.16
  4536.7  433.88  4658.3  433.26  4740.7  430.73  4800.3  431.28  4830.7  430.23
  4861.1  433.12    4899  431.86  4927.9  428.03  4932.9  429.29  4942.2  429.33
  4969.1  427.55  4969.6  427.05    4976  427.55  4988.8  428.74  5037.8  428.43
  5054.8  428.39  5084.1  430.97  5110.7   435.5  5204.2  439.17  5409.9  445.87
  5580.8   450.7  5713.2  456.21  5825.7   461.1  6030.7  468.29  6151.5  472.31
#Mann= 13 ,-1 , 0
  3607.1     .05       0  4156.6     .12       0  4296.9     .05       0
  4740.7     .12       0    4899      .1       0  4969.1     .05       0
    4976      .1       0  5037.8     .05       0  5204.2     .12       0
  5409.9     .05       0  5713.2     .12       0  5825.7     .05       0
  6030.7     .12       0
Bank Sta=4969.1,4976
XS Rating Curve= 0 ,0
Exp/Cntr=0.3,0.1

Type RM Length L Ch R = 1 ,412783  ,507,507,507
BEGIN DESCRIPTION:
Mapping XS 9e38d306
END DESCRIPTION:
XS GIS Cut Line= 4
      2405248.23     13583929.62      2404645.26     13583647.79
      2403282.06     13583195.58        2402858.     13583169.48
#Sta/Elev= 30
  3548.9  478.29  3690.1   474.1  3870.7  465.09    3917  462.91  4238.7  448.55
  4491.6  438.89  4616.5  434.15    4689  429.76  4715.4   431.2  4741.6  430.96
  4762.6  429.42  4778.8  430.53  4858.6  430.98  4890.4  430.96  4910.8  431.44
    4991   425.8  4991.5   425.3  4997.9   425.8  5057.6  427.62  5069.2   429.7
  5095.7  431.62  5127.3     435  5285.7  443.12  5468.5  451.03  5481.1  450.61
  5521.2  453.22  5727.9  461.83    5748  460.85  5828.1  463.79  6075.6  468.12
#Mann= 11 ,-1 , 0
  3548.9     .05       0  3870.7     .12       0    3917     .05       0
  4238.7     .12       0  4491.6     .05       0  4616.5     .12       0
  4858.6     .05       0  4890.4      .1       0    4991     .05       0
  4997.9      .1       0  5095.7     .05       0
Bank Sta=4991,4997.9
XS Rating Curve= 0 ,0
Exp/Cntr=0.3,0.1

Type RM Length L Ch R = 1 ,412276  ,713,713,713
BEGIN DESCRIPTION:
Mapping XS be977788
END DESCRIPTION:
XS GIS Cut Line= 4
      2405451.35      13583588.8      2404704.24     13583261.12
      2403898.12     13582900.66       2403079.5     13582874.46
#Sta/Elev= 30
  3680.7  477.63  4157.2  457.82  4452.8  446.52  4496.5  445.09  4506.6  443.92
  4632.5  437.91  4823.1  430.22  4929.5  425.81  4945.2  425.42    4963  426.56
  4968.4  425.72  4977.7  427.16  4991.6  424.39  5011.4  424.01  5011.9  423.51
  5018.4  424.01  5021.5  425.04  5054.3  426.15  5066.7  428.47  5084.5  427.93
  5098.2  429.45  5160.6  432.46  5356.1  442.95  5383.6  442.96  5398.9  444.77
  5472.7  447.49  5662.8  450.24  5882.9   455.3    6043  459.75  6198.6  465.28
#Mann= 8 ,-1 , 0
  3680.7     .05       0  4452.8     .12       0  4632.5     .05       0
  4823.1     .12       0  4929.5      .1       0  5011.4     .05       0
  5018.4      .1       0  5160.6     .05       0
Bank Sta=5011.4,5018.4
XS Rating Curve= 0 ,0
Exp/Cntr=0.3,0.1

Type RM Length L Ch R = 1 ,411563  ,755,755,755
BEGIN DESCRIPTION:
Mapping XS 396edd39
END DESCRIPTION:
XS GIS Cut Line= 4
      2405536.59     13583287.34       2405051.6     13582717.15
      2404206.15     13582317.37      2403583.58     13582422.22
#Sta/Elev= 30
  3788.1  472.03    4067  461.14  4095.6  459.12  4358.1  447.05  4534.8  439.75
    4648  436.34    4739  432.55  4830.1  430.24  4852.8  428.71  4873.4  426.23
  4906.2  424.14  4926.6  425.98  4991.3  422.37  4991.8  421.87  4998.4  422.37
  5013.5  424.21  5030.7  426.87  5040.4  427.25  5091.5  426.85  5159.7  424.09
  5205.3  425.21  5279.1  424.78  5370.1  429.99    5488  434.04  5574.4  438.81
    5609  439.26  5655.6  441.78  5817.8  445.67    5828  445.13  6103.2  447.65
#Mann= 6 ,-1 , 0
  3788.1     .05       0  4873.4     .12       0  4906.2      .1       0
  4991.3     .05       0  4998.4      .1       0  5013.5     .05       0
Bank Sta=4991.3,4998.4
XS Rating Curve= 0 ,0
Exp/Cntr=0.3,0.1

Type RM Length L Ch R = 1 ,410808  ,1065,1065,1065
BEGIN DESCRIPTION:
Mapping XS d595146c
END DESCRIPTION:
XS GIS Cut Line= 4
      2405831.52      13583097.3      2405215.44     13582081.43
       2404455.2     13581806.17      2403544.18     13582173.19
#Sta/Elev= 30
  3237.6  462.64  3396.5  461.89  3512.8  459.04  3906.9  441.99    3951  438.93
  4125.5  431.85    4300  426.64  4430.7  423.51  4656.1  425.77  4682.9  426.14
  4745.2  426.03  4819.7  422.93  4930.3  425.37  4955.6  421.98  4997.1  421.23
  5007.5  420.52    5008  420.02  5014.7  420.52  5038.7  422.56  5398.7  437.24
    5504  439.54  5510.7  439.44  5516.1  436.48  5525.5  438.89  5540.3  439.15
  5687.2  437.86  5714.4  439.09    5890  441.46  5905.8  441.66  6216.4  447.07
#Mann= 11 ,-1 , 0
  3237.6     .05       0  4656.1     .12       0  4682.9     .05       0
  4997.1     .12       0  5007.5     .05       0  5014.7     .12       0
  5038.7     .05       0  5398.7     .04       0  5714.4    .013       0
    5890     .04       0  5905.8     .05       0
Bank Sta=5007.5,5014.7
XS Rating Curve= 0 ,0
Exp/Cntr=0.3,0.1