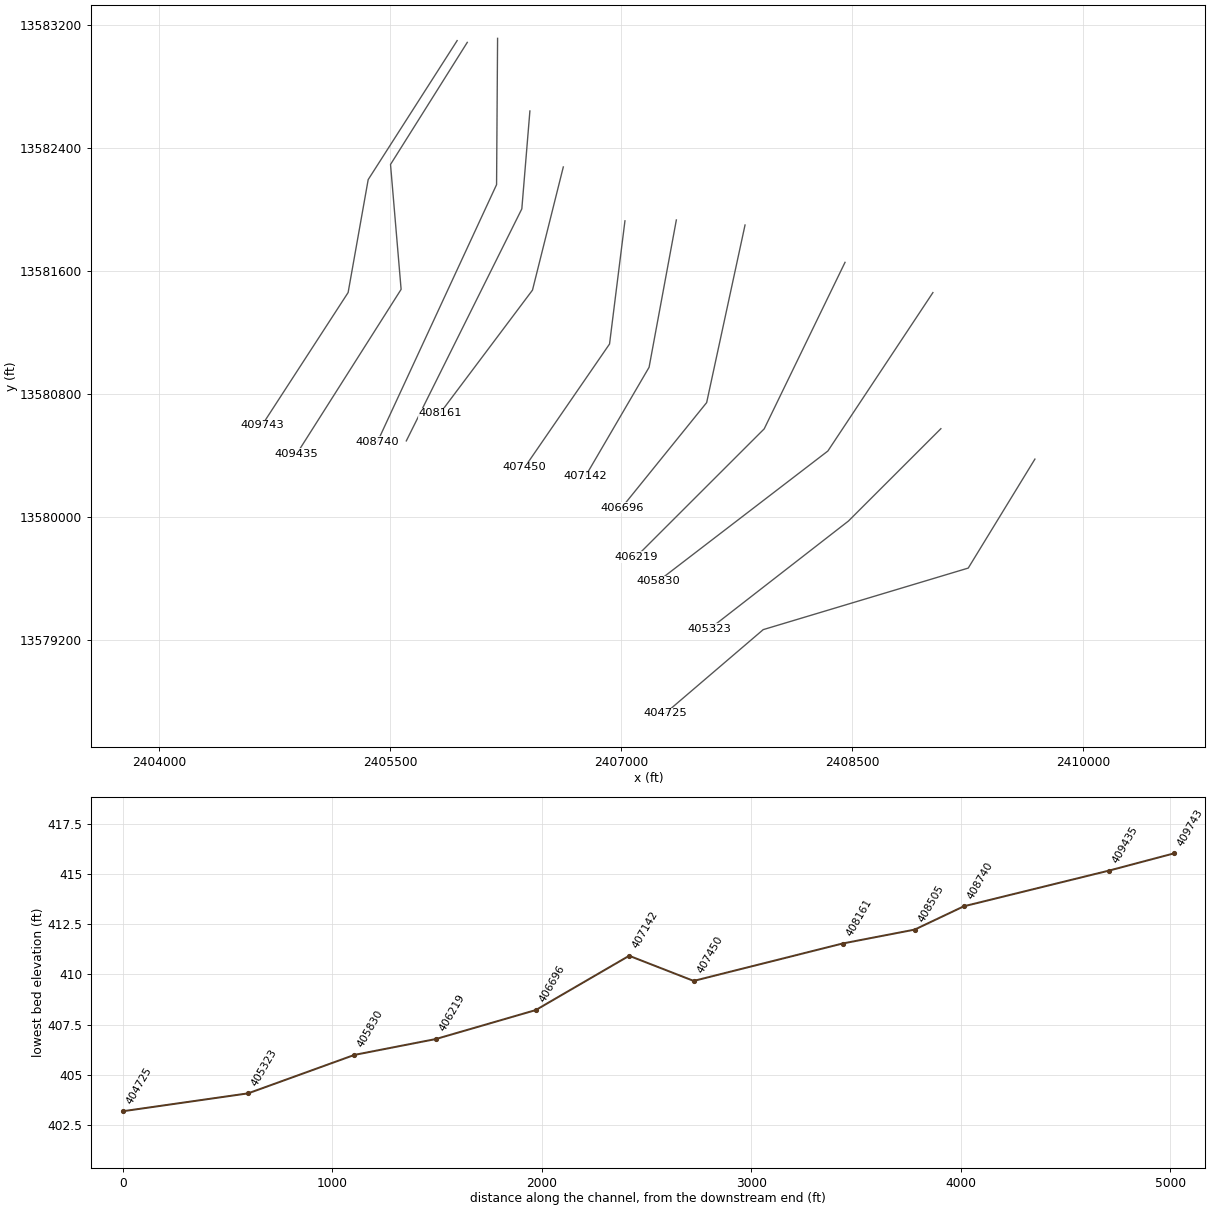
HEC-RAS study COLETO CREEK.prj: COLETO CREEK Base Level Engineering

--- COLETO CREEK.g01 (geometry) --- (continued)

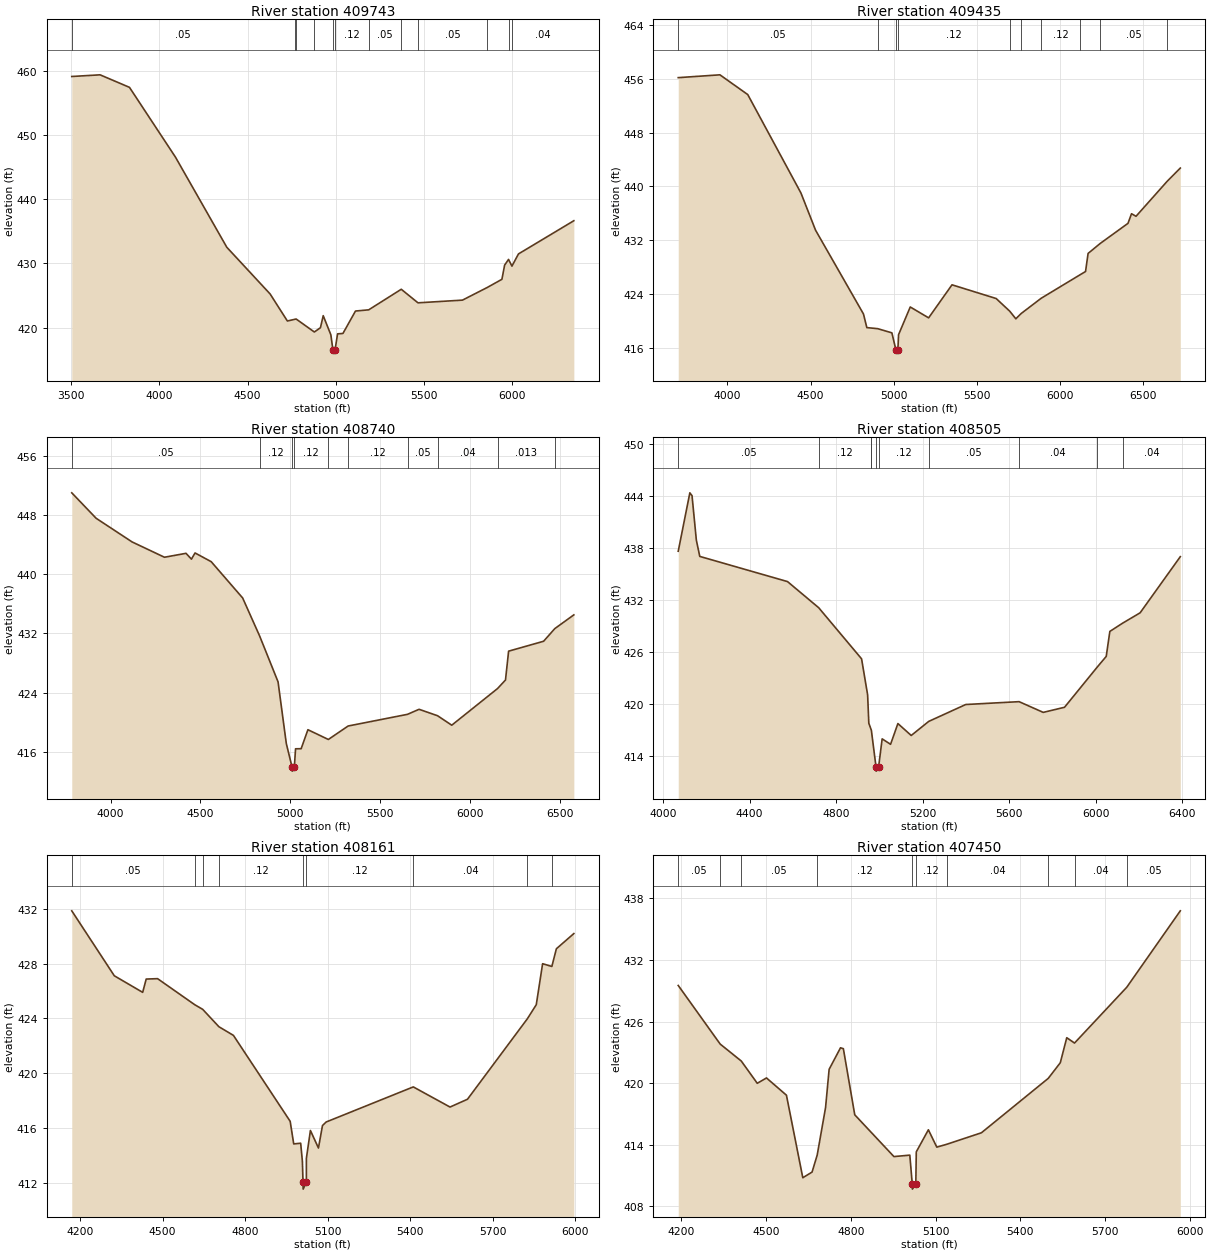
Type RM Length L Ch R = 1 ,409743  ,308,308,308
BEGIN DESCRIPTION:
Mapping XS 5f1dd911
END DESCRIPTION:
XS GIS Cut Line= 4
      2405936.13     13583095.52       2405358.9     13582192.78
      2405228.69     13581459.27      2404669.39     13580596.48
#Sta/Elev= 30
  3504.1  459.08  3664.5  459.34  3831.1  457.39  4091.6  446.53  4382.5   432.5
  4627.9  425.23  4725.7  421.02    4767  421.28  4775.4  421.33  4878.5  419.31
  4913.1  419.98  4928.8  421.85  4972.2  418.86  4983.8  416.52  4984.3  416.02
  4995.8  416.52  5010.1  419.02  5040.5  419.08  5111.6  422.57  5186.5  422.76
    5371  425.96  5465.7  423.85  5717.8  424.27    5859  426.25  5941.3  427.51
  5956.5  429.71  5978.7  430.61  5998.1  429.56    6035  431.46  6348.8  436.63
#Mann= 12 ,-1 , 0
  3504.1     .05       0    4767     .12       0  4775.4     .05       0
  4878.5     .12       0  4983.8     .05       0  4995.8     .12       0
  5186.5     .05       0    5371     .12       0  5465.7     .05       0
    5859    .013       0  5978.7     .05       0  5998.1     .04       0
Bank Sta=4983.8,4995.8
XS Rating Curve= 0 ,0
Exp/Cntr=0.3,0.1

Type RM Length L Ch R = 1 ,409435  ,695,695,695
BEGIN DESCRIPTION:
Mapping XS 5994fee2
END DESCRIPTION:
XS GIS Cut Line= 4
      2406001.92      13583084.2      2405503.81     13582291.15
      2405572.54     13581479.93      2404894.33     13580410.24
#Sta/Elev= 30
  3705.1  456.18  3955.6   456.6  4122.9  453.66  4442.1  439.03  4530.4  433.47
  4818.4  420.99  4838.5  418.97  4903.7  418.81    4989  418.19  5013.1  415.67
  5013.6  415.17  5025.1  415.67  5029.1  417.91  5099.4  422.04  5209.8  420.42
  5350.3  425.34  5615.6   423.3  5697.4  421.41  5733.9  420.28  5765.7  421.06
  5886.4  423.34  6122.3  426.87  6152.8  427.32  6168.1  430.01  6241.1   431.5
  6407.9  434.49  6429.1  435.92  6456.2  435.54  6643.7  440.76  6722.3  442.72
#Mann= 10 ,-1 , 0
  3705.1     .05       0  4903.7     .12       0  5013.1     .05       0
  5025.1     .12       0  5697.4     .04       0  5765.7     .05       0
  5886.4     .12       0  6122.3    .013       0  6241.1     .05       0
  6643.7     .04       0
Bank Sta=5013.1,5025.1
XS Rating Curve= 0 ,0
Exp/Cntr=0.3,0.1

Type RM Length L Ch R = 1 ,408740  ,235,235,235
BEGIN DESCRIPTION:
Mapping XS 2d1e8ff4
END DESCRIPTION:
XS GIS Cut Line= 3
      2406198.52     13583110.39      2406191.96     13582160.07
      2405418.62     13580488.87
#Sta/Elev= 30
  3784.5  451.02  3919.9  447.58  4119.9  444.38  4299.9  442.31  4419.9  442.84
  4449.9  442.05  4469.9  442.89  4559.9  441.71  4734.8   436.8  4829.2  431.66
  4931.6  425.46  4977.5  417.12  5009.9  413.89  5010.4  413.39    5022  413.89
  5028.8  416.41    5060  416.42  5097.6  418.99  5211.2  417.67  5321.2  419.49
  5651.4  421.07  5715.7  421.75  5818.5  420.88  5897.4   419.6  6151.8  424.55
  6196.2  425.71  6213.6  429.61  6408.1  430.95  6470.5  432.66  6576.3  434.52
#Mann= 10 ,-1 , 0
  3784.5     .05       0  4829.2     .12       0  5009.9     .05       0
    5022     .12       0  5211.2     .05       0  5321.2     .12       0
  5651.4     .05       0  5818.5     .04       0  6151.8    .013       0
  6470.5     .04       0
Bank Sta=5009.9,5022
XS Rating Curve= 0 ,0
Exp/Cntr=0.3,0.1

Type RM Length L Ch R = 1 ,408505  ,344,344,344
BEGIN DESCRIPTION:
Mapping XS fc70b5b5
END DESCRIPTION:
XS GIS Cut Line= 3
      2406408.24     13582638.54      2406355.81     13582002.78
      2405606.28     13580495.69
#Sta/Elev= 30
  4070.1  437.65  4123.8   444.4  4133.9  444.07  4153.9  438.92  4169.7  437.05
  4575.3  434.14  4719.4  431.12  4917.7  425.21  4945.6  421.06  4951.2  417.76
  4962.9  416.96    4963  416.94  4984.4  412.73  4984.9  412.23  4996.5  412.73
  5012.8  415.96  5051.8  415.33  5085.6  417.73  5147.2  416.35  5228.3  417.98
  5399.2  419.93  5645.9  420.26  5757.5  419.02  5855.9  419.61  6007.6  424.27
  6048.7  425.49  6065.5  428.38  6124.3  429.33  6205.4  430.53  6391.2  437.02
#Mann= 10 ,-1 , 0
  4070.1     .05       0  4719.4     .12       0  4962.9     .05       0
    4963     .12       0  4984.4     .05       0  4996.5     .12       0
  5228.3     .05       0  5645.9     .04       0  6007.6    .013       0
  6124.3     .04       0
Bank Sta=4984.4,4996.5
XS Rating Curve= 0 ,0
Exp/Cntr=0.3,0.1

Type RM Length L Ch R = 1 ,408161  ,711,711,711
BEGIN DESCRIPTION:
SALT CREEK 118.0
END DESCRIPTION:
XS GIS Cut Line= 3
      2406624.99     13582274.97        2406425.       13581475.
        2405825.     13580674.99
#Sta/Elev= 30
  4170.2  431.85  4324.8  427.11  4427.9   425.9  4440.7  426.87    4482   426.9
    4617     425    4646  424.66    4705  423.39  4757.7  422.76  4963.9  416.49
  4976.8  414.84  5002.1  414.89  5008.3  413.57  5010.6  412.04  5011.1  411.54
  5022.7  412.04  5022.9   413.8  5037.5  415.82  5066.7  414.54  5081.3  416.18
  5094.8  416.44  5411.3     419  5544.8  417.53  5608.3   418.1  5825.8  423.97
  5858.3     425  5881.3  427.99  5914.9  427.79  5931.3  429.08  5994.8  430.19
#Mann= 9 ,-1 , 0
  4170.2     .05       0    4617     .12       0    4646     .05       0
    4705     .12       0  5010.6     .05       0  5022.7     .12       0
  5411.3     .04       0  5825.8    .013       0  5914.9     .04       0
Bank Sta=5010.6,5022.7
XS Rating Curve= 0 ,0
Exp/Cntr=0.3,0.1

Type RM Length L Ch R = 1 ,407450  ,308,308,308
BEGIN DESCRIPTION:
SALT CREEK 117.0
END DESCRIPTION:
XS GIS Cut Line= 3
        2407025.       13581925.        2406925.       13581125.
      2406374.97     13580324.96
#Sta/Elev= 30
  4189.1  429.52  4337.6  423.81  4412.2  422.16  4468.8  419.99  4501.5  420.51
  4572.1  418.83    4630  410.79  4662.8  411.34    4681     413  4710.6  417.63
  4723.2  421.35  4763.5  423.45  4773.6  423.36  4813.9  416.92  4952.5  412.85
  5008.8  412.99  5017.4  410.18  5017.9  409.68    5030  410.18  5031.7  413.31
  5074.5  415.46  5104.3  413.77  5139.7  414.05  5262.3  415.17  5498.8  420.47
  5541.4  421.99  5564.3  424.43  5591.8  423.91  5776.5  429.34  5966.2  436.79
#Mann= 10 ,-1 , 0
  4189.1     .05       0  4337.6     .12       0  4412.2     .05       0
    4681     .12       0  5017.4     .05       0    5030     .12       0
  5139.7     .04       0  5498.8    .013       0  5591.8     .04       0
  5776.5     .05       0
Bank Sta=5017.4,5030
XS Rating Curve= 0 ,0
Exp/Cntr=0.3,0.1

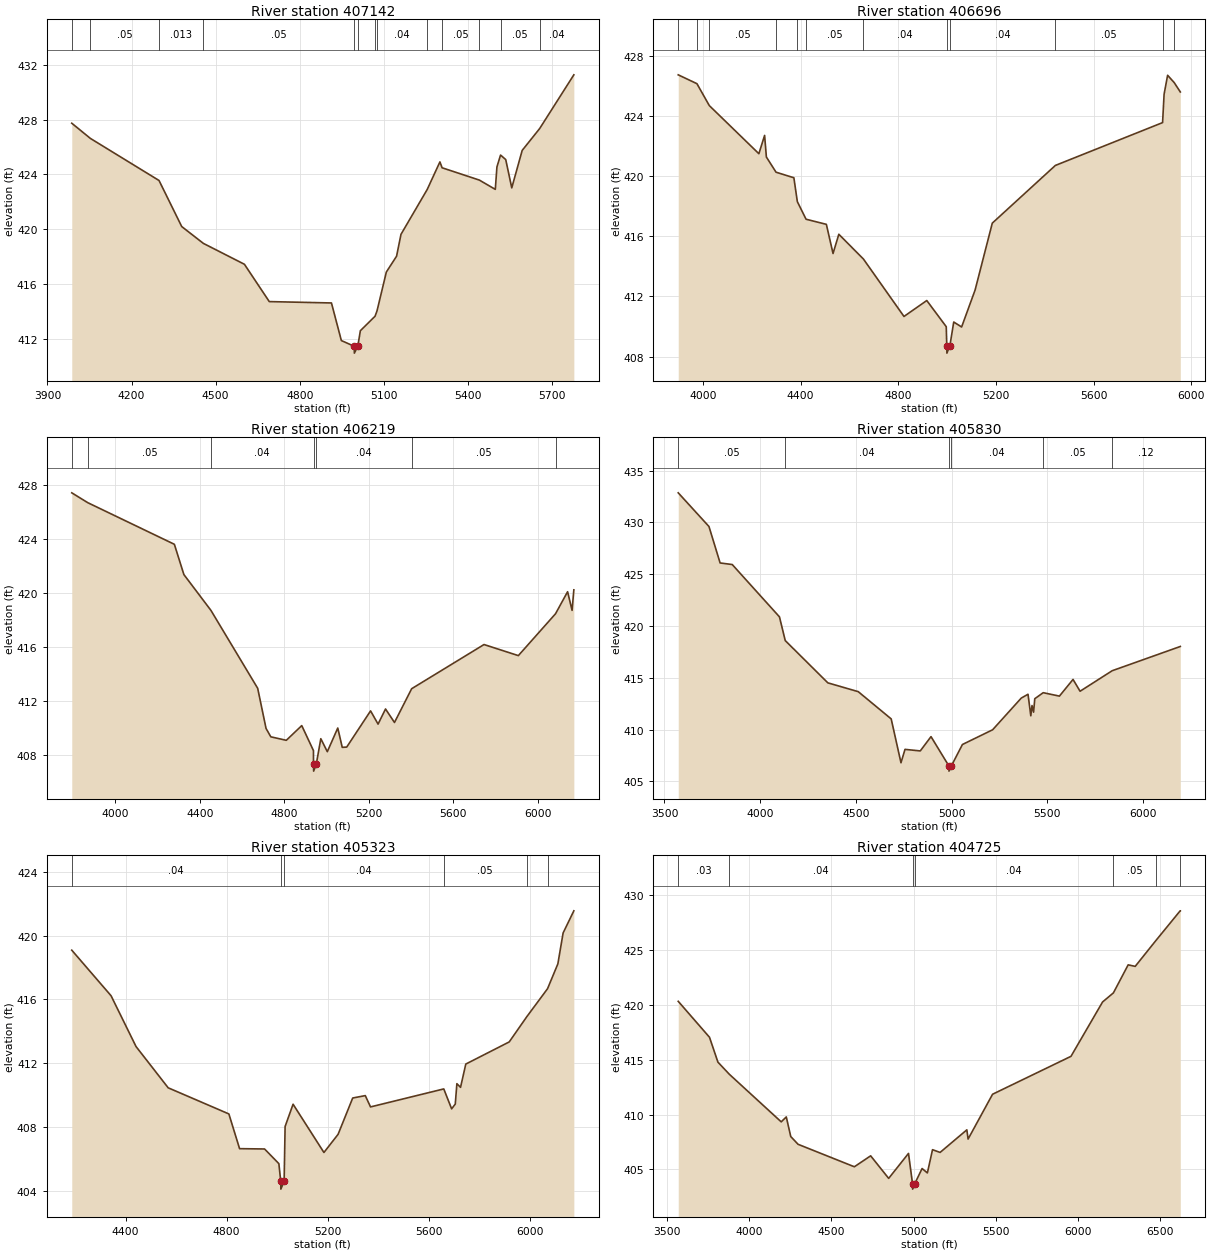
Type RM Length L Ch R = 1 ,407142  ,446,446,446
BEGIN DESCRIPTION:
Mapping XS 0665ccac
END DESCRIPTION:
XS GIS Cut Line= 3
      2407358.55     13581930.73      2407181.59     13580973.83
      2406769.34     13580267.11
#Sta/Elev= 30
  3986.6  427.75  4052.9  426.64  4297.9  423.56  4378.9  420.19    4456  418.96
  4602.6  417.43  4691.3   414.7  4913.1   414.6  4948.4  411.85  4994.4  411.43
  4994.9  410.93    5007  411.43  5016.3  412.57  5068.7  413.63  5075.8  414.03
  5108.9  416.86  5145.4  418.02  5161.2  419.62  5254.7   422.9  5300.1  424.92
  5307.9  424.49  5440.7  423.59  5497.7  422.91  5503.5  424.55  5516.4  425.42
  5534.9  425.09  5556.4  423.02  5593.6  425.76    5656  427.36  5777.9  431.29
#Mann= 13 ,-1 , 0
  3986.6    .013       0  4052.9     .05       0  4297.9    .013       0
    4456     .05       0  4994.4     .05       0    5007     .05       0
  5068.7    .013       0  5075.8     .04       0  5254.7    .013       0
  5307.9     .05       0  5440.7    .013       0  5516.4     .05       0
    5656     .04       0
Bank Sta=4994.4,5007
XS Rating Curve= 0 ,0
Exp/Cntr=0.3,0.1

Type RM Length L Ch R = 1 ,406696  ,477,477,477
BEGIN DESCRIPTION:
Mapping XS 1344d650
END DESCRIPTION:
XS GIS Cut Line= 3
       2407804.2     13581897.89      2407555.16     13580744.45
      2407004.63     13580062.83
#Sta/Elev= 30
  3899.1  426.75  3975.7  426.16  4026.5   424.7  4229.4   421.5  4252.8  422.72
  4260.1  421.28  4299.6  420.27  4372.7   419.9  4386.9  418.31  4422.6  417.14
  4505.7   416.8  4533.1  414.86  4556.8  416.14  4657.6  414.49  4823.6  410.67
    4917  411.73  4996.7  409.99  4998.9  408.73  4999.4  408.23  5011.7  408.73
  5027.4   410.3  5059.7  409.97  5114.9  412.43  5185.3  416.88  5443.6  420.72
  5882.7  423.57  5888.9  425.46  5903.3  426.72  5930.4  426.23  5955.3  425.61
#Mann= 12 ,-1 , 0
  3899.1    .013       0  3975.7     .03       0  4026.5     .05       0
  4299.6     .12       0  4386.9     .04       0  4422.6     .05       0
  4657.6     .04       0  4998.9     .04       0  5011.7     .04       0
  5443.6     .05       0  5882.7    .013       0  5930.4     .05       0
Bank Sta=4998.9,5011.7
XS Rating Curve= 0 ,0
Exp/Cntr=0.3,0.1

Type RM Length L Ch R = 1 ,406219  ,389,389,389
BEGIN DESCRIPTION:
Mapping XS 2356ef9d
END DESCRIPTION:
XS GIS Cut Line= 3
      2408453.02      13581655.4      2407928.73     13580574.05
      2407096.42     13579741.74
#Sta/Elev= 30
  3792.9  427.39  3868.8  426.66    4279  423.58  4324.1  421.34  4452.2  418.69
  4673.8  412.92  4713.4  409.95    4736  409.33  4809.3  409.07  4882.6  410.16
    4938  408.31  4938.3  407.29  4938.8  406.79  4951.2  407.29  4972.9  409.19
  5003.7  408.23  5053.2  409.98  5074.4  408.55  5095.6  408.57  5208.7  411.25
  5244.1  410.27  5279.5  411.39  5321.9  410.39  5403.3  412.89  5746.1  416.16
  5908.8  415.34    6085  418.44  6142.1  420.07  6163.3  418.69  6171.7  420.21
#Mann= 7 ,-1 , 0
  3792.9     .12       0  3868.8     .05       0  4452.2     .04       0
  4938.3     .04       0  4951.2     .04       0  5403.3     .05       0
    6085    .013       0
Bank Sta=4938.3,4951.2
XS Rating Curve= 0 ,0
Exp/Cntr=0.3,0.1

Type RM Length L Ch R = 1 ,405830  ,507,507,507
BEGIN DESCRIPTION:
Mapping XS 88c448c5
END DESCRIPTION:
XS GIS Cut Line= 3
      2409023.22     13581458.83      2408341.62     13580429.86
       2407240.6     13579584.44
#Sta/Elev= 30
  3571.8  432.86  3732.3  429.61  3790.6  426.09  3853.8  425.94  4100.5  420.89
  4130.7   418.6  4353.2  414.52    4512  413.67  4684.1  411.04  4735.2  406.81
  4756.3   408.1    4836  407.95  4892.1  409.33  4985.4   406.5  4985.9     406
  4998.3   406.5  5056.2  408.57  5213.9  409.99  5363.5  413.05  5398.8  413.42
  5413.3  411.34  5419.6  412.33  5427.8  411.69  5434.1  412.99  5478.1  413.57
  5562.8  413.24  5633.9  414.85  5670.7  413.71  5838.4  415.69  6194.2  418.03
#Mann= 6 ,-1 , 0
  3571.8     .05       0  4130.7     .04       0  4985.4     .04       0
  4998.3     .04       0  5478.1     .05       0  5838.4     .12       0
Bank Sta=4985.4,4998.3
XS Rating Curve= 0 ,0
Exp/Cntr=0.3,0.1

Type RM Length L Ch R = 1 ,405323  ,598,598,598
BEGIN DESCRIPTION:
SALT CREEK 113.0
END DESCRIPTION:
XS GIS Cut Line= 3
      2409075.03     13580575.03        2408475.       13579975.
      2407575.04     13579275.03
#Sta/Elev= 30
  4186.8  419.09  4342.4  416.23  4441.4  413.04  4568.7  410.45  4809.1  408.81
  4851.5  406.63  4950.5  406.61  5007.1  405.69  5014.5  404.59    5015  404.09
    5028  404.59  5031.8  408.02  5063.4  409.42  5185.6  406.39  5241.7  407.53
  5299.6  409.81  5349.4  409.96  5370.2  409.25  5660.3  410.38  5691.4  409.13
  5705.9  409.43  5712.2  410.71  5726.7  410.48  5747.5  411.94  5919.5  413.33
    5989  414.91  6071.3  416.67  6112.2  418.23    6133  420.17  6175.5  421.56
#Mann= 6 ,-1 , 0
  4186.8     .04       0  5014.5     .04       0    5028     .04       0
  5660.3     .05       0    5989     .12       0  6071.3     .05       0
Bank Sta=5014.5,5028
XS Rating Curve= 0 ,0
Exp/Cntr=0.3,0.1

Type RM Length L Ch R = 1 ,404725  ,222,222,222
BEGIN DESCRIPTION:
Mapping XS ce1f9388
END DESCRIPTION:
XS GIS Cut Line= 4
      2409685.14     13580377.42       2409252.6     13579669.62
      2407922.17     13579269.84      2407286.44     13578725.86
#Sta/Elev= 30
  3567.4  420.34  3757.7  417.06  3808.9  414.79  3878.6  413.68  4194.1  409.34
    4225  409.79  4252.1     408  4296.8  407.29  4639.3  405.24  4738.4  406.24
    4848  404.18  4968.7  406.46  4993.2   403.7  4993.7   403.2  5006.9   403.7
  5051.4  405.08  5083.6  404.68  5114.9   406.8    5161  406.55  5323.7  408.61
  5331.4  407.77  5480.3  411.86  5957.5  415.32  6149.7  420.28  6215.6  421.11
  6305.5  423.67  6348.3  423.53  6472.2  425.85  6621.9   428.6  6622.8   428.6
#Mann= 7 ,-1 , 0
  3567.4     .03       0  3878.6     .04       0  4993.2     .04       0
  5006.9     .04       0  6215.6     .05       0  6472.2     .04       0
  6621.9    .013       0
Bank Sta=4993.2,5006.9
XS Rating Curve= 0 ,0
Exp/Cntr=0.3,0.1