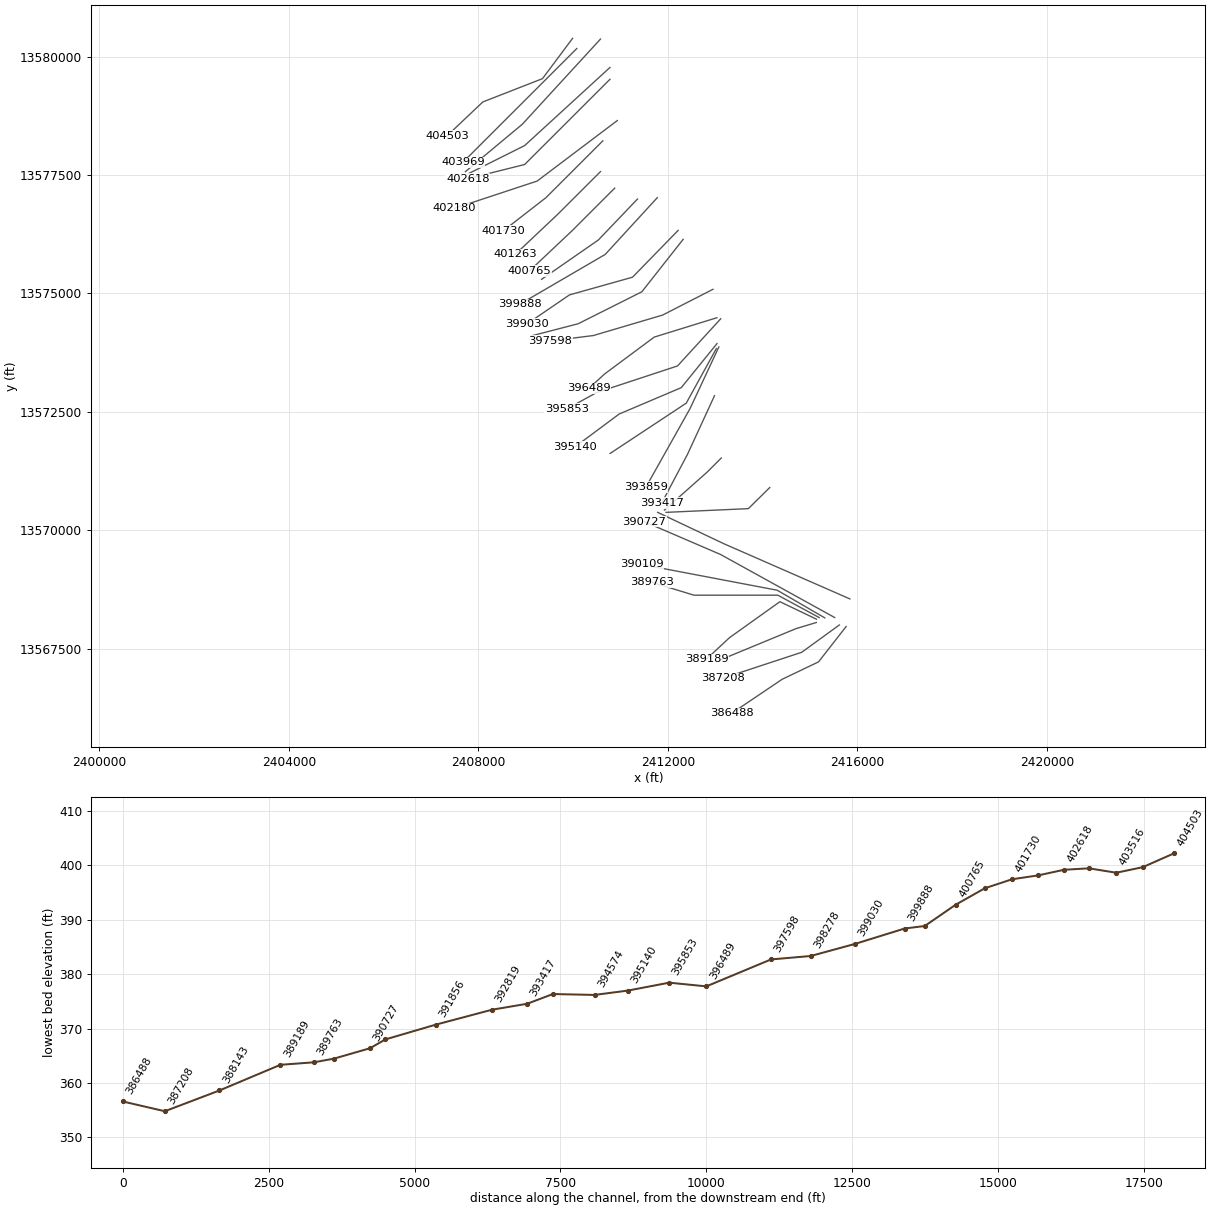
HEC-RAS study COLETO CREEK.prj: COLETO CREEK Base Level Engineering

--- COLETO CREEK.g01 (geometry) --- (continued)

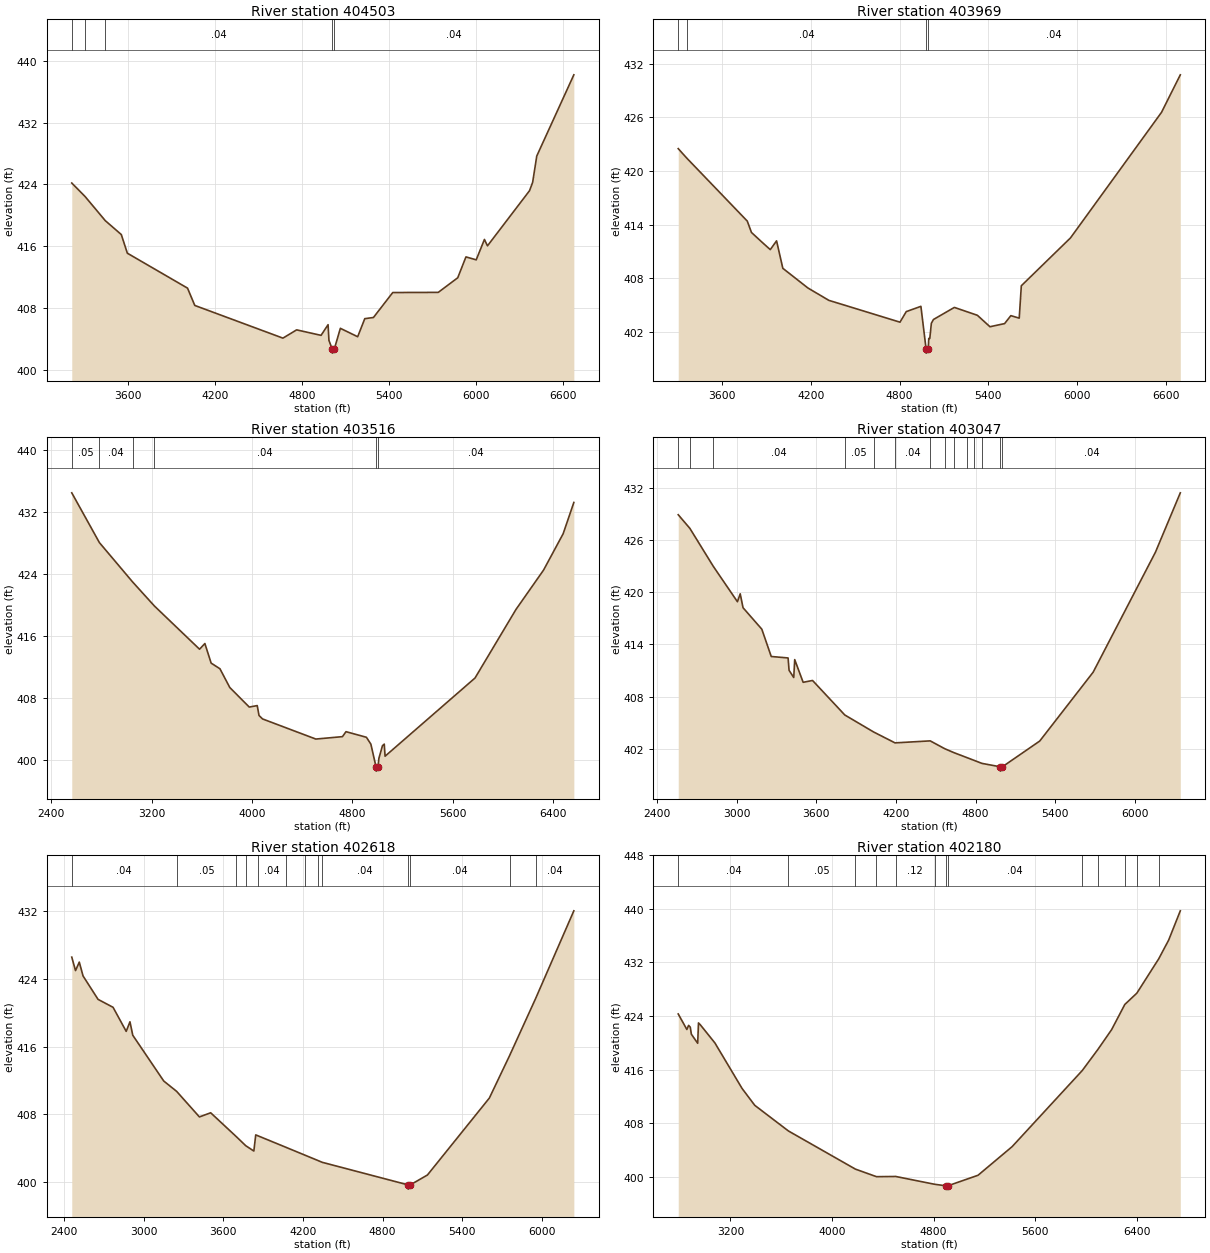
Type RM Length L Ch R = 1 ,404503  ,534,534,534
BEGIN DESCRIPTION:
Mapping XS 96b071f0
END DESCRIPTION:
XS GIS Cut Line= 4
      2409986.65     13580390.57      2409350.91     13579538.54
      2408092.57     13579047.01      2407332.34     13578326.09
#Sta/Elev= 30
  3211.7  424.18  3303.2  422.44  3442.8  419.31  3553.3  417.51  3594.9   415.1
  4009.8  410.58  4059.9  408.34  4667.6  404.11  4762.2  405.18  4930.5  404.47
  4978.9  405.85  4984.8  403.82  5007.8  402.67  5008.3  402.17  5021.5  402.67
  5063.6  405.38    5183  404.29    5232  406.63  5291.7  406.78  5424.8  410.01
  5738.6  410.03  5872.9  411.92  5929.5  414.62  6000.3  414.24  6056.9  416.88
  6077.9  416.05    6368  423.19  6389.4  424.27  6417.7  427.67  6673.4  438.18
#Mann= 5 ,-1 , 0
  3211.7     .04       0  3303.2     .03       0  3442.8     .04       0
  5007.8     .04       0  5021.5     .04       0
Bank Sta=5007.8,5021.5
XS Rating Curve= 0 ,0
Exp/Cntr=0.3,0.1

Type RM Length L Ch R = 1 ,403969  ,453,453,453
BEGIN DESCRIPTION:
SALT CREEK 110.0
END DESCRIPTION:
XS GIS Cut Line= 3
      2410075.01     13580175.01        2408875.       13578975.
      2407675.02     13577775.02
#Sta/Elev= 30
  3303.3   422.5  3359.8  421.46    3770   414.4  3798.3  413.13    3869  412.05
  3925.6  411.21    3968  412.19  4010.4  409.12  4180.1  406.92  4321.5  405.54
  4802.4   403.1  4844.8  404.28  4943.8  404.87  4978.6  400.14  4979.1  399.64
  4993.8  400.14  4996.8  401.28  5003.9  401.28  5014.5  402.98  5028.7   403.4
  5170.1  404.75  5325.6  403.87  5410.5  402.59  5509.5  402.94  5551.9  403.83
  5608.5  403.55  5622.6  407.17    5955  412.52  6570.1  426.55  6697.4  430.75
#Mann= 4 ,-1 , 0
  3303.3     .03       0  3359.8     .04       0  4978.6     .04       0
  4993.8     .04       0
Bank Sta=4978.6,4993.8
XS Rating Curve= 0 ,0
Exp/Cntr=0.3,0.1

Type RM Length L Ch R = 1 ,403516  ,469,469,469
BEGIN DESCRIPTION:
SALT CREEK 109.0
END DESCRIPTION:
XS GIS Cut Line= 3
      2410575.01     13580375.01        2408925.       13578575.
      2407724.99     13577574.99
#Sta/Elev= 30
  2562.8  434.46  2783.2  428.05  3047.6  422.99  3221.6  419.89  3581.8  414.32
  3624.3  415.05  3674.3  412.53  3744.6   411.8  3822.9  409.39  3978.3  406.87
  4041.8  407.06    4056  405.79  4084.3  405.34  4509.2  402.75  4721.3  403.06
  4749.7   403.7  4912.5  402.98  4948.2  402.09  4989.9  399.12  4990.4  398.62
  5005.1  399.12  5011.8  400.25  5040.4  401.89  5054.8   402.1  5061.3  400.54
  5778.5  410.61  6105.2  419.44  6325.2  424.51  6481.4  429.19  6566.7  433.22
#Mann= 6 ,-1 , 0
  2562.8     .05       0  2783.2     .04       0  3047.6     .03       0
  3221.6     .04       0  4989.9     .04       0  5005.1     .04       0
Bank Sta=4989.9,5005.1
XS Rating Curve= 0 ,0
Exp/Cntr=0.3,0.1

Type RM Length L Ch R = 1 ,403047  ,429,429,429
BEGIN DESCRIPTION:
SALT CREEK 108.0
END DESCRIPTION:
XS GIS Cut Line= 3
        2410775.       13579775.        2408975.       13578125.
      2407774.97     13577524.99
#Sta/Elev= 30
  2558.7  428.93  2646.4  427.36    2823  422.99  3004.8  418.92  3025.8  419.83
  3047.1  418.23  3188.6  415.76  3259.5  412.62  3386.5  412.45  3393.9  411.03
  3429.1   410.2  3436.5  412.26    3500  409.65  3570.9  409.86  3813.8  405.89
  4031.6  403.93  4192.3  402.68  4457.6  402.91    4567  402.01    4634  401.57
  4738.4  400.96  4784.6  400.69  4847.3  400.32  4985.4  399.93  4985.9  399.43
  5001.4  399.93  5282.8  402.89  5685.3  410.81  6154.9  424.62  6342.2  431.45
#Mann= 14 ,-1 , 0
  2558.7     .04       0  2646.4     .05       0    2823     .04       0
  3813.8     .05       0  4031.6     .03       0  4192.3     .04       0
  4457.6     .05       0    4567     .04       0    4634     .05       0
  4738.4     .04       0  4784.6     .05       0  4847.3     .04       0
  4985.4     .04       0  5001.4     .04       0
Bank Sta=4985.4,5001.4
XS Rating Curve= 0 ,0
Exp/Cntr=0.3,0.1

Type RM Length L Ch R = 1 ,402618  ,438,438,438
BEGIN DESCRIPTION:
SALT CREEK 107.0
END DESCRIPTION:
XS GIS Cut Line= 3
      2410775.01     13579525.01        2408975.       13577725.
      2407775.02     13577425.01
#Sta/Elev= 30
    2459  426.57  2487.3  424.98  2515.6  425.98  2543.9  424.35    2657  421.58
  2770.1  420.64  2869.1   417.8  2897.4  418.93  2918.6  417.34    3152  411.93
  3249.1  410.71  3420.7  407.69  3505.5  408.18  3697.3  405.38  3769.7  404.29
  3830.8  403.66  3844.9  405.57  3861.8  405.46  4072.7   404.1  4216.3  403.17
  4310.5  402.56  4345.3  402.33    4993  399.66  4993.5  399.16  5009.1  399.66
  5138.6  400.83    5605  409.92    5757  414.92    5953  421.66  6241.5  432.04
#Mann= 13 ,-1 , 0
    2459     .04       0  3249.1     .05       0  3697.3     .04       0
  3769.7     .03       0  3861.8     .04       0  4072.7     .05       0
  4216.3     .04       0  4310.5     .05       0  4345.3     .04       0
    4993     .04       0  5009.1     .04       0    5757     .03       0
    5953     .04       0
Bank Sta=4993,5009.1
XS Rating Curve= 0 ,0
Exp/Cntr=0.3,0.1

Type RM Length L Ch R = 1 ,402180  ,450,450,450
BEGIN DESCRIPTION:
Mapping XS 5bd64cda
END DESCRIPTION:
XS GIS Cut Line= 3
      2410930.37     13578653.77      2409239.49     13577375.78
      2407497.65     13576799.53
#Sta/Elev= 30
  2789.1  424.31    2857  421.99    2871  422.61  2884.1  422.33  2892.4  421.29
  2942.3  419.93  2948.6  422.97  2963.1  422.69  3077.6  419.99  3291.9  413.18
  3391.8  410.66  3656.9  406.83  4184.4  401.13  4350.5     400    4502  400.03
  4809.8  398.86  4896.7  398.64  4897.2  398.14  4912.3  398.14  4912.8  398.64
  5150.1  400.21  5418.9  404.49  5971.2  415.86  6094.2  419.01  6202.1  421.96
  6306.2  425.73    6401  427.42    6573  432.54  6651.4  435.34  6743.3  439.72
#Mann= 13 ,-1 , 0
  2789.1     .04       0  3656.9     .05       0  4184.4     .12       0
  4350.5     .05       0    4502     .12       0  4809.8     .04       0
  4896.7     .04       0  4912.8     .04       0  5971.2     .03       0
  6094.2     .04       0  6306.2    .013       0    6401     .05       0
    6573     .04       0
Bank Sta=4896.7,4912.8
XS Rating Curve= 0 ,0
Exp/Cntr=0.3,0.1

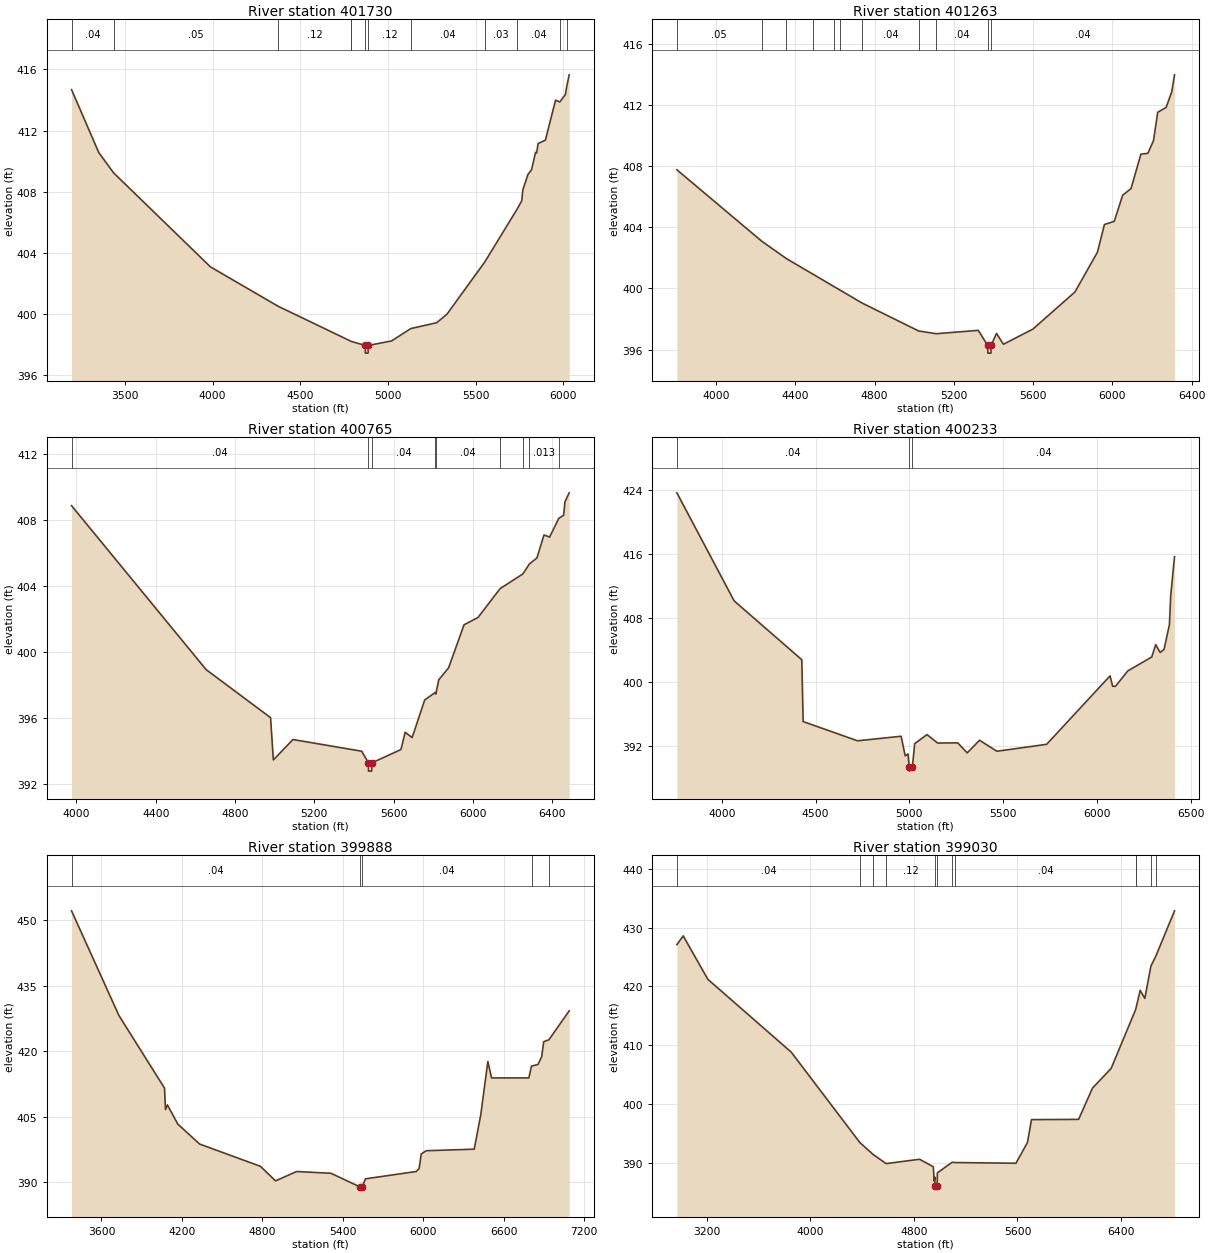
Type RM Length L Ch R = 1 ,401730  ,467,467,467
BEGIN DESCRIPTION:
SALT CREEK 105.0
END DESCRIPTION:
XS GIS Cut Line= 3
        2410625.       13578225.        2409425.       13577025.
      2408525.03     13576325.02
#Sta/Elev= 30
  3195.9  414.68  3351.5  410.55  3435.6  409.23  3987.9  403.07  4373.8  400.49
  4788.5   398.2  4789.7  398.19  4870.7  397.92  4871.2  397.42  4886.4  397.42
  4886.9  397.92  5020.6  398.22  5130.4  399.03  5277.5  399.41  5335.5  399.96
  5551.8  403.39  5737.1  406.87  5762.6   407.4  5768.9  408.12  5797.9  409.12
  5818.7  409.44  5841.3  410.57  5847.6  410.53  5855.8  411.15  5897.4  411.37
  5955.3  413.99  5979.3  413.87  6011.4  414.36  6018.8  414.87  6033.1  415.65
#Mann= 12 ,-1 , 0
  3195.9     .04       0  3435.6     .05       0  4373.8     .12       0
  4788.5     .05       0  4789.7     .12       0  4870.7     .05       0
  4886.9     .12       0  5130.4     .04       0  5551.8     .03       0
  5737.1     .04       0  5979.3     .03       0  6018.8     .04       0
Bank Sta=4870.7,4886.9
XS Rating Curve= 0 ,0
Exp/Cntr=0.3,0.1

Type RM Length L Ch R = 1 ,401263  ,498,498,498
BEGIN DESCRIPTION:
SALT CREEK 104.0
END DESCRIPTION:
XS GIS Cut Line= 3
      2410575.02     13577575.02        2409675.       13576675.
      2408774.98     13575824.98
#Sta/Elev= 30
  3802.9  407.76    4230   403.1  4355.8  401.95  4491.1  400.92  4594.5  400.13
  4626.3  399.89    4738  399.04  5022.6  397.22  5110.9  397.04  5323.3  397.26
  5371.4  396.27  5371.9  395.77  5387.6  395.77  5388.1  396.27  5415.4  397.06
  5450.5  396.35    5599  397.34  5811.4  399.77  5924.7  402.37  5959.9  404.18
  6009.6  404.39  6052.1   406.1  6094.2  406.53    6144  408.78  6179.2  408.84
  6207.5  409.66  6228.9  411.52  6271.4  411.84  6299.7  412.87  6313.7  413.97
#Mann= 11 ,-1 , 0
  3802.9     .05       0    4230     .03       0  4355.8     .12       0
  4491.1     .05       0  4594.5     .04       0  4626.3     .05       0
    4738     .04       0  5022.6    .013       0  5110.9     .04       0
  5371.4     .04       0  5388.1     .04       0
Bank Sta=5371.4,5388.1
XS Rating Curve= 0 ,0
Exp/Cntr=0.3,0.1

Type RM Length L Ch R = 1 ,400765  ,532,532,532
BEGIN DESCRIPTION:
SALT CREEK 103.0
END DESCRIPTION:
XS GIS Cut Line= 3
      2410874.99     13577224.99        2409975.       13576325.
      2409075.02     13575475.01
#Sta/Elev= 30
  3975.1  408.89  4653.9  398.93  4979.2  396.01  4993.3  393.44  5092.3  394.68
    5439  393.97  5473.1  393.26  5473.6  392.76  5489.4  392.76  5489.9  393.26
  5636.9  394.07  5658.3  395.12  5693.5   394.8    5757  397.09  5810.3  397.54
  5812.7  397.44  5827.8  398.31  5877.6  399.04  5955.2  401.65    6026   402.1
  6137.3  403.85  6251.9  404.74  6285.4  405.35    6323  405.71  6358.6  407.11
  6386.9  406.98  6433.4  408.12  6457.7  408.31  6464.6  409.13  6485.8  409.67
#Mann= 9 ,-1 , 0
  3975.1     .04       0  5473.1     .04       0  5489.9     .04       0
  5810.3    .013       0  5812.7     .04       0  6137.3    .013       0
  6251.9     .04       0  6285.4    .013       0  6433.4     .04       0
Bank Sta=5473.1,5489.9
XS Rating Curve= 0 ,0
Exp/Cntr=0.3,0.1

Type RM Length L Ch R = 1 ,400233  ,345,345,345
BEGIN DESCRIPTION:
Mapping XS b37bde1a
END DESCRIPTION:
XS GIS Cut Line= 3
      2411356.41     13576995.69       2410530.6     13576130.55
      2409332.54     13575299.12
#Sta/Elev= 30
  3760.1   423.7  4065.6  410.16  4426.3  402.79  4433.6  395.04  4723.6  392.63
  4956.1   393.2  4977.9  390.74  4992.8  390.98  4999.2  389.33  4999.7  388.83
    5016  389.33  5028.5  392.27  5094.1  393.41  5150.8  392.35  5258.2  392.37
  5308.8  391.12  5374.4   392.7  5466.9  391.32  5732.3  392.19  6070.6  400.77
  6084.2  399.47  6099.1  399.45  6164.6  401.38  6292.9  403.13    6314  404.68
  6337.5   403.7  6358.4  404.08  6387.1  407.18  6394.2  410.86  6414.4   415.7
#Mann= 3 ,-1 , 0
  3760.1     .04       0  4999.2     .04       0    5016     .04       0
Bank Sta=4999.2,5016
XS Rating Curve= 0 ,0
Exp/Cntr=0.3,0.1

Type RM Length L Ch R = 1 ,399888  ,858,858,858
BEGIN DESCRIPTION:
SALT CREEK 101.0
END DESCRIPTION:
XS GIS Cut Line= 3
      2411775.03     13577025.03        2410675.       13575825.
      2408874.99     13574774.99
#Sta/Elev= 30
    3377  452.16  3730.7  428.15  4070.4  411.53  4077.8  406.61    4092  407.68
  4169.7  403.27  4332.5   398.7  4785.7   393.6  4898.6  390.26  5055.8  392.41
  5312.1     392    5529  388.87  5529.5  388.37  5545.9  388.87  5568.5  390.73
    5948  392.41  5969.5  393.09  5985.2  396.43  6022.5  397.17  6380.5  397.53
  6429.3  405.42  6482.2  417.63  6509.9  413.86  6787.8  413.86  6807.7  416.56
    6856  416.94  6883.3   418.7    6899  422.16  6937.6  422.61  7088.8  429.23
#Mann= 5 ,-1 , 0
    3377     .04       0    5529     .04       0  5545.9     .04       0
  6807.7    .013       0  6937.6     .05       0
Bank Sta=5529,5545.9
XS Rating Curve= 0 ,0
Exp/Cntr=0.3,0.1

Type RM Length L Ch R = 1 ,399030  ,752,752,752
BEGIN DESCRIPTION:
Mapping XS d8398fce
END DESCRIPTION:
XS GIS Cut Line= 4
      2412214.91      13576333.7      2411251.52     13575344.09
      2409921.09     13574970.53      2409029.91     13574361.12
#Sta/Elev= 30
  2970.2  427.09  3018.7  428.59  3209.6  421.19  3853.2  408.81  4383.1  393.44
  4484.5  391.43  4585.8  389.86  4844.2   390.6  4950.1  389.32  4956.8   386.9
    4962  387.56  4962.2  386.02  4962.7  385.52  4979.6  386.02  4981.3  388.28
  5095.6  390.09    5119  390.04    5588  389.92  5677.2  393.45  5708.3  397.34
  6072.2  397.38  6179.9  402.72  6323.4  406.04  6513.2  416.09  6513.5  416.12
  6547.6  419.32  6583.5  417.95  6630.4  423.45    6667  425.06  6812.8  432.84
#Mann= 12 ,-1 , 0
  2970.2     .04       0  4383.1     .12       0  4484.5     .05       0
  4585.8     .12       0  4962.2     .05       0  4979.6     .12       0
  5095.6     .05       0    5119     .04       0  6513.2    .013       0
  6513.5     .04       0  6630.4     .05       0    6667     .03       0
Bank Sta=4962.2,4979.6
XS Rating Curve= 0 ,0
Exp/Cntr=0.3,0.1

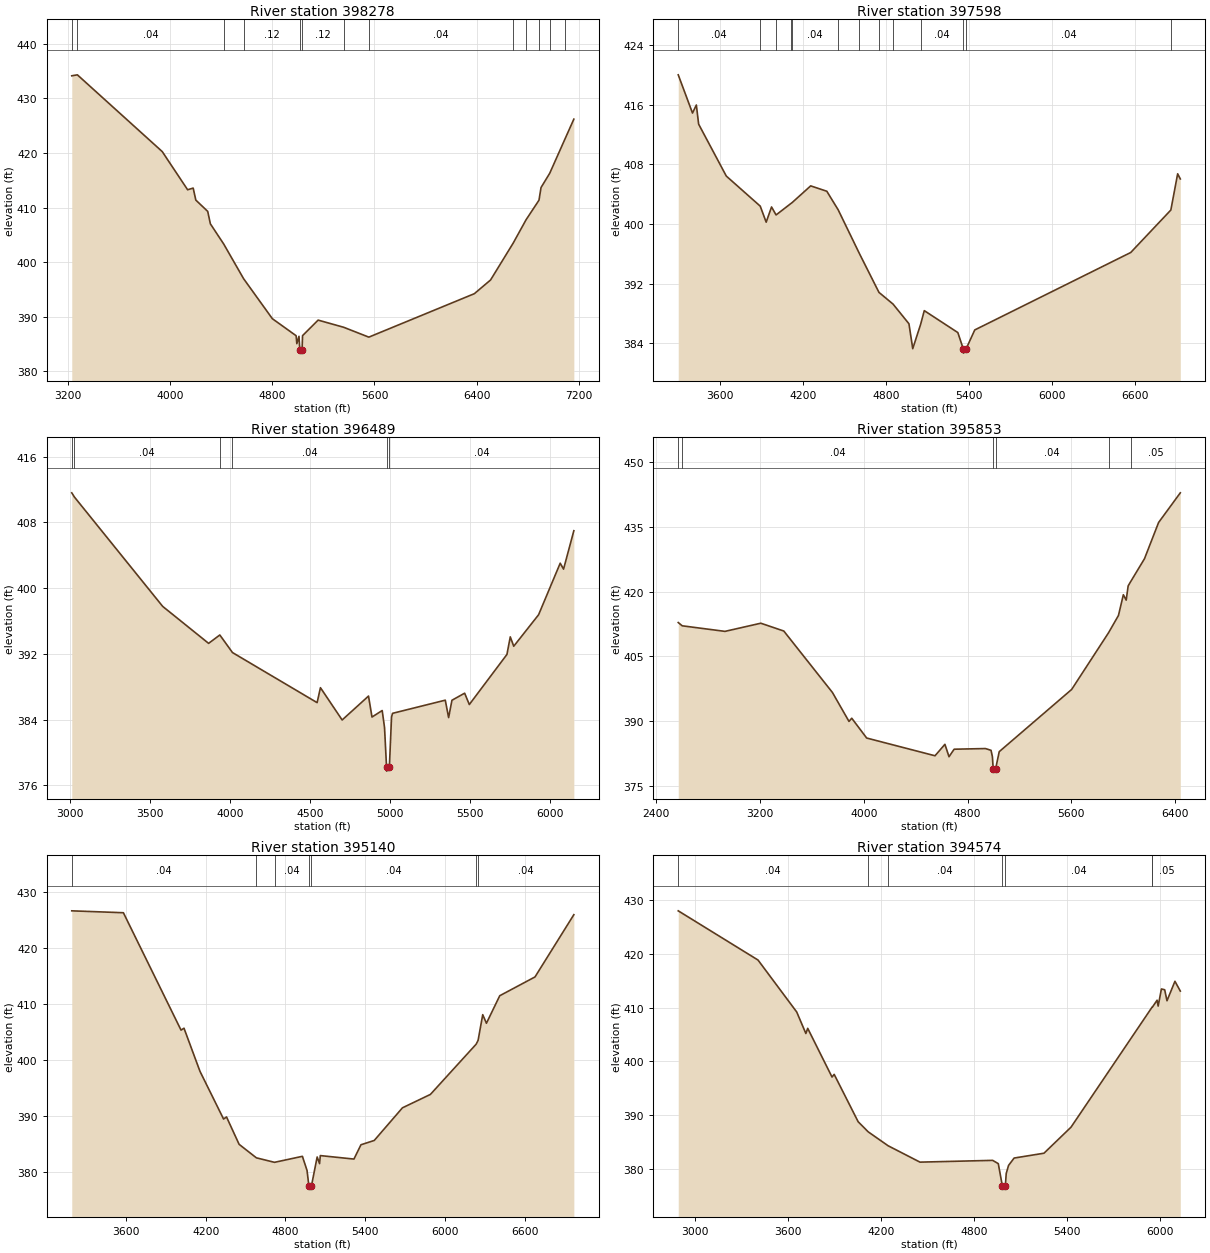
Type RM Length L Ch R = 1 ,398278  ,680,680,680
BEGIN DESCRIPTION:
Mapping XS b32c6cf7
END DESCRIPTION:
XS GIS Cut Line= 4
      2412319.77     13576143.64      2411448.13     13575036.06
       2410104.6     13574361.02      2409121.49     13574105.41
#Sta/Elev= 30
  3231.2  434.13    3275  434.31    3939  420.25  4137.8  413.25  4181.2  413.56
    4202  411.36    4295  409.29  4315.8  407.01  4419.9  403.32    4576  396.95
  4800.8  389.63  4986.8  386.51  4992.4  385.06  5009.2   386.4  5015.9  383.82
  5016.4  383.32  5033.3  383.82  5037.1  386.52  5158.9  389.37  5358.5  388.06
  5555.7  386.25  6381.4  394.21  6508.3  396.72  6685.4  403.48  6786.3  407.76
  6887.2  411.34  6903.3  413.66  6971.2  416.27  7088.9  422.46    7160  426.19
#Mann= 13 ,-1 , 0
  3231.2     .03       0    3275     .04       0  4419.9     .05       0
    4576     .12       0  5015.9     .05       0  5033.3     .12       0
  5358.5     .05       0  5555.7     .04       0  6685.4     .05       0
  6786.3    .013       0  6887.2     .05       0  6971.2     .03       0
  7088.9     .12       0
Bank Sta=5015.9,5033.3
XS Rating Curve= 0 ,0
Exp/Cntr=0.3,0.1

Type RM Length L Ch R = 1 ,397598  ,1109,1109,1109
BEGIN DESCRIPTION:
Mapping XS 76e13b6d
END DESCRIPTION:
XS GIS Cut Line= 4
      2412948.98     13575088.51      2411887.24     13574544.53
      2410425.74     13574111.97      2409519.25      13573997.8
#Sta/Elev= 30
  3299.4  420.03  3402.6   414.9  3430.4  415.98    3447  413.41  3646.8  406.45
  3892.4  402.41  3935.4  400.26  3974.2   402.3    4007  401.23  4115.9  402.79
  4121.4  402.86  4257.2  405.13  4373.8  404.41    4456  401.92  4609.8  396.04
    4751  390.84  4852.8  389.27  4967.8  386.63  4995.3  383.29  5052.1  386.54
  5078.7  388.39  5321.3  385.45    5362  383.19  5362.5  382.69  5379.5  383.19
  5443.7   385.8  6571.6  396.19  6861.8  401.89    6911  406.75  6930.2  406.06
#Mann= 13 ,-1 , 0
  3299.4     .04       0  3892.4    .013       0    4007     .04       0
  4115.9     .05       0  4121.4     .04       0    4456     .03       0
  4609.8     .04       0    4751     .05       0  4852.8     .12       0
  5052.1     .04       0    5362     .05       0  5379.5     .04       0
  6861.8    .013       0
Bank Sta=5362,5379.5
XS Rating Curve= 0 ,0
Exp/Cntr=0.3,0.1

Type RM Length L Ch R = 1 ,396489  ,636,636,636
BEGIN DESCRIPTION:
Mapping XS 427930e0
END DESCRIPTION:
XS GIS Cut Line= 4
      2413031.99     13574488.08      2411710.29      13574079.2
      2410661.67      13573299.3      2410332.43     13572996.73
#Sta/Elev= 30
  3012.2  411.59  3029.1  411.07  3580.2  397.78  3867.4  393.28  3937.4   394.3
  4016.6  392.16  4545.4  386.07  4566.2  387.89  4701.8  383.96  4866.6  386.87
  4888.3  384.32  4952.1  385.11  4966.7  383.04  4979.2  378.24  4979.7  377.74
  4996.9  378.24  5010.5  384.32  5016.8  384.77  5346.3  386.37  5367.2  384.25
    5388  386.36  5467.3  387.22  5496.5  385.84  5731.5  391.93  5752.5  394.07
  5774.1  392.93  5929.4  396.76  6064.5  403.03  6085.4  402.31  6149.7  406.98
#Mann= 6 ,-1 , 0
  3012.2    .013       0  3029.1     .04       0  3937.4     .03       0
  4016.6     .04       0  4979.2     .04       0  4996.9     .04       0
Bank Sta=4979.2,4996.9
XS Rating Curve= 0 ,0
Exp/Cntr=0.3,0.1

Type RM Length L Ch R = 1 ,395853  ,713,713,713
BEGIN DESCRIPTION:
Mapping XS 52ff6c32
END DESCRIPTION:
XS GIS Cut Line= 4
      2413112.77     13574465.85      2412201.82      13573469.7
      2410491.27     13572906.07       2409863.3     13572559.38
#Sta/Elev= 30
  2571.1  412.86  2601.7   412.1  2931.1  410.81  3207.4   412.7  3384.4  410.89
  3759.3  396.64  3886.7  389.94  3907.9  390.68  4022.9  386.09  4549.4  381.98
  4625.7  384.63  4657.4  381.76  4696.8   383.5  4938.1  383.65    4981  383.24
  4991.6  381.77  4997.7  378.92  4998.2  378.42  5016.1  378.92  5044.2  382.93
  5602.2  397.35  5886.4  410.49  5962.7  414.49  6000.5   419.3  6022.3  418.05
  6037.6  421.36  6056.3  422.31  6163.2  427.64  6272.1  436.05  6439.3  442.92
#Mann= 6 ,-1 , 0
  2571.1    .013       0  2601.7     .04       0  4997.7     .04       0
  5016.1     .04       0  5886.4    .013       0  6056.3     .05       0
Bank Sta=4997.7,5016.1
XS Rating Curve= 0 ,0
Exp/Cntr=0.3,0.1

Type RM Length L Ch R = 1 ,395140  ,566,566,566
BEGIN DESCRIPTION:
Mapping XS 06708f3a
END DESCRIPTION:
XS GIS Cut Line= 4
      2413034.14     13573941.55      2412280.47     13573010.93
       2410969.7     13572453.86      2410045.64     13571765.72
#Sta/Elev= 30
  3193.6  426.59  3581.6  426.25  4014.8  405.32  4037.2  405.66  4157.1  397.98
  4334.6  389.46  4356.9  389.83  4451.4  384.95  4581.3  382.54  4717.6  381.74
  4927.2  382.81  4962.1  380.28  4976.2  377.46  4976.7  376.96  4994.6  377.46
  5038.1  382.69  5056.3  381.51  5061.8  382.94  5314.6  382.32  5367.3  384.87
  5467.3  385.64  5679.2  391.46  5889.3  393.85  6233.3  402.81  6247.8  403.49
  6282.6  408.07  6310.5  406.54  6410.6  411.45  6675.5   414.8  6967.5   425.9
#Mann= 7 ,-1 , 0
  3193.6     .04       0  4581.3     .05       0  4717.6     .04       0
  4976.2     .04       0  4994.6     .04       0  6233.3    .013       0
  6247.8     .04       0
Bank Sta=4976.2,4994.6
XS Rating Curve= 0 ,0
Exp/Cntr=0.3,0.1

Type RM Length L Ch R = 1 ,394574  ,715,715,715
BEGIN DESCRIPTION:
Mapping XS 899f859f
END DESCRIPTION:
XS GIS Cut Line= 3
      2413021.06     13573836.73      2412385.33     13572683.24
      2410779.84     13571621.65
#Sta/Elev= 30
    2891  428.03  3406.1  418.86    3656  409.18  3715.1  405.17  3727.1  406.13
  3884.1  397.05  3897.8  397.56  4052.7  388.73  4117.4  386.85  4246.3  384.25
  4451.9   381.2  4921.4  381.53  4957.5  380.92  4984.4  376.67  4984.9  376.17
  5002.9  376.67  5008.7  379.07  5023.7  380.58  5059.7  381.96  5252.4  382.86
    5427  387.71  5951.3  410.11  5952.9   410.1  5982.8  411.37  5989.8  410.28
  6010.8  413.47  6031.9  413.32  6046.9  411.27  6098.1   414.9  6132.8  413.08
#Mann= 7 ,-1 , 0
    2891     .04       0  4117.4     .05       0  4246.3     .04       0
  4984.4     .04       0  5002.9     .04       0  5951.3    .013       0
  5952.9     .05       0
Bank Sta=4984.4,5002.9
XS Rating Curve= 0 ,0
Exp/Cntr=0.3,0.1

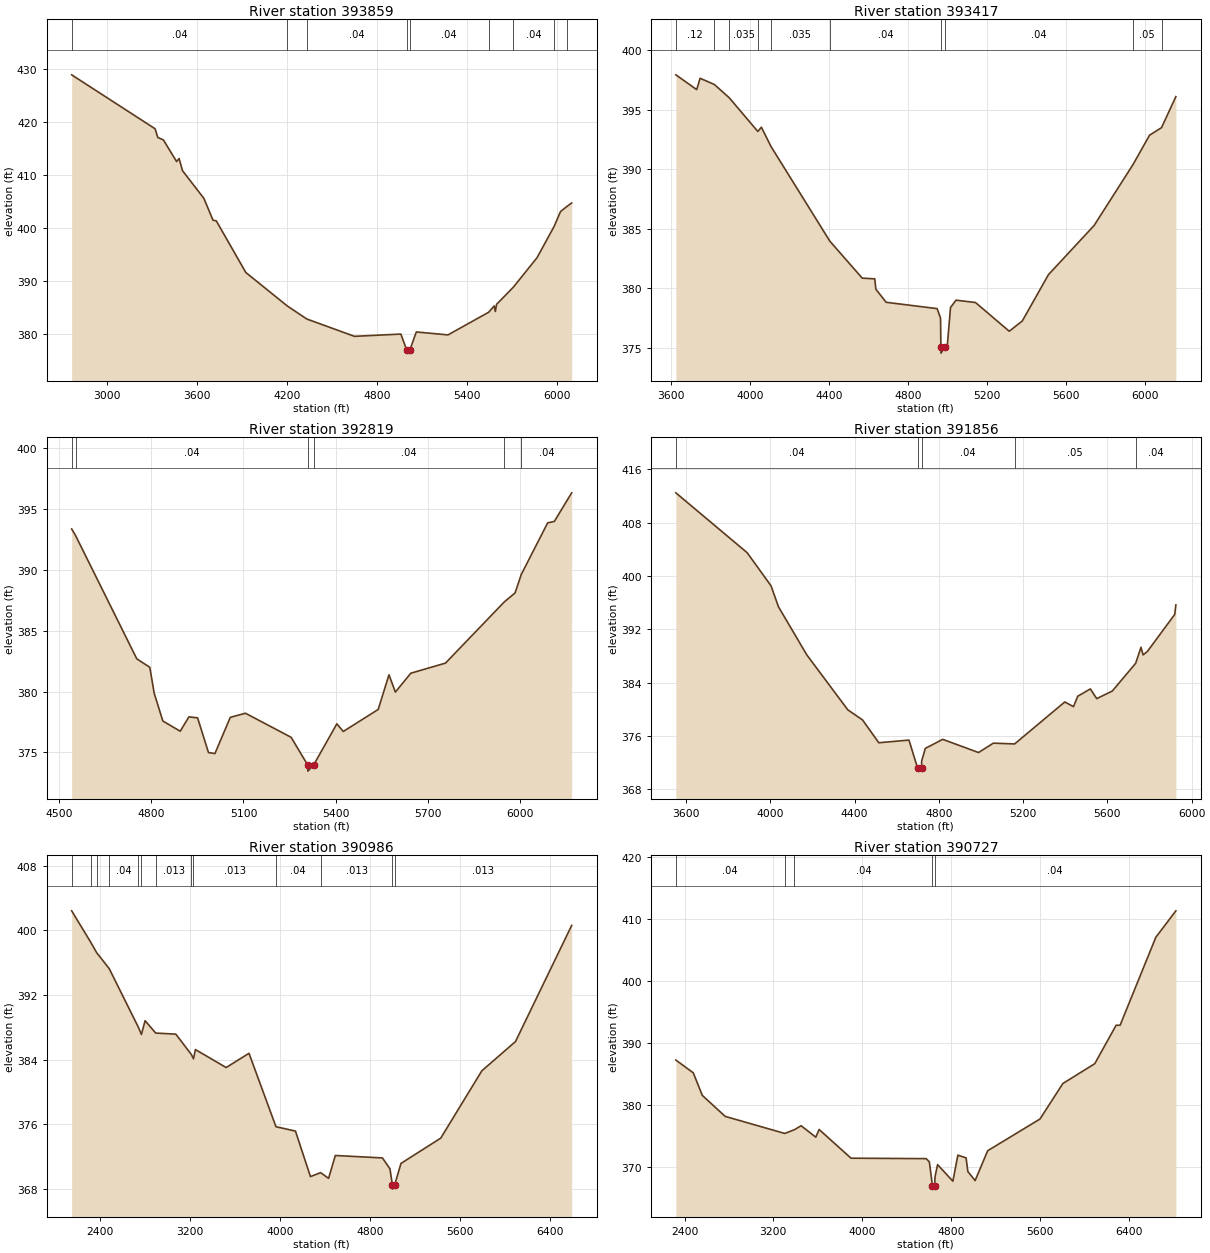
Type RM Length L Ch R = 1 ,393859  ,442,442,442
BEGIN DESCRIPTION:
Mapping XS 1299fea1
END DESCRIPTION:
XS GIS Cut Line= 3
      2413073.49     13573869.51      2412465.81     13572569.08
       2411535.6     13570910.88
#Sta/Elev= 30
  2764.3  428.88  3321.3  418.69  3338.6  417.06  3376.4  416.59  3464.7   412.5
  3481.2  413.08  3504.1  410.78  3646.7  405.55  3707.5  401.44  3729.6   401.3
  3926.4  391.56    4203  385.24  4333.6  382.77  4651.6   379.5  4961.1  379.93
  5001.5  376.83    5002  376.33    5020  376.83  5064.3  380.33  5275.4  379.77
    5547  384.05  5583.5  385.23  5591.8  384.19  5599.5  385.53  5711.9  388.79
  5869.9  394.35  5984.3  400.28  6026.2  403.05  6068.9  404.02    6101  404.68
#Mann= 9 ,-1 , 0
  2764.3     .04       0    4203     .05       0  4333.6     .04       0
  5001.5     .04       0    5020     .04       0    5547     .05       0
  5711.9     .04       0  5984.3    .013       0  6068.9     .04       0
Bank Sta=5001.5,5020
XS Rating Curve= 0 ,0
Exp/Cntr=0.3,0.1

Type RM Length L Ch R = 1 ,393417  ,598,598,598
BEGIN DESCRIPTION:
Mapping XS d9761675
END DESCRIPTION:
XS GIS Cut Line= 3
      2412981.74     13572840.57      2412411.55     13571601.86
      2411867.59     13570572.94
#Sta/Elev= 30
  3626.2  397.92  3731.5  396.68  3748.9  397.63  3820.7  397.11  3895.6     396
  4040.7  393.16  4058.5  393.52  4107.1   391.9  4404.5  383.95  4568.3  380.84
  4631.7  380.78  4637.2  379.91  4689.2  378.81  4946.8  378.28  4964.2  377.48
  4965.8  375.04  4966.3  374.54  4984.9  375.04  4998.2  375.15  5014.6  378.38
  5042.8  378.99    5141  378.79  5311.4  376.38  5377.4  377.24  5509.5  381.13
  5740.3  385.26    5937  390.38  6020.7  392.85  6081.1  393.48  6153.7  396.09
#Mann= 10 ,-1 , 0
  3626.2     .12       0  3820.7     .04       0  3895.6    .035       0
  4040.7     .04       0  4107.1    .035       0  4404.5     .04       0
  4965.8     .04       0  4984.9     .04       0    5937     .05       0
  6081.1     .04       0
Bank Sta=4965.8,4984.9
XS Rating Curve= 0 ,0
Exp/Cntr=0.3,0.1

Type RM Length L Ch R = 1 ,392819  ,963,963,963
BEGIN DESCRIPTION:
SALT CREEK 88.0
END DESCRIPTION:
XS GIS Cut Line= 3
      2413124.98     13571524.98        2412825.       13571225.
        2411925.       13570425.
#Sta/Elev= 30
  4540.4  393.37  4553.1  392.83  4752.5  382.69  4794.9     382  4809.1  379.87
  4837.4  377.58  4893.9  376.74  4922.2  377.92  4950.5  377.84    4986  374.99
  5006.9   374.9    5057  377.88  5106.4  378.22  5255.2  376.24  5309.2  373.96
  5309.7  373.46  5328.3  373.96  5404.1  377.35    5425  376.72  5538.7  378.53
  5573.8  381.38  5594.7  379.96  5644.9  381.51  5757.8  382.34  5949.3  387.37
  5984.4  388.11  6004.7  389.63  6090.6  393.87  6112.4  393.99  6168.8  396.34
#Mann= 6 ,-1 , 0
  4540.4    .035       0  4553.1     .04       0  5309.2     .04       0
  5328.3     .04       0  5949.3     .05       0  6004.7     .04       0
Bank Sta=5309.2,5328.3
XS Rating Curve= 0 ,0
Exp/Cntr=0.3,0.1

Type RM Length L Ch R = 1 ,391856  ,870,870,870
BEGIN DESCRIPTION:
Mapping XS 6751402a
END DESCRIPTION:
XS GIS Cut Line= 3
      2414148.28     13570900.57       2413696.1     13570454.94
      2411959.64     13570376.31
#Sta/Elev= 30
    3552  412.49  3890.6   403.5  4003.8  398.53  4039.1  395.38  4173.5  388.17
  4368.1  379.92  4438.2   378.4  4515.2  374.98  4658.4  375.38  4698.9  371.22
  4699.4  370.72  4718.1  371.22  4718.5  372.22  4735.8  374.13  4818.6  375.49
  4988.8  373.51  5058.9  374.92  5159.8   374.8  5397.8   381.1  5439.2   380.4
  5459.3  381.96  5519.3  383.06  5549.4   381.6  5623.4  382.74  5734.2   386.9
  5759.6  389.31  5769.6  388.17  5789.6  388.67  5919.7  394.24  5925.1  395.67
#Mann= 5 ,-1 , 0
    3552     .04       0  4698.9     .04       0  4718.1     .04       0
  5159.8     .05       0  5734.2     .04       0
Bank Sta=4698.9,4718.1
XS Rating Curve= 0 ,0
Exp/Cntr=0.3,0.1

Type RM Length L Ch R = 1 ,390986  ,259,259,259
BEGIN DESCRIPTION:
Mapping XS 367ab264
END DESCRIPTION:
XS GIS Cut Line= 3
      2415839.19     13568547.78      2413178.34     13569714.36
      2411782.37      13570376.3
#Sta/Elev= 30
  2145.8  402.41  2314.5  398.55  2368.6  397.23  2480.2  395.26  2739.2  388.02
  2766.5  387.12  2799.4  388.82    2894  387.29  3072.9  387.16  3211.1  384.64
  3229.9  384.11  3247.4  385.25  3520.9  383.03  3724.2  384.79  3964.2  375.71
  4137.6  375.17  4271.2  369.54  4361.6  370.03  4432.4  369.32  4492.4  372.15
  4911.6  371.85  4978.4  370.51  5000.9  368.49  5001.4  367.99  5020.2  368.49
    5077  371.17  5431.1   374.3  5796.3  382.62    6096  386.24  6596.1   400.6
#Mann= 13 ,-1 , 0
  2145.8    .035       0  2314.5     .04       0  2368.6    .013       0
  2480.2     .04       0  2739.2     .05       0  2766.5     .04       0
    2894    .013       0  3211.1     .05       0  3229.9    .013       0
  3964.2     .04       0  4361.6    .013       0  5000.9     .03       0
  5020.2    .013       0
Bank Sta=5000.9,5020.2
XS Rating Curve= 0 ,0
Exp/Cntr=0.3,0.1

Type RM Length L Ch R = 1 ,390727  ,618,618,618
BEGIN DESCRIPTION:
Mapping XS 8a4ddbba
END DESCRIPTION:
XS GIS Cut Line= 3
      2415518.08     13568154.53       2413112.8     13569484.97
      2411500.52     13570179.69
#Sta/Elev= 30
  2322.1  387.25    2479  385.18  2560.3  381.54  2766.4  378.14    3303  375.38
  3390.7  375.99  3450.2  376.63  3582.7  374.78  3612.8  376.02  3900.3  371.38
  4576.9  371.31  4605.7  370.79  4633.9  366.88  4634.4  366.38  4653.2  366.88
  4656.9  368.39  4679.8  370.34  4817.6  367.66  4862.6  371.87  4936.7  371.43
  4952.8  369.22    5018  367.76  5131.2  372.59    5602  377.71  5808.9  383.46
  6095.9  386.66    6288  392.87  6323.9  392.87  6646.1   407.1  6826.4  411.37
#Mann= 5 ,-1 , 0
  2322.1     .04       0    3303    .013       0  3390.7     .04       0
  4633.9     .04       0  4653.2     .04       0
Bank Sta=4633.9,4653.2
XS Rating Curve= 0 ,0
Exp/Cntr=0.3,0.1

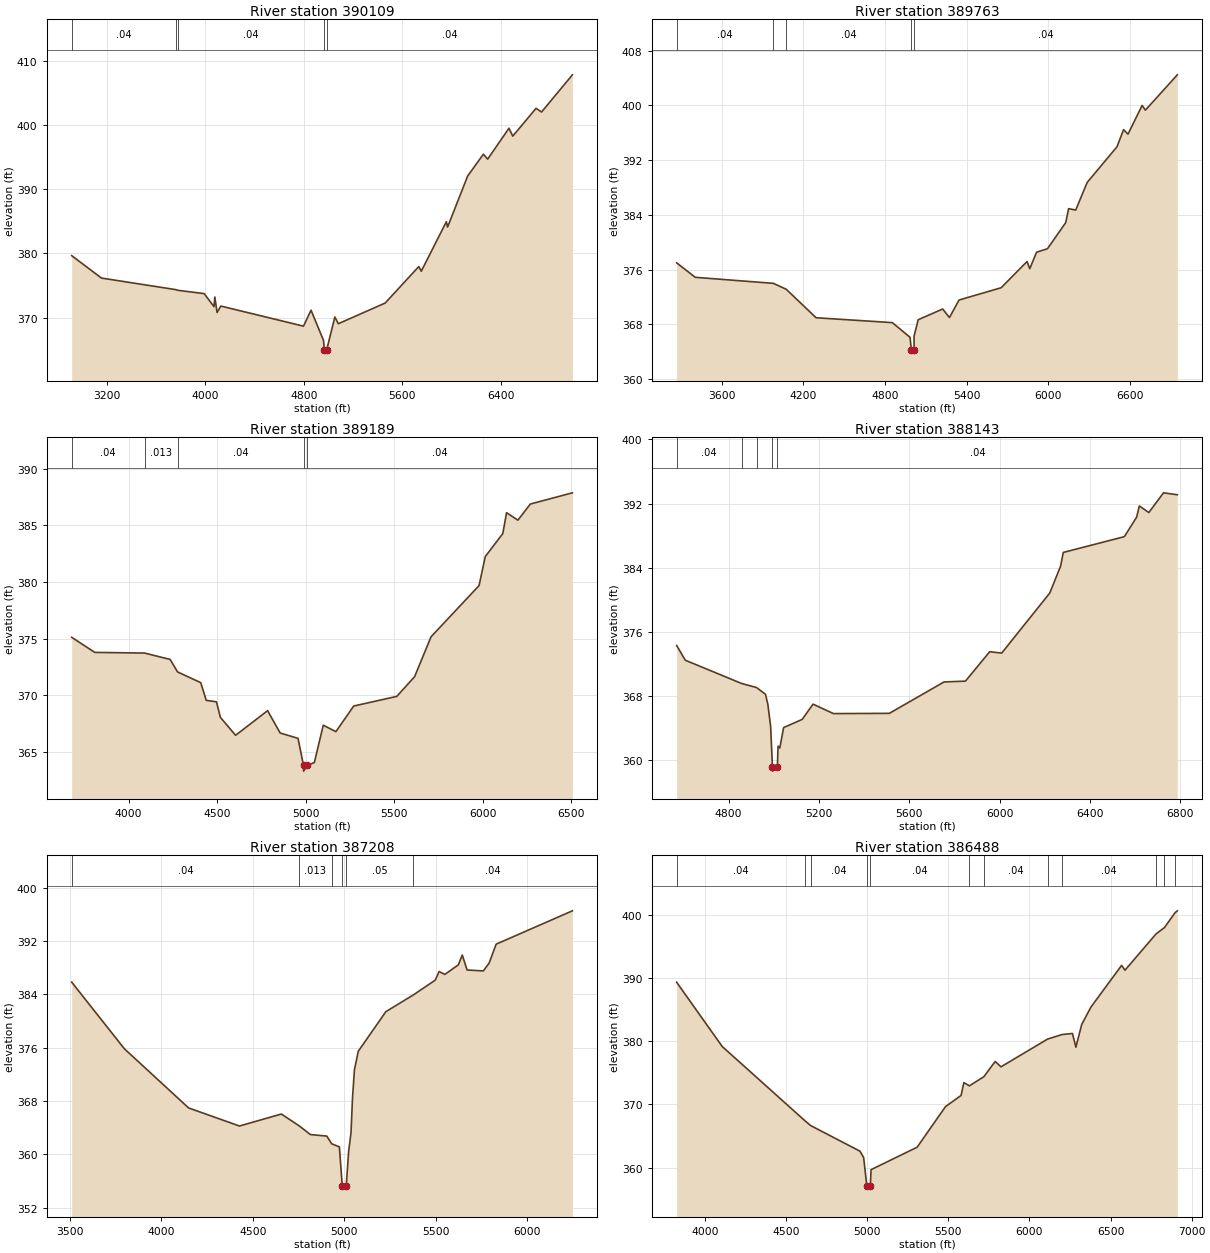
Type RM Length L Ch R = 1 ,390109  ,346,346,346
BEGIN DESCRIPTION:
Mapping XS 79c989ab
END DESCRIPTION:
XS GIS Cut Line= 3
      2415308.37     13568147.97       2414305.6     13568731.28
      2411449.08     13569275.07
#Sta/Elev= 30
  2913.1  379.65    3155  376.16  3758.5  374.36  3775.7  374.25  3989.1  373.74
  4069.4  371.71    4076  373.21  4094.2   370.8  4124.8   371.8  4796.5  368.67
  4857.6  371.16  4959.4  366.43  4965.1  364.97  4965.6  364.47  4984.9  364.97
    5051  370.09  5079.4  369.05    5460  372.27  5733.1  377.95  5753.4  377.22
    5957  384.93  5967.2   384.1  6130.1  392.05    6258  395.45  6292.9  394.68
    6466   399.5  6496.5  398.26  6685.7  402.59  6730.7  402.02    6981  407.81
#Mann= 5 ,-1 , 0
  2913.1     .04       0  3758.5    .013       0  3775.7     .04       0
  4965.1     .04       0  4984.9     .04       0
Bank Sta=4965.1,4984.9
XS Rating Curve= 0 ,0
Exp/Cntr=0.3,0.1

Type RM Length L Ch R = 1 ,389763  ,574,574,574
BEGIN DESCRIPTION:
Mapping XS 9c2eb7e8
END DESCRIPTION:
XS GIS Cut Line= 4
      2415190.35     13568154.55      2414318.71     13568626.42
      2412549.18     13568626.42      2411670.97     13568895.13
#Sta/Elev= 30
  3269.2  376.99  3406.4  374.87  3979.9  373.99  4074.9  373.12  4294.1  368.96
  4854.1  368.25  4984.1  366.11  4994.1  364.29  4994.6  363.79    5014  364.29
  5014.1  366.28  5044.1  368.67  5224.1  370.24  5274.1  368.99  5344.1  371.55
  5654.1  373.35  5844.1  377.18  5864.1  376.13  5914.1  378.54  5994.1  379.05
  6128.4  382.87  6149.6  384.91  6201.6   384.7  6285.9  388.74  6504.9  393.95
  6553.4  396.46  6586.1   395.8  6689.7  399.99    6714  399.31  6948.3  404.47
#Mann= 5 ,-1 , 0
  3269.2     .04       0  3979.9    .013       0  4074.9     .04       0
  4994.1     .04       0    5014     .04       0
Bank Sta=4994.1,5014
XS Rating Curve= 0 ,0
Exp/Cntr=0.3,0.1

Type RM Length L Ch R = 1 ,389189  ,1046,1046,1046
BEGIN DESCRIPTION:
Mapping XS 9e05a0bd
END DESCRIPTION:
XS GIS Cut Line= 4
      2415132.66     13568120.25      2414362.24     13568489.18
      2413298.88     13567729.63      2412810.58     13567273.89
#Sta/Elev= 30
  3678.8  375.13  3809.3   373.8  4090.8  373.74    4235  373.18  4276.8  372.08
    4408  371.13    4439  369.57  4496.7  369.44  4518.9  368.07  4604.9  366.49
  4785.6  368.66  4856.9  366.69  4957.6  366.22  4988.6  363.83  4989.1  363.33
  5010.3  363.83  5049.8  364.09  5100.2  367.38  5171.5  366.81  5272.2  369.07
  5515.6  369.92  5616.3  371.66  5709.4  375.18  5980.4  379.69  6015.6  382.25
  6114.7  384.28  6135.8  386.12  6199.8  385.46  6270.1  386.88  6507.7  387.87
#Mann= 5 ,-1 , 0
  3678.8     .04       0  4090.8    .013       0  4276.8     .04       0
  4988.6     .04       0  5010.3     .04       0
Bank Sta=4988.6,5010.3
XS Rating Curve= 0 ,0
Exp/Cntr=0.3,0.1

Type RM Length L Ch R = 1 ,388143  ,935,935,935
BEGIN DESCRIPTION:
Mapping XS 39e839d4
END DESCRIPTION:
XS GIS Cut Line= 3
      2415131.43      13568049.7      2414698.83     13567918.61
      2413068.44     13567244.19
#Sta/Elev= 30
  4570.4  374.29  4608.8  372.45  4857.9  369.55  4924.3  369.04  4963.7   368.2
  4974.2  366.95  4986.5  364.19  4994.6  359.11  4995.1  358.61  5016.4  359.11
  5019.4  361.72  5027.2   361.5  5043.9  364.04  5126.4  365.07  5174.2  366.97
  5264.6  365.79    5512  365.82  5754.2  369.74    5849  369.84  5956.2  373.51
  6009.4  373.34  6222.3  380.84  6270.1  384.19  6281.9   385.9  6552.4  387.87
  6606.5  390.29  6618.7   391.7  6660.7  390.88  6725.6  393.34  6786.8   393.1
#Mann= 5 ,-1 , 0
  4570.4     .04       0  4857.9    .013       0  4924.3     .04       0
  4994.6     .04       0  5016.4     .04       0
Bank Sta=4994.6,5016.4
XS Rating Curve= 0 ,0
Exp/Cntr=0.3,0.1

Type RM Length L Ch R = 1 ,387208  ,720,720,720
BEGIN DESCRIPTION:
Mapping XS 92c2cefa
END DESCRIPTION:
XS GIS Cut Line= 3
      2415616.37     13567997.26      2414823.35     13567420.52
      2413152.15       13566870.
#Sta/Elev= 30
  3508.9  385.83  3797.2  375.84  4148.8  366.97  4427.1  364.26  4656.2  366.06
  4753.7  364.29  4815.1  362.98  4905.1  362.75  4931.5   361.6  4973.9  361.13
  4989.5   355.3    4990   354.8  5011.4   355.3  5024.7   360.5  5037.5  363.25
  5045.7  368.48  5056.3   372.7  5077.3  375.47  5228.1   381.4  5378.9  383.92
  5498.5  386.13  5519.5  387.42  5551.1  386.99  5624.8  388.42  5646.4  389.89
  5672.9  387.65  5761.7  387.51  5793.3  388.68  5831.8  391.52    6249  396.52
#Mann= 6 ,-1 , 0
  3508.9     .04       0  4753.7    .013       0  4931.5     .05       0
  4989.5     .05       0  5011.4     .05       0  5378.9     .04       0
Bank Sta=4989.5,5011.4
XS Rating Curve= 0 ,0
Exp/Cntr=0.3,0.1

Type RM Length L Ch R = 1 ,386488  ,556,556,556
BEGIN DESCRIPTION:
Mapping XS f5fd6d0e
END DESCRIPTION:
XS GIS Cut Line= 4
      2415760.54     13567964.48      2415177.26     13567217.35
      2414410.46     13566850.33      2413342.63     13566129.71
#Sta/Elev= 30
  3825.5  389.36  4106.5  379.18  4615.1  367.45  4650.9  366.67  4955.6   362.6
  4978.3  361.59  4997.7  357.09  4998.2  356.59  5019.6  357.09  5023.7  359.67
    5308  363.23  5482.5  369.65  5578.8  371.43  5595.9  373.46  5630.1  372.95
    5719  374.39  5788.9  376.81  5824.9  375.96  6112.4  380.36  6202.3  381.08
  6265.5  381.24  6286.5  379.07  6322.5  382.68  6379.5  385.43  6568.3  392.03
  6589.3  391.27  6780.9  397.02  6832.5  398.02  6897.3  400.36  6911.7  400.67
#Mann= 12 ,-1 , 0
  3825.5     .04       0  4615.1     .03       0  4650.9     .04       0
  4997.7     .04       0  5019.6     .04       0  5630.1     .03       0
    5719     .04       0  6112.4     .03       0  6202.3     .04       0
  6780.9     .05       0  6832.5     .04       0  6897.3     .05       0
Bank Sta=4997.7,5019.6
XS Rating Curve= 0 ,0
Exp/Cntr=0.3,0.1