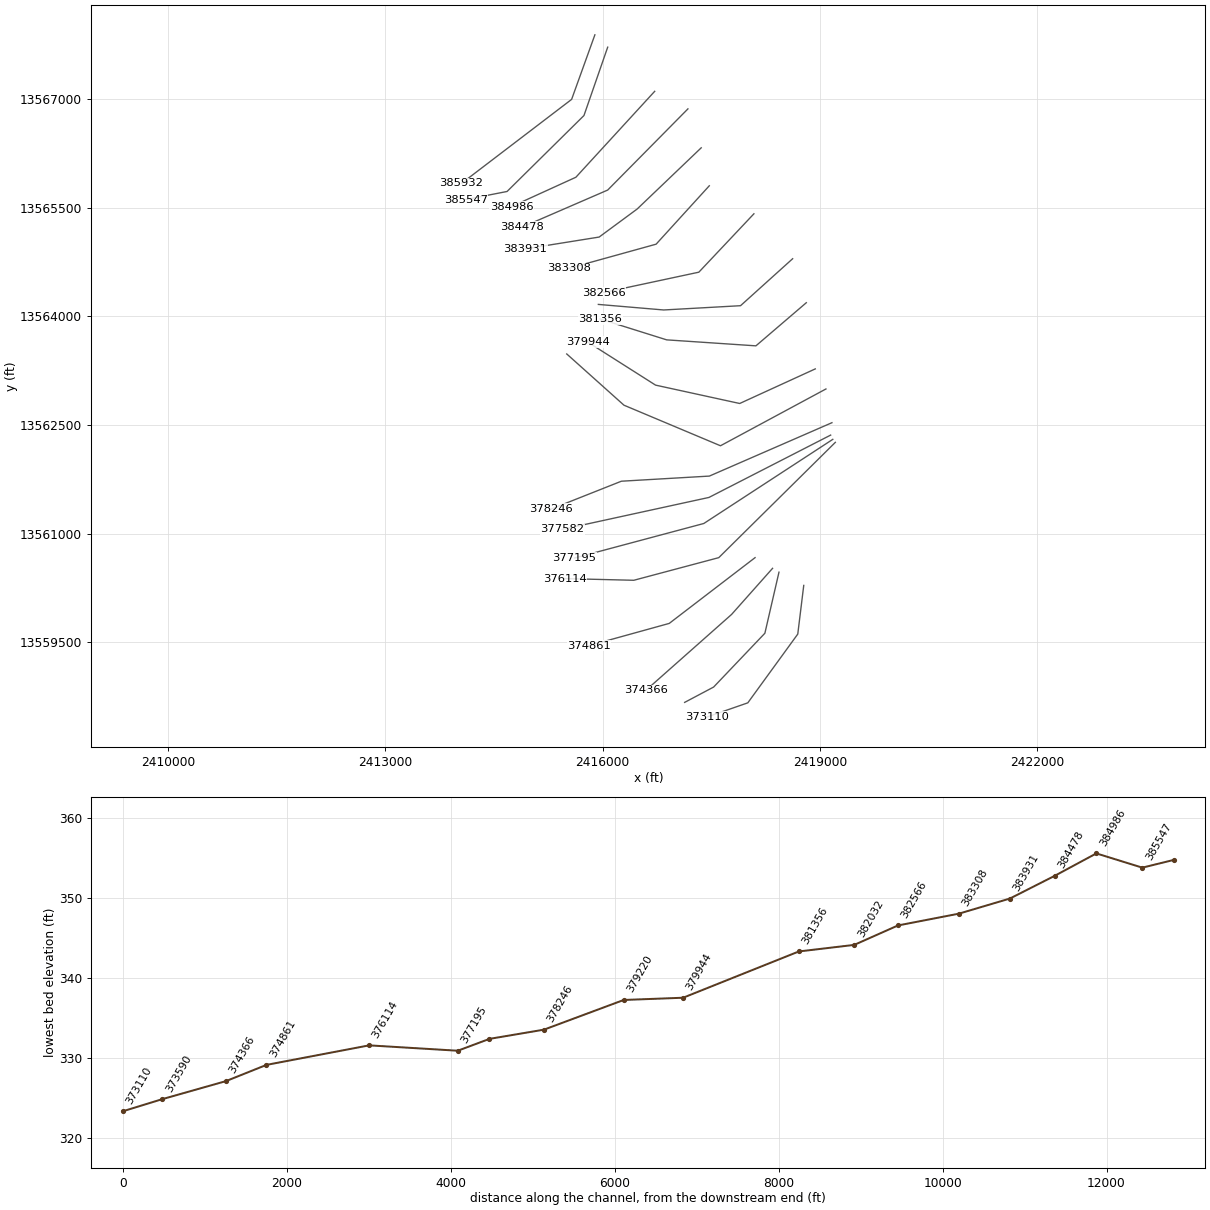
HEC-RAS study COLETO CREEK.prj: COLETO CREEK Base Level Engineering

--- COLETO CREEK.g01 (geometry) --- (continued)

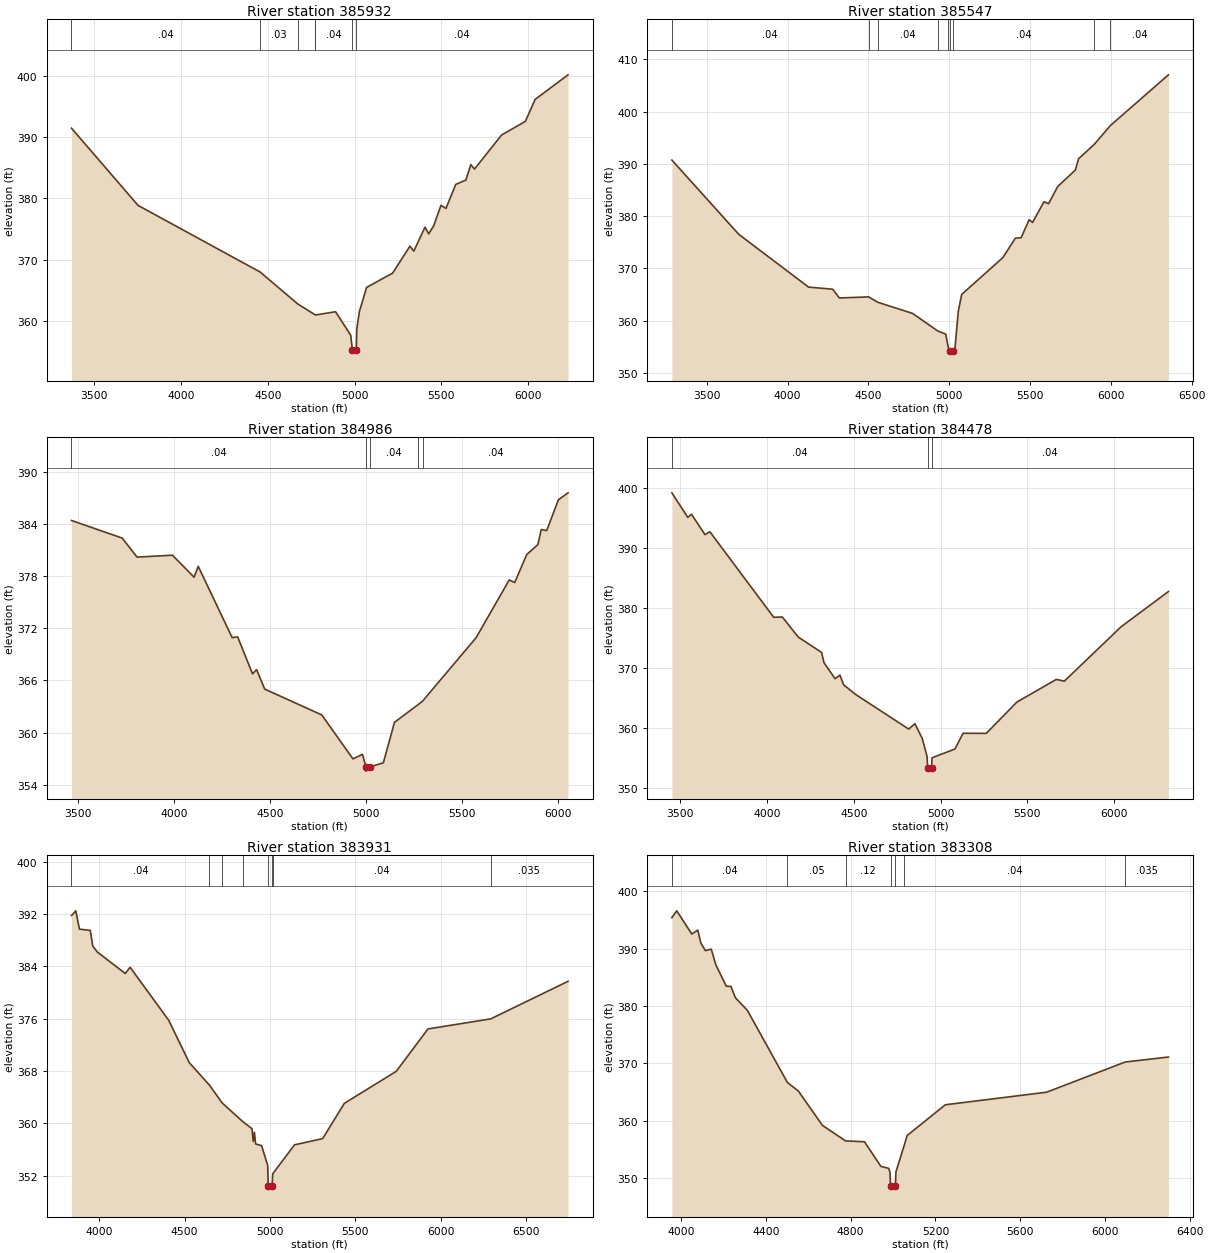
Type RM Length L Ch R = 1 ,385932  ,385,385,385
BEGIN DESCRIPTION:
Mapping XS 53767b69
END DESCRIPTION:
XS GIS Cut Line= 3
      2415891.62     13567885.83      2415570.49     13566994.52
      2414049.98     13565834.47
#Sta/Elev= 30
  3369.4  391.43  3752.7  378.84  4455.5  367.98  4673.5  362.75  4771.4  361.02
  4773.9  360.97  4890.4   361.5  4977.6  357.68  4987.4  355.25  4987.9  354.75
  5009.5  355.25  5012.9  358.75  5027.5  361.52  5069.1  365.47  5218.8  367.79
  5318.5  372.18  5341.3  371.39  5405.4  375.29  5426.6   374.2  5455.6  375.51
  5497.3  378.84  5526.3  378.35  5582.5  382.26  5640.6  382.97  5669.5  385.49
  5690.5  384.76  5846.5  390.32  5983.5  392.54  6039.7  396.12  6229.3  400.13
#Mann= 7 ,-1 , 0
  3369.4     .04       0  4455.5     .03       0  4673.5     .04       0
  4771.4     .03       0  4773.9     .04       0  4987.4     .04       0
  5009.5     .04       0
Bank Sta=4987.4,5009.5
XS Rating Curve= 0 ,0
Exp/Cntr=0.3,0.1

Type RM Length L Ch R = 1 ,385547  ,561,561,561
BEGIN DESCRIPTION:
Mapping XS e0f812ad
END DESCRIPTION:
XS GIS Cut Line= 4
      2416068.57     13567715.41      2415740.89     13566771.69
      2414679.17     13565723.08       2414109.5     13565611.76
#Sta/Elev= 30
  3284.6  390.71  3697.9  376.52  4130.2  366.41  4279.2  366.01  4320.7  364.33
  4501.6  364.54  4559.2   363.5  4773.3  361.38  4929.1  358.03  4978.4  357.42
  4995.6  354.72  5002.7  354.28  5003.2  353.78  5024.8  354.28    5035  354.41
  5056.2  361.75  5077.4  365.01    5332  372.05  5409.7  375.79  5445.1  375.85
  5494.6  379.31  5515.8  378.77  5586.5  382.74  5614.8  382.36  5671.3  385.66
  5780.5   388.8  5800.5  390.97  5898.2  393.74  5997.7  397.33  6356.3  407.02
#Mann= 9 ,-1 , 0
  3284.6     .04       0  4501.6     .03       0  4559.2     .04       0
  4929.1      .1       0  4995.6     .04       0  5002.7     .04       0
  5024.8     .04       0  5898.2     .03       0  5997.7     .04       0
Bank Sta=5002.7,5024.8
XS Rating Curve= 0 ,0
Exp/Cntr=0.3,0.1

Type RM Length L Ch R = 1 ,384986  ,508,508,508
BEGIN DESCRIPTION:
Mapping XS 478da511
END DESCRIPTION:
XS GIS Cut Line= 3
      2416717.39     13567105.91      2415629.47     13565919.69
      2414739.09     13565513.78
#Sta/Elev= 30
    3465  384.37  3729.1  382.35  3806.8  380.16  3991.2  380.38    4104  377.85
  4125.6   379.1  4302.6   370.9  4330.9     371  4408.6  366.74  4429.6  367.23
  4472.1  364.99  4769.4  362.02  4932.1  356.97  4982.1  357.49  4999.2  356.06
  4999.7  355.56  5021.7  356.06  5090.5  356.52  5148.5  361.17  5269.6  363.17
    5295  363.61    5574   370.9  5746.6  377.54  5775.1  377.24  5837.8  380.46
  5895.8   381.6  5913.4  383.33  5941.9  383.21  6002.6  386.74  6053.1  387.55
#Mann= 5 ,-1 , 0
    3465     .04       0  4999.2     .04       0  5021.7     .04       0
  5269.6     .03       0    5295     .04       0
Bank Sta=4999.2,5021.7
XS Rating Curve= 0 ,0
Exp/Cntr=0.3,0.1

Type RM Length L Ch R = 1 ,384478  ,547,547,547
BEGIN DESCRIPTION:
Mapping XS a0a72cdd
END DESCRIPTION:
XS GIS Cut Line= 3
      2417176.21     13566863.47      2416068.58     13565742.74
      2414889.44     13565231.78
#Sta/Elev= 30
  3452.4   399.2  3544.1   395.1  3565.3  395.63  3643.1  392.23  3671.4   392.7
  4039.1  378.43  4088.6  378.48  4180.5  375.13  4314.9  372.57    4329  370.84
  4392.6  368.19  4420.9  368.78  4442.1  367.15  4512.9  365.52  4816.9  359.78
  4852.3  360.67  4894.7  358.23    4923  355.16  4925.8  353.26  4926.3  352.76
  4948.4  353.26  4951.3  354.99  5083.2  356.45  5130.1  359.08  5263.8  359.06
  5439.1  364.26  5666.7  368.06  5713.6  367.78  6040.6  376.85  6313.2  382.73
#Mann= 3 ,-1 , 0
  3452.4     .04       0  4925.8     .04       0  4948.4     .04       0
Bank Sta=4925.8,4948.4
XS Rating Curve= 0 ,0
Exp/Cntr=0.3,0.1

Type RM Length L Ch R = 1 ,383931  ,623,623,623
BEGIN DESCRIPTION:
Mapping XS 73c331e9
END DESCRIPTION:
XS GIS Cut Line= 4
      2417359.68     13566326.03      2416474.92     13565480.58
      2415950.61     13565093.91      2414929.08      13564930.2
#Sta/Elev= 30
  3837.1   391.8  3862.3  392.52  3883.7  389.72  3947.2  389.52  3961.4  387.13
  3989.7  386.19  4152.3  382.93  4180.6  383.88    4407  375.76  4527.2  369.28
  4645.5  365.84  4720.2  363.11  4841.8  360.23  4894.8  359.17  4902.1  357.23
    4909  358.62  4916.2  356.84  4951.5  356.56    4987  353.52  4989.8  350.42
  4990.3  349.92  5012.5  350.42  5016.4  352.26  5143.8   356.7  5308.8  357.65
  5436.1  363.05  5740.2  367.95  5926.1  374.44    6294  375.98  6746.9  381.73
#Mann= 8 ,-1 , 0
  3837.1     .04       0  4645.5     .05       0  4720.2     .04       0
  4841.8     .05       0  4989.8     .05       0  5012.5     .05       0
  5016.4     .04       0    6294    .035       0
Bank Sta=4989.8,5012.5
XS Rating Curve= 0 ,0
Exp/Cntr=0.3,0.1

Type RM Length L Ch R = 1 ,383308  ,742,742,742
BEGIN DESCRIPTION:
Mapping XS 527aba85
END DESCRIPTION:
XS GIS Cut Line= 3
      2417471.12     13565801.75      2416737.07      13564995.6
      2415531.21     13564661.37
#Sta/Elev= 30
  3957.2  395.41  3980.2  396.59  4051.1  392.54  4079.5  393.23  4093.7  390.97
  4115.1  389.65    4143   389.9  4164.6  387.17  4213.9  383.43  4235.6  383.41
  4256.5  381.44  4313.3  379.22  4501.8  366.65  4553.8  365.14  4667.3  359.15
  4776.6  356.44  4865.3   356.3    4943  351.99  4978.8  351.67  4985.6  350.99
  4988.4  348.53  4988.9  348.03  5011.1  348.53  5013.9  351.06    5050  355.33
  5066.8  357.39  5246.8  362.75  5724.1  364.94    6095  370.21  6298.8  371.08
#Mann= 7 ,-1 , 0
  3957.2     .04       0  4501.8     .05       0  4776.6     .12       0
  4988.4     .05       0  5011.1     .12       0    5050     .04       0
    6095    .035       0
Bank Sta=4988.4,5011.1
XS Rating Curve= 0 ,0
Exp/Cntr=0.3,0.1

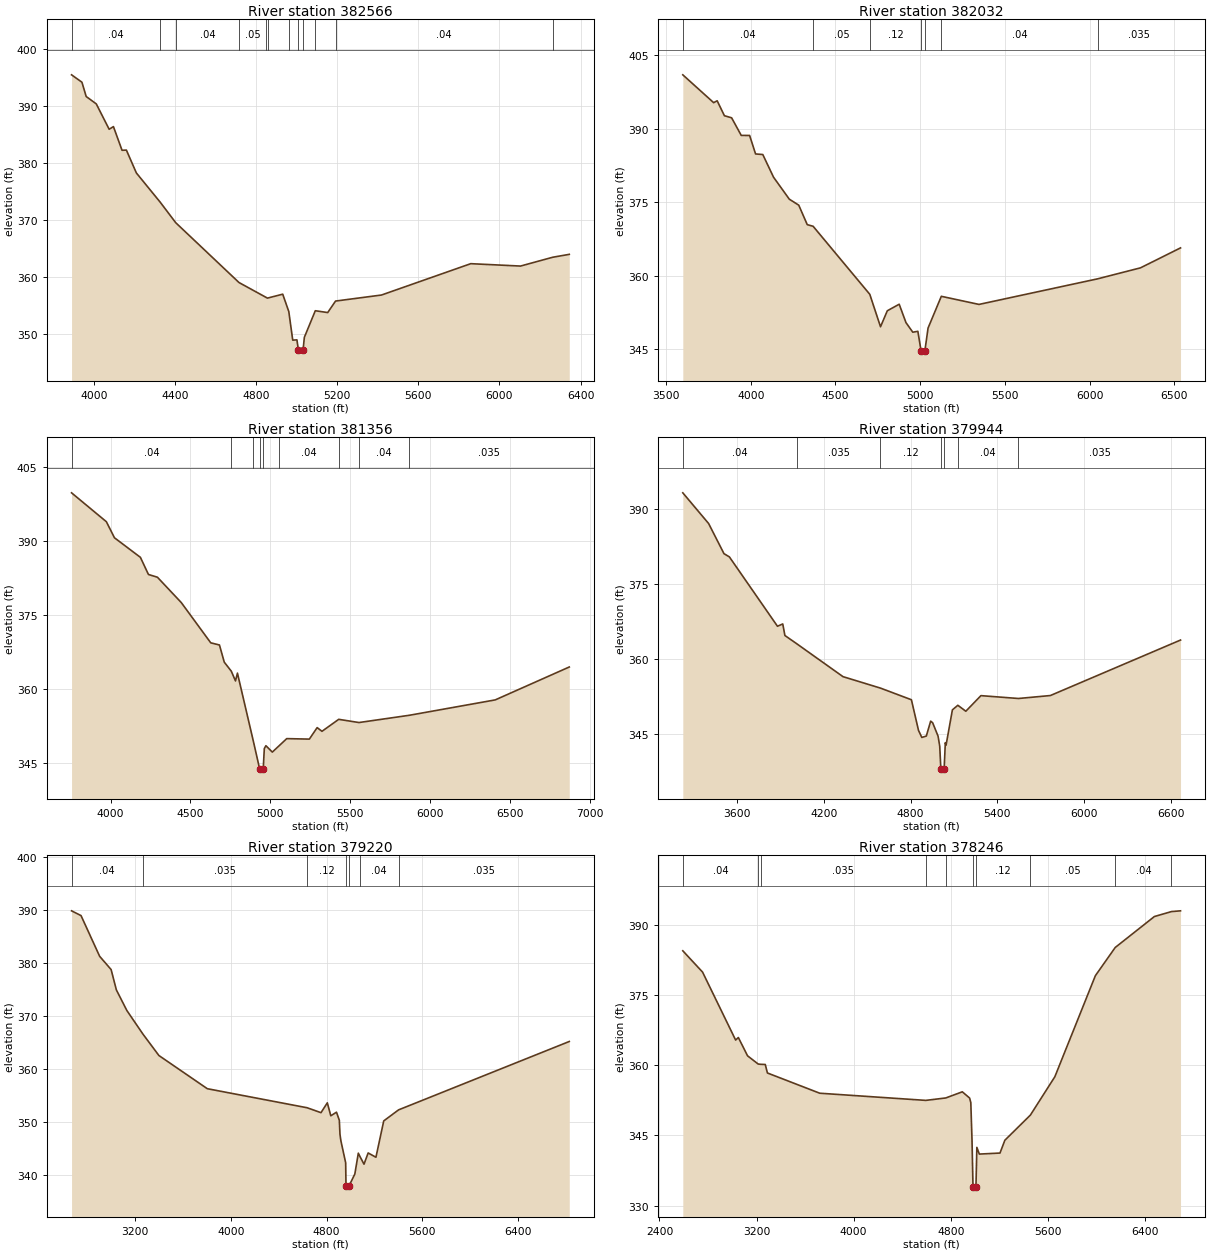
Type RM Length L Ch R = 1 ,382566  ,534,534,534
BEGIN DESCRIPTION:
Mapping XS 417e3053
END DESCRIPTION:
XS GIS Cut Line= 3
      2418087.18     13565415.07      2417326.92     13564608.92
      2416009.82     13564327.16
#Sta/Elev= 30
  3889.4  395.47  3940.6  394.17  3961.6  391.66  4011.4  390.36  4074.9   385.9
    4096  386.37  4138.4  382.21  4159.9  382.24  4209.2  378.22  4327.1  373.07
  4403.3  369.48  4715.2  358.97  4850.3  356.33    4856  356.23    4931  356.92
    4961  353.86  4980.4  348.84    5001  348.89  5008.5  347.06    5009  346.56
  5031.3  347.06  5037.7  349.34  5091.7  354.01  5152.9  353.69  5191.6  355.71
  5418.1  356.77  5858.5  362.28  6103.9  361.86  6262.6  363.41  6344.4  363.92
#Mann= 12 ,-1 , 0
  3889.4     .04       0  4327.1     .05       0  4403.3     .04       0
  4715.2     .05       0  4850.3     .12       0    4856     .05       0
    4961     .12       0  5008.5     .05       0  5031.3     .12       0
  5091.7     .05       0  5191.6     .04       0  6262.6    .035       0
Bank Sta=5008.5,5031.3
XS Rating Curve= 0 ,0
Exp/Cntr=0.3,0.1

Type RM Length L Ch R = 1 ,382032  ,676,676,676
BEGIN DESCRIPTION:
Mapping XS 249b39d4
END DESCRIPTION:
XS GIS Cut Line= 4
      2418621.87     13564794.69      2417902.63     13564146.19
      2416841.43     13564087.23      2415939.75     13564163.84
#Sta/Elev= 30
  3599.4  401.04  3781.3  395.35  3802.2  395.73  3844.8  392.68  3887.4  392.25
  3944.2  388.65  3993.5  388.64  4028.7  384.86  4071.3  384.74  4134.8   380.1
  4227.5  375.62  4283.5  374.38  4333.6   370.4  4368.2  370.07  4702.4  356.16
  4765.8  349.52  4805.8  352.79  4875.9  354.13    4916  350.37  4956.1  348.41
  4986.1  348.59  5004.8  344.63  5005.3  344.13  5027.6  344.63  5046.2  349.25
  5124.5  355.75  5346.7  354.09  6046.3  359.32  6299.5  361.57  6535.6  365.65
#Mann= 7 ,-1 , 0
  3599.4     .04       0  4368.2     .05       0  4702.4     .12       0
  5004.8     .05       0  5027.6     .12       0  5124.5     .04       0
  6046.3    .035       0
Bank Sta=5004.8,5027.6
XS Rating Curve= 0 ,0
Exp/Cntr=0.3,0.1

Type RM Length L Ch R = 1 ,381356  ,1412,1412,1412
BEGIN DESCRIPTION:
Mapping XS 077547cc
END DESCRIPTION:
XS GIS Cut Line= 4
      2418810.56     13564187.47      2418114.87       13563592.
       2416882.7     13563674.54      2415962.97     13563963.43
#Sta/Elev= 30
  3755.7  399.73  3973.7  393.87  4024.2  390.62  4186.6  386.65  4236.9  383.18
  4293.1  382.62  4442.4  377.48  4626.8  369.32  4681.3  368.88  4711.4   365.4
  4755.3  363.58  4781.6   361.6  4793.8  363.18  4893.7  349.34  4932.4  343.81
  4932.9  343.31  4955.3  343.81    4962  347.89    4972  348.46  5012.1  347.17
  5055.2  348.47  5102.3   349.9  5243.8   349.8  5292.7  352.13  5322.8  351.38
  5427.6  353.81  5554.4  353.16  5869.2  354.63  6407.1  357.75  6870.4  364.42
#Mann= 9 ,-1 , 0
  3755.7     .04       0  4755.3     .05       0  4893.7     .12       0
  4932.4     .05       0  4955.3     .12       0  5055.2     .04       0
  5427.6     .05       0  5554.4     .04       0  5869.2    .035       0
Bank Sta=4932.4,4955.3
XS Rating Curve= 0 ,0
Exp/Cntr=0.3,0.1

Type RM Length L Ch R = 1 ,379944  ,724,724,724
BEGIN DESCRIPTION:
Mapping XS 4ca6f92f
END DESCRIPTION:
XS GIS Cut Line= 4
      2418934.31     13563273.63      2417890.84     13562796.11
      2416729.41     13563049.61      2415792.06     13563645.04
#Sta/Elev= 30
  3222.5   393.2  3401.3  387.06  3507.7  381.03  3544.9  380.39  3878.1  366.51
  3914.6  366.97  3929.6  364.66  4012.1     363  4331.8  356.43  4591.1  354.14
  4805.6  351.81  4854.6   345.7  4877.6  344.27  4908.8  344.54    4939  347.53
  4952.7  347.21  4990.2  344.53  5001.7  342.53  5009.4  338.03  5009.9  337.53
  5032.4  338.03  5040.5  343.22  5045.6  342.72  5089.5  349.79  5127.2   350.7
  5182.5  349.51    5287  352.63  5546.9  352.06    5768  352.65  6669.3  363.75
#Mann= 7 ,-1 , 0
  3222.5     .04       0  4012.1    .035       0  4591.1     .12       0
  5009.4     .05       0  5032.4     .12       0  5127.2     .04       0
  5546.9    .035       0
Bank Sta=5009.4,5032.4
XS Rating Curve= 0 ,0
Exp/Cntr=0.3,0.1

Type RM Length L Ch R = 1 ,379220  ,974,974,974
BEGIN DESCRIPTION:
Mapping XS 44da890d
END DESCRIPTION:
XS GIS Cut Line= 4
       2419081.7     13562996.54      2417625.54     13562212.45
      2416293.14     13562772.52      2415503.17     13563479.96
#Sta/Elev= 30
  2667.9  389.88  2747.1  388.98  2902.7  381.28  2998.6  378.77  3042.4  374.93
  3130.1  371.03  3264.2  366.58  3397.8  362.52  3802.6  356.24  4636.6  352.64
  4752.5  351.71  4805.4  353.57  4834.6  351.12  4882.1   351.8  4905.8  350.27
  4911.2  347.62  4918.9  346.39  4958.7  342.24  4961.6  337.75  4962.1  337.25
  4984.7  337.75  5035.4  340.11  5064.6  344.05  5077.3  343.46  5112.1  341.97
  5146.7  344.09  5211.8  343.28  5276.9  350.15    5401  352.24  6827.5  365.17
#Mann= 7 ,-1 , 0
  2667.9     .04       0  3264.2    .035       0  4636.6     .12       0
  4961.6     .05       0  4984.7     .12       0  5077.3     .04       0
    5401    .035       0
Bank Sta=4961.6,4984.7
XS Rating Curve= 0 ,0
Exp/Cntr=0.3,0.1

Type RM Length L Ch R = 1 ,378246  ,664,664,664
BEGIN DESCRIPTION:
Mapping XS 47ede1e3
END DESCRIPTION:
XS GIS Cut Line= 4
      2419164.31     13562530.82      2417472.25     13561793.86
      2416257.77     13561723.12      2415291.05     13561339.97
#Sta/Elev= 30
  2592.1  384.41    2755  379.86  3027.6  365.35  3049.9   365.9  3125.8  361.99
  3213.2  360.24  3233.6  360.18  3271.7  360.14  3289.4  358.33  3720.7  354.01
  4594.7  352.48  4759.3     353  4895.7  354.31  4955.8  352.98  4965.8     352
  4975.8   343.8  4983.7  334.04  4984.2  333.54  5008.1  334.04  5015.4  342.45
  5035.9  341.02  5206.2  341.24  5246.3  343.97  5456.9  349.35  5658.4  357.53
  5992.2  379.09  6155.7  385.11  6478.5  391.72  6619.4  392.78  6694.1  392.94
#Mann= 10 ,-1 , 0
  2592.1     .04       0  3213.2     .03       0  3233.6    .035       0
  4594.7     .05       0  4759.3     .12       0  4983.7     .05       0
  5008.1     .12       0  5456.9     .05       0  6155.7     .04       0
  6619.4     .05       0
Bank Sta=4983.7,5008.1
XS Rating Curve= 0 ,0
Exp/Cntr=0.3,0.1

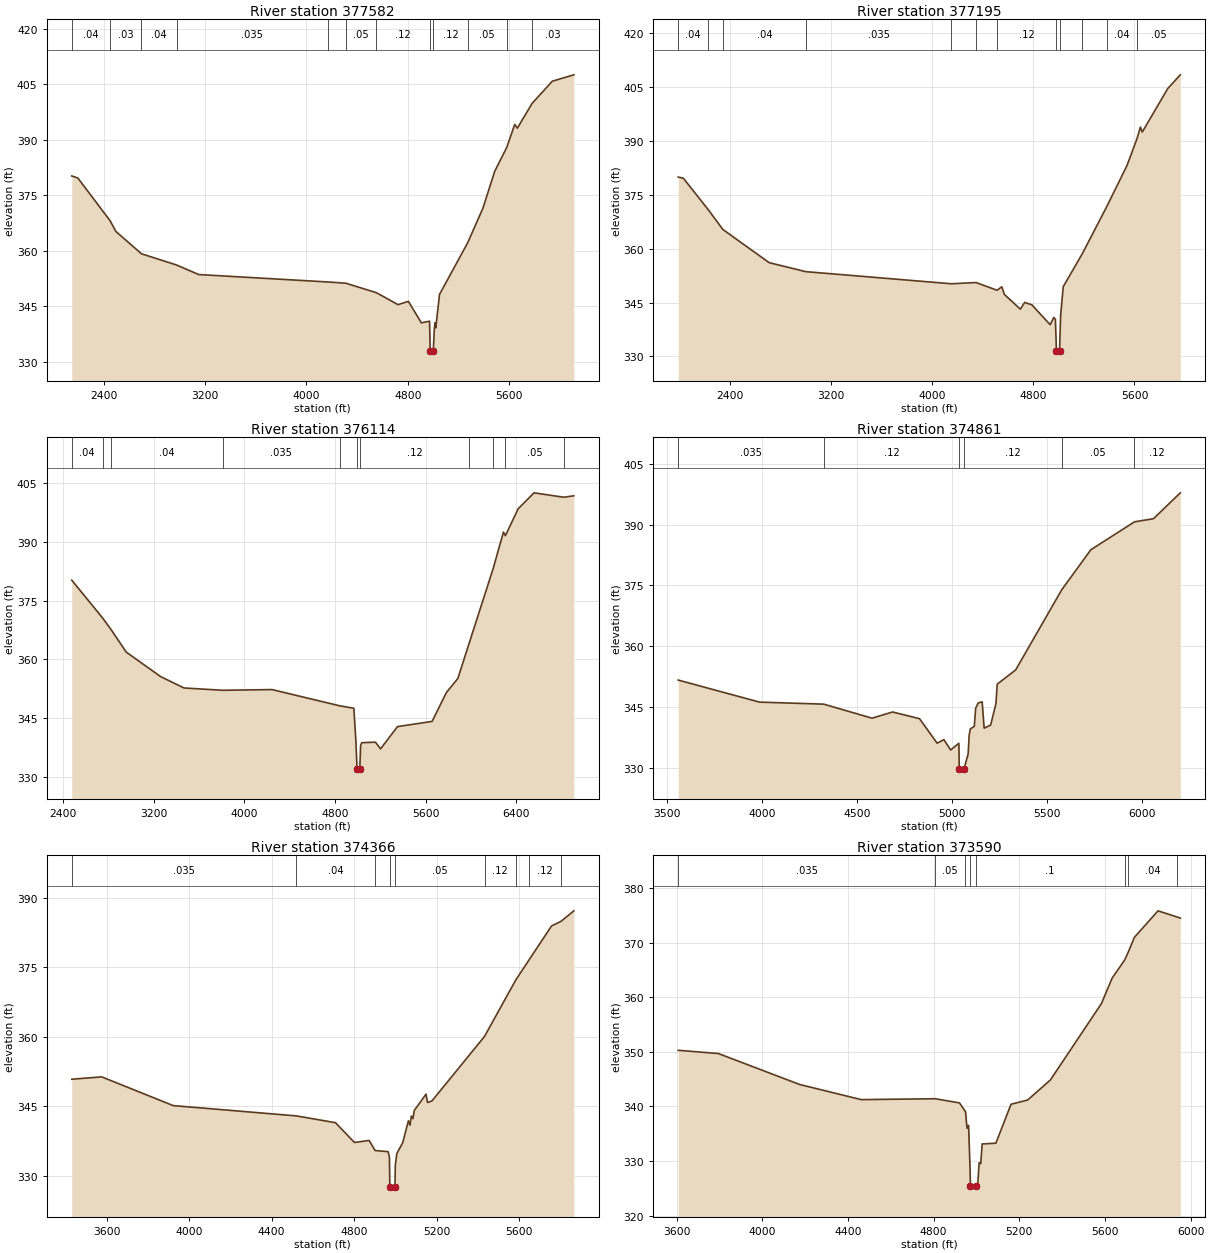
Type RM Length L Ch R = 1 ,377582  ,387,387,387
BEGIN DESCRIPTION:
Mapping XS 5b5aa6c3
END DESCRIPTION:
XS GIS Cut Line= 3
      2419146.57     13562359.83      2417466.36     13561499.09
      2415439.13      13561057.1
#Sta/Elev= 30
  2148.3  380.26  2196.2  379.72  2451.7  368.13  2495.8   365.3  2698.3  359.24
  2975.4  356.21    3150  353.63    4169  351.62  4310.4  351.29  4553.1  348.72
  4723.3  345.49  4805.2  346.38  4907.5  340.58  4972.4  341.02  4977.2  332.89
  4977.7  332.39  5001.6  332.89  5009.9  339.05  5016.3  340.62  5021.5  339.23
  5050.8  348.26  5273.1  362.21  5393.5  371.57  5486.5  381.52  5581.7     388
  5644.4   394.2  5664.9  393.18  5781.7  399.88  5941.2  405.88    6111   407.6
#Mann= 12 ,-1 , 0
  2148.3     .04       0  2451.7     .03       0  2698.3     .04       0
  2975.4    .035       0    4169     .12       0  4310.4     .05       0
  4553.1     .12       0  4977.2     .05       0  5001.6     .12       0
  5273.1     .05       0  5581.7     .04       0  5781.7     .03       0
Bank Sta=4977.2,5001.6
XS Rating Curve= 0 ,0
Exp/Cntr=0.3,0.1

Type RM Length L Ch R = 1 ,377195  ,1081,1081,1081
BEGIN DESCRIPTION:
Mapping XS 7b4702b1
END DESCRIPTION:
XS GIS Cut Line= 3
      2419176.08     13562300.89      2417395.61     13561139.46
      2415609.62     13560662.02
#Sta/Elev= 30
  1988.3  379.98    2029  379.65  2226.7  370.85    2342  365.36  2707.8  356.13
  2997.4  353.62    4150  350.24  4345.8  350.58  4512.3  348.43  4549.5  349.39
  4570.2  347.27  4696.2  343.17  4731.1  345.05  4787.6  344.37  4932.5  338.84
  4961.1  340.85  4973.9  340.35  4982.4  331.41  4982.9  330.91  5006.8  331.41
  5015.3  341.42    5036  349.42  5187.8  358.67  5379.2  371.65  5541.3  383.24
  5620.8  390.78  5646.7  393.91  5661.5  392.52  5864.1  404.68  5962.8  408.47
#Mann= 12 ,-1 , 0
  1988.3     .04       0  2226.7     .03       0    2342     .04       0
  2997.4    .035       0    4150     .12       0  4345.8     .05       0
  4512.3     .12       0  4982.4     .05       0  5006.8     .12       0
  5187.8     .05       0  5379.2     .04       0  5620.8     .05       0
Bank Sta=4982.4,5006.8
XS Rating Curve= 0 ,0
Exp/Cntr=0.3,0.1

Type RM Length L Ch R = 1 ,376114  ,1253,1253,1253
BEGIN DESCRIPTION:
Mapping XS ab548998
END DESCRIPTION:
XS GIS Cut Line= 4
       2419211.4     13562259.58      2417601.95     13560667.82
      2416428.74     13560355.35      2415473.68     13560378.93
#Sta/Elev= 30
  2475.6  380.19  2747.9  370.57  2822.8  367.61  2957.1  361.87  3261.2  355.63
  3466.3  352.75  3809.3  352.16  4244.1  352.34  4844.1  348.19  4966.4  347.59
  4984.4  339.22  4994.3  332.08  4994.8  331.58  5018.8  332.08  5025.8   338.1
  5036.2  338.82  5156.7  338.95    5202  337.25  5352.1  342.92  5657.1  344.23
  5783.2  351.58  5884.8  355.18    5987  364.37  6194.7     383  6287.2  392.43
  6304.3  391.52  6417.2  398.37  6557.3  402.43  6819.1  401.31  6908.7  401.67
#Mann= 11 ,-1 , 0
  2475.6     .04       0  2747.9     .03       0  2822.8     .04       0
  3809.3    .035       0  4844.1     .12       0  4994.3     .05       0
  5018.8     .12       0    5987     .05       0  6194.7     .03       0
  6304.3     .05       0  6819.1     .03       0
Bank Sta=4994.3,5018.8
XS Rating Curve= 0 ,0
Exp/Cntr=0.3,0.1

Type RM Length L Ch R = 1 ,374861  ,495,495,495
BEGIN DESCRIPTION:
Mapping XS 1e27d64b
END DESCRIPTION:
XS GIS Cut Line= 3
      2418103.11     13560667.84      2416918.07      13559759.9
      2415809.85     13559453.37
#Sta/Elev= 30
  3559.1  351.62  3987.2  346.18  4324.8  345.68  4579.2  342.21  4687.1  343.74
  4829.1  342.09  4921.9  336.04  4957.3  336.91  4992.9  334.37  5036.2  336.02
  5038.4  329.64  5038.9  329.14    5063  329.64  5085.1   333.4  5090.3  337.96
  5096.7  339.58  5117.4  340.19  5124.6  344.67  5138.2  345.98  5158.9  346.25
  5169.3  339.76  5203.6  340.52  5231.5  345.86  5237.9   350.6  5335.3  354.14
  5577.7  373.92  5730.8   383.8  5960.3  390.69  6060.4  391.47  6201.8  397.86
#Mann= 6 ,-1 , 0
  3559.1    .035       0  4324.8     .12       0  5038.4     .05       0
    5063     .12       0  5577.7     .05       0  5960.3     .12       0
Bank Sta=5038.4,5063
XS Rating Curve= 0 ,0
Exp/Cntr=0.3,0.1

Type RM Length L Ch R = 1 ,374366  ,776,776,776
BEGIN DESCRIPTION:
Mapping XS 8b7106e2
END DESCRIPTION:
XS GIS Cut Line= 3
      2418344.76      13560520.4      2417778.82     13559883.71
      2416593.84     13558834.32
#Sta/Elev= 30
  3430.6  350.85  3575.8  351.36  3922.8  345.15  4519.7  342.93  4709.4  341.46
  4801.4  337.19  4872.5  337.63  4901.7  335.44  4964.5  335.21  4971.1  334.03
    4973  327.61  4973.5  327.11  4997.7  327.61  4999.6  332.26  5007.1  334.82
  5035.6  337.16  5063.1  341.89  5070.7  340.93  5077.4  342.89  5084.9  342.34
  5091.6  344.11  5148.5  347.63  5155.8  345.82  5176.9  346.15  5432.2   360.1
  5583.3  372.26  5649.6  376.73  5757.4  383.97  5803.2  384.96  5865.3  387.23
#Mann= 9 ,-1 , 0
  3430.6    .035       0  4519.7     .04       0  4901.7     .05       0
    4973     .05       0  4997.7     .05       0  5432.2     .12       0
  5583.3     .05       0  5649.6     .12       0  5803.2     .05       0
Bank Sta=4973,4997.7
XS Rating Curve= 0 ,0
Exp/Cntr=0.3,0.1

Type RM Length L Ch R = 1 ,373590  ,480,480,480
BEGIN DESCRIPTION:
Mapping XS 764eff85
END DESCRIPTION:
XS GIS Cut Line= 4
      2418433.23     13560467.37      2418238.67      13559624.3
      2417531.21     13558881.47      2417131.07     13558669.63
#Sta/Elev= 30
  3607.7  350.28  3794.8  349.69  4174.6  344.02  4461.9  341.25  4807.5  341.41
  4920.6  340.65  4944.5  339.28  4948.9  339.04  4955.8  336.01  4963.1  336.53
    4970  328.64  4971.8  325.36  4972.3  324.86  4996.6  325.36  5005.6  325.63
  5012.5   329.7  5019.7  329.52  5026.6  333.13  5090.5  333.27  5161.3   340.4
  5238.9  341.18  5344.9  344.84  5583.3  358.84    5633  363.48  5691.6   366.8
  5709.1  368.31  5737.3  370.97  5847.4  375.82  5937.9  374.67  5951.5   374.5
#Mann= 8 ,-1 , 0
  3607.7    .035       0  4807.5     .05       0  4944.5      .1       0
  4971.8     .04       0  4996.6      .1       0  5691.6     .05       0
  5709.1     .04       0  5937.9     .05       0
Bank Sta=4971.8,4996.6
XS Rating Curve= 0 ,0
Exp/Cntr=0.3,0.1

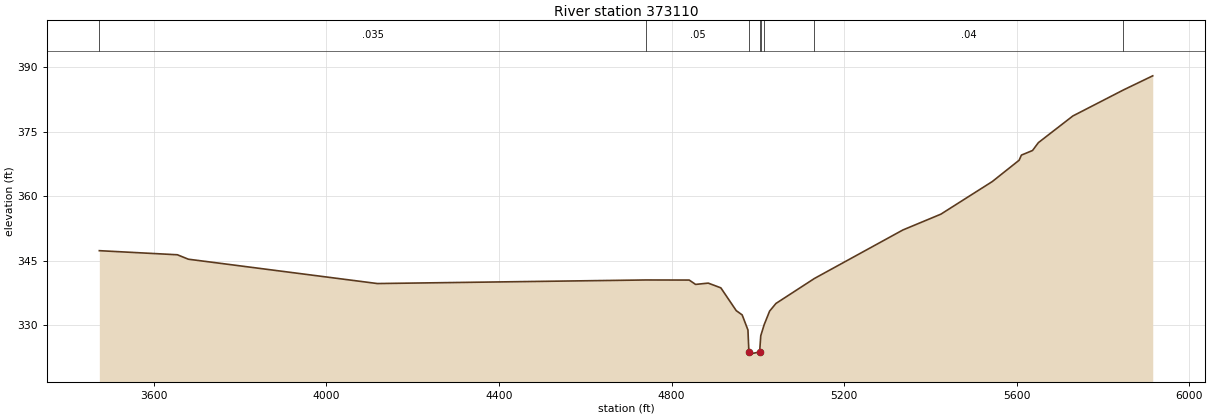
Type RM Length L Ch R = 1 ,373110  ,544,544,544
BEGIN DESCRIPTION:
Mapping XS 538bb9ed
END DESCRIPTION:
XS GIS Cut Line= 4
      2418775.16     13560284.58      2418692.63     13559612.51
      2418002.85     13558663.33      2417444.53     13558469.39
#Sta/Elev= 30
  3473.8  347.36  3654.7  346.41  3680.1  345.38  4118.2  339.73  4740.4  340.56
    4841  340.54  4855.7  339.53  4885.1  339.83  4914.3  338.73    4950  333.44
  4963.7  332.45  4977.1  328.95  4979.3  323.85  4979.8  323.35  5004.2  323.85
  5006.8  327.61  5014.6  330.15  5027.3  333.33    5042  335.11  5131.2  340.91
  5336.1  352.16  5424.2  355.83  5543.4   363.4  5605.6  368.35  5610.9  369.54
  5636.7  370.61  5650.2  372.43  5730.1  378.62  5847.5  384.67  5915.3  387.94
#Mann= 8 ,-1 , 0
  3473.8    .035       0  4740.4     .05       0  4979.3     .05       0
  5004.2     .05       0  5006.8      .1       0  5014.6     .05       0
  5131.2     .04       0  5847.5    .013       0
Bank Sta=4979.3,5004.2
XS Rating Curve= 0 ,0
Exp/Cntr=0.3,0.1