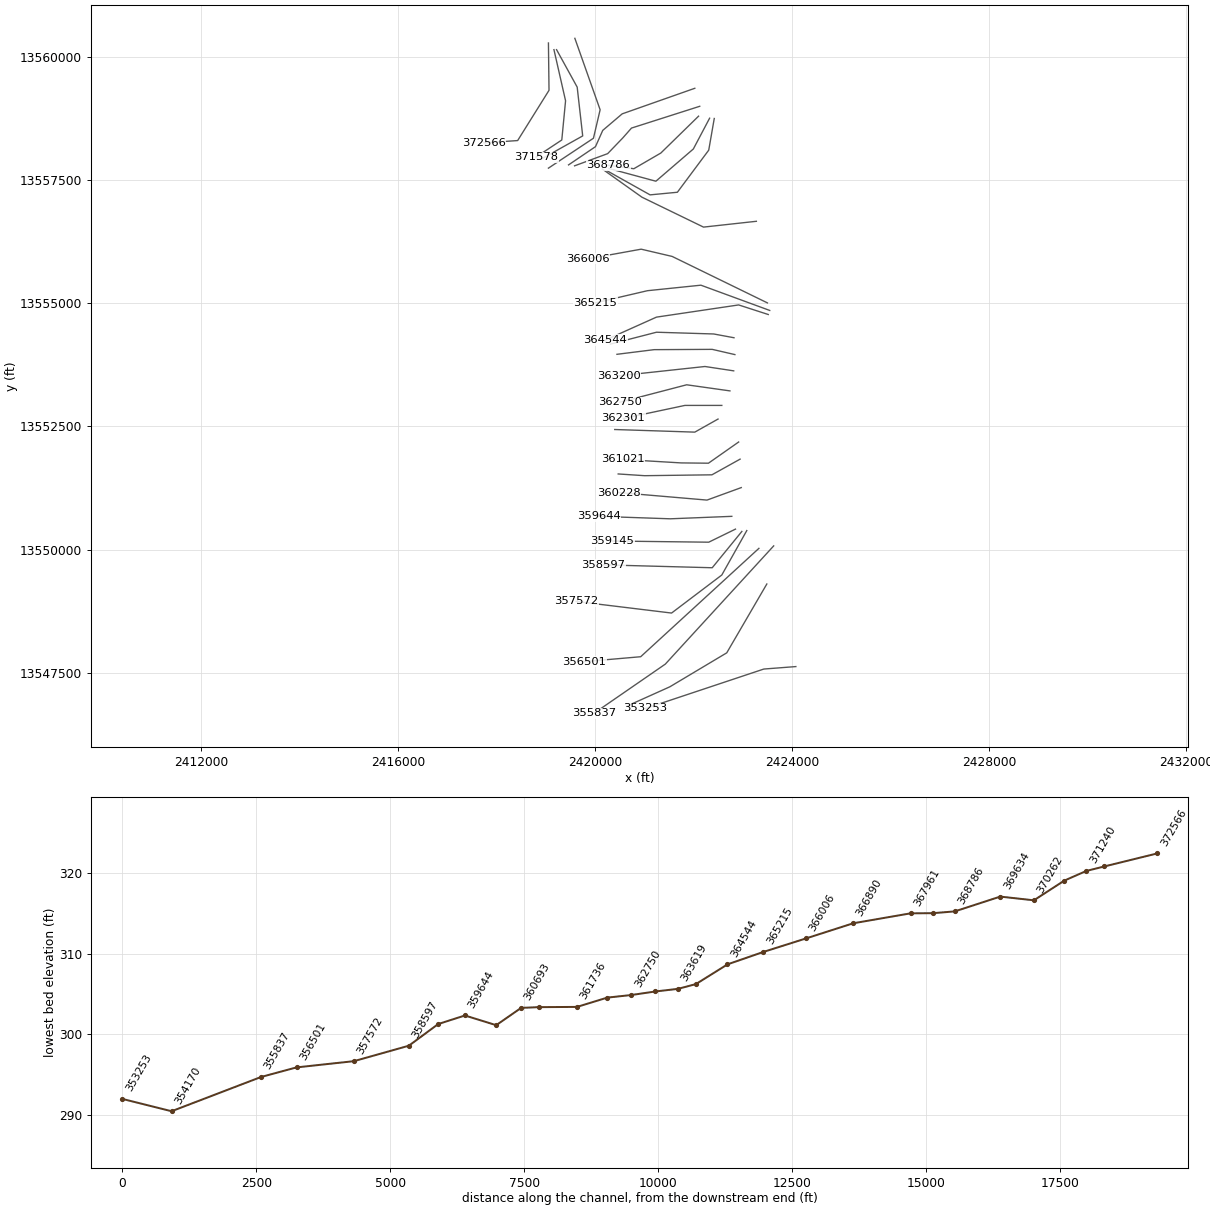
HEC-RAS study COLETO CREEK.prj: COLETO CREEK Base Level Engineering

--- COLETO CREEK.g01 (geometry) --- (continued)

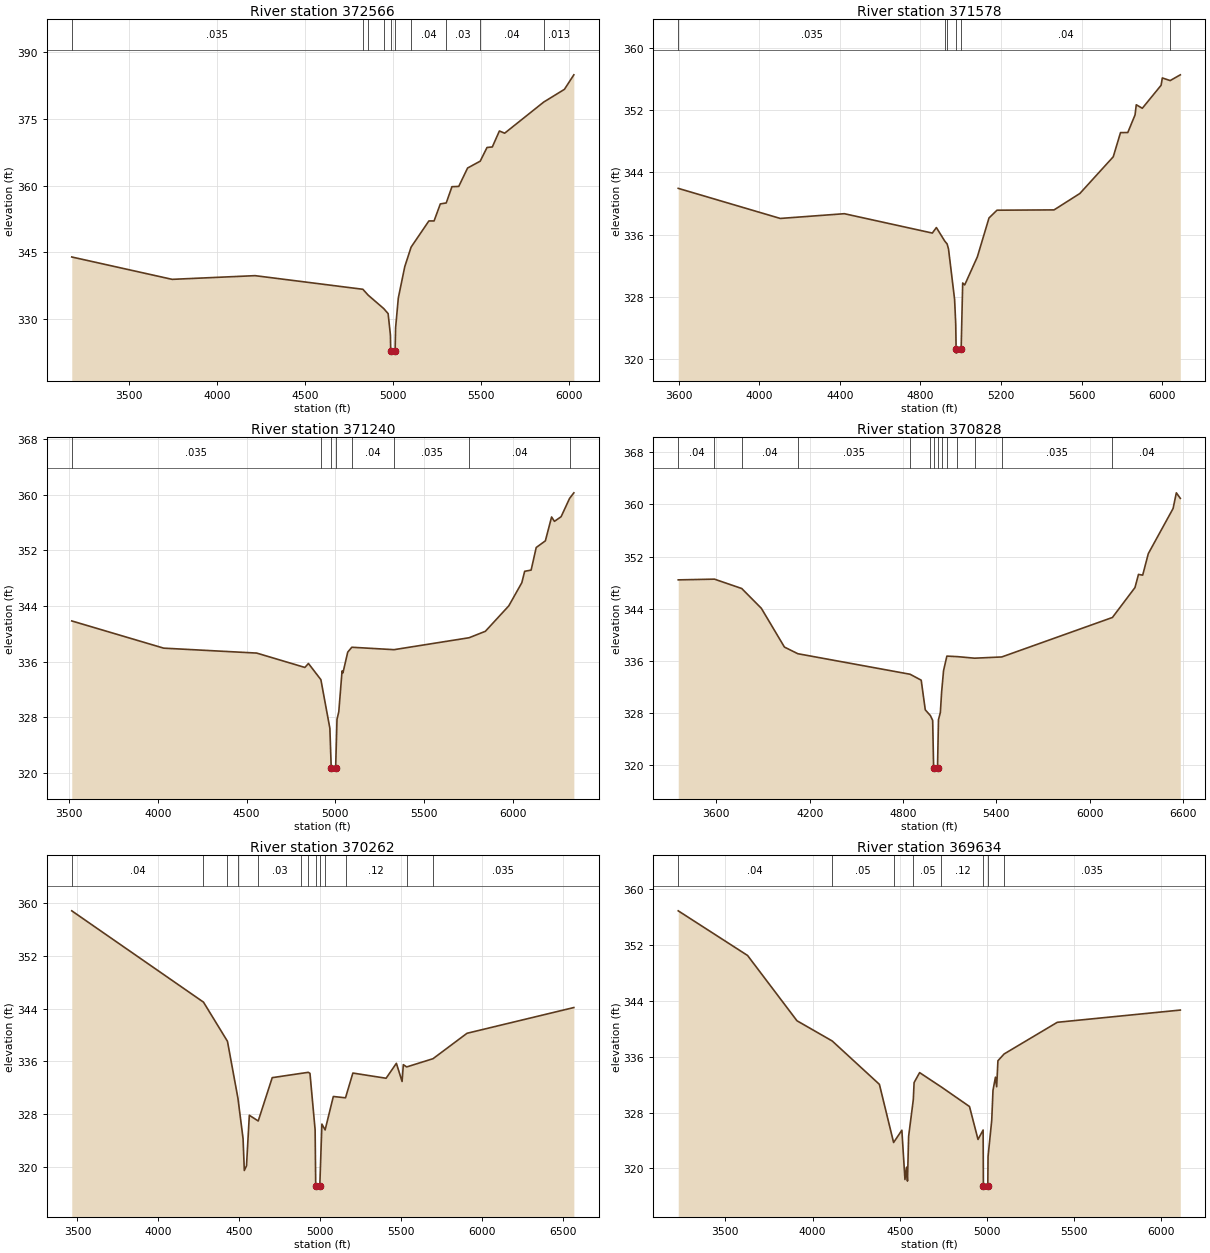
Type RM Length L Ch R = 1 ,372566  ,988,988,988
BEGIN DESCRIPTION:
Mapping XS acab9259
END DESCRIPTION:
XS GIS Cut Line= 4
      2419052.26     13560284.64      2419064.05     13559323.63
      2418427.33      13558303.7      2417743.49     13558256.54
#Sta/Elev= 30
  3176.9  343.96  3746.6  338.94  4217.1  339.77  4828.7  336.71  4858.6   335.4
    4947  332.38    4972  331.25  4985.1  326.39  4986.7  322.88  4987.2  322.38
  5011.6  322.88  5014.4  328.06  5029.8  334.75  5066.4  341.79  5102.3  346.17
  5203.2  352.05  5232.7  352.05  5268.1  355.87  5301.7  356.09  5334.1  359.74
  5372.7   359.8  5422.9  363.93  5494.5  365.47  5533.1  368.54  5563.2  368.66
  5603.3  372.24  5633.4  371.75  5854.6  378.73  5972.3  381.59  6025.8  384.85
#Mann= 10 ,-1 , 0
  3176.9    .035       0  4828.7     .05       0  4858.6     .04       0
    4947     .12       0  4986.7     .05       0  5011.6     .12       0
  5102.3     .04       0  5301.7     .03       0  5494.5     .04       0
  5854.6    .013       0
Bank Sta=4986.7,5011.6
XS Rating Curve= 0 ,0
Exp/Cntr=0.3,0.1

Type RM Length L Ch R = 1 ,371578  ,338,338,338
BEGIN DESCRIPTION:
Mapping XS 5c0a5378
END DESCRIPTION:
XS GIS Cut Line= 4
      2419164.27     13560149.02      2419400.09     13559111.39
      2419323.45     13558315.49      2418799.41      13557968.1
#Sta/Elev= 30
    3598  341.96  4104.6  338.09  4422.5   338.7  4859.4  336.21  4879.5  336.92
    4921  335.18  4932.8  334.81  4939.8  334.15  4969.9  327.69  4975.5  324.55
  4977.5  321.27    4978  320.77  5002.4  321.27  5010.1  329.79  5020.1  329.54
  5082.9  333.15  5140.7  338.15  5180.3  339.15  5463.7  339.19  5591.8   341.3
  5757.5  346.02  5793.6  349.13  5829.7  349.14  5865.8  351.41  5871.8  352.71
  5901.8  352.26  5995.1  355.22  6001.1  356.16    6040  355.82  6090.4  356.56
#Mann= 6 ,-1 , 0
    3598    .035       0    4921     .12       0  4932.8     .04       0
  4977.5     .04       0  5002.4     .04       0    6040     .03       0
Bank Sta=4977.5,5002.4
XS Rating Curve= 0 ,0
Exp/Cntr=0.3,0.1

Type RM Length L Ch R = 1 ,371240  ,412,412,412
BEGIN DESCRIPTION:
Mapping XS 8a41d7e4
END DESCRIPTION:
XS GIS Cut Line= 4
      2419217.35     13560148.97      2419635.92     13559388.48
      2419747.93     13558398.03      2418904.83     13557926.37
#Sta/Elev= 30
  3514.3  341.85  4032.5  337.93    4557  337.22  4828.7  335.15  4848.8  335.72
  4918.9  333.39  4969.6  326.38  4977.2  320.71  4977.7  320.21  5002.2  320.71
  5009.8  327.67  5019.9  328.77  5038.3  334.64  5043.3  334.37  5070.2  337.35
  5093.3  338.06  5330.9  337.71  5754.7  339.43  5846.4  340.36  5978.3  344.02
  6051.9  347.36  6067.9     349  6104.4  349.18    6133  352.43  6184.6  353.39
  6219.8  356.83  6235.8   356.2  6273.4  356.87    6321   359.5  6345.2  360.31
#Mann= 8 ,-1 , 0
  3514.3    .035       0  4918.9     .12       0  4977.2     .05       0
  5002.2     .12       0  5093.3     .04       0  5330.9    .035       0
  5754.7     .04       0    6321     .03       0
Bank Sta=4977.2,5002.2
XS Rating Curve= 0 ,0
Exp/Cntr=0.3,0.1

Type RM Length L Ch R = 1 ,370828  ,566,566,566
BEGIN DESCRIPTION:
Mapping XS 4af71248
END DESCRIPTION:
XS GIS Cut Line= 4
      2419588.75     13560378.94      2420101.66     13558928.63
      2419966.07     13558350.87      2419052.23     13557743.61
#Sta/Elev= 30
  3354.8  348.41    3588  348.52  3763.3  347.08  3889.3  344.04  4037.8  338.08
  4123.6  337.06  4846.2   333.9  4917.4  332.99  4943.6  328.43  4976.7  327.54
  4991.2  326.81  4997.3  319.51  4997.8  319.01  5022.3  319.51  5028.5  326.92
  5040.7  328.04  5048.7  331.15  5061.2  334.47  5082.5  336.69  5150.7  336.61
  5260.5  336.37  5435.6  336.56  6147.2  342.63  6292.3  347.23  6314.8  349.25
  6341.9  349.14  6377.9  352.44  6537.3  359.38  6558.3  361.79  6583.8  360.94
#Mann= 14 ,-1 , 0
  3354.8     .04       0    3588     .05       0  3763.3     .04       0
  4123.6    .035       0  4846.2     .12       0  4976.7      .1       0
  4997.3     .05       0  5022.3      .1       0  5048.7     .12       0
  5082.5      .1       0  5150.7     .05       0  5260.5     .04       0
  5435.6    .035       0  6147.2     .04       0
Bank Sta=4997.3,5022.3
XS Rating Curve= 0 ,0
Exp/Cntr=0.3,0.1

Type RM Length L Ch R = 1 ,370262  ,628,628,628
BEGIN DESCRIPTION:
Mapping XS a1001127
END DESCRIPTION:
XS GIS Cut Line= 5
      2422023.64     13559364.91      2420549.73     13558846.09
      2420154.72     13558510.05      2420007.34      13558179.9
      2419460.68     13557809.58
#Sta/Elev= 30
  3464.7  358.85  4278.8  344.98    4427  339.03  4491.7  330.38  4523.4  324.25
  4531.1  319.41  4544.6  320.12  4562.1   327.8    4617  326.93  4703.6  333.51
  4884.4  334.17  4926.7  334.32  4936.9  334.16  4968.7  325.59  4972.4  317.08
  4972.9  316.58  4997.6  317.08  5010.6  326.46  5030.5  325.57  5081.2  330.65
  5156.5  330.45    5202  334.21  5407.3  333.42    5471  335.69  5506.2  332.93
  5513.9  335.48  5534.6  335.14  5697.3  336.39  5907.4  340.25  6567.7  344.16
#Mann= 13 ,-1 , 0
  3464.7     .04       0  4278.8     .05       0    4427     .12       0
  4491.7     .05       0    4617     .03       0  4884.4     .05       0
  4926.7     .12       0  4972.4     .05       0  4997.6     .12       0
  5030.5      .1       0  5156.5     .12       0  5534.6     .05       0
  5697.3    .035       0
Bank Sta=4972.4,4997.6
XS Rating Curve= 0 ,0
Exp/Cntr=0.3,0.1

Type RM Length L Ch R = 1 ,369634  ,848,848,848
BEGIN DESCRIPTION:
Mapping XS c5457596
END DESCRIPTION:
XS GIS Cut Line= 5
      2422123.84     13558999.38      2420738.38     13558557.21
      2420561.52     13558356.76      2420254.95      13558038.4
       2419582.9     13557790.81
#Sta/Elev= 30
  3229.8  356.86  3627.6  350.47  3910.9  341.13  4113.4  338.23  4383.7  332.03
  4465.1  323.71  4512.5  325.47  4530.2  318.41  4539.4  320.18  4544.7  318.19
  4551.2  324.58  4578.1  329.84  4582.7  332.29  4614.3  333.71  4739.7  331.64
  4900.4  328.86  4949.3  324.15  4978.6   325.5  4980.1  317.54  4980.6  317.04
  5005.4  317.54  5006.9  321.69    5028   326.9  5035.2  331.18  5049.3  333.06
  5056.3  331.69  5063.5  335.41    5099  336.38    5404  340.91  6109.6  342.66
#Mann= 8 ,-1 , 0
  3229.8     .04       0  4113.4     .05       0  4465.1     .12       0
  4578.1     .05       0  4739.7     .12       0  4980.1     .05       0
  5005.4     .12       0    5099    .035       0
Bank Sta=4980.1,5005.4
XS Rating Curve= 0 ,0
Exp/Cntr=0.3,0.1

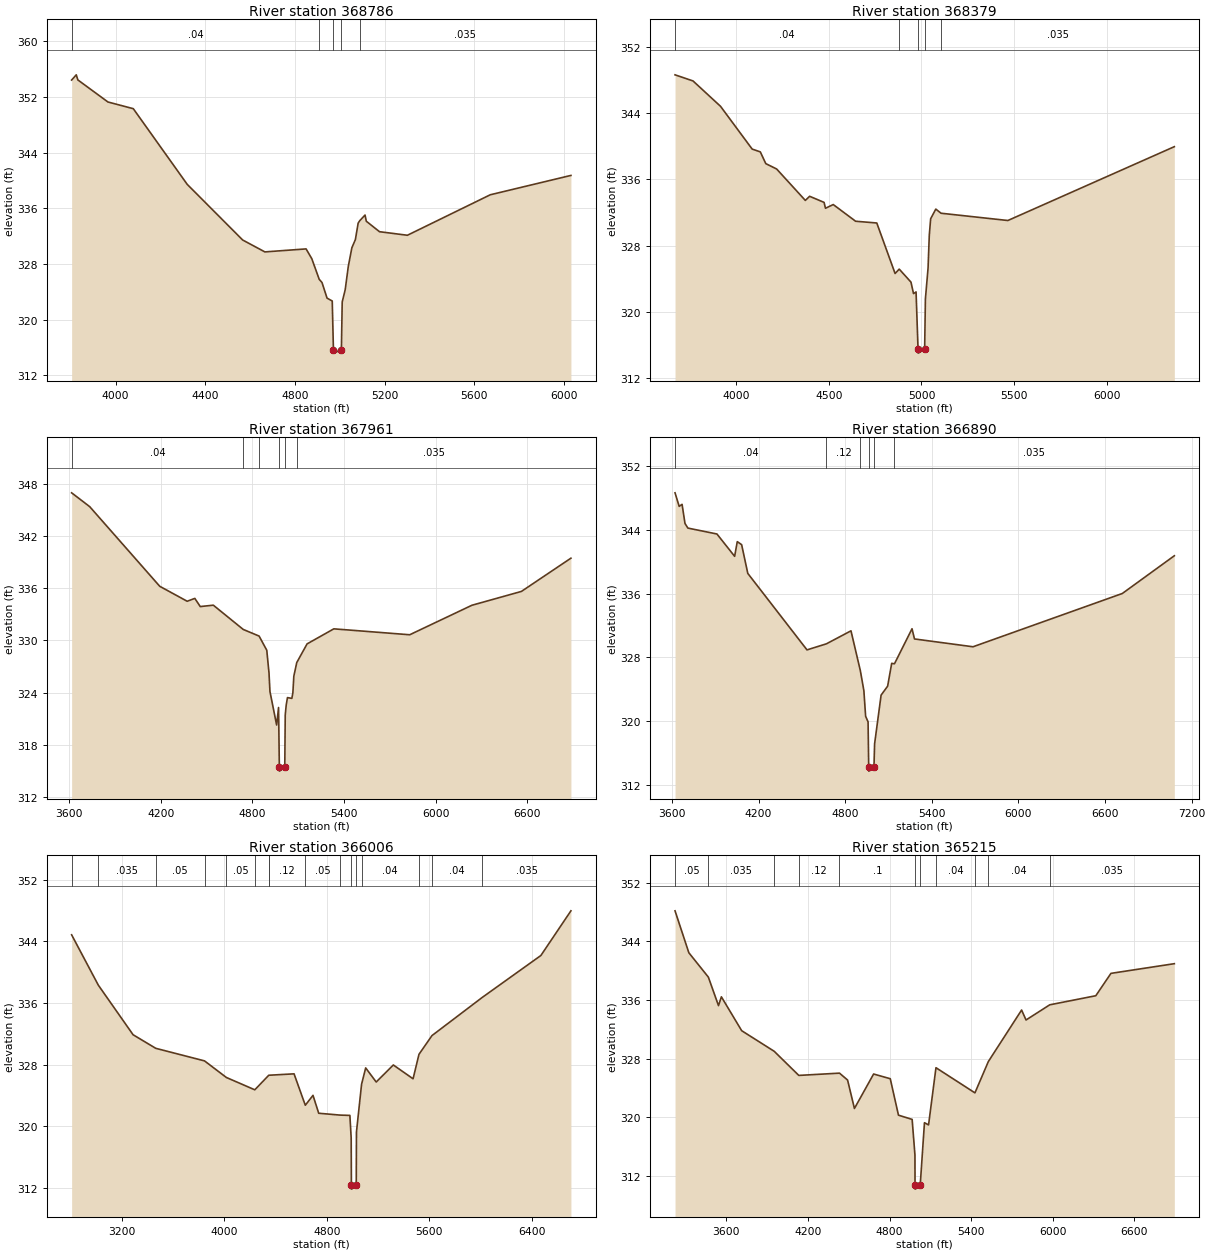
Type RM Length L Ch R = 1 ,368786  ,407,407,407
BEGIN DESCRIPTION:
Mapping XS b71d9f9d
END DESCRIPTION:
XS GIS Cut Line= 4
      2422100.23      13558798.9      2421333.83     13558050.19
      2420785.55     13557731.83      2420268.36     13557802.36
#Sta/Elev= 30
  3804.1  354.41  3824.8  355.16  3831.8  354.43  3966.1  351.26  4079.2   350.3
  4319.7  339.44  4567.1  331.45  4666.2  329.74    4850  330.17  4875.5  328.77
  4908.5  325.81    4921  325.35  4943.5  323.11  4966.7  322.69    4972  315.71
  4972.8  315.21  5007.5  315.71  5011.2  322.56  5024.5  324.31  5038.5  327.69
  5054.3  330.34    5070  331.51  5082.3  333.87  5089.4  334.22    5113  335.03
  5118.8  334.14  5177.6  332.64    5302  332.13  5671.6  337.94  6031.5  340.72
#Mann= 5 ,-1 , 0
  3804.1     .04       0  4908.5      .1       0    4972     .05       0
  5007.5      .1       0  5089.4    .035       0
Bank Sta=4972,5007.5
XS Rating Curve= 0 ,0
Exp/Cntr=0.3,0.1

Type RM Length L Ch R = 1 ,368379  ,418,418,418
BEGIN DESCRIPTION:
Mapping XS 7a53e8f3
END DESCRIPTION:
XS GIS Cut Line= 4
       2422324.3     13558757.69      2421994.13     13558132.73
      2421233.61     13557478.33      2420285.24     13557734.93
#Sta/Elev= 30
  3671.2  348.65  3768.2  347.91  3916.6  344.84  4087.1  339.67  4131.1  339.33
  4160.6  337.91  4219.2  337.26  4373.9  333.46  4397.1  333.96    4475  333.22
  4482.4  332.51  4524.4  332.96  4645.1  330.94  4759.2  330.73  4857.9  324.62
  4880.2  325.15  4943.5  323.58  4957.3  322.19    4971  322.39  4981.7  315.49
  4982.5  314.99  5017.3  315.49  5021.4  321.55  5035.7  325.27  5042.3  329.23
  5049.7  331.24  5077.4  332.41  5105.7  331.91  5466.1  331.03  6363.8  339.96
#Mann= 5 ,-1 , 0
  3671.2     .04       0  4880.2      .1       0  4981.7     .05       0
  5017.3      .1       0  5105.7    .035       0
Bank Sta=4981.7,5017.3
XS Rating Curve= 0 ,0
Exp/Cntr=0.3,0.1

Type RM Length L Ch R = 1 ,367961  ,1071,1071,1071
BEGIN DESCRIPTION:
Mapping XS dc4ecb46
END DESCRIPTION:
XS GIS Cut Line= 5
      2422418.61     13558751.73       2422306.6     13558109.15
      2421669.88      13557254.3       2421115.7     13557201.24
      2420246.05     13557687.97
#Sta/Elev= 30
  3615.8  346.95  3734.3  345.36  4193.1  336.21    4373  334.49  4422.9  334.82
  4458.7  333.88  4544.2  334.04  4740.3  331.25  4844.2  330.49  4894.5  328.86
  4909.1  326.24  4915.3  324.12    4959  320.27  4971.6  322.28  4976.8  315.47
  4977.6  314.97  5012.4  315.47  5015.4  321.42  5021.7  322.55    5030  323.42
  5058.8  323.33  5065.5  323.98  5071.7  325.88    5091  327.45  5158.5  329.59
  5333.9  331.32  5831.1  330.64  6238.6  334.03  6562.9  335.62  6887.3  339.44
#Mann= 6 ,-1 , 0
  3615.8     .04       0  4740.3     .03       0  4844.2      .1       0
  4976.8     .05       0  5012.4      .1       0    5091    .035       0
Bank Sta=4976.8,5012.4
XS Rating Curve= 0 ,0
Exp/Cntr=0.3,0.1

Type RM Length L Ch R = 1 ,366890  ,884,884,884
BEGIN DESCRIPTION:
Mapping XS ec2e75a9
END DESCRIPTION:
XS GIS Cut Line= 4
      2423273.51     13556664.75      2422200.48     13556546.83
      2420950.62     13557154.07      2420144.26     13557727.13
#Sta/Elev= 30
  3621.3  348.63    3650  346.93  3670.1  347.19  3690.2  344.79  3710.3  344.21
  3911.5  343.47  4034.1  340.67  4052.4  342.51  4082.6  342.13  4125.2  338.53
  4535.3  328.94  4669.9   329.7    4840  331.33    4905  326.32  4929.2  323.84
  4941.4  320.62  4958.4  319.91  4962.7  314.24  4963.6  313.74  4999.2  314.24
  5003.5  317.15  5048.6  323.27  5093.8  324.39  5121.9  327.25  5141.3   327.2
  5262.8  331.59  5279.8  330.31  5685.2  329.33  6719.4  336.01  7079.6  340.74
#Mann= 6 ,-1 , 0
  3621.3     .04       0  4669.9     .12       0    4905      .1       0
  4962.7     .05       0  4999.2      .1       0  5141.3    .035       0
Bank Sta=4962.7,4999.2
XS Rating Curve= 0 ,0
Exp/Cntr=0.3,0.1

Type RM Length L Ch R = 1 ,366006  ,791,791,791
BEGIN DESCRIPTION:
Mapping XS be17c3b3
END DESCRIPTION:
XS GIS Cut Line= 4
      2423497.46     13555008.11      2421563.76     13555951.38
      2420934.97     13556098.77      2419854.59     13555903.05
#Sta/Elev= 30
  2809.1  344.84  3017.4  338.31  3288.6  331.88  3465.5  330.12  3845.9  328.49
  4016.2  326.34  4238.2  324.74  4346.7  326.62  4349.1  326.63  4544.4  326.81
  4632.1  322.74  4692.2  324.02  4736.7   321.7    4904  321.46  4979.9  321.42
  4990.1  318.47  4991.7  312.36  4992.7  311.86  5029.6  312.36  5031.2  319.26
  5071.1  325.46  5103.1  327.58  5185.3  325.75  5318.8  327.96  5472.9  326.17
    5519  329.34  5620.3  331.77    6011   336.7  6470.2  342.16  6704.4  347.95
#Mann= 16 ,-1 , 0
  2809.1     .05       0  3017.4    .035       0  3465.5     .05       0
  3845.9     .12       0  4016.2     .05       0  4238.2     .12       0
  4346.7     .05       0  4349.1     .12       0  4632.1     .05       0
    4904      .1       0  4991.7     .05       0  5029.6      .1       0
  5071.1     .04       0    5519    .013       0  5620.3     .04       0
    6011    .035       0
Bank Sta=4991.7,5029.6
XS Rating Curve= 0 ,0
Exp/Cntr=0.3,0.1

Type RM Length L Ch R = 1 ,365215  ,671,671,671
BEGIN DESCRIPTION:
Mapping XS 8eb0821a
END DESCRIPTION:
XS GIS Cut Line= 4
       2423544.7      13554854.8      2422147.42     13555367.72
      2421062.64     13555255.71      2420001.44     13555008.09
#Sta/Elev= 30
    3224  348.16  3325.5  342.44  3468.8  339.12  3543.3  335.23  3564.6  336.43
  3713.7  331.81  3952.7     329  4133.4  325.71  4432.4  326.02  4491.8  325.08
  4542.1   321.2  4683.1   325.9  4805.4  325.26  4865.7  320.29  4966.2  319.71
  4986.8  314.85  4987.4   310.7  4988.4   310.2  5025.4   310.7  5056.7  319.26
  5086.8  318.96  5141.3  326.76  5427.6  323.33  5526.1   327.6  5770.5  334.63
    5803  333.27  5977.3  335.34  6315.7  336.58    6427  339.63  6892.7  340.95
#Mann= 11 ,-1 , 0
    3224     .05       0  3468.8    .035       0  3952.7     .05       0
  4133.4     .12       0  4432.4      .1       0  4987.4     .05       0
  5025.4      .1       0  5141.3     .04       0  5427.6    .013       0
  5526.1     .04       0  5977.3    .035       0
Bank Sta=4987.4,5025.4
XS Rating Curve= 0 ,0
Exp/Cntr=0.3,0.1

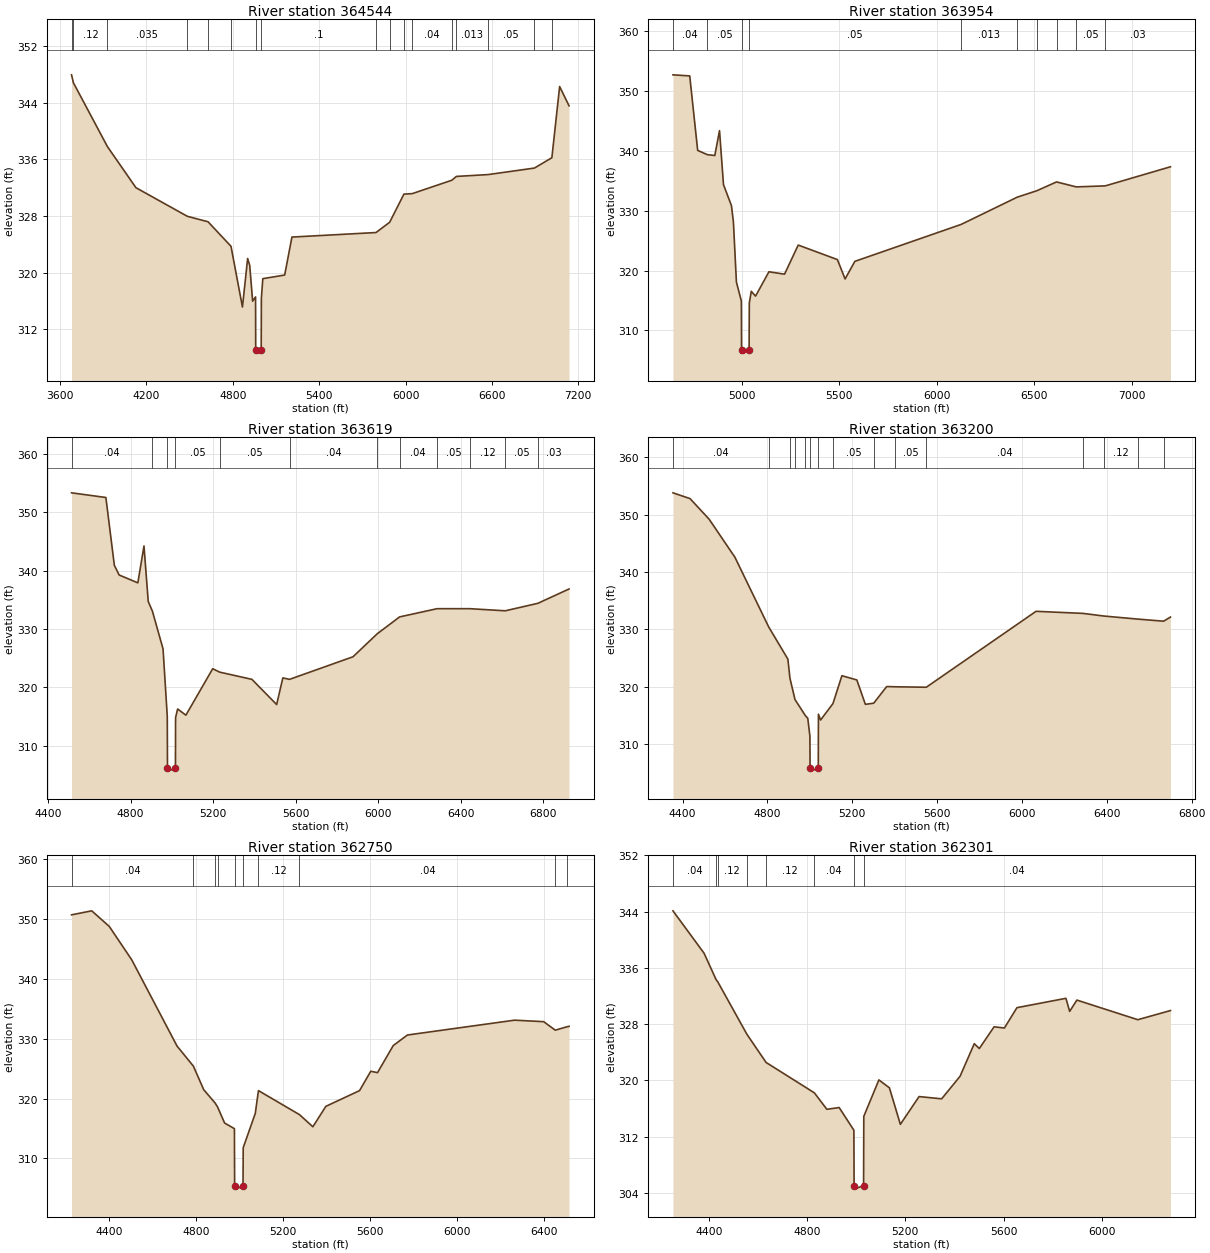
Type RM Length L Ch R = 1 ,364544  ,590,590,590
BEGIN DESCRIPTION:
Mapping XS 95d5a159
END DESCRIPTION:
XS GIS Cut Line= 4
      2423515.18     13554772.27      2422913.84     13554966.82
       2421245.4     13554719.21      2420208.88     13554253.95
#Sta/Elev= 30
  3680.7  347.94  3693.4  346.83  3929.6  337.82  4127.9  332.01  4485.1  327.97
  4628.7   327.2    4788  323.74  4867.6  315.17  4903.6  322.02  4918.1  321.05
  4938.3     316  4958.6  316.59  4959.7  309.16  4960.7  308.66  4997.8  309.16
    4999  316.42  5009.1  319.17  5160.8  319.68  5211.3  325.04  5795.1  325.68
  5889.9  327.13  5988.9   331.1  6046.5  331.17  6321.4  333.06  6353.3   333.6
  6573.5  333.86  6895.4  334.78  7016.4  336.24  7070.3  346.29  7135.6  343.57
#Mann= 17 ,-1 , 0
  3680.7     .05       0  3693.4     .12       0  3929.6    .035       0
  4485.1     .05       0  4628.7     .12       0    4788      .1       0
  4959.7     .04       0  4997.8      .1       0  5795.1    .013       0
  5889.9     .05       0  5988.9     .03       0  6046.5     .04       0
  6321.4     .03       0  6353.3    .013       0  6573.5     .05       0
  6895.4     .12       0  7016.4     .03       0
Bank Sta=4959.7,4997.8
XS Rating Curve= 0 ,0
Exp/Cntr=0.3,0.1

Type RM Length L Ch R = 1 ,363954  ,335,335,335
BEGIN DESCRIPTION:
Mapping XS 4c9182d2
END DESCRIPTION:
XS GIS Cut Line= 4
       2422819.5     13554300.63      2422406.82     13554377.27
       2421245.4     13554412.64      2420309.02     13554171.19
#Sta/Elev= 30
  4648.4  352.71  4734.3  352.53    4775  340.09    4824  339.38  4862.7  339.23
  4886.9  343.39  4907.2  334.37  4947.9  330.87  4958.1  328.13  4973.5  318.08
  4998.8  314.92  4999.9  306.72  5000.9  306.22  5038.4  306.72  5039.5  314.59
  5049.6  316.55  5071.5  315.74    5140  319.81    5220  319.41  5290.1  324.27
  5490.7  321.85  5530.2  318.61  5580.2  321.55  6125.5  327.73  6411.9  332.27
  6512.7  333.35  6613.5  334.82  6714.3  333.99  6863.2  334.16  7197.1  337.35
#Mann= 10 ,-1 , 0
  4648.4     .04       0    4824     .05       0  4999.9     .05       0
  5038.4     .05       0  6125.5    .013       0  6411.9     .04       0
  6512.7     .05       0  6613.5     .04       0  6714.3     .05       0
  6863.2     .03       0
Bank Sta=4999.9,5038.4
XS Rating Curve= 0 ,0
Exp/Cntr=0.3,0.1

Type RM Length L Ch R = 1 ,363619  ,419,419,419
BEGIN DESCRIPTION:
Mapping XS 18a91910
END DESCRIPTION:
XS GIS Cut Line= 4
      2422837.24     13553958.68      2422377.34     13554064.81
      2421198.24     13554058.91      2420443.62     13553964.58
#Sta/Elev= 30
    4514  353.33  4680.5  352.53  4721.6   340.9  4744.7  339.25  4835.4   337.9
  4865.2  344.22  4885.8   334.7  4905.9  333.06  4957.6  326.58  4978.1     315
  4979.1  306.13  4980.1  305.63  5017.6  306.13  5018.3  314.81  5028.3  316.28
  5068.3  315.22  5198.3  323.18  5231.9   322.6  5388.3  321.36  5508.3  317.04
  5538.3  321.61  5570.9  321.36  5878.3  325.23  5995.8  329.17  6104.1  332.06
  6285.6  333.47  6445.5  333.47  6616.5  333.11  6774.4  334.39  6925.6  336.85
#Mann= 12 ,-1 , 0
    4514     .04       0  4905.9     .05       0  4979.1     .05       0
  5017.6     .05       0  5231.9     .05       0  5570.9     .04       0
  5995.8     .05       0  6104.1     .04       0  6285.6     .05       0
  6445.5     .12       0  6616.5     .05       0  6774.4     .03       0
Bank Sta=4979.1,5017.6
XS Rating Curve= 0 ,0
Exp/Cntr=0.3,0.1

Type RM Length L Ch R = 1 ,363200  ,450,450,450
BEGIN DESCRIPTION:
Mapping XS fca3792d
END DESCRIPTION:
XS GIS Cut Line= 3
      2422813.65     13553628.53      2422229.96     13553716.97
      2420484.87     13553528.31
#Sta/Elev= 30
  4354.5  353.81  4435.1   352.8  4525.1  349.21  4646.4   342.6  4806.1  330.42
  4896.3  324.83    4906  321.51  4929.8  317.79  4978.8  314.98  4990.1  314.52
  5000.1  311.41  5000.9  305.81  5001.9  305.31  5039.5  305.81  5040.4  315.23
  5050.4  314.22  5108.8  317.08    5151  321.94  5221.4   321.2  5261.6  316.95
    5301  317.15  5362.2  320.05  5399.6  320.01  5548.9  319.93  6066.3  333.16
  6287.1   332.8  6385.7  332.34  6547.4   331.8  6667.8  331.44  6700.1  332.16
#Mann= 15 ,-1 , 0
  4354.5     .04       0  4806.1     .05       0    4906     .12       0
  4929.8      .1       0  4978.8     .12       0  5000.9     .05       0
  5039.5     .12       0  5108.8     .05       0    5301     .12       0
  5399.6     .05       0  5548.9     .04       0  6287.1     .05       0
  6385.7     .12       0  6547.4     .05       0  6667.8     .12       0
Bank Sta=5000.9,5039.5
XS Rating Curve= 0 ,0
Exp/Cntr=0.3,0.1

Type RM Length L Ch R = 1 ,362750  ,449,449,449
BEGIN DESCRIPTION:
Mapping XS 54cb9bbd
END DESCRIPTION:
XS GIS Cut Line= 3
      2422737.01     13553221.74      2421858.54     13553345.55
      2420502.57     13552991.82
#Sta/Elev= 30
  4227.2   350.7  4320.1  351.37  4400.9  348.76  4504.2  343.18  4712.6  328.77
  4787.9  325.41  4835.2  321.49  4887.6  319.26  4898.9  318.61  4931.2  315.92
  4976.5  314.97  4977.4  305.37  4978.4  304.87    5016  305.37  5016.9   311.8
  5072.5  317.53    5087  321.33  5275.6  317.32  5337.3  315.29    5397   318.7
  5552.1  321.33  5603.7  324.57  5634.7  324.33  5707.1  328.86  5772.2  330.62
  6265.2   333.1  6399.2  332.85  6452.4  331.43  6508.6  332.02  6515.7  332.07
#Mann= 10 ,-1 , 0
  4227.2     .04       0  4787.9     .05       0  4887.6      .1       0
  4898.9     .12       0  4977.4     .05       0    5016     .12       0
    5087     .12       0  5275.6     .04       0  6452.4     .05       0
  6508.6     .12       0
Bank Sta=4977.4,5016
XS Rating Curve= 0 ,0
Exp/Cntr=0.3,0.1

Type RM Length L Ch R = 1 ,362301  ,565,565,565
BEGIN DESCRIPTION:
Mapping XS f37995bb
END DESCRIPTION:
XS GIS Cut Line= 3
      2422571.88     13552926.97      2421823.16     13552926.97
      2420573.33     13552661.67
#Sta/Elev= 30
  4253.5  344.12  4380.4  338.08  4428.9  334.36  4436.2  334.01  4554.5  326.58
  4632.8  322.56  4829.5  318.24  4880.4   315.9  4930.4  316.15  4990.4  312.93
  4991.3  305.05  4992.3  304.55  5029.9  305.05  5030.8   314.9  5092.3  320.08
  5135.2  318.95  5179.7  313.76  5255.9  317.71  5347.9  317.39  5422.8  320.59
  5480.8  325.23  5501.3  324.54  5561.5  327.63  5603.5  327.46  5654.6  330.35
  5854.2  331.68  5869.3  329.82  5898.7  331.43  6146.9  328.64  6279.9  329.94
#Mann= 8 ,-1 , 0
  4253.5     .04       0  4428.9     .05       0  4436.2     .12       0
  4554.5     .05       0  4632.8     .12       0  4829.5     .04       0
  4991.3     .04       0  5029.9     .04       0
Bank Sta=4991.3,5029.9
XS Rating Curve= 0 ,0
Exp/Cntr=0.3,0.1

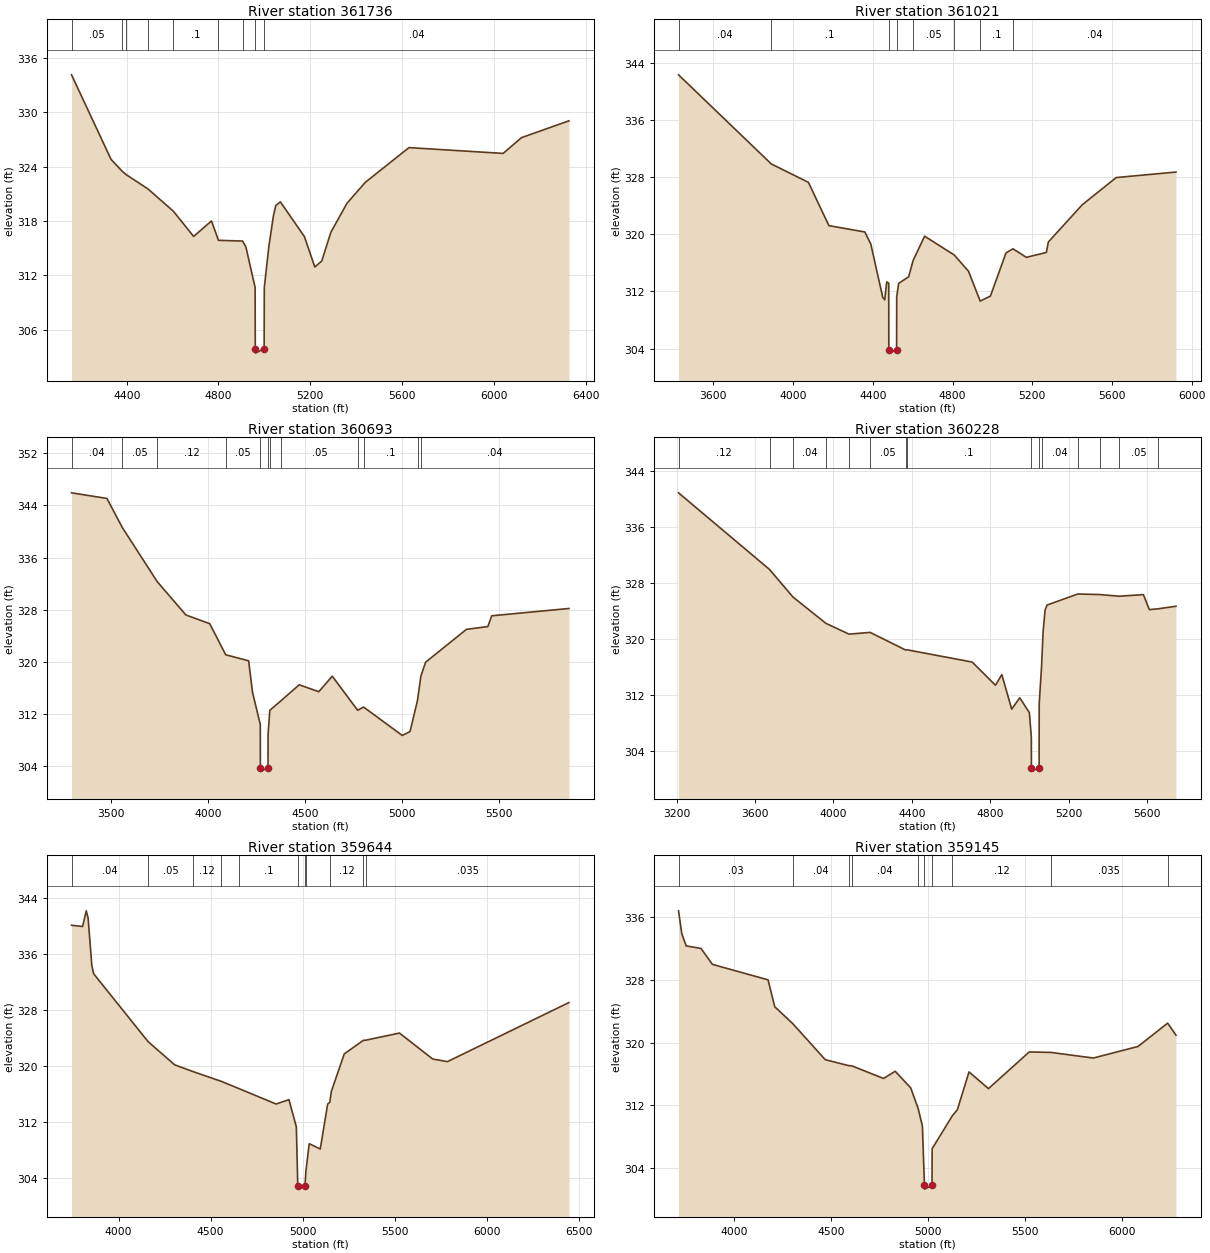
Type RM Length L Ch R = 1 ,361736  ,715,715,715
BEGIN DESCRIPTION:
Mapping XS f8331f9f
END DESCRIPTION:
XS GIS Cut Line= 3
      2422495.28     13552649.89      2422023.61     13552384.58
      2420398.24     13552437.58
#Sta/Elev= 30
  4159.7  334.14  4332.1  324.79  4381.5  323.46  4397.7  323.12  4492.5  321.54
  4603.6  319.07  4691.7  316.29  4769.5     318  4799.9  315.86  4905.1  315.78
  4919.6  315.11  4959.6  310.65  4960.3   303.9  4961.3   303.4  4998.9   303.9
  4999.6  310.65  5019.6  315.21  5039.7  318.61  5049.7   319.7  5069.7  320.11
  5174.4  316.27  5219.7  312.91  5249.8  313.57  5289.8  316.76  5359.8  319.95
  5439.9  322.27    5630   326.1  6040.2  325.46  6120.2   327.2  6327.1  329.06
#Mann= 9 ,-1 , 0
  4159.7     .05       0  4381.5     .12       0  4397.7     .05       0
  4492.5     .12       0  4603.6      .1       0  4799.9     .05       0
  4905.1     .04       0  4960.3     .04       0  4998.9     .04       0
Bank Sta=4960.3,4998.9
XS Rating Curve= 0 ,0
Exp/Cntr=0.3,0.1

Type RM Length L Ch R = 1 ,361021  ,328,328,328
BEGIN DESCRIPTION:
Mapping XS 297a4579
END DESCRIPTION:
XS GIS Cut Line= 4
      2422913.85     13552184.13       2422300.7     13551753.75
      2421746.52     13551759.65      2420555.65     13551830.39
#Sta/Elev= 30
  3425.1   342.3  3890.8  329.83  4076.8  327.26  4179.9   321.2  4359.9  320.32
  4389.9  318.64  4449.9  311.17  4459.9  310.82  4469.9  313.34  4479.9  313.16
  4480.4  303.87  4481.4  303.37  4519.5  303.87  4519.9  311.25  4529.9  313.13
  4579.9  314.05  4602.5  316.34  4659.9  319.73    4809  317.09  4880.2  314.83
  4938.9  310.65  4990.4  311.36  5068.6   317.4  5103.4  317.96  5170.7  316.77
  5270.9  317.45  5280.9  318.91  5451.2  324.13  5621.5  327.93  5921.4   328.7
#Mann= 8 ,-1 , 0
  3425.1     .04       0  3890.8      .1       0  4480.4     .05       0
  4519.5      .1       0  4602.5     .05       0    4809     .12       0
  4938.9      .1       0  5103.4     .04       0
Bank Sta=4480.4,4519.5
XS Rating Curve= 0 ,0
Exp/Cntr=0.3,0.1

Type RM Length L Ch R = 1 ,360693  ,465,465,465
BEGIN DESCRIPTION:
Mapping XS bcbe21f8
END DESCRIPTION:
XS GIS Cut Line= 4
      2422943.28     13551836.27      2422371.45     13551517.93
      2421003.68     13551500.24      2420468.59     13551535.52
#Sta/Elev= 30
  3299.1  345.92  3481.2  345.06  3559.8  340.63  3739.7  332.32  3887.1  327.21
    4010  325.87  4091.9  321.11    4210  320.18    4230  315.36    4270  310.42
  4270.5  303.78  4271.5  303.28  4309.6  303.78    4310  308.95    4319   312.6
  4378.7  314.12  4470.1  316.51    4571  315.45  4640.1  317.83  4770.6  312.61
  4801.6  313.09  5000.1  308.75  5040.1  309.34  5078.6  314.12  5095.9  317.82
  5120.1  319.96  5330.2     325  5440.4  325.43  5460.4  327.08  5857.7   328.2
#Mann= 12 ,-1 , 0
  3299.1     .04       0  3559.8     .05       0  3739.7     .12       0
  4091.9     .05       0  4270.5     .05       0  4309.6     .05       0
    4319      .1       0  4378.7     .05       0  4770.6     .12       0
  4801.6      .1       0  5078.6     .12       0  5095.9     .04       0
Bank Sta=4270.5,4309.6
XS Rating Curve= 0 ,0
Exp/Cntr=0.3,0.1

Type RM Length L Ch R = 1 ,360228  ,584,584,584
BEGIN DESCRIPTION:
Mapping XS a3d1d54a
END DESCRIPTION:
XS GIS Cut Line= 3
      2422966.93     13551258.54      2422271.22     13551005.02
      2420479.53     13551158.26
#Sta/Elev= 30
  3209.2  340.84  3673.5  329.91  3793.5  325.97  3960.9  322.23  4079.2  320.68
  4187.1  320.93  4367.9  318.42  4373.2  318.46  4707.9   316.7  4826.8  313.39
  4859.2  314.91  4909.4  309.98  4950.7   311.6  4999.7  309.48  5009.7  306.01
  5010.2  301.64  5011.2  301.14  5049.4  301.64  5049.9  310.74  5061.7  315.98
    5070   321.1    5080  324.13    5090  324.83    5247  326.41  5358.5  326.33
  5457.4  326.09  5581.8  326.32  5611.9  324.18  5655.3  324.29  5747.9  324.66
#Mann= 15 ,-1 , 0
  3209.2     .12       0  3673.5     .05       0  3793.5     .04       0
  3960.9     .05       0  4079.2     .12       0  4187.1     .05       0
  4367.9     .12       0  4373.2      .1       0  5010.2     .05       0
  5049.4      .1       0  5061.7     .04       0    5247     .05       0
  5358.5     .04       0  5457.4     .05       0  5655.3    .035       0
Bank Sta=5010.2,5049.4
XS Rating Curve= 0 ,0
Exp/Cntr=0.3,0.1

Type RM Length L Ch R = 1 ,359644  ,499,499,499
BEGIN DESCRIPTION:
SALT CREEK 36.0
END DESCRIPTION:
XS GIS Cut Line= 3
      2422774.98       13550675.        2421525.       13550625.
      2420075.04       13550675.
#Sta/Elev= 30
  3744.4  340.09  3804.4  339.92  3824.4  342.16  3834.5  341.11  3854.5  334.35
  3864.5  333.16    4160  323.45  4304.8  320.12  4406.5  319.14  4556.9  317.77
  4655.2  316.71  4855.3  314.52  4925.3  315.14  4965.4  311.25  4973.3  302.84
  4974.3  302.34  5012.5  302.84  5017.4  304.91  5035.4  308.84  5095.4  308.08
  5135.5  314.51    5147  314.76  5155.5  316.31  5225.5  321.68  5328.8  323.62
    5344  323.66  5525.7  324.67  5705.8  320.96  5785.9  320.58  6446.2  329.04
#Mann= 11 ,-1 , 0
  3744.4     .04       0    4160     .05       0  4406.5     .12       0
  4556.9     .05       0  4655.2      .1       0  4973.3     .05       0
  5012.5      .1       0  5017.4      .1       0    5147     .12       0
  5328.8     .05       0    5344    .035       0
Bank Sta=4973.3,5012.5
XS Rating Curve= 0 ,0
Exp/Cntr=0.3,0.1

Type RM Length L Ch R = 1 ,359145  ,548,548,548
BEGIN DESCRIPTION:
Mapping XS 8269f57c
END DESCRIPTION:
XS GIS Cut Line= 3
      2422849.02     13550415.48       2422306.6     13550150.16
      2420349.67     13550173.74
#Sta/Elev= 30
  3714.8  336.84  3731.6  333.92  3754.1  332.36  3830.6  332.03  3889.2     330
  4175.7  328.02  4209.9  324.59  4302.8  322.43  4470.2  317.82  4590.8  317.06
  4607.2  317.03  4770.3  315.42  4830.3  316.34  4910.3  314.21  4948.6  311.56
  4970.3  309.34  4980.7  301.78  4981.7  301.28  5019.9  301.78  5020.3  306.44
  5124.2  310.64  5150.3  311.43  5210.3  316.26  5310.3  314.12  5520.3  318.81
  5631.9  318.75  5850.3  318.03  6080.4  319.51  6232.9  322.49  6275.7  320.95
#Mann= 10 ,-1 , 0
  3714.8     .03       0  4302.8     .04       0  4590.8     .05       0
  4607.2     .04       0  4948.6      .1       0  4980.7     .05       0
  5019.9      .1       0  5124.2     .12       0  5631.9    .035       0
  6232.9     .05       0
Bank Sta=4980.7,5019.9
XS Rating Curve= 0 ,0
Exp/Cntr=0.3,0.1

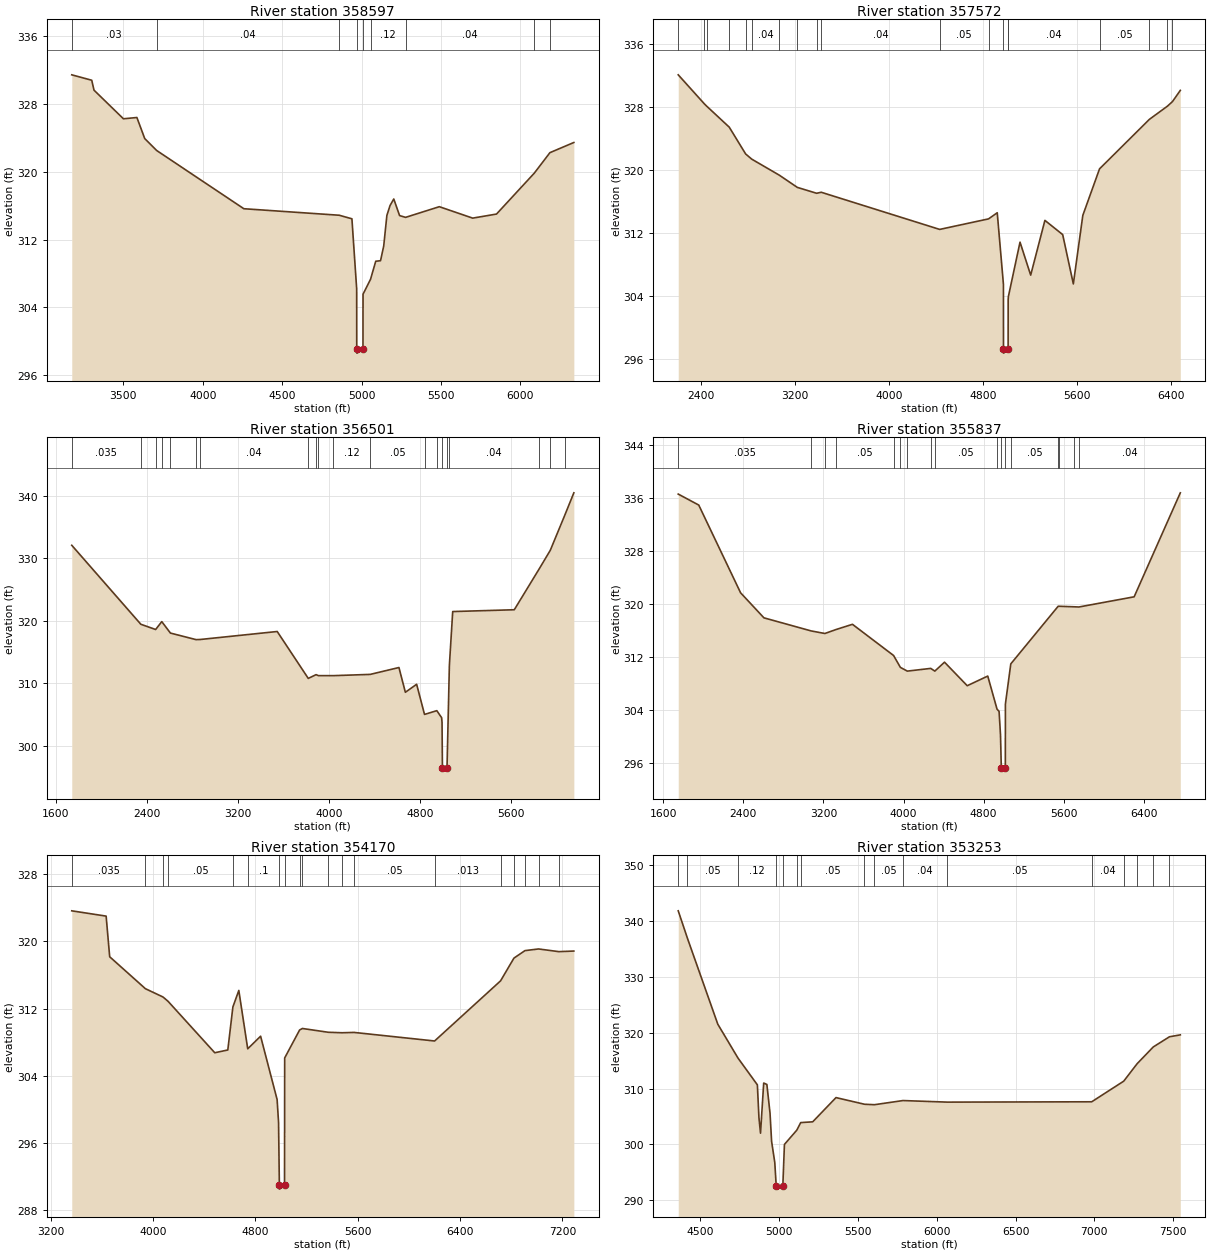
Type RM Length L Ch R = 1 ,358597  ,1025,1025,1025
BEGIN DESCRIPTION:
Mapping XS 0c5dd5ad
END DESCRIPTION:
XS GIS Cut Line= 3
      2422978.69      13550368.3      2422377.34     13549631.36
      2420168.29     13549690.26
#Sta/Elev= 30
  3175.4  331.46  3301.1  330.82  3315.4  329.65  3500.7  326.27  3585.4  326.42
  3634.9  323.93  3709.6  322.53  4258.9  315.65  4859.7  314.88  4939.2  314.46
  4969.2  306.17  4969.6   299.1  4970.6   298.6  5008.8   299.1  5009.2  305.56
  5056.4  307.32  5089.2  309.45  5119.3  309.51  5139.3  311.24  5159.3  314.86
  5179.3  316.03  5202.7   316.8  5239.3  314.84  5277.1  314.63  5489.4  315.89
  5699.5  314.54  5849.5  315.02  6087.4  319.85  6185.8  322.27  6336.4  323.47
#Mann= 9 ,-1 , 0
  3175.4     .03       0  3709.6     .04       0  4859.7      .1       0
  4969.6     .05       0  5008.8      .1       0  5056.4     .12       0
  5277.1     .04       0  6087.4     .05       0  6185.8     .12       0
Bank Sta=4969.6,5008.8
XS Rating Curve= 0 ,0
Exp/Cntr=0.3,0.1

Type RM Length L Ch R = 1 ,357572  ,1071,1071,1071
BEGIN DESCRIPTION:
Mapping XS de04261f
END DESCRIPTION:
XS GIS Cut Line= 4
      2423078.93     13550386.01       2422571.9     13549483.97
      2421551.97     13548711.65      2419612.37     13548947.47
#Sta/Elev= 30
  2208.3  332.12  2430.1  328.43  2450.9  328.12  2641.9  325.46  2781.1  322.05
  2832.8  321.39    3068  319.34  3220.7  317.79  3384.7  317.04  3423.8  317.17
  4430.8  312.44    4846  313.78  4920.1  314.56  4972.7  305.45  4973.2  297.19
  4974.2  296.69  5012.5  297.19    5013  303.47  5014.5  303.87  5113.7  310.82
  5204.4  306.62  5325.3  313.59  5476.4  311.78    5567   305.5  5647.6  314.23
  5789.7  320.15  6213.4  326.45  6366.8  328.13  6409.5  328.71  6476.3  330.14
#Mann= 19 ,-1 , 0
  2208.3     .04       0  2430.1    .013       0  2450.9     .04       0
  2641.9     .03       0  2781.1    .013       0  2832.8     .04       0
    3068    .013       0  3220.7     .04       0  3384.7     .12       0
  3423.8     .04       0  4430.8     .05       0    4846     .12       0
  4973.2     .05       0  5012.5     .12       0  5014.5     .04       0
  5789.7     .05       0  6213.4     .04       0  6366.8     .03       0
  6409.5     .04       0
Bank Sta=4973.2,5012.5
XS Rating Curve= 0 ,0
Exp/Cntr=0.3,0.1

Type RM Length L Ch R = 1 ,356501  ,664,664,664
BEGIN DESCRIPTION:
SALT CREEK 33.0
END DESCRIPTION:
XS GIS Cut Line= 3
      2423325.02     13550025.02        2420925.       13547825.
      2419775.03       13547725.
#Sta/Elev= 30
  1739.6  332.04  2346.3  319.41  2476.3  318.57  2530.2  319.83  2606.3     318
  2831.4  316.95  2866.3  316.97  3544.2  318.25    3817  310.75  3885.6  311.35
  3906.1  311.19  4036.3  311.19  4360.9  311.39  4613.4  312.49  4669.8  308.53
  4768.8  309.81  4838.1  304.99    4946  305.59  4988.3  304.47    4992  303.69
  4995.3  296.42  4996.3  295.92  5035.6  296.42  5056.4  312.82  5085.7  321.44
  5626.5  321.73  5844.2  328.23  5942.6  331.23  6069.7  336.83  6149.7  340.43
#Mann= 20 ,-1 , 0
  1739.6    .035       0  2346.3     .04       0  2476.3    .013       0
  2530.2    .035       0  2606.3     .04       0  2831.4     .12       0
  2866.3     .04       0    3817     .05       0  3885.6     .04       0
  3906.1     .03       0  4036.3     .12       0  4360.9     .05       0
  4838.1     .12       0    4946     .12       0  4995.3     .05       0
  5035.6     .12       0  5056.4     .04       0  5844.2     .05       0
  5942.6     .04       0  6069.7    .013       0
Bank Sta=4995.3,5035.6
XS Rating Curve= 0 ,0
Exp/Cntr=0.3,0.1

Type RM Length L Ch R = 1 ,355837  ,1667,1667,1667
BEGIN DESCRIPTION:
SALT CREEK 32.0
END DESCRIPTION:
XS GIS Cut Line= 3
        2423625.       13550075.        2421425.       13547675.
      2419974.96     13546674.97
#Sta/Elev= 30
  1748.7  336.64  1953.7  334.98  2371.8  321.71  2604.9  317.92  3076.6  315.94
    3214  315.55  3323.6  316.14  3489.7  316.94  3900.7  312.22  3968.8  310.42
    4038  309.86  4272.1  310.27  4312.7  309.86  4409.7  311.21  4636.6  307.65
  4841.7  309.11  4934.6   304.1  4954.8  303.77    4969  300.24  4977.2  295.23
  4978.2  294.73  5017.5  295.23    5018  304.87  5071.9  310.95  5545.3  319.67
  5550.4  319.67  5703.8  319.59  5752.9  319.56  6304.7   321.1  6765.9  336.83
#Mann= 17 ,-1 , 0
  1748.7    .035       0  3076.6     .12       0    3214     .04       0
  3323.6     .05       0  3900.7     .12       0  3968.8     .05       0
    4038     .12       0  4272.1     .03       0  4312.7     .05       0
  4934.6     .12       0  4977.2     .05       0  5017.5     .12       0
  5071.9     .05       0  5545.3    .013       0  5550.4     .04       0
  5703.8     .05       0  5752.9     .04       0
Bank Sta=4977.2,5017.5
XS Rating Curve= 0 ,0
Exp/Cntr=0.3,0.1

Type RM Length L Ch R = 1 ,354170  ,917,917,917
BEGIN DESCRIPTION:
Mapping XS 5c456d8a
END DESCRIPTION:
XS GIS Cut Line= 4
      2423485.73     13549301.25      2422672.12     13547903.96
       2421516.6     13547214.18      2420638.16     13546819.18
#Sta/Elev= 30
  3363.9  323.64  3632.6  323.01  3660.4  318.17  3939.5  314.37  4077.1  313.38
  4116.6  312.87    4482  306.74    4584  307.07  4623.7  312.19    4670  314.16
  4739.7  307.21  4840.4  308.71  4969.5  301.17  4980.8  298.45  4987.1     291
  4988.1   290.5  5027.5     291  5028.7  306.12  5145.5  309.45    5167  309.63
  5369.1  309.18  5477.2  309.12  5571.1  309.16  6200.9  308.14  6716.7   315.3
  6821.4  318.01  6907.4   318.9  7013.9   319.1  7171.7  318.78  7289.7  318.85
#Mann= 19 ,-1 , 0
  3363.9    .035       0  3939.5     .05       0  4077.1    .035       0
  4116.6     .05       0  4623.7     .12       0  4739.7      .1       0
  4987.1     .05       0  5027.5      .1       0  5145.5     .12       0
    5167    .013       0  5369.1     .05       0  5477.2    .013       0
  5571.1     .05       0  6200.9    .013       0  6716.7     .03       0
  6821.4    .013       0  6907.4     .04       0  7013.9     .05       0
  7171.7     .04       0
Bank Sta=4987.1,5027.5
XS Rating Curve= 0 ,0
Exp/Cntr=0.3,0.1

Type RM Length L Ch R = 1 ,353253  ,561,561,561
BEGIN DESCRIPTION:
SALT CREEK 30.0
END DESCRIPTION:
XS GIS Cut Line= 3
      2424075.01       13547625.        2423425.       13547575.
      2421025.05     13546775.02
#Sta/Elev= 30
  4362.7  341.76    4421  336.86  4613.4   321.5  4741.5  315.44  4864.2  310.66
  4874.2  304.77  4884.2  302.02  4904.3  310.98  4924.4  310.73  4944.4   305.6
  4954.4  300.55  4974.5  296.79  4983.8  292.52  4984.8  292.02  5025.4  292.52
  5035.7  300.01  5114.1  302.56  5138.8  303.91  5214.9  304.05  5362.5  308.38
    5543  307.19  5606.4  307.11  5787.1  307.85  6067.6  307.57  6982.9  307.63
    7186  311.32  7270.3  314.42    7373  317.43  7475.6  319.25  7544.4  319.59
#Mann= 16 ,-1 , 0
  4362.7     .12       0    4421     .05       0  4741.5     .12       0
  4983.8     .05       0  5025.4     .12       0  5114.1      .1       0
  5138.8     .05       0    5543     .04       0  5606.4     .05       0
  5787.1     .04       0  6067.6     .05       0  6982.9     .04       0
    7186     .03       0  7270.3     .04       0    7373     .03       0
  7475.6    .013       0
Bank Sta=4983.8,5025.4
XS Rating Curve= 0 ,0
Exp/Cntr=0.3,0.1