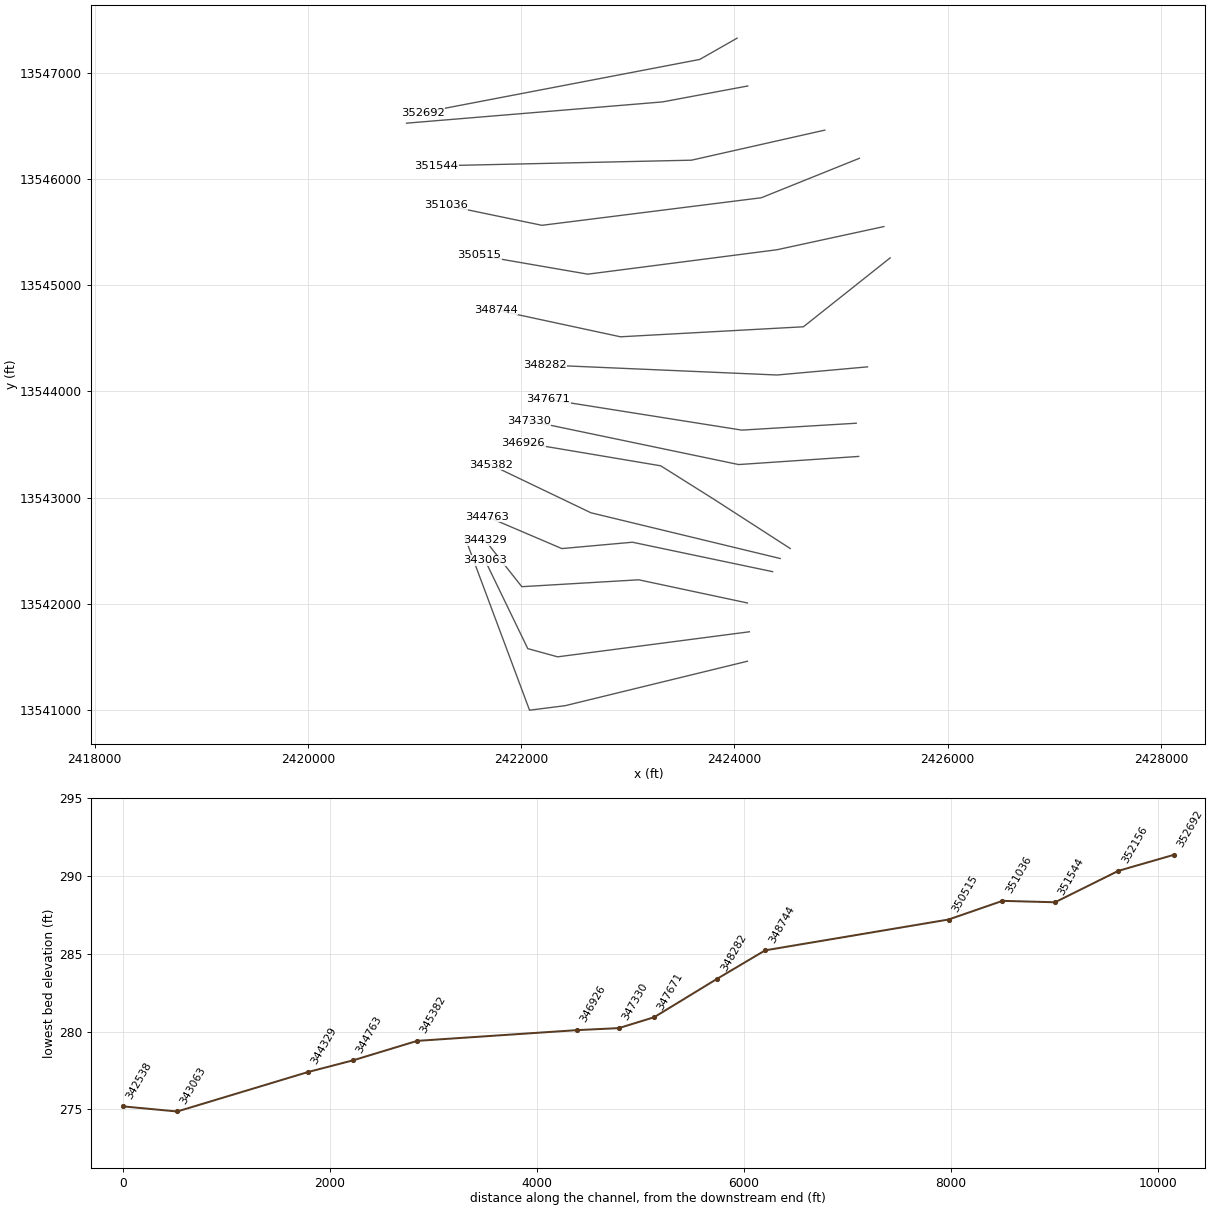
HEC-RAS study COLETO CREEK.prj: COLETO CREEK Base Level Engineering

--- COLETO CREEK.g01 (geometry) --- (continued)

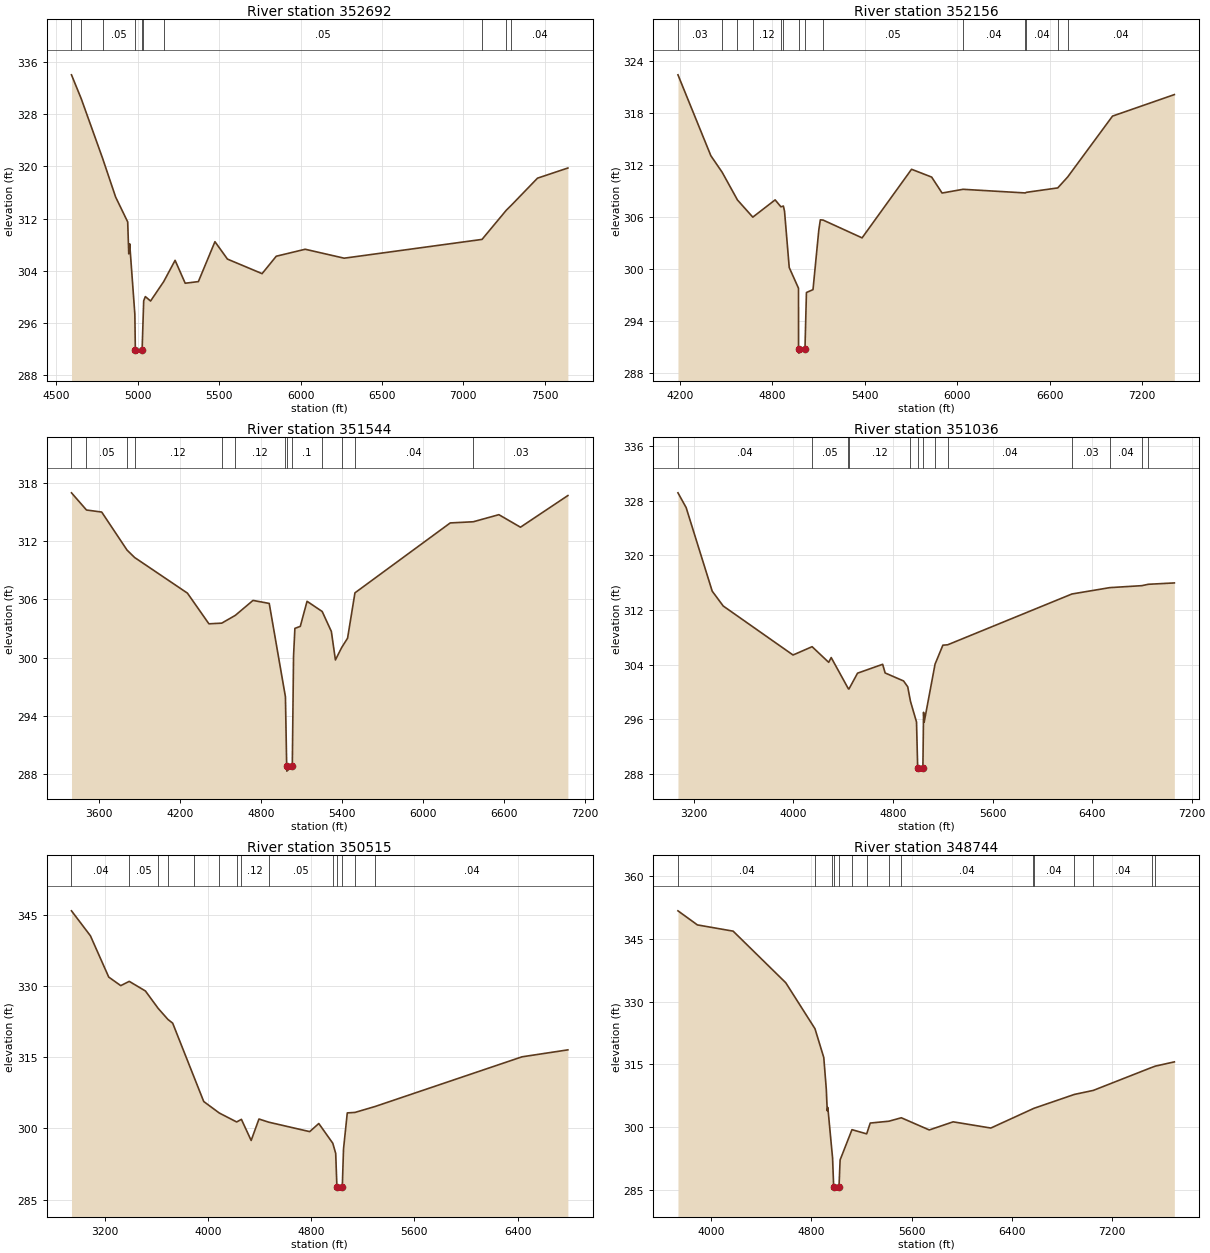
Type RM Length L Ch R = 1 ,352692  ,536,536,536
BEGIN DESCRIPTION:
SALT CREEK 29.0
END DESCRIPTION:
XS GIS Cut Line= 3
      2424024.97     13547324.98        2423675.       13547125.
      2421075.02       13546625.
#Sta/Elev= 30
  4592.2  334.05  4652.4  330.37  4783.5  321.24  4863.5  315.31  4937.7  311.49
  4944.2  306.59  4949.9  308.14  4981.6  297.35  4984.7  291.87  4985.7  291.37
  5026.3  291.87    5033  297.07    5036   299.4  5046.2  300.04  5078.3  299.36
  5159.4  302.36    5229   305.6  5291.1  302.09  5372.1  302.34  5473.9  308.46
  5550.8  305.79  5763.6  303.56  5850.7  306.23  6028.4   307.3  6268.2  305.93
  7115.3  308.81  7264.9   313.3  7295.1  314.04  7456.1   318.2  7642.9  319.76
#Mann= 10 ,-1 , 0
  4592.2     .05       0  4652.4     .04       0  4783.5     .05       0
  4984.7     .05       0  5026.3     .05       0    5033      .1       0
  5159.4     .05       0  7115.3     .04       0  7264.9     .03       0
  7295.1     .04       0
Bank Sta=4984.7,5026.3
XS Rating Curve= 0 ,0
Exp/Cntr=0.3,0.1

Type RM Length L Ch R = 1 ,352156  ,612,612,612
BEGIN DESCRIPTION:
SALT CREEK 28.0
END DESCRIPTION:
XS GIS Cut Line= 3
      2424124.97     13546874.99        2423325.       13546725.
      2420925.02       13546525.
#Sta/Elev= 30
  4186.5  322.43  4400.1   313.1  4473.3   311.2  4572.8     308  4672.3  306.02
  4817.3  308.01  4854.9  307.21  4870.9   307.3  4878.3   306.7  4908.8  300.21
    4969  297.82  4969.4  290.84  4970.4  290.34    5011  290.84  5020.5  297.33
  5063.1  297.66  5100.8  304.53  5110.8  305.71  5128.9  305.68  5381.7  303.63
  5702.8  311.54  5833.3  310.64    5901   308.8  6037.2  309.23  6441.6  308.81
  6447.9  308.88  6651.8  309.39  6716.2  310.65  7007.3  317.67  7408.7  320.15
#Mann= 14 ,-1 , 0
  4186.5     .03       0  4473.3     .04       0  4572.8     .05       0
  4672.3     .12       0  4854.9     .05       0  4870.9     .12       0
  4969.4     .05       0    5011     .12       0  5128.9     .05       0
  6037.2     .04       0  6441.6     .03       0  6447.9     .04       0
  6651.8     .05       0  6716.2     .04       0
Bank Sta=4969.4,5011
XS Rating Curve= 0 ,0
Exp/Cntr=0.3,0.1

Type RM Length L Ch R = 1 ,351544  ,508,508,508
BEGIN DESCRIPTION:
Mapping XS 6bba9572
END DESCRIPTION:
XS GIS Cut Line= 3
      2424847.58     13546459.56      2423597.72     13546176.57
      2421204.11     13546123.51
#Sta/Elev= 30
  3395.7  316.98  3506.8  315.21  3619.5     315  3807.3  311.08  3863.2  310.32
  4254.3  306.65  4413.4  303.49  4508.5  303.56  4608.7  304.36  4739.9   305.9
    4860  305.59    4980  295.97  4989.2  288.82  4990.2  288.32  5030.8  288.82
    5040  300.15    5050  303.02    5090  303.23    5140  305.81  5252.1  304.76
  5320.1   302.7  5350.1  299.77  5396.4  301.05  5440.1  302.01  5494.7  306.68
  6200.3  313.88  6370.9     314  6560.4  314.73  6720.4  313.44  7071.4   316.7
#Mann= 13 ,-1 , 0
  3395.7     .04       0  3506.8     .05       0  3807.3     .04       0
  3863.2     .12       0  4508.5     .05       0  4608.7     .12       0
    4980      .1       0  4989.2     .05       0  5030.8      .1       0
  5252.1     .12       0  5396.4     .05       0  5494.7     .04       0
  6370.9     .03       0
Bank Sta=4989.2,5030.8
XS Rating Curve= 0 ,0
Exp/Cntr=0.3,0.1

Type RM Length L Ch R = 1 ,351036  ,521,521,521
BEGIN DESCRIPTION:
Mapping XS 90a35867
END DESCRIPTION:
XS GIS Cut Line= 4
      2425171.82     13546194.25      2424252.13     13545822.84
      2422194.58     13545563.43      2421292.59     13545752.08
#Sta/Elev= 30
  3073.4  329.18  3139.1  327.02  3348.4  314.78    3437   312.6  3997.8  305.42
  4150.9  306.64  4284.1  304.35  4304.3  305.05  4442.6  300.46  4446.9  300.44
  4515.9  302.76  4717.5  304.06  4737.7  302.79  4885.6  301.62  4919.1  300.76
    4941  298.64  4989.6  295.61  4998.9  288.91  4999.9  288.41  5040.8  288.91
  5046.2  297.03  5051.2  295.59  5138.5  304.08  5201.3  306.86  5240.4  306.92
  6237.9  314.36  6541.5  315.29  6799.5  315.58  6851.3  315.78  7060.6  315.98
#Mann= 13 ,-1 , 0
  3073.4     .04       0  4150.9     .05       0  4442.6      .1       0
  4446.9     .12       0    4941     .05       0  4998.9     .05       0
  5040.8     .05       0  5138.5     .05       0  5240.4     .04       0
  6237.9     .03       0  6541.5     .04       0  6799.5     .03       0
  6851.3     .04       0
Bank Sta=4998.9,5040.8
XS Rating Curve= 0 ,0
Exp/Cntr=0.3,0.1

Type RM Length L Ch R = 1 ,350515  ,1771,1771,1771
BEGIN DESCRIPTION:
Mapping XS 3426b589
END DESCRIPTION:
XS GIS Cut Line= 4
      2425401.71     13545551.63      2424399.52     13545333.51
      2422624.96     13545103.58      2421606.31     13545280.22
#Sta/Elev= 30
  2941.4  345.92  3088.3  340.65  3230.4  331.94  3323.5  330.14  3389.3  331.04
  3514.8  329.01  3613.8  325.33  3689.3  323.01  3726.1  322.22  3889.4     311
  3966.8  305.69  4087.9  303.26  4222.1  301.38  4258.9  301.93  4334.6  297.48
  4395.1     302  4471.3  301.33  4788.4  299.34    4859  301.05  4967.5  296.89
  4990.1  294.75  4999.4  287.71  5000.4  287.21  5041.3  287.71  5050.6  295.65
  5079.8  303.29  5139.4  303.39  5296.5  304.65  6434.6  315.12  6790.3  316.59
#Mann= 14 ,-1 , 0
  2941.4     .04       0  3389.3     .05       0  3613.8     .04       0
  3689.3     .12       0  3889.4     .05       0  4087.9     .12       0
  4222.1      .1       0  4258.9     .12       0  4471.3     .05       0
  4967.5     .12       0  4999.4     .05       0  5041.3     .12       0
  5139.4     .05       0  5296.5     .04       0
Bank Sta=4999.4,5041.3
XS Rating Curve= 0 ,0
Exp/Cntr=0.3,0.1

Type RM Length L Ch R = 1 ,348744  ,462,462,462
BEGIN DESCRIPTION:
Mapping XS 6c6c88bf
END DESCRIPTION:
XS GIS Cut Line= 4
      2425460.74     13545256.89      2424647.13     13544608.35
      2422931.53     13544514.02      2421759.14     13544767.35
#Sta/Elev= 30
  3737.1  351.65    3892  348.29  4177.1   346.8  4596.6  334.49  4829.6  323.52
  4899.9  316.64  4919.9  309.08  4927.3  303.93  4932.3   304.7  4962.5  295.01
    4970  292.68  4978.8  285.73  4979.8  285.23  5021.2  285.73  5030.1   292.2
  5124.6  299.42  5241.9  298.42  5270.4     301  5419.6  301.44    5518  302.26
  5741.1  299.35  5931.4  301.29  6231.9  299.81  6566.2  304.39  6574.8  304.51
  6897.8  307.83  7048.7  308.79  7513.8  314.26  7544.2  314.59  7695.2   315.6
#Mann= 15 ,-1 , 0
  3737.1     .04       0  4829.6     .12       0  4962.5     .05       0
  4978.8     .05       0  5021.2     .05       0  5124.6      .1       0
  5241.9     .12       0  5419.6     .05       0    5518     .04       0
  6566.2     .05       0  6574.8     .04       0  6897.8    .013       0
  7048.7     .04       0  7513.8    .013       0  7544.2     .04       0
Bank Sta=4978.8,5021.2
XS Rating Curve= 0 ,0
Exp/Cntr=0.3,0.1

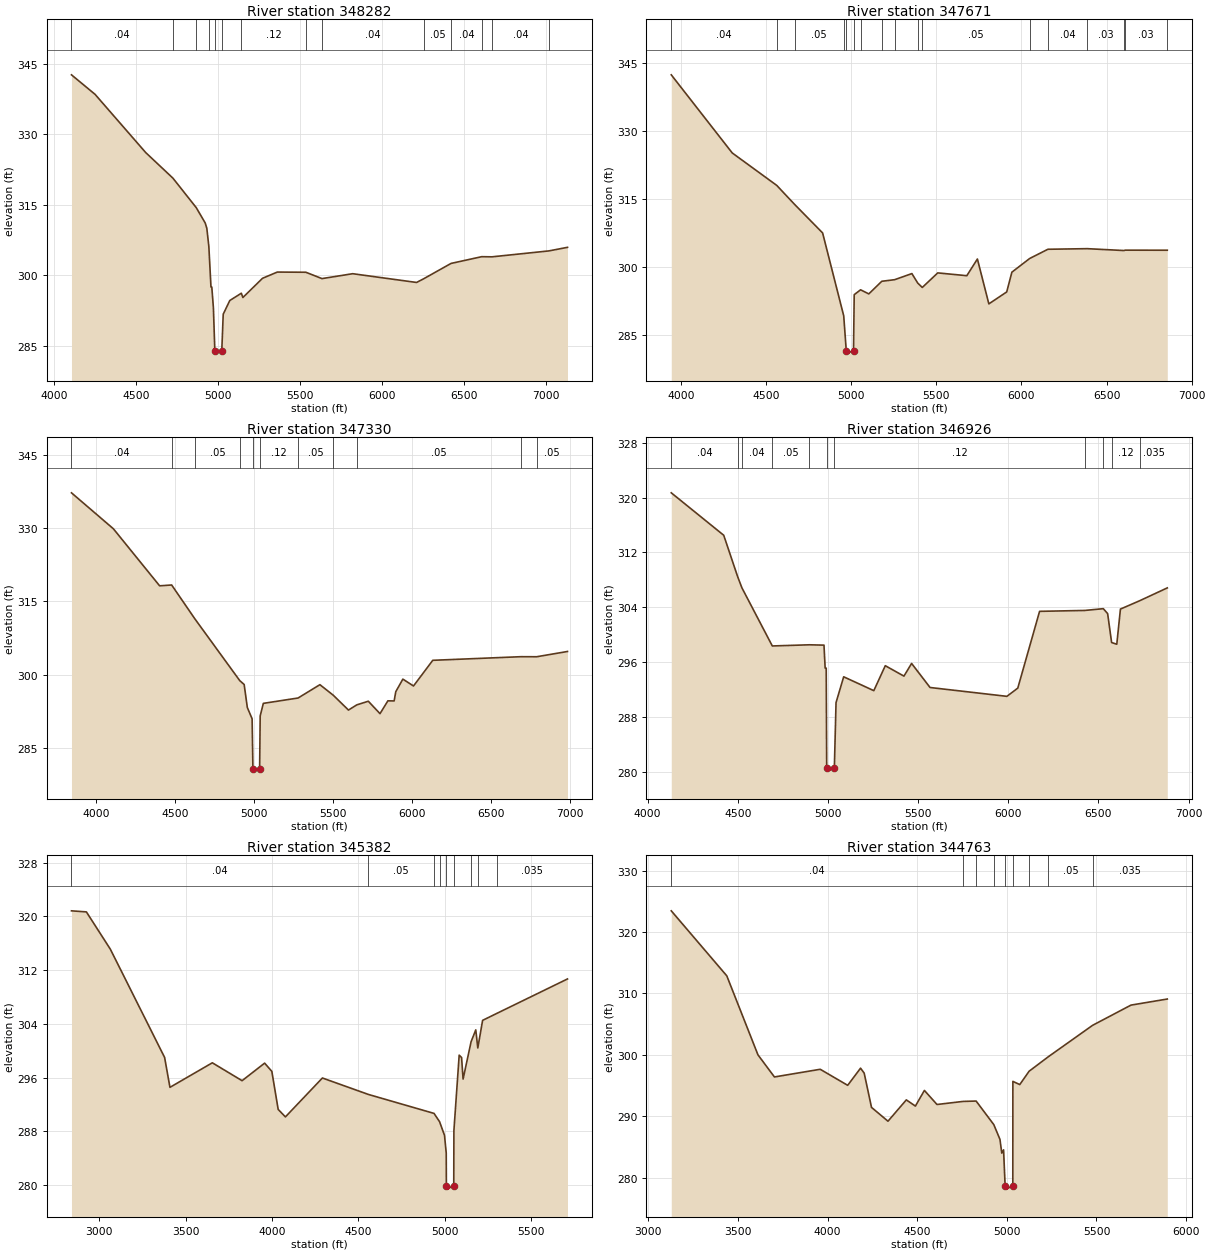
Type RM Length L Ch R = 1 ,348282  ,611,611,611
BEGIN DESCRIPTION:
Mapping XS 099e683f
END DESCRIPTION:
XS GIS Cut Line= 3
       2425248.5     13544231.04      2424399.52      13544154.4
      2422224.09     13544248.72
#Sta/Elev= 30
  4104.1   342.6  4248.2  338.45  4557.5  326.07  4723.7  320.63  4866.2  314.36
  4920.9   311.1  4930.9  309.97  4943.3  306.08  4956.3  297.47  4961.3  297.47
  4971.1  293.06  4979.9  283.91  4980.9  283.41  5022.3  283.91  5031.1  291.69
  5071.2   294.6  5141.7  296.15  5151.2  295.24  5271.3  299.33  5361.4  300.65
  5535.9  300.61  5634.5  299.26  5821.9   300.3  6212.2  298.44  6254.8  299.21
  6422.9  302.49    6610  303.92  6672.6  303.89  7020.2  305.15    7134  305.91
#Mann= 14 ,-1 , 0
  4104.1     .04       0  4723.7     .05       0  4866.2     .12       0
  4943.3     .05       0  4979.9     .05       0  5022.3     .05       0
  5141.7     .12       0  5535.9     .05       0  5634.5     .04       0
  6254.8     .05       0  6422.9     .04       0    6610     .03       0
  6672.6     .04       0  7020.2     .05       0
Bank Sta=4979.9,5022.3
XS Rating Curve= 0 ,0
Exp/Cntr=0.3,0.1

Type RM Length L Ch R = 1 ,347671  ,341,341,341
BEGIN DESCRIPTION:
Mapping XS 904a133b
END DESCRIPTION:
XS GIS Cut Line= 3
      2425142.35     13543700.44      2424069.37     13543635.59
      2422253.54     13543924.47
#Sta/Elev= 30
  3943.2  342.29  4301.2  325.07  4562.8  317.91  4668.7  313.68  4832.2  307.43
  4956.2  289.15  4971.2  281.43  4972.2  280.93  5013.7  281.43  5017.8  293.82
  5055.2  294.89  5103.6  293.99  5179.8  296.77  5255.2  297.12  5356.7  298.47
  5390.8  296.38  5417.7  295.41  5508.6  298.62  5679.2     298  5741.4  301.68
  5808.7  291.79  5913.6  294.42    5944  298.78  6048.3  301.79  6155.5  303.83
  6386.6  303.96  6602.2  303.55  6608.7  303.63  6855.8  303.62  6856.8  303.62
#Mann= 17 ,-1 , 0
  3943.2     .04       0  4562.8     .03       0  4668.7     .05       0
  4956.2      .1       0  4971.2     .05       0  5013.7      .1       0
  5055.2     .05       0  5179.8     .12       0  5255.2     .05       0
  5390.8     .12       0  5417.7     .05       0  6048.3     .12       0
  6155.5     .04       0  6386.6     .03       0  6602.2     .04       0
  6608.7     .03       0  6855.8     .05       0
Bank Sta=4971.2,5013.7
XS Rating Curve= 0 ,0
Exp/Cntr=0.3,0.1

Type RM Length L Ch R = 1 ,347330  ,404,404,404
BEGIN DESCRIPTION:
Mapping XS a5d9ecaf
END DESCRIPTION:
XS GIS Cut Line= 3
      2425165.91     13543387.97      2424039.89     13543311.33
       2422070.8     13543724.02
#Sta/Elev= 30
  3845.7  337.24  4111.3  329.87  4403.9  318.19  4480.1  318.36  4626.9  311.43
  4911.5  298.76  4939.1  297.98  4959.2  293.26  4989.5  290.95  4994.6  280.73
  4995.6  280.23  5037.1  280.73  5040.6  291.54  5060.6  294.11  5280.6  295.21
  5418.7  297.94  5503.2  295.78  5599.5  292.74  5652.6  293.81  5725.2  294.55
  5799.2     292  5849.1  294.63  5888.7  294.61    5899  296.49  5943.9  299.08
  6011.3  297.67  6133.3  302.93  6690.3  303.67  6791.4  303.66  6986.2  304.74
#Mann= 11 ,-1 , 0
  3845.7     .04       0  4480.1     .03       0  4626.9     .05       0
  4911.5     .12       0  4994.6     .05       0  5037.1     .12       0
  5280.6     .05       0  5503.2     .12       0  5652.6     .05       0
  6690.3     .12       0  6791.4     .05       0
Bank Sta=4994.6,5037.1
XS Rating Curve= 0 ,0
Exp/Cntr=0.3,0.1

Type RM Length L Ch R = 1 ,346926  ,1544,1544,1544
BEGIN DESCRIPTION:
Mapping XS 878d429f
END DESCRIPTION:
XS GIS Cut Line= 4
      2424523.36      13542521.3      2423804.07     13542987.08
      2423308.84     13543299.54      2422018.82     13543517.49
#Sta/Elev= 30
  4131.1   320.7    4422  314.51  4500.2   308.4  4522.9  306.84  4691.5  298.36
  4897.5  298.53    4978  298.48  4984.5  295.13  4990.4  295.13  4993.1   280.6
  4994.1   280.1  5035.6   280.6  5044.9   290.1  5087.3  293.86  5254.4  291.84
    5318  295.48  5421.5  293.96  5463.9  295.81  5566.3   292.3  5992.4  291.01
  6052.8  292.21  6173.7  303.41  6424.5  303.54  6526.9   303.8  6551.1  303.08
  6573.2  298.86  6601.8  298.61  6622.1  303.74  6729.9  304.97  6881.9  306.83
#Mann= 11 ,-1 , 0
  4131.1     .04       0  4500.2     .12       0  4522.9     .04       0
  4691.5     .05       0  4897.5     .12       0  4993.1     .05       0
  5035.6     .12       0  6424.5     .12       0  6526.9     .05       0
  6573.2     .12       0  6729.9    .035       0
Bank Sta=4993.1,5035.6
XS Rating Curve= 0 ,0
Exp/Cntr=0.3,0.1

Type RM Length L Ch R = 1 ,345382  ,619,619,619
BEGIN DESCRIPTION:
Mapping XS db7cfcea
END DESCRIPTION:
XS GIS Cut Line= 3
      2424429.01       13542427.      2422654.44     13542857.38
      2421712.55     13543310.66
#Sta/Elev= 30
  2838.9  320.83  2925.3  320.67    3064  315.12  3378.1  299.01    3409  294.56
  3654.3  298.21  3826.6  295.55  3957.1  298.16  3998.9  296.93  4035.6  291.27
  4077.4  290.16  4291.5  295.95    4558   293.5  4937.7  290.68  4969.7  289.45
  4998.3  287.42  5008.3  284.79  5009.1  279.91  5010.1  279.41  5051.9  279.91
  5052.7  288.11  5083.3  299.35  5097.1     299  5105.9  295.79  5152.2  301.35
  5179.3  303.11  5191.1  300.42    5219  304.53  5301.7  305.57  5710.2  310.69
#Mann= 9 ,-1 , 0
  2838.9     .04       0    4558     .05       0  4937.7     .12       0
  4969.7     .05       0  5009.1     .05       0  5051.9     .05       0
  5152.2     .12       0  5191.1     .05       0  5301.7    .035       0
Bank Sta=5009.1,5051.9
XS Rating Curve= 0 ,0
Exp/Cntr=0.3,0.1

Type RM Length L Ch R = 1 ,344763  ,434,434,434
BEGIN DESCRIPTION:
Mapping XS 15aeb0f3
END DESCRIPTION:
XS GIS Cut Line= 4
      2424358.26     13542303.19      2423043.54     13542580.29
      2422381.43      13542520.5      2421683.54     13542819.62
#Sta/Elev= 30
  3127.5  323.44  3437.4  312.86  3611.2  300.01  3703.1  296.41  3958.6  297.66
  4111.9  295.05  4183.7  297.84  4203.9  297.04  4244.8  291.46  4336.8  289.21
    4439  292.68  4489.7  291.67  4539.9  294.22  4610.2  291.93  4755.9  292.43
  4828.6  292.49  4927.1  288.66  4961.6  286.25  4971.7  284.02  4981.7  284.55
  4990.4  278.66  4991.4  278.16  5033.3  278.66  5033.6  295.69  5072.1  295.17
  5124.1  297.34  5231.5   299.7  5478.4  304.81  5692.7   308.1  5895.2  309.09
#Mann= 9 ,-1 , 0
  3127.5     .04       0  4755.9     .05       0  4828.6     .04       0
  4927.1     .12       0  4990.4     .05       0  5033.3     .12       0
  5124.1     .04       0  5231.5     .05       0  5478.4    .035       0
Bank Sta=4990.4,5033.3
XS Rating Curve= 0 ,0
Exp/Cntr=0.3,0.1

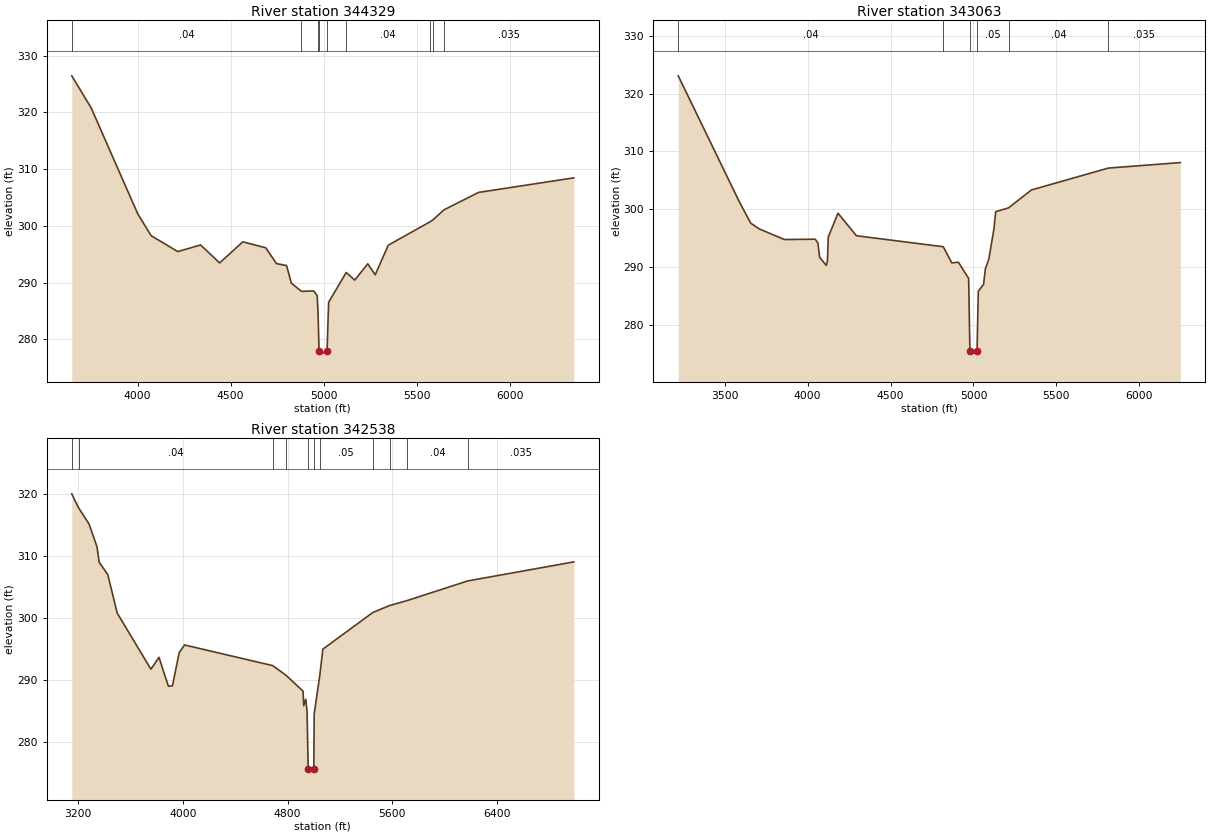
Type RM Length L Ch R = 1 ,344329  ,1266,1266,1266
BEGIN DESCRIPTION:
Mapping XS 416c8f66
END DESCRIPTION:
XS GIS Cut Line= 4
      2424122.38     13542008.43       2423102.5     13542226.55
      2422005.93      13542161.7      2421660.93      13542600.1
#Sta/Elev= 30
  3646.3  326.43  3750.2  320.81  4001.5  302.09  4073.1  298.27  4216.3  295.47
    4339  296.64  4441.3  293.47  4565.7  297.19  4689.2  296.14  4746.8  293.36
  4801.1  293.01    4827  289.91  4881.2  288.47  4947.2  288.54  4965.9   287.7
  4970.4  284.69  4975.8  277.91  4976.8  277.41  5018.7  277.91  5027.3  286.55
  5121.9  291.79  5167.6  290.45  5237.7  293.32  5277.8  291.39  5347.9   296.6
  5572.2  300.71  5587.3  301.04  5647.2  302.82  5833.1  305.89  6345.6  308.46
#Mann= 9 ,-1 , 0
  3646.3     .04       0  4881.2     .05       0  4970.4      .1       0
  4975.8     .05       0  5018.7      .1       0  5121.9     .04       0
  5572.2     .05       0  5587.3     .04       0  5647.2    .035       0
Bank Sta=4975.8,5018.7
XS Rating Curve= 0 ,0
Exp/Cntr=0.3,0.1

Type RM Length L Ch R = 1 ,343063  ,525,525,525
BEGIN DESCRIPTION:
Mapping XS eb6d4b07
END DESCRIPTION:
XS GIS Cut Line= 4
      2424140.13     13541737.23      2422341.97      13541501.4
       2422061.9     13541578.69      2421661.13     13542410.48
#Sta/Elev= 30
  3219.8  323.08  3588.1  301.27  3656.8  297.56  3709.1  296.55  3860.4  294.72
  4045.7  294.78  4062.1  294.11  4072.2  291.67  4112.5  290.24  4119.4  290.98
  4124.5  295.16  4183.1  299.28  4294.1  295.38  4817.9  293.47  4868.9  290.68
  4909.3  290.79    4971  287.98  4978.6  275.37  4979.6  274.87  5021.5  275.37
  5029.3  285.77  5060.9  286.95  5071.7  289.63  5092.5  291.32  5123.6  296.58
    5134  299.54  5211.7  300.21  5349.4  303.31  5813.4   307.1  6247.2  308.05
#Mann= 6 ,-1 , 0
  3219.8     .04       0  4817.9     .05       0  4978.6     .05       0
  5021.5     .05       0  5211.7     .04       0  5813.4    .035       0
Bank Sta=4978.6,5021.5
XS Rating Curve= 0 ,0
Exp/Cntr=0.3,0.1

Type RM Length L Ch R = 1 ,342538  ,318,318,318
BEGIN DESCRIPTION:
Mapping XS 7b7aff77
END DESCRIPTION:
XS GIS Cut Line= 4
      2424122.42     13541460.13      2422412.72     13541041.55
      2422078.57     13540999.12      2421471.81     13542630.19
#Sta/Elev= 30
  3150.6  319.98  3202.2  317.74  3282.1  315.15  3343.6  311.45  3360.2  308.97
  3425.9  306.98    3498  300.79  3755.4  291.76  3817.1  293.67  3889.2  289.02
  3920.1  289.08  3971.6  294.43  4012.7  295.66  4686.2  292.34  4786.7  290.81
  4918.3  288.23  4923.4  285.88  4938.7  286.93  4948.8  285.01  4957.6   275.7
  4958.6   275.2  5000.5   275.7  5003.4   284.6  5045.9   290.7  5069.8  294.99
  5451.1  300.88  5580.3  302.01  5713.3   302.8  6175.9  305.96  6987.9  309.03
#Mann= 11 ,-1 , 0
  3150.6     .05       0  3202.2     .04       0  4686.2     .05       0
  4786.7      .1       0  4957.6     .05       0  5000.5      .1       0
  5045.9     .05       0  5451.1    .013       0  5580.3     .05       0
  5713.3     .04       0  6175.9    .035       0
Bank Sta=4957.6,5000.5
XS Rating Curve= 0 ,0
Exp/Cntr=0.3,0.1