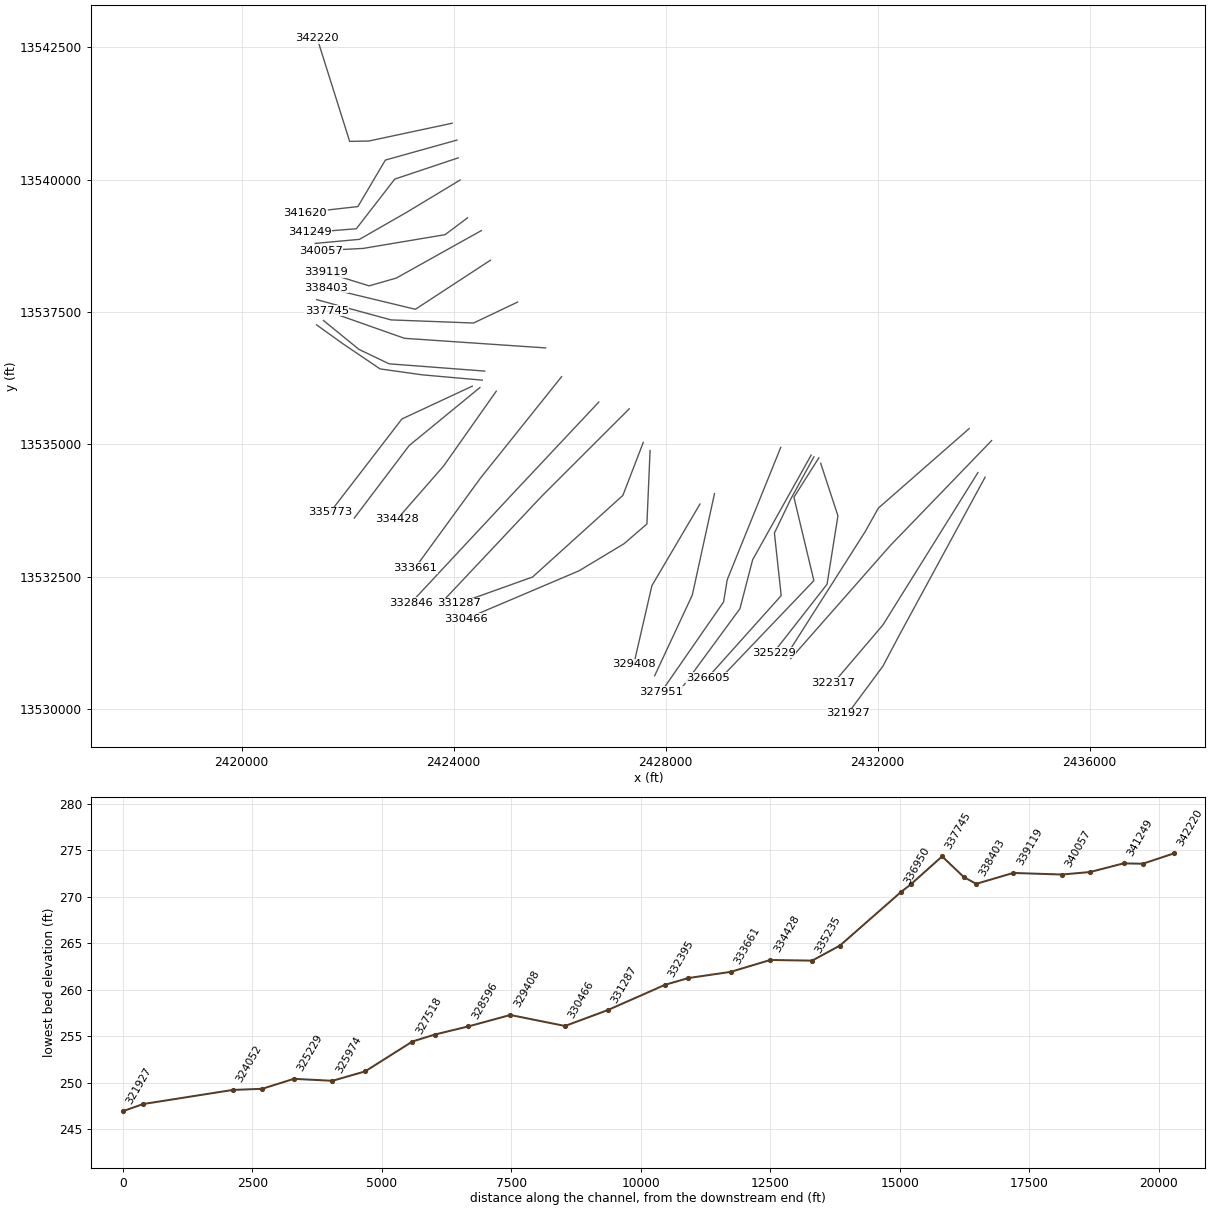
HEC-RAS study COLETO CREEK.prj: COLETO CREEK Base Level Engineering

--- COLETO CREEK.g01 (geometry) --- (continued)

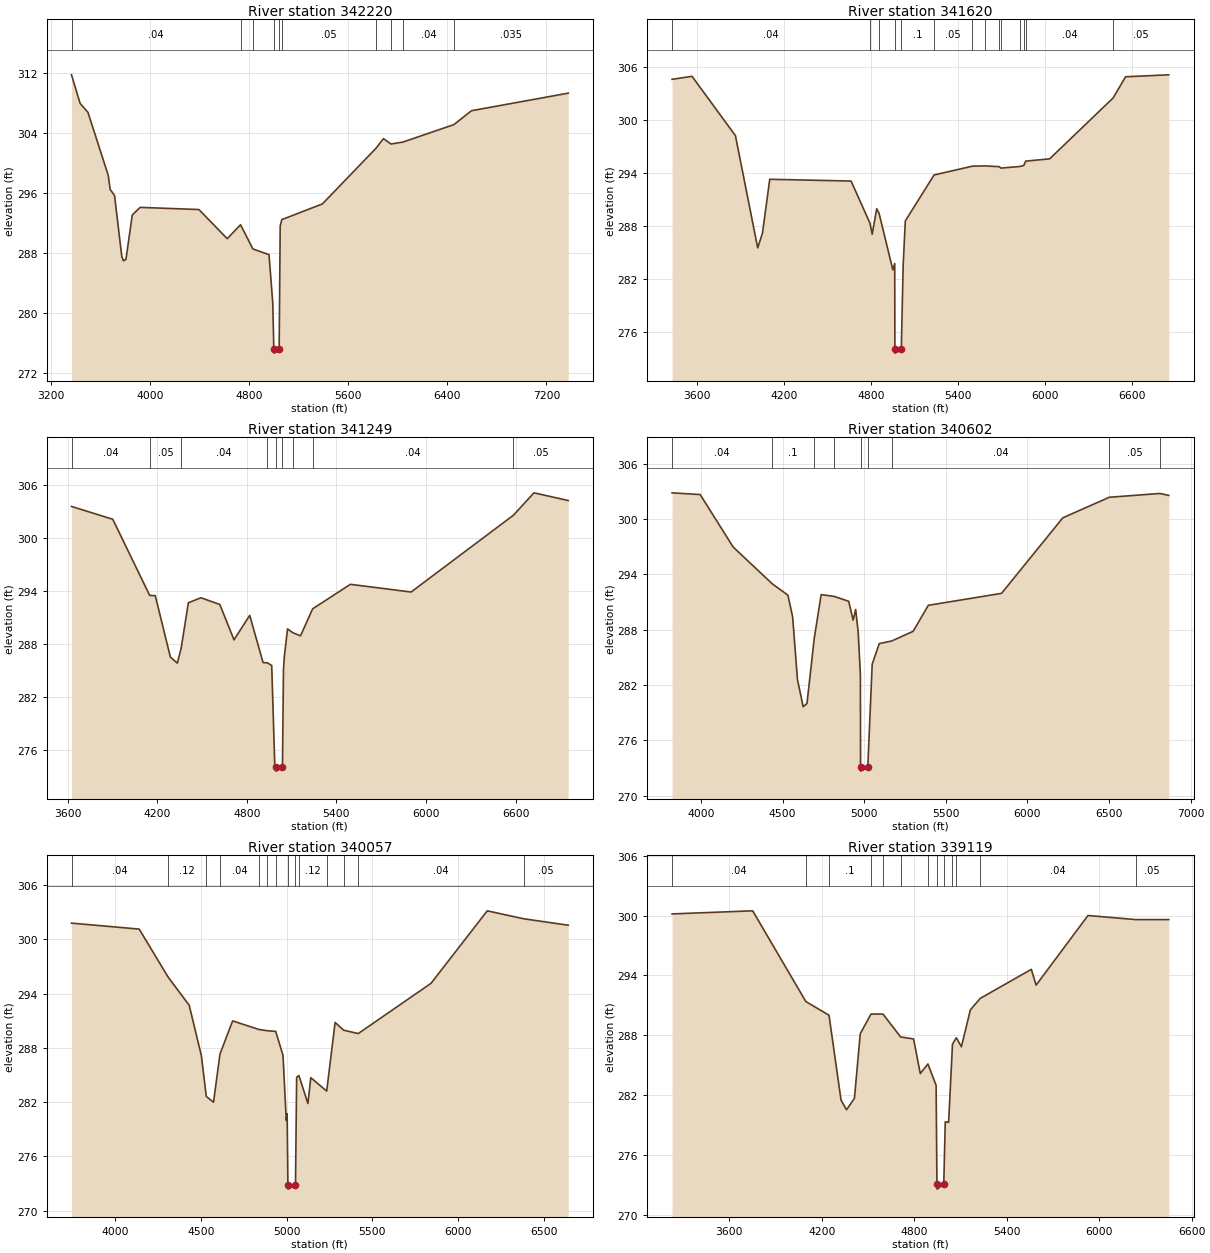
Type RM Length L Ch R = 1 ,342220  ,600,600,600
BEGIN DESCRIPTION:
Mapping XS e09b66a3
END DESCRIPTION:
XS GIS Cut Line= 4
      2423975.06     13541065.14      2422400.93     13540729.09
      2422039.37     13540722.41       2421426.3      13542668.3
#Sta/Elev= 30
  3364.4  311.72  3433.9  307.92  3497.4  306.72    3661  298.34  3676.4  296.47
  3712.1  295.64  3770.3  287.57  3783.7  286.96  3804.1  287.14  3855.3  293.06
  3918.8  294.07  4393.5  293.78  4622.2   289.9  4729.6  291.76  4829.5  288.53
  4959.6  287.77  4989.9   281.3  4998.5  275.16  4999.5  274.66  5041.4  275.16
  5049.9   291.6    5063  292.44  5390.8  294.53  5822.2  301.92  5883.5  303.22
  5945.1  302.51  6041.7  302.77  6452.6  305.09  6594.7  306.94  7375.8  309.28
#Mann= 10 ,-1 , 0
  3364.4     .04       0  4729.6     .05       0  4829.5      .1       0
  4998.5     .05       0  5041.4      .1       0    5063     .05       0
  5822.2    .013       0  5945.1     .05       0  6041.7     .04       0
  6452.6    .035       0
Bank Sta=4998.5,5041.4
XS Rating Curve= 0 ,0
Exp/Cntr=0.3,0.1

Type RM Length L Ch R = 1 ,341620  ,371,371,371
BEGIN DESCRIPTION:
Mapping XS e9d72ce7
END DESCRIPTION:
XS GIS Cut Line= 4
      2424063.47     13540746.77      2422713.39     13540369.46
      2422194.58     13539491.02      2421199.17     13539379.11
#Sta/Elev= 30
  3428.2  304.61  3565.8  304.95    3865  298.22  4018.5  285.49  4051.3  287.16
  4101.5  293.27  4662.2  293.07  4792.2  288.29  4807.6  287.04  4838.8  289.93
  4854.9  289.42  4950.1  282.99  4962.9  283.71    4964  274.05    4965  273.55
  5008.3  274.05    5021  283.43  5035.9  288.55  5234.2  293.76  5498.8  294.76
  5583.6  294.79  5683.2   294.7  5694.8  294.54  5825.3  294.72  5852.1  294.83
  5866.1  295.33  6030.9  295.59  6468.4   302.5  6554.2   304.9  6851.9  305.12
#Mann= 14 ,-1 , 0
  3428.2     .04       0  4792.2     .05       0  4854.9      .1       0
    4964     .05       0  5008.3      .1       0  5234.2     .05       0
  5498.8     .12       0  5583.6     .05       0  5683.2      .1       0
  5694.8     .12       0  5825.3     .04       0  5852.1     .12       0
  5866.1     .04       0  6468.4     .05       0
Bank Sta=4964,5008.3
XS Rating Curve= 0 ,0
Exp/Cntr=0.3,0.1

Type RM Length L Ch R = 1 ,341249  ,647,647,647
BEGIN DESCRIPTION:
Mapping XS 17fafce7
END DESCRIPTION:
XS GIS Cut Line= 4
      2424087.04     13540410.72      2422890.26     13540009.83
      2422165.11     13539072.44      2421288.33     13539001.82
#Sta/Elev= 30
  3625.6  303.53    3902  302.08  4149.5  293.46  4186.7  293.44    4288  286.48
  4334.3  285.81  4359.9  287.47  4408.2  292.63  4492.5   293.2  4619.1  292.44
    4714  288.44  4819.2  291.21  4908.7  285.87  4937.4  285.84  4966.6  285.54
  4987.4  274.12  4994.3  274.09  4995.3  273.59  5038.6  274.09  5045.4  285.09
  5051.7  286.63  5072.6  289.68  5107.6  289.25  5159.4  288.89  5240.9  291.95
  5493.6  294.72  5900.2  293.85  6585.9  302.54  6723.1  305.07  6952.5   304.2
#Mann= 9 ,-1 , 0
  3625.6     .04       0  4149.5     .05       0  4359.9     .04       0
  4937.4      .1       0  4994.3     .05       0  5038.6      .1       0
  5107.6     .05       0  5240.9     .04       0  6585.9     .05       0
Bank Sta=4994.3,5038.6
XS Rating Curve= 0 ,0
Exp/Cntr=0.3,0.1

Type RM Length L Ch R = 1 ,340602  ,545,545,545
BEGIN DESCRIPTION:
Mapping XS df55d11d
END DESCRIPTION:
XS GIS Cut Line= 4
      2424122.46     13539992.17      2423108.39     13539379.01
      2422224.06     13538871.99      2421388.46     13538795.49
#Sta/Elev= 30
    3823  302.84  3995.3  302.65  4197.1  296.97  4435.8  292.99  4532.9  291.74
  4561.8  289.39  4591.3   282.6  4626.4  279.64  4649.7     280  4694.2  287.05
  4736.5   291.8    4816  291.61  4905.2  291.08  4932.4  289.04  4947.9  290.19
  4963.4  287.76  4976.9  283.13  4978.1  273.16  4979.1  272.66  5022.4  273.16
  5049.3  284.26  5092.6  286.49  5168.5  286.77  5300.1  287.82  5393.1  290.64
  5841.9  291.94  6217.3  300.13  6502.1  302.36  6811.7  302.77  6866.5  302.56
#Mann= 9 ,-1 , 0
    3823     .04       0  4435.8      .1       0  4694.2     .05       0
    4816      .1       0  4978.1     .05       0  5022.4      .1       0
  5168.5     .04       0  6502.1     .05       0  6811.7     .12       0
Bank Sta=4978.1,5022.4
XS Rating Curve= 0 ,0
Exp/Cntr=0.3,0.1

Type RM Length L Ch R = 1 ,340057  ,938,938,938
BEGIN DESCRIPTION:
Mapping XS 762862c4
END DESCRIPTION:
XS GIS Cut Line= 4
      2424263.88     13539278.76      2423839.44     13538960.42
      2422294.81     13538701.02      2421492.99     13538659.75
#Sta/Elev= 30
  3744.5   301.8  4139.6  301.14  4309.1  295.82  4431.7  292.72  4502.6  287.15
  4531.3  282.64  4573.6     282  4611.2  287.32  4685.2  290.99  4837.3  290.05
  4883.8  289.91  4936.6  289.83  4979.2  287.19  4998.3  279.98  5003.4  280.72
  5007.8  272.89  5008.8  272.39  5052.1  272.89  5058.9  284.76  5072.1  284.95
  5124.6  281.86  5141.5  284.71  5234.3  283.23  5283.4  290.82  5333.5  289.96
  5418.6  289.59  5843.7  295.15  6171.6  303.16  6384.6  302.28  6644.2  301.57
#Mann= 14 ,-1 , 0
  3744.5     .04       0  4309.1     .12       0  4531.3      .1       0
  4611.2     .04       0  4837.3     .12       0  4883.8     .05       0
  4936.6     .12       0  5007.8     .05       0  5052.1     .12       0
  5072.1     .12       0  5234.3     .05       0  5333.5    .013       0
  5418.6     .04       0  6384.6     .05       0
Bank Sta=5007.8,5052.1
XS Rating Curve= 0 ,0
Exp/Cntr=0.3,0.1

Type RM Length L Ch R = 1 ,339119  ,716,716,716
BEGIN DESCRIPTION:
Mapping XS ec6c54e0
END DESCRIPTION:
XS GIS Cut Line= 4
      2424523.29     13539037.05      2422919.73     13538140.94
      2422406.82     13537993.55      2421593.23     13538247.07
#Sta/Elev= 30
  3228.7  300.16  3751.8  300.47  4096.8  291.37    4247     290  4325.2  281.48
  4360.8  280.52    4412  281.67  4449.7  288.14  4519.5  290.12  4597.5  290.11
  4711.7  287.82  4795.8  287.62  4839.2  284.15  4888.7  285.11    4942  282.97
  4947.2  273.06  4948.2  272.56  4991.6  273.06  5001.3  279.31  5023.1  279.26
  5048.2   287.1  5073.2  287.74  5106.1  286.84  5164.2  290.54  5228.4  291.69
  5559.6   294.6  5590.8  293.02  5927.3     300  6237.5  299.59  6451.5  299.59
#Mann= 13 ,-1 , 0
  3228.7     .04       0  4096.8     .12       0    4247      .1       0
  4519.5     .05       0  4597.5     .12       0  4711.7     .05       0
  4888.7      .1       0  4947.2     .05       0  4991.6      .1       0
  5048.2     .12       0  5073.2    .013       0  5228.4     .04       0
  6237.5     .05       0
Bank Sta=4947.2,4991.6
XS Rating Curve= 0 ,0
Exp/Cntr=0.3,0.1

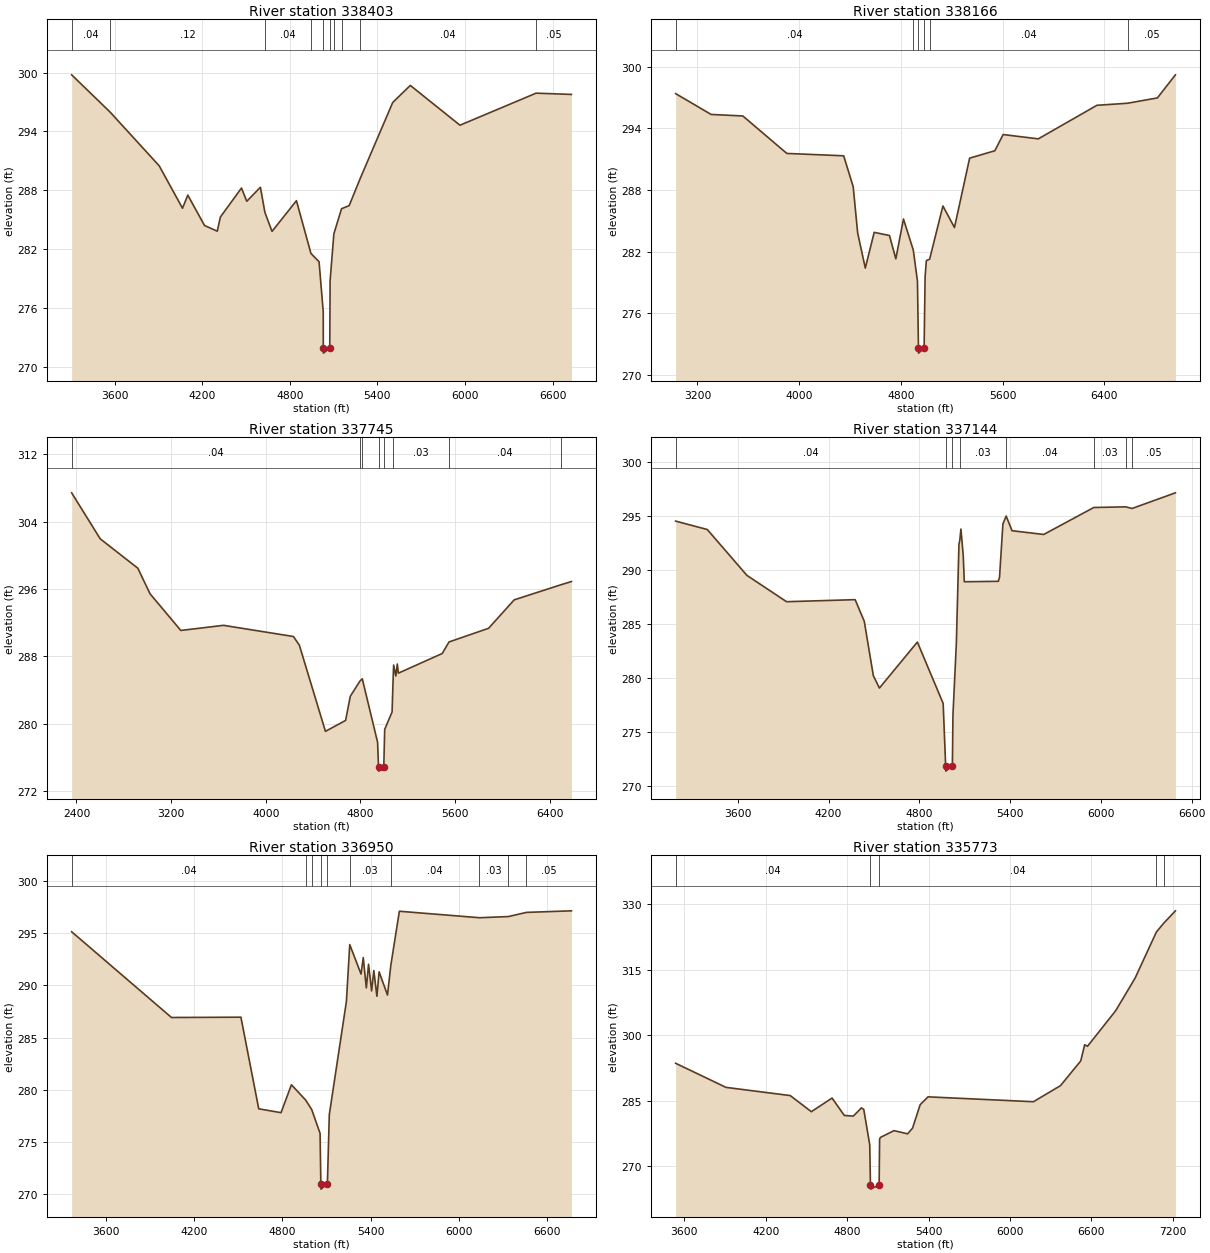
Type RM Length L Ch R = 1 ,338403  ,237,237,237
BEGIN DESCRIPTION:
Mapping XS 0d804388
END DESCRIPTION:
XS GIS Cut Line= 3
      2424694.28     13538476.98      2423279.36     13537551.39
      2421593.21     13537958.19
#Sta/Elev= 30
  3304.5  299.78  3567.4  295.99  3904.4   290.5  4064.3  286.17  4100.5  287.51
  4215.1  284.41  4302.5  283.83  4323.6  285.27  4468.4  288.23  4504.6  286.88
  4598.1  288.31  4629.2  285.73  4677.8  283.81  4845.1  286.94  4944.4  281.56
  5000.1  280.71  5028.7   275.6    5029  271.89    5030  271.39  5073.4  271.89
  5075.8  278.79  5101.6  283.56  5154.1  286.12  5206.6  286.44  5282.2  289.21
    5505  296.96  5625.5   298.7  5965.8  294.64  6487.7  297.91  6729.8  297.78
#Mann= 10 ,-1 , 0
  3304.5     .04       0  3567.4     .12       0  4629.2     .04       0
  4944.4     .12       0    5029     .05       0  5073.4     .12       0
  5101.6      .1       0  5154.1     .05       0  5282.2     .04       0
  6487.7     .05       0
Bank Sta=5029,5073.4
XS Rating Curve= 0 ,0
Exp/Cntr=0.3,0.1

Type RM Length L Ch R = 1 ,338166  ,421,421,421
BEGIN DESCRIPTION:
Mapping XS a99ddd75
END DESCRIPTION:
XS GIS Cut Line= 4
      2425207.17     13537686.97      2424375.93     13537291.98
      2422819.51     13537350.94      2421418.18     13537733.65
#Sta/Elev= 30
  3028.1   297.4  3307.3  295.37  3556.7  295.22    3903  291.57  4349.6  291.34
  4424.5  288.34  4459.7  283.83  4519.8   280.4  4589.8  283.88  4709.9  283.57
  4759.9   281.3    4820  285.18  4897.5  282.14    4930  279.12  4937.9  272.61
  4938.9  272.11  4982.3  272.61  4990.1  279.56  5000.1  281.13  5025.7  281.26
  5130.2  286.45  5221.1  284.35  5340.3  291.11  5538.4  291.83  5603.9  293.41
  5880.3  292.99  6341.3  296.26  6582.1  296.46  6816.8  296.98  6958.6  299.23
#Mann= 6 ,-1 , 0
  3028.1     .04       0  4897.5      .1       0  4937.9     .05       0
  4982.3      .1       0  5025.7     .04       0  6582.1     .05       0
Bank Sta=4937.9,4982.3
XS Rating Curve= 0 ,0
Exp/Cntr=0.3,0.1

Type RM Length L Ch R = 1 ,337745  ,601,601,601
BEGIN DESCRIPTION:
Mapping XS 1a066402
END DESCRIPTION:
XS GIS Cut Line= 3
       2425735.9     13536821.78      2423073.02      13537003.1
      2421605.05      13537521.9
#Sta/Elev= 30
  2359.1  307.44  2600.6  301.97    2919  298.47  3021.5  295.44  3282.1  291.07
    3643  291.68  4234.3  290.35  4284.4  289.32    4505  279.07  4675.4  280.37
  4715.4  283.25  4796.6  285.05  4816.5  285.32    4946  277.77  4953.8  274.84
  4954.8  274.34  4998.2  274.84  5006.1  279.31  5068.5  281.38  5075.6  284.59
  5081.6  286.96  5100.3  285.66  5112.5  287.08  5121.5  285.99  5492.7  288.33
  5549.5   289.7  5884.5  291.33  6100.9  294.71  6497.2  296.51  6585.1  296.89
#Mann= 8 ,-1 , 0
  2359.1     .04       0  4796.6      .1       0  4816.5     .04       0
  4953.8     .04       0  4998.2     .04       0  5075.6     .03       0
  5549.5     .04       0  6497.2     .05       0
Bank Sta=4953.8,4998.2
XS Rating Curve= 0 ,0
Exp/Cntr=0.3,0.1

Type RM Length L Ch R = 1 ,337144  ,194,194,194
BEGIN DESCRIPTION:
Mapping XS 3668cee0
END DESCRIPTION:
XS GIS Cut Line= 4
      2424588.16     13536384.07      2422782.79     13536521.58
      2422215.05     13536794.01      2421546.06     13537339.16
#Sta/Elev= 30
  3189.4  294.52  3398.7  293.74  3660.7  289.49  3922.7  287.05    4376  287.24
  4436.2  285.24  4496.3  280.19  4536.5  279.05  4787.2  283.31  4957.7  277.62
  4974.1  271.85  4975.1  271.35  5018.7  271.85  5022.4  276.57    5045  283.24
  5062.1  292.37  5067.7  292.76  5075.2  293.78  5090.3  291.34  5097.4   288.9
  5322.4  288.94  5330.3  289.32  5352.5  294.25    5374  294.99    5413  293.63
  5622.3  293.28  5953.2  295.78    6165  295.84  6206.2  295.69  6492.7  297.14
#Mann= 8 ,-1 , 0
  3189.4     .04       0  4974.1     .04       0  5018.7     .04       0
  5067.7     .03       0    5374     .04       0  5953.2     .03       0
    6165     .04       0  6206.2     .05       0
Bank Sta=4974.1,5018.7
XS Rating Curve= 0 ,0
Exp/Cntr=0.3,0.1

Type RM Length L Ch R = 1 ,336950  ,1177,1177,1177
BEGIN DESCRIPTION:
Mapping XS 8074fdf1
END DESCRIPTION:
XS GIS Cut Line= 5
      2424540.99      13536213.1      2423409.06     13536313.32
      2422613.17     13536425.34      2421899.81     13536908.77
      2421416.37     13537256.61
#Sta/Elev= 30
  3367.2  295.12  4045.8  286.92  4517.8  286.95  4638.9  278.19  4790.4  277.82
  4861.1  280.49  4957.6  279.03  4998.7  278.13  5055.9  275.84    5061  271.01
    5062  270.51  5105.6  271.01  5118.6  277.63  5234.8  288.45  5257.6  293.89
  5334.4  291.07  5349.3  292.65  5370.3  289.75  5385.3  292.01  5406.2  289.46
  5421.2  291.41  5442.2  288.95  5457.1  291.29  5514.1  289.07  5536.9  291.92
  5594.9  297.08  6139.5  296.46    6335  296.57  6458.7  296.97  6764.6  297.12
#Mann= 10 ,-1 , 0
  3367.2     .04       0  4957.6      .1       0  4998.7     .04       0
    5061     .04       0  5105.6     .04       0  5257.6     .03       0
  5536.9     .04       0  6139.5     .03       0    6335     .04       0
  6458.7     .05       0
Bank Sta=5061,5105.6
XS Rating Curve= 0 ,0
Exp/Cntr=0.3,0.1

Type RM Length L Ch R = 1 ,335773  ,538,538,538
BEGIN DESCRIPTION:
SMITH CREEK 80.0
END DESCRIPTION:
XS GIS Cut Line= 3
      2424351.64     13536098.99      2423025.39     13535480.16
      2421672.65     13533719.69
#Sta/Elev= 30
  3535.9  293.59  3906.9  288.07  4380.6  286.19  4536.4   282.5  4688.9  285.62
  4779.2  281.64  4845.4  281.49  4905.6  283.37  4922.6  283.02  4966.7  274.93
  4971.9  265.76  4973.4  264.76    5036  265.76  5039.3  276.22  5045.6  276.61
  5145.3  278.16  5245.5  277.43  5282.2  278.73  5338.3   284.1  5396.4   285.9
    6173  284.78  6372.4  288.46  6521.9  294.13  6550.9  297.83  6571.7  297.48
  6779.3  305.63  6922.5   313.1  7079.6  323.67  7132.6  325.65  7219.6  328.51
#Mann= 5 ,-1 , 0
  3535.9     .04       0  4971.9     .04       0    5036     .04       0
  7079.6     .05       0  7132.6     .04       0
Bank Sta=4971.9,5036
XS Rating Curve= 0 ,0
Exp/Cntr=0.3,0.1

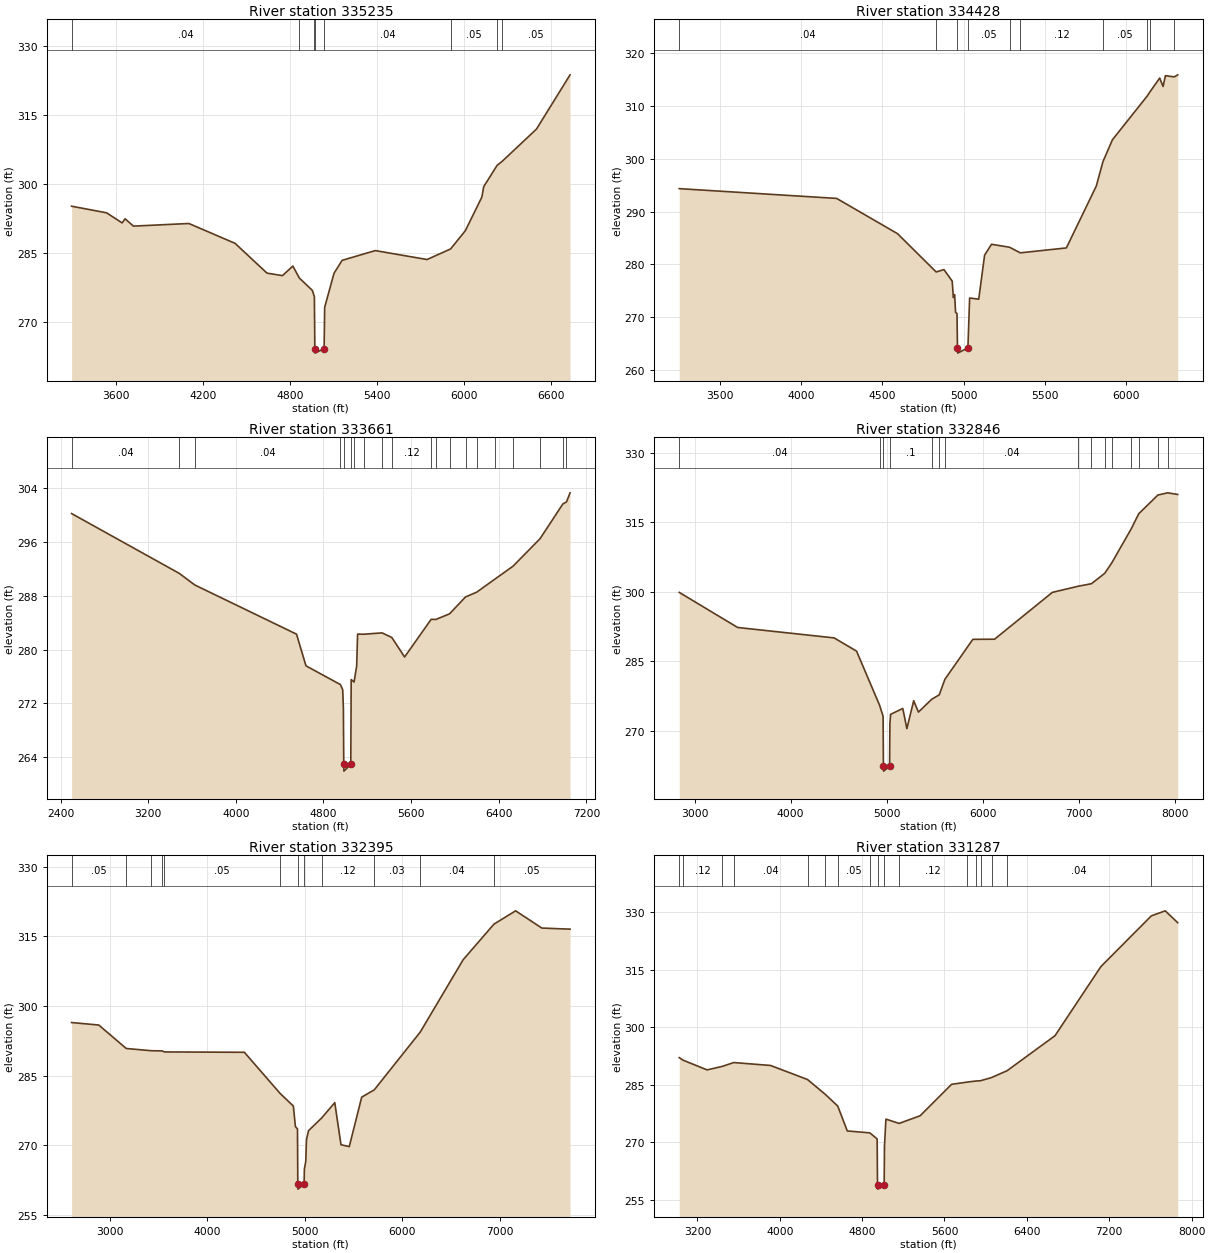
Type RM Length L Ch R = 1 ,335235  ,807,807,807
BEGIN DESCRIPTION:
Mapping XS 8408ad72
END DESCRIPTION:
XS GIS Cut Line= 3
      2424497.12      13536073.3       2423161.8     13534977.65
      2422126.78     13533609.04
#Sta/Elev= 30
  3291.2  295.08  3533.1  293.64    3640  291.45  3660.8  292.35  3718.2  290.75
  4101.4  291.32  4420.7     287  4641.1  280.53    4748  279.99  4819.7  282.07
  4864.2  279.47  4953.9  276.79  4968.3  275.41  4968.7  273.96  4971.4  264.14
  4972.9  263.14  5035.5  264.14  5039.3   273.1  5103.8  280.49    5160  283.31
  5388.9  285.43  5746.8  283.49  5909.2  285.79  6011.1  289.76  6125.1  297.06
  6138.1  299.34  6230.7  303.97  6265.2  304.83  6502.2  311.84  6734.4  323.64
#Mann= 8 ,-1 , 0
  3291.2     .04       0  4864.2     .05       0  4968.7     .04       0
  4971.4     .04       0  5035.5     .04       0  5909.2     .05       0
  6230.7     .04       0  6265.2     .05       0
Bank Sta=4971.4,5035.5
XS Rating Curve= 0 ,0
Exp/Cntr=0.3,0.1

Type RM Length L Ch R = 1 ,334428  ,767,767,767
BEGIN DESCRIPTION:
Mapping XS 21002219
END DESCRIPTION:
XS GIS Cut Line= 3
      2424805.26     13536004.81      2423812.34     13534592.46
      2422930.66     13533582.38
#Sta/Elev= 30
  3250.7  294.34  4219.2  292.49  4593.8  285.82  4831.7  278.57  4879.6  279.02
  4930.2  276.84  4937.4  273.72    4945  274.28  4951.1  270.92  4959.8   270.7
  4962.7  264.21  4964.2  263.21  5026.9  264.21  5037.5  273.64  5093.5  273.42
  5129.6  281.75  5172.3  283.81  5283.3  283.25  5349.1  282.19  5632.7  283.12
  5816.9  294.83  5858.1  299.47  5916.2  303.59  6129.7  311.85  6145.4  312.58
    6207  315.27  6227.9  313.67  6242.1  315.72  6296.4  315.49  6317.9  315.88
#Mann= 10 ,-1 , 0
  3250.7     .04       0  4831.7     .05       0  4962.7     .05       0
  5026.9     .05       0  5283.3     .05       0  5349.1     .12       0
  5858.1     .05       0  6129.7     .04       0  6145.4     .05       0
  6296.4     .04       0
Bank Sta=4962.7,5026.9
XS Rating Curve= 0 ,0
Exp/Cntr=0.3,0.1

Type RM Length L Ch R = 1 ,333661  ,815,815,815
BEGIN DESCRIPTION:
Mapping XS b1125eaa
END DESCRIPTION:
XS GIS Cut Line= 3
      2426037.85     13536278.72      2424505.67     13534361.35
      2423273.08     13532666.53
#Sta/Elev= 30
  2500.8   300.2  3482.9  291.32  3625.2  289.59  4553.9  282.28  4640.4  277.57
  4954.7  274.79  4975.4  274.02  4981.7   271.3  4985.1  262.93  4986.6  261.93
  5049.3  262.93  5052.8  275.53  5079.3  275.17    5103  277.56  5111.4  282.29
  5166.5  282.27  5335.2  282.47  5424.1  281.78  5540.4  278.89  5782.9  284.48
  5826.2  284.47  5950.7   285.3  6096.7  287.81  6199.7  288.53    6363  290.44
  6530.2  292.38  6776.5  296.46  6985.8  301.64  7017.8  301.92  7050.8  303.28
#Mann= 20 ,-1 , 0
  2500.8     .04       0  3482.9     .03       0  3625.2     .04       0
  4954.7     .05       0  4985.1     .05       0  5049.3     .05       0
  5079.3      .1       0  5166.5     .12       0  5335.2     .04       0
  5424.1     .12       0  5782.9     .04       0  5826.2     .12       0
  5950.7     .12       0  6096.7     .04       0  6199.7     .12       0
    6363     .04       0  6530.2     .05       0  6776.5     .05       0
  6985.8     .04       0  7017.8     .05       0
Bank Sta=4985.1,5049.3
XS Rating Curve= 0 ,0
Exp/Cntr=0.3,0.1

Type RM Length L Ch R = 1 ,332846  ,451,451,451
BEGIN DESCRIPTION:
Mapping XS d1dc62c1
END DESCRIPTION:
XS GIS Cut Line= 3
      2426739.75     13535799.37      2425181.89      13534138.8
      2423197.24     13532008.72
#Sta/Elev= 30
  2840.3  299.86  3448.3  292.28  4452.5  290.03    4686  287.17  4925.2  275.51
    4962  273.12  4965.5  262.27    4967  261.27  5029.7  262.27  5032.8  271.49
  5040.1  273.53  5167.1   274.8  5209.6  270.44  5280.5  276.47  5329.8  274.01
  5469.1   276.8  5546.3  277.73  5605.3  281.09  5896.1  289.72  6122.3  289.75
  6723.7  299.86    6992  301.18  7130.5  301.73  7268.9  303.97  7343.5  306.27
  7545.8  313.62  7623.4  316.85  7822.7  320.88  7923.9  321.35  8028.6     321
#Mann= 15 ,-1 , 0
  2840.3     .04       0  4925.2      .1       0  4965.5     .05       0
  5029.7      .1       0  5469.1     .04       0  5546.3      .1       0
  5605.3     .04       0    6992     .05       0  7130.5     .04       0
  7268.9    .013       0  7343.5     .04       0  7545.8    .013       0
  7623.4     .05       0  7822.7    .013       0  7923.9     .04       0
Bank Sta=4965.5,5029.7
XS Rating Curve= 0 ,0
Exp/Cntr=0.3,0.1

Type RM Length L Ch R = 1 ,332395  ,1108,1108,1108
BEGIN DESCRIPTION:
Mapping XS fb2c2108
END DESCRIPTION:
XS GIS Cut Line= 3
      2427313.29     13535671.01      2425661.24     13534018.96
       2423761.5     13531999.42
#Sta/Elev= 30
  2610.1  296.42  2888.9  295.88  3170.4  290.83  3425.6  290.35  3537.7  290.31
  3560.8  290.09  4380.9  290.01  4747.9  281.14    4883  278.43  4904.2     274
  4925.4   273.5  4928.6  261.54  4930.1  260.54  4993.1  261.54    4996  264.87
  5010.2   266.5  5017.5  271.19  5038.5  273.13  5172.9  275.86  5307.6  279.17
  5371.1  270.11    5456  269.69  5583.4  280.35  5712.6  281.93    6184  294.38
  6623.3  309.95  6938.4   317.6    7161  320.48  7429.7  316.77  7719.1  316.53
#Mann= 12 ,-1 , 0
  2610.1     .05       0  3170.4     .12       0  3425.6     .05       0
  3537.7     .12       0  3560.8     .05       0  4747.9      .1       0
  4928.6     .05       0  4993.1      .1       0  5172.9     .12       0
  5712.6     .03       0    6184     .04       0  6938.4     .05       0
Bank Sta=4928.6,4993.1
XS Rating Curve= 0 ,0
Exp/Cntr=0.3,0.1

Type RM Length L Ch R = 1 ,331287  ,821,821,821
BEGIN DESCRIPTION:
Mapping XS d32aeb15
END DESCRIPTION:
XS GIS Cut Line= 4
      2427578.61     13535037.56      2427193.43     13534036.08
      2425490.04     13532495.33      2424104.97     13531999.44
#Sta/Elev= 30
    3024  292.06  3063.7  291.37    3294  288.87  3441.8  289.78  3553.6  290.78
  3911.1  290.02  4269.7  286.36  4440.7  282.54  4563.3  279.45    4656  272.97
  4874.6  272.47    4946  270.89  4949.6  258.82  4951.1  257.82  5014.1  258.82
    5017  268.93  5031.2  276.05  5159.5  274.93  5363.7  276.93  5668.5  285.11
  5820.5  285.69    5905  285.97  5949.7  286.04  6056.8  286.87  6208.2  288.66
  6673.3  297.77  7118.9  315.77  7608.7  328.98  7743.7  330.29    7865   327.2
#Mann= 17 ,-1 , 0
    3024     .05       0  3063.7     .12       0  3441.8     .05       0
  3553.6     .04       0  4269.7     .05       0  4440.7     .04       0
  4563.3     .05       0  4874.6      .1       0  4949.6     .05       0
  5014.1      .1       0  5159.5     .12       0  5820.5     .05       0
    5905     .12       0  5949.7     .03       0  6056.8     .12       0
  6208.2     .04       0  7608.7     .05       0
Bank Sta=4949.6,5014.1
XS Rating Curve= 0 ,0
Exp/Cntr=0.3,0.1

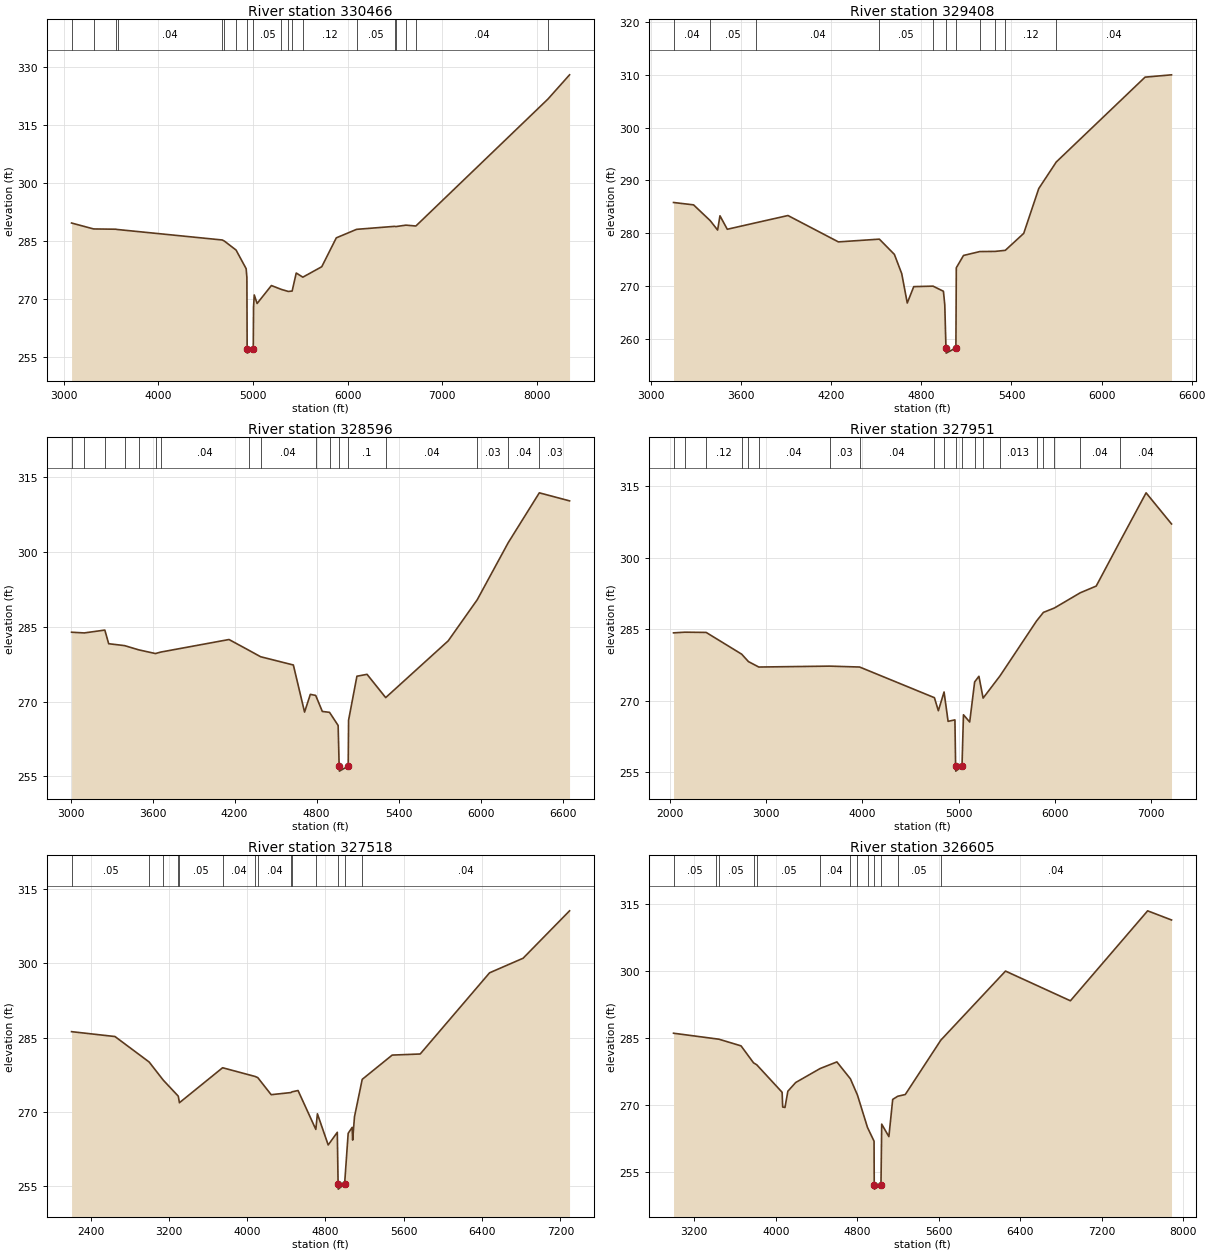
Type RM Length L Ch R = 1 ,330466  ,1058,1058,1058
BEGIN DESCRIPTION:
Mapping XS 4a7e0f63
END DESCRIPTION:
XS GIS Cut Line= 5
      2427707.01     13534883.45      2427647.09     13533496.82
      2427218.05     13533125.68        2426368.     13532613.04
      2424240.33     13531707.84
#Sta/Elev= 30
  3084.7  289.71  3317.6  288.18  3550.7  288.11  3571.4  288.03  4676.6  285.33
    4700  285.03  4822.3  282.73  4928.9  277.91  4936.6  275.65  4939.4  257.12
  4940.9  256.12  5003.9  257.12  5006.8  267.94  5014.5  271.14  5044.6  268.93
  5195.3  273.57  5301.9  272.56  5374.5  272.04  5414.7  272.15  5457.8   276.8
  5527.6  275.73  5727.6  278.43    5881  285.88  6095.4  288.08  6496.3  288.85
  6510.4  288.79    6616  289.16  6721.6  288.94    8116   321.7  8344.8  327.97
#Mann= 19 ,-1 , 0
  3084.7     .12       0  3317.6     .04       0  3550.7     .12       0
  3571.4     .04       0  4676.6     .05       0    4700      .1       0
  4822.3     .05       0  4939.4     .05       0  5003.9     .05       0
  5301.9     .05       0  5374.5     .12       0  5414.7     .05       0
  5527.6     .12       0  6095.4     .05       0  6496.3     .12       0
  6510.4     .05       0    6616     .03       0  6721.6     .04       0
    8116     .05       0
Bank Sta=4939.4,5003.9
XS Rating Curve= 0 ,0
Exp/Cntr=0.3,0.1

Type RM Length L Ch R = 1 ,329408  ,812,812,812
BEGIN DESCRIPTION:
Mapping XS 5999174d
END DESCRIPTION:
XS GIS Cut Line= 3
       2428648.6     13533873.48      2427741.25      13532332.7
      2427398.87     13530843.34
#Sta/Elev= 30
  3149.6  285.82    3283  285.37    3394  282.38  3443.1   280.6  3458.8   283.3
  3507.6  280.75  3697.8  281.98  3911.7  283.35  4247.5  278.36  4520.3  278.88
  4620.4  275.99  4669.1  272.36  4706.2  266.79  4749.3  269.89  4877.9  269.98
    4947  269.01  4955.9  266.45  4963.8   258.3  4965.3   257.3    5030   258.3
  5032.7  273.46  5080.6  275.79  5189.4  276.53  5291.2  276.56  5358.9  276.76
  5481.6  279.97  5581.8  288.46  5698.5  293.49  6289.8  309.55  6465.9  309.99
#Mann= 11 ,-1 , 0
  3149.6     .04       0    3394     .05       0  3697.8     .04       0
  4520.3     .05       0  4877.9      .1       0  4963.8     .05       0
    5030      .1       0  5189.4     .12       0  5291.2     .05       0
  5358.9     .12       0  5698.5     .04       0
Bank Sta=4963.8,5030
XS Rating Curve= 0 ,0
Exp/Cntr=0.3,0.1

Type RM Length L Ch R = 1 ,328596  ,645,645,645
BEGIN DESCRIPTION:
Mapping XS 1fa235d3
END DESCRIPTION:
XS GIS Cut Line= 3
       2428922.5     13534070.34      2428503.06     13532152.94
      2427792.76     13530629.65
#Sta/Elev= 30
    3007  283.88  3100.1  283.74  3250.4  284.31  3278.6  281.58  3394.7   281.2
  3498.6  280.35  3621.1  279.61  3658.4   279.9    4159  282.42  4307.3  280.22
  4390.3  278.97  4629.8  277.32  4711.7  267.89  4753.9  271.44  4793.1  271.23
  4841.7  268.02  4894.4  267.84  4957.4  265.21  4964.8  257.07  4966.3  256.07
    5031  257.07  5033.7  266.26  5094.8  275.07  5168.9  275.45  5305.3  270.79
  5762.6  282.15  5975.2  290.39  6201.4  301.79  6429.3  311.79  6650.5  310.18
#Mann= 17 ,-1 , 0
    3007     .12       0  3100.1     .05       0  3250.4     .04       0
  3394.7     .05       0  3498.6     .04       0  3621.1     .03       0
  3658.4     .04       0  4307.3     .05       0  4390.3     .04       0
  4793.1     .05       0  4894.4      .1       0  4964.8     .05       0
    5031      .1       0  5305.3     .04       0  5975.2     .03       0
  6201.4     .04       0  6429.3     .03       0
Bank Sta=4964.8,5031
XS Rating Curve= 0 ,0
Exp/Cntr=0.3,0.1

Type RM Length L Ch R = 1 ,327951  ,433,433,433
BEGIN DESCRIPTION:
Mapping XS 5eccda2b
END DESCRIPTION:
XS GIS Cut Line= 4
      2430172.19     13534943.37      2429162.16     13532443.97
      2429093.68     13532024.55      2427921.12      13530329.9
#Sta/Elev= 30
    2034  284.25  2149.9  284.39  2373.7  284.34  2743.1  279.77  2813.5  278.21
  2921.1  277.07    3659  277.26  3970.6  277.07  4748.4  270.63  4789.5  267.89
  4848.8  271.83  4890.8  265.66  4961.8  265.97  4969.1   256.2  4970.6   255.2
  5035.4   256.2  5050.7  267.04  5115.5  265.52    5167  273.94  5211.4  275.13
  5255.1  270.54    5433  275.27  5811.2  286.75  5882.6  288.55  5996.7  289.47
  6266.1  292.67  6431.9  294.08  6677.1  303.38  6950.9  313.67  7215.5  307.13
#Mann= 20 ,-1 , 0
    2034     .04       0  2149.9     .05       0  2373.7     .12       0
  2743.1     .12       0  2813.5     .05       0  2921.1     .04       0
    3659     .03       0  3970.6     .04       0  4748.4     .05       0
  4848.8      .1       0  4969.1     .05       0  5035.4      .1       0
    5167      .1       0  5255.1     .05       0    5433    .013       0
  5811.2     .04       0  5882.6    .013       0  5996.7     .04       0
  6266.1     .04       0  6677.1     .04       0
Bank Sta=4969.1,5035.4
XS Rating Curve= 0 ,0
Exp/Cntr=0.3,0.1

Type RM Length L Ch R = 1 ,327518  ,913,913,913
BEGIN DESCRIPTION:
Mapping XS cca26b49
END DESCRIPTION:
XS GIS Cut Line= 4
      2430745.69     13534797.86      2429641.51      13532820.6
      2429401.83     13531896.15      2428297.77     13530389.83
#Sta/Elev= 30
  2205.9  286.18  2649.2   285.2  2998.3  280.07  3142.8  276.41  3296.1  273.18
  3307.8  271.86  3748.8  278.91  4079.8  277.16  4108.2  276.92  4245.1  273.48
    4447  273.91  4458.8  274.06  4519.6  274.32  4701.2  266.49  4717.4  269.63
  4827.6  263.35  4920.6   265.9  4928.8  255.45  4930.3  254.45  4995.1  255.45
  5031.7   265.7  5072.3  266.89  5077.5  264.33  5096.2  269.04  5175.1  276.57
  5481.1  281.46  5767.5  281.68  6476.1  298.04  6818.8  300.98  7293.2  310.53
#Mann= 14 ,-1 , 0
  2205.9     .05       0  2998.3     .04       0  3142.8     .05       0
  3296.1     .04       0  3307.8     .05       0  3748.8     .04       0
  4079.8     .05       0  4108.2     .04       0    4447    .013       0
  4458.8     .04       0  4701.2      .1       0  4928.8     .05       0
  4995.1      .1       0  5175.1     .04       0
Bank Sta=4928.8,4995.1
XS Rating Curve= 0 ,0
Exp/Cntr=0.3,0.1

Type RM Length L Ch R = 1 ,326605  ,631,631,631
BEGIN DESCRIPTION:
Mapping XS 87f713c2
END DESCRIPTION:
XS GIS Cut Line= 5
      2430797.08     13534763.68      2430360.52      13533967.6
      2430052.37     13533325.62      2430180.77     13532144.38
      2428794.07     13530595.05
#Sta/Elev= 30
  2995.9  286.14    3415  284.88  3441.3   284.8  3658.5  283.31  3781.1  279.51
  3812.4  279.08  4061.6  272.92  4067.2  269.62  4089.8  269.53    4118  273.16
  4195.1  275.11  4434.9  278.24  4599.1  279.72  4731.9  275.93  4800.8  272.31
  4899.6  265.04  4963.9  261.97  4965.6  252.24  4967.1  251.24  5031.9  252.24
    5039  265.79  5109.4  262.99  5146.9  271.32  5196.1  272.03  5270.4  272.42
  5619.2  284.59    6254  300.05    6891   293.4  7649.1  313.54  7883.4  311.49
#Mann= 13 ,-1 , 0
  2995.9     .05       0    3415     .04       0  3441.3     .05       0
  3781.1     .04       0  3812.4     .05       0  4434.9     .04       0
  4731.9     .05       0  4800.8     .12       0  4899.6      .1       0
  4965.6     .05       0  5031.9      .1       0  5196.1     .05       0
  5619.2     .04       0
Bank Sta=4965.6,5031.9
XS Rating Curve= 0 ,0
Exp/Cntr=0.3,0.1

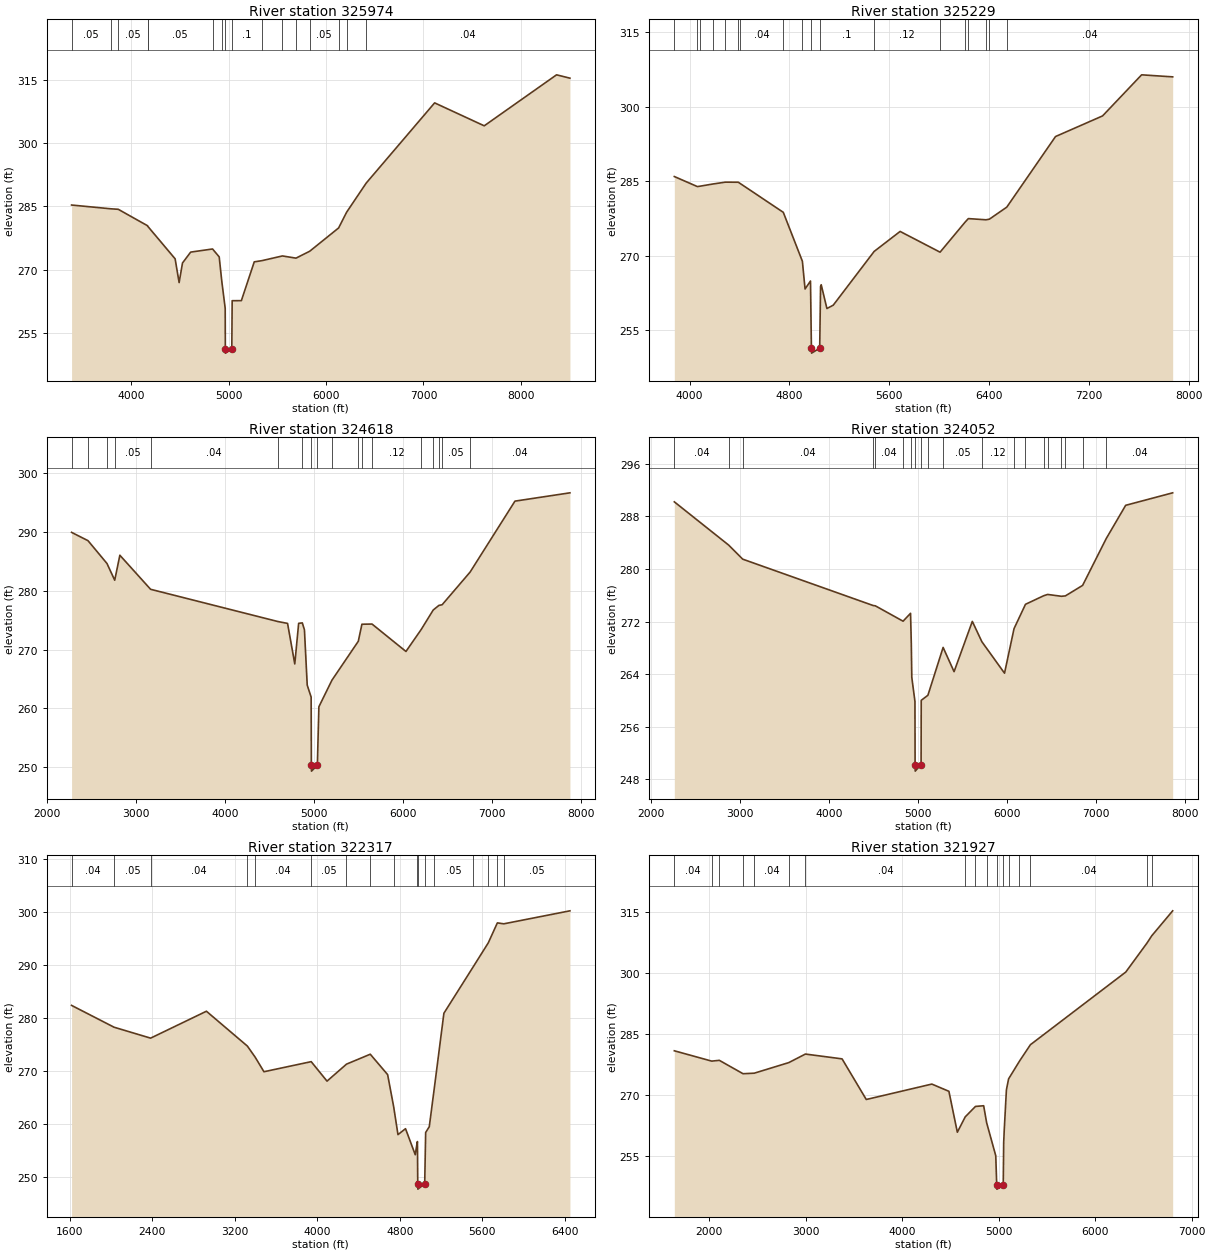
Type RM Length L Ch R = 1 ,325974  ,745,745,745
BEGIN DESCRIPTION:
Mapping XS 4befafc1
END DESCRIPTION:
XS GIS Cut Line= 4
      2430891.25     13534746.58      2430420.44     13534001.84
      2430797.07     13532426.85      2428990.97     13530535.16
#Sta/Elev= 30
    3388  285.34  3789.3  284.45  3867.1  284.33  4168.9  280.42    4170   280.3
  4450.9  272.59    4492  266.95  4526.6   271.6  4610.7  274.18  4835.1  274.92
  4903.3  273.05  4930.5  267.18    4965  260.83  4966.4  251.23  4967.9  250.23
  5032.7  251.23  5036.5  262.66  5130.9  262.67  5263.2  271.87  5341.3  272.15
  5552.1  273.27  5691.6  272.75  5832.9  274.39  6129.4  279.91  6211.4  283.64
  6412.7  290.55  7114.9  309.56  7624.1  304.12  8366.6  316.21  8503.9  315.42
#Mann= 16 ,-1 , 0
    3388     .05       0  3789.3     .04       0  3867.1     .05       0
  4168.9     .12       0    4170     .05       0  4835.1     .12       0
  4930.5      .1       0  4966.4     .05       0  5032.7      .1       0
  5341.3     .12       0  5552.1     .05       0  5691.6     .12       0
  5832.9     .05       0  6129.4     .04       0  6211.4     .05       0
  6412.7     .04       0
Bank Sta=4966.4,5032.7
XS Rating Curve= 0 ,0
Exp/Cntr=0.3,0.1

Type RM Length L Ch R = 1 ,325229  ,611,611,611
BEGIN DESCRIPTION:
Mapping XS 17514618
END DESCRIPTION:
XS GIS Cut Line= 4
      2430925.46     13534643.85      2431250.73     13533650.89
       2431045.3     13532358.38      2430035.25     13531065.85
#Sta/Elev= 30
  3877.5  285.95  4062.2  283.93  4081.8     284  4184.6  284.44  4287.3  284.82
  4390.1   284.8    4400  284.64  4750.9  278.75  4903.9  268.91  4925.2  263.33
  4968.8  264.94  4976.2  251.44  4977.7  250.44  5042.6  251.44  5049.6  263.86
  5054.7  264.19  5100.5  259.41  5151.1  260.08    5479  270.89  5687.1  274.91
  6007.3  270.74  6207.9  276.78    6234  277.49  6375.3  277.25  6402.7  277.38
  6542.1   279.8  6932.6  293.99  7309.7  298.14  7622.6   306.4  7871.5  305.99
#Mann= 18 ,-1 , 0
  3877.5     .05       0  4062.2     .12       0  4081.8     .04       0
  4184.6     .05       0  4287.3     .04       0  4390.1     .05       0
    4400     .04       0  4750.9     .05       0  4903.9      .1       0
  4976.2     .05       0  5042.6      .1       0    5479     .12       0
  6007.3     .05       0  6207.9     .03       0    6234     .05       0
  6375.3     .03       0  6402.7     .05       0  6542.1     .04       0
Bank Sta=4976.2,5042.6
XS Rating Curve= 0 ,0
Exp/Cntr=0.3,0.1

Type RM Length L Ch R = 1 ,324618  ,566,566,566
BEGIN DESCRIPTION:
Mapping XS c2a2fb21
END DESCRIPTION:
XS GIS Cut Line= 4
      2433726.89     13535298.27      2432012.84     13533795.84
      2431764.32      13533351.3      2430257.79     13530980.24
#Sta/Elev= 30
  2273.2  289.89  2457.7  288.48  2670.7  284.61  2757.7  281.77  2815.5  286.01
  3160.6  280.23  4589.9  274.76  4699.2  274.44  4780.3  267.56  4823.7  274.45
  4864.8  274.53  4888.8  273.35  4920.1  263.96  4964.2  261.93  4966.6  250.37
  4968.1  249.37  5033.9  250.37    5051  260.29  5197.6   264.8  5493.8  271.41
  5534.4   274.3    5648  274.33  6028.9  269.68  6199.6  273.39  6335.2  276.71
  6398.7  277.49  6435.7  277.61  6749.6  283.15  7253.4  295.19    7871   296.6
#Mann= 18 ,-1 , 0
  2273.2     .04       0  2457.7     .05       0  2670.7     .04       0
  2757.7     .05       0  3160.6     .04       0  4589.9     .05       0
  4864.8      .1       0  4966.6     .05       0  5033.9      .1       0
  5197.6     .05       0  5493.8     .12       0  5534.4     .05       0
    5648     .12       0  6199.6     .03       0  6335.2     .04       0
  6398.7     .03       0  6435.7     .05       0  6749.6     .04       0
Bank Sta=4966.6,5033.9
XS Rating Curve= 0 ,0
Exp/Cntr=0.3,0.1

Type RM Length L Ch R = 1 ,324052  ,1735,1735,1735
BEGIN DESCRIPTION:
Mapping XS b661ca86
END DESCRIPTION:
XS GIS Cut Line= 3
      2434149.58      13535071.2       2432235.1     13533085.95
      2430360.54      13530954.6
#Sta/Elev= 30
  2262.5  290.22  2873.6  283.63  3030.1   281.5  4496.4  274.44  4519.6   274.4
  4831.3  272.06  4915.1  273.26  4923.7  268.69  4929.2  263.53  4964.7  259.84
  4966.3  250.25  4967.8  249.25  5033.6  250.25  5035.1  260.02  5110.2  260.79
    5281  268.07    5404  264.38    5609  272.03  5716.1  268.94  5970.5  264.15
  6077.5  270.93    6206  274.63    6410  275.93  6454.2  276.13    6610  275.85
  6654.2  275.91  6847.7  277.51  7112.3  284.62    7331  289.69  7858.9  291.59
#Mann= 20 ,-1 , 0
  2262.5     .04       0  2873.6     .03       0  3030.1     .04       0
  4496.4     .05       0  4519.6     .04       0  4831.3     .12       0
  4923.7      .1       0  4966.3     .05       0  5033.6      .1       0
  5110.2     .12       0    5281     .05       0  5716.1     .12       0
  6077.5     .03       0    6206     .04       0    6410     .03       0
  6454.2     .04       0    6610     .05       0  6654.2     .04       0
  6847.7     .05       0  7112.3     .04       0
Bank Sta=4966.3,5033.6
XS Rating Curve= 0 ,0
Exp/Cntr=0.3,0.1

Type RM Length L Ch R = 1 ,322317  ,390,390,390
BEGIN DESCRIPTION:
Mapping XS 1de50bc5
END DESCRIPTION:
XS GIS Cut Line= 3
      2433892.14     13534468.39      2432098.15       13531588.
      2431165.11     13530492.33
#Sta/Elev= 30
  1616.3  282.35  2028.1  278.24  2382.7  276.18  2923.8  281.25  3320.7  274.69
    3396  272.61  3481.7  269.85  3939.8  271.75  4093.3  268.08  4282.1  271.28
  4512.6  273.15    4681  269.31  4739.2  263.29  4781.3     258  4854.5  259.12
  4948.9  254.21  4966.8  256.45  4970.2  256.69    4973  248.73  4974.5  247.73
  5040.5  248.73  5049.8   258.4  5084.9  259.49  5133.9   266.8  5226.6  280.87
  5509.6  289.58  5657.4  294.15  5745.1   297.9  5807.3  297.72  6448.8  300.17
#Mann= 17 ,-1 , 0
  1616.3     .04       0  2028.1     .05       0  2382.7     .04       0
  3320.7     .05       0    3396     .04       0  3939.8     .05       0
  4282.1     .04       0  4512.6     .05       0  4739.2     .12       0
  4966.8      .1       0    4973     .05       0  5040.5      .1       0
  5133.9     .05       0  5509.6     .04       0  5657.4     .05       0
  5745.1     .04       0  5807.3     .05       0
Bank Sta=4973,5040.5
XS Rating Curve= 0 ,0
Exp/Cntr=0.3,0.1

Type RM Length L Ch R = 1 ,321927  ,678,678,678
BEGIN DESCRIPTION:
Mapping XS ecfe9cd4
END DESCRIPTION:
XS GIS Cut Line= 4
      2434027.55     13534381.56      2432414.86     13531408.25
      2432098.15     13530809.07      2431439.93     13529920.05
#Sta/Elev= 30
    1637  280.87  2024.5  278.34  2103.6  278.53  2349.5  275.25  2465.6  275.38
  2824.3  277.98  2995.9  280.07    3376  278.89    3627  268.93  4306.5  272.71
  4483.6  270.94    4571  260.91  4652.7  264.67  4758.9  267.23  4843.9   267.4
  4874.8  263.23  4969.4  255.14  4979.4  247.96  4980.9  246.96  5046.9  247.96
  5051.4  258.29  5057.1  261.36  5079.7  271.28  5102.2  273.98  5215.4  278.34
  5328.6  282.36  6317.1  300.17    6536  307.24  6586.8  309.07  6803.4  315.18
#Mann= 17 ,-1 , 0
    1637     .04       0  2024.5     .05       0  2103.6     .12       0
  2349.5     .05       0  2465.6     .04       0  2824.3     .05       0
  2995.9     .04       0  4652.7     .12       0  4758.9     .05       0
  4874.8      .1       0  4979.4     .05       0  5046.9      .1       0
  5102.2     .03       0  5215.4     .05       0  5328.6     .04       0
    6536     .05       0  6586.8     .04       0
Bank Sta=4979.4,5046.9
XS Rating Curve= 0 ,0
Exp/Cntr=0.3,0.1