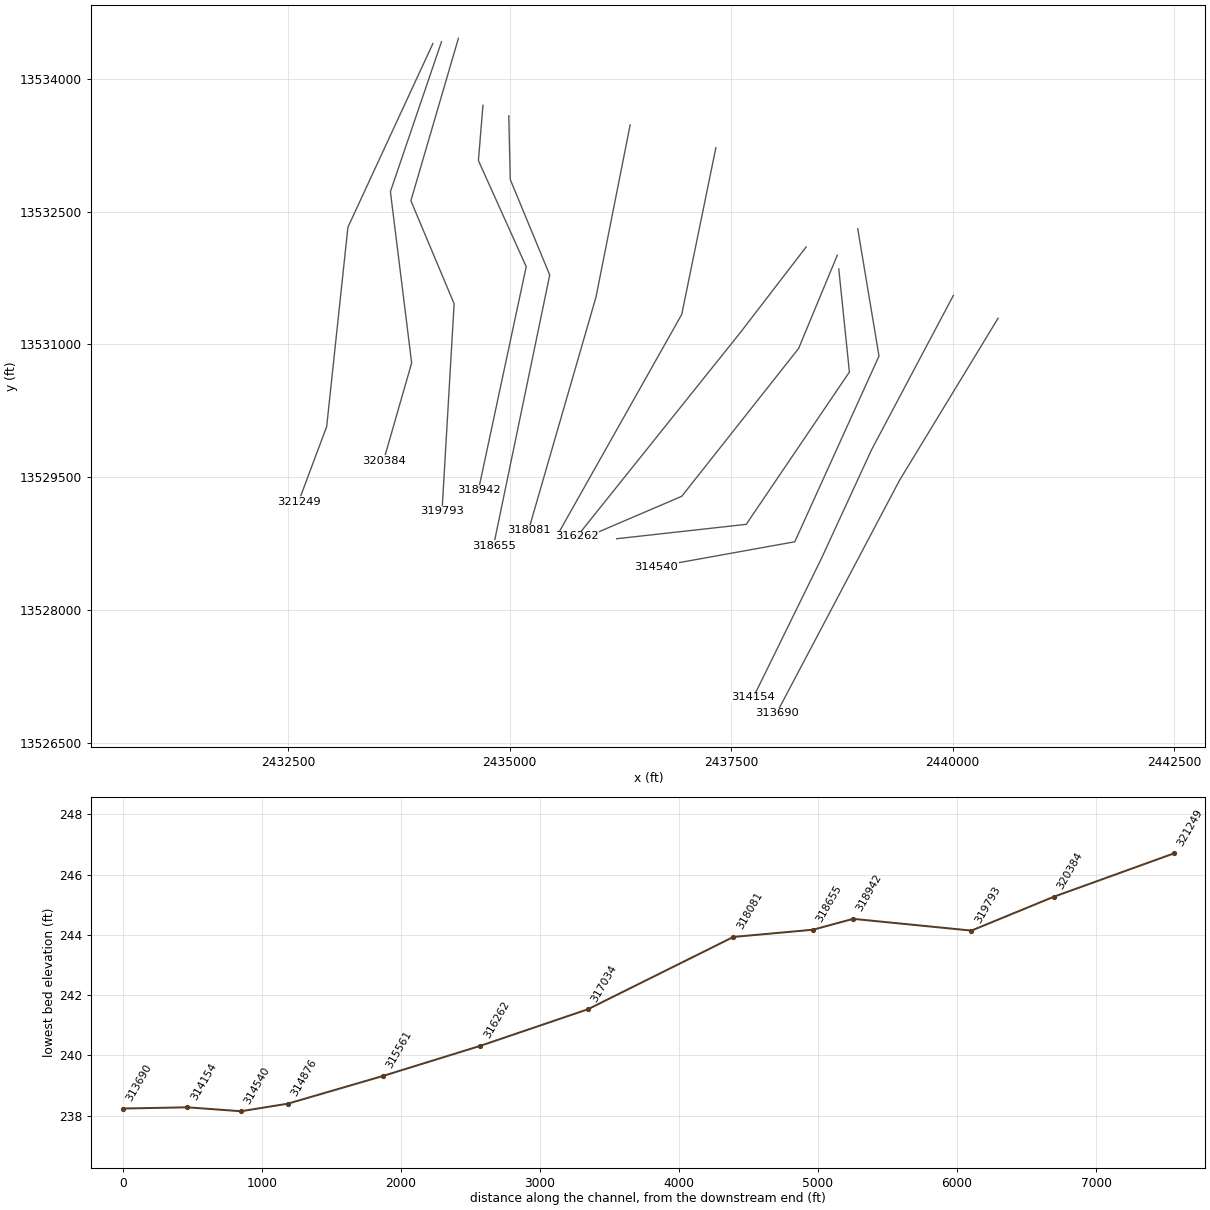
HEC-RAS study COLETO CREEK.prj: COLETO CREEK Base Level Engineering

--- COLETO CREEK.g01 (geometry) --- (continued)

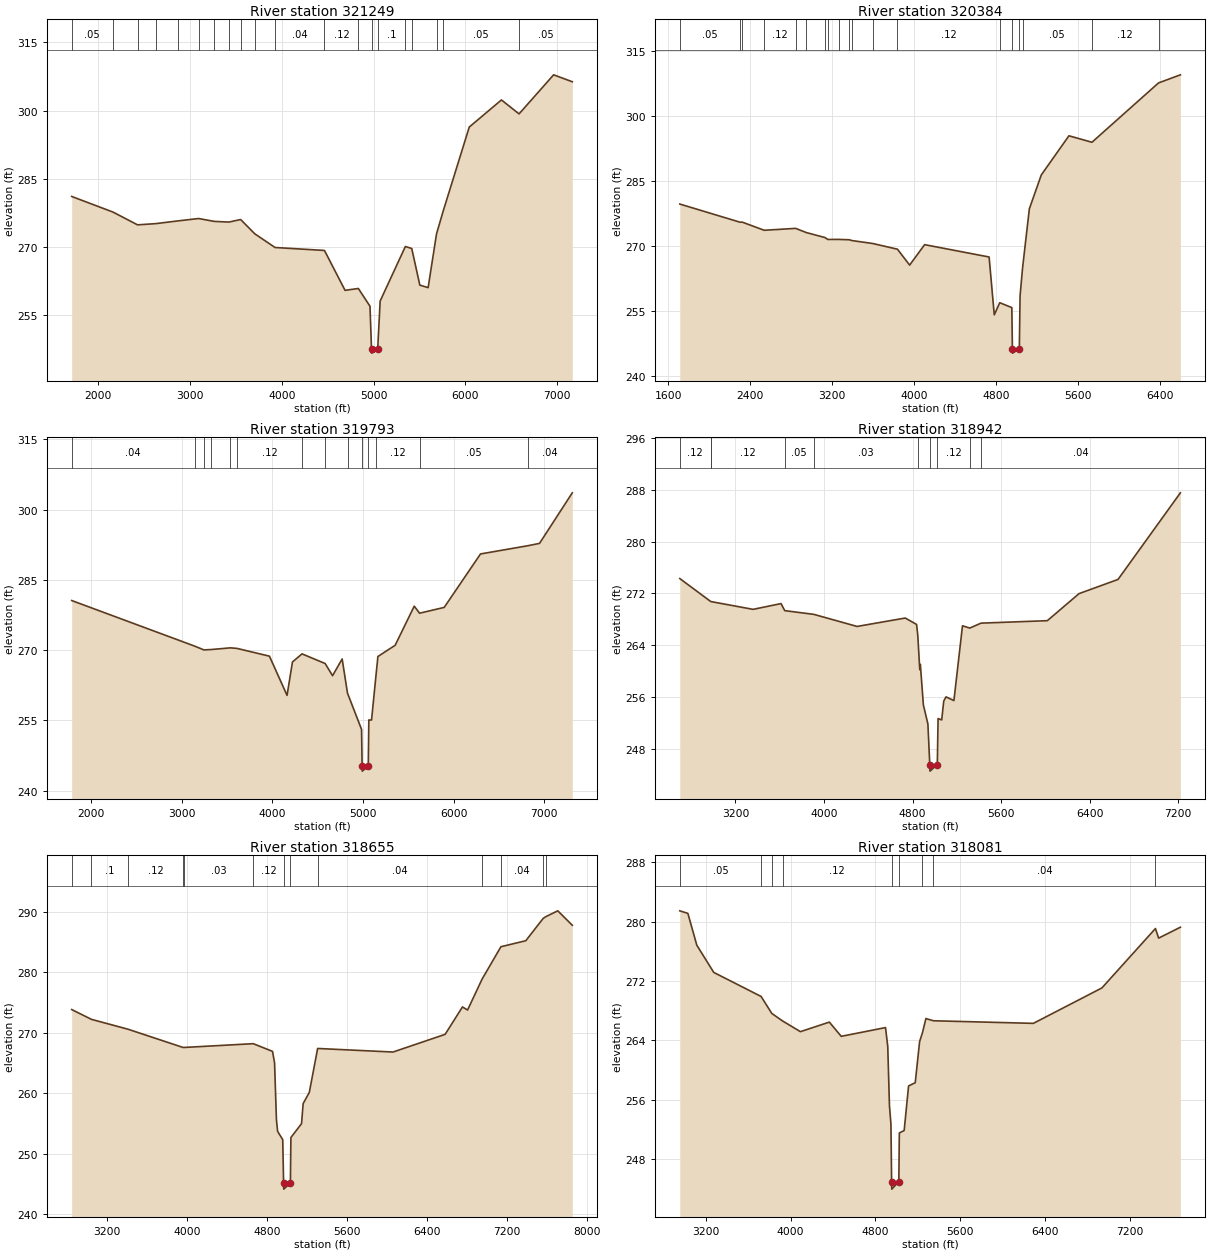
Type RM Length L Ch R = 1 ,321249  ,865,865,865
BEGIN DESCRIPTION:
Mapping XS 15596095
END DESCRIPTION:
XS GIS Cut Line= 4
      2434135.19     13534398.92      2433176.67     13532324.14
        2432937.     13530072.93      2432620.28      13529225.5
#Sta/Elev= 30
  1709.8  281.14  2158.3  277.72  2427.4   274.9  2626.9  275.17  2872.7  275.78
  3092.8  276.29  3263.2  275.66  3422.9  275.51  3550.4  276.07  3704.7  272.93
  3925.5  269.92  4463.8  269.27  4688.3   260.5    4833  260.91  4959.8  257.01
  4976.3   247.7  4977.8   246.7  5043.9   247.7  5070.5  258.15  5345.3  270.14
  5414.8   269.7  5502.9  261.65  5593.4   261.1  5684.5   272.9  5757.1  277.92
  6041.4   296.4    6392  302.36  6583.9  299.29  6960.5  307.88  7163.9  306.36
#Mann= 20 ,-1 , 0
  1709.8     .05       0  2158.3     .12       0  2427.4     .12       0
  2626.9     .04       0  2872.7     .05       0  3092.8     .04       0
  3263.2     .04       0  3422.9     .05       0  3550.4     .05       0
  3704.7     .04       0  3925.5     .04       0  4463.8     .12       0
    4833      .1       0  4976.3     .05       0  5043.9      .1       0
  5345.3     .12       0  5414.8      .1       0  5684.5     .12       0
  5757.1     .05       0  6583.9     .05       0
Bank Sta=4976.3,5043.9
XS Rating Curve= 0 ,0
Exp/Cntr=0.3,0.1

Type RM Length L Ch R = 1 ,320384  ,591,591,591
BEGIN DESCRIPTION:
Mapping XS 69ec2c4b
END DESCRIPTION:
XS GIS Cut Line= 4
       2434232.4     13534419.72      2433656.02     13532726.44
      2433895.69     13530791.95      2433578.98     13529687.75
#Sta/Elev= 30
  1714.1  279.69  2304.7  275.48  2322.9  275.52  2538.4  273.63  2844.9  274.07
  2949.7   273.1  3130.1  271.96    3160  271.51  3265.2  271.52  3370.3  271.44
  3390.5  271.27  3597.2  270.58  3839.1  269.26  3957.7  265.59  4104.2  270.31
  4733.6  267.46    4784  254.11  4837.5   256.9  4955.3  255.78    4961  246.26
  4962.5  245.26  5028.6  246.26  5035.9  258.52  5060.8  265.06  5126.6  278.59
  5242.8   286.4  5512.8  295.45  5737.6  293.96  6387.5  307.66  6600.8  309.53
#Mann= 19 ,-1 , 0
  1714.1     .05       0  2304.7     .12       0  2322.9     .05       0
  2538.4     .12       0  2844.9     .04       0  2949.7     .05       0
  3130.1     .04       0    3160     .05       0  3265.2     .04       0
  3370.3     .05       0  3390.5     .12       0  3597.2     .05       0
  3839.1     .12       0  4837.5      .1       0    4961     .05       0
  5028.6      .1       0  5060.8     .05       0  5737.6     .12       0
  6387.5     .04       0
Bank Sta=4961,5028.6
XS Rating Curve= 0 ,0
Exp/Cntr=0.3,0.1

Type RM Length L Ch R = 1 ,319793  ,851,851,851
BEGIN DESCRIPTION:
Mapping XS 01737f3c
END DESCRIPTION:
XS GIS Cut Line= 4
      2434423.37     13534457.92      2433887.13     13532623.73
      2434375.03     13531459.61      2434238.08     13529114.21
#Sta/Elev= 30
  1786.3  280.59  3141.2  270.86  3244.8  270.04  3326.3  270.12  3536.8  270.48
  3610.2  270.36  3967.9   268.7  4162.1  260.33  4221.9  267.47  4327.4  269.19
  4582.4  267.13  4664.1  264.53  4770.1   268.1    4829   260.8  4984.2  253.05
  4990.4  245.14  4991.9  244.14    5058  245.14  5064.3  255.07  5094.3  255.06
  5142.8   264.5  5164.5  268.63  5354.8  271.03  5565.3  279.39  5624.1  277.88
  5895.7  279.12  6296.4  290.54  6816.6  292.29  6947.5   292.8  7308.9   303.6
#Mann= 14 ,-1 , 0
  1786.3     .04       0  3141.2     .12       0  3244.8     .05       0
  3326.3     .12       0  3536.8     .05       0  3610.2     .12       0
  4327.4     .05       0  4582.4     .12       0    4829      .1       0
  4990.4     .05       0    5058      .1       0  5142.8     .12       0
  5624.1     .05       0  6816.6     .04       0
Bank Sta=4990.4,5058
XS Rating Curve= 0 ,0
Exp/Cntr=0.3,0.1

Type RM Length L Ch R = 1 ,318942  ,287,287,287
BEGIN DESCRIPTION:
Mapping XS 39bf4631
END DESCRIPTION:
XS GIS Cut Line= 4
       2434700.3     13533702.27      2434648.94     13533077.39
      2435188.21     13531879.03      2434648.95     13529353.96
#Sta/Elev= 30
  2696.9  274.28  2977.4  270.72  2978.6  270.72  3359.4  269.52  3611.6  270.41
  3645.2  269.32    3907  268.75  4299.1  266.88  4734.1  268.18  4836.4  267.19
  4847.1  265.56  4865.4  260.18  4870.5  261.02  4897.8  254.77  4938.7  251.81
  4955.8  245.53  4957.3  244.53  5023.7  245.53  5030.7  252.65  5063.4  252.44
  5081.8  255.35  5102.3     256  5173.8  255.43  5251.2  266.98  5317.2  266.63
  5418.7  267.39  6017.7  267.77  6304.5  271.95  6656.5  274.14    7220  287.52
#Mann= 10 ,-1 , 0
  2696.9     .12       0  2977.4     .05       0  2978.6     .12       0
  3645.2     .05       0    3907     .03       0  4847.1     .12       0
  4955.8     .05       0  5023.7     .12       0  5317.2     .05       0
  5418.7     .04       0
Bank Sta=4955.8,5023.7
XS Rating Curve= 0 ,0
Exp/Cntr=0.3,0.1

Type RM Length L Ch R = 1 ,318655  ,574,574,574
BEGIN DESCRIPTION:
Mapping XS 6b083629
END DESCRIPTION:
XS GIS Cut Line= 4
      2434991.33     13533582.44      2435008.45      13532863.4
      2435453.56     13531784.87      2434820.24     13528729.53
#Sta/Elev= 30
  2848.6  273.84  3045.8  272.22    3412  270.59  3961.5  267.58  3976.4  267.58
  4664.4   268.2    4857  266.93  4877.5  265.02  4896.4  255.58  4908.1  253.72
  4959.2  252.33  4967.8  245.17  4969.3  244.17  5035.7  245.17  5040.9   252.7
  5147.2  254.99  5163.4  258.31  5224.7  260.14  5308.3  267.41  6062.1  266.82
    6583  269.74  6756.6  274.27  6807.6  273.76  6952.3  278.85  7141.3  284.22
  7389.8  285.21  7563.9   288.9  7590.5  289.19  7709.9  290.15  7854.9  287.77
#Mann= 13 ,-1 , 0
  2848.6     .12       0  3045.8      .1       0    3412     .12       0
  3961.5     .05       0  3976.4     .03       0  4664.4     .12       0
  4967.8     .05       0  5035.7     .12       0  5308.3     .04       0
  6952.3     .03       0  7141.3     .04       0  7563.9     .05       0
  7590.5     .04       0
Bank Sta=4967.8,5035.7
XS Rating Curve= 0 ,0
Exp/Cntr=0.3,0.1

Type RM Length L Ch R = 1 ,318081  ,1047,1047,1047
BEGIN DESCRIPTION:
Mapping XS cb50a0e2
END DESCRIPTION:
XS GIS Cut Line= 3
      2436360.89      13533479.7       2435975.7     13531536.64
      2435213.89     13528900.27
#Sta/Elev= 30
  2954.8  281.47    3031  281.13  3115.6  276.83  3275.6  273.16  3722.2  269.92
  3823.3  267.63  3924.4  266.62  4093.5  265.17  4366.4  266.46  4478.6  264.54
  4896.6  265.72  4917.8   263.2    4934  255.16  4947.8   252.7  4954.3  244.93
  4955.8  243.93  5022.2  244.93  5027.1   251.5  5072.7  251.84  5114.3  257.85
  5177.2  258.28  5218.4  263.83  5245.5  265.04    5278  266.94    5349  266.64
  6292.4  266.29  6939.3  271.07  7444.4  279.08  7474.9  277.79  7679.9  279.26
#Mann= 9 ,-1 , 0
  2954.8     .05       0  3722.2     .12       0  3823.3     .05       0
  3924.4     .12       0  4954.3     .05       0  5022.2     .12       0
  5245.5     .05       0    5349     .04       0  7444.4     .05       0
Bank Sta=4954.3,5022.2
XS Rating Curve= 0 ,0
Exp/Cntr=0.3,0.1

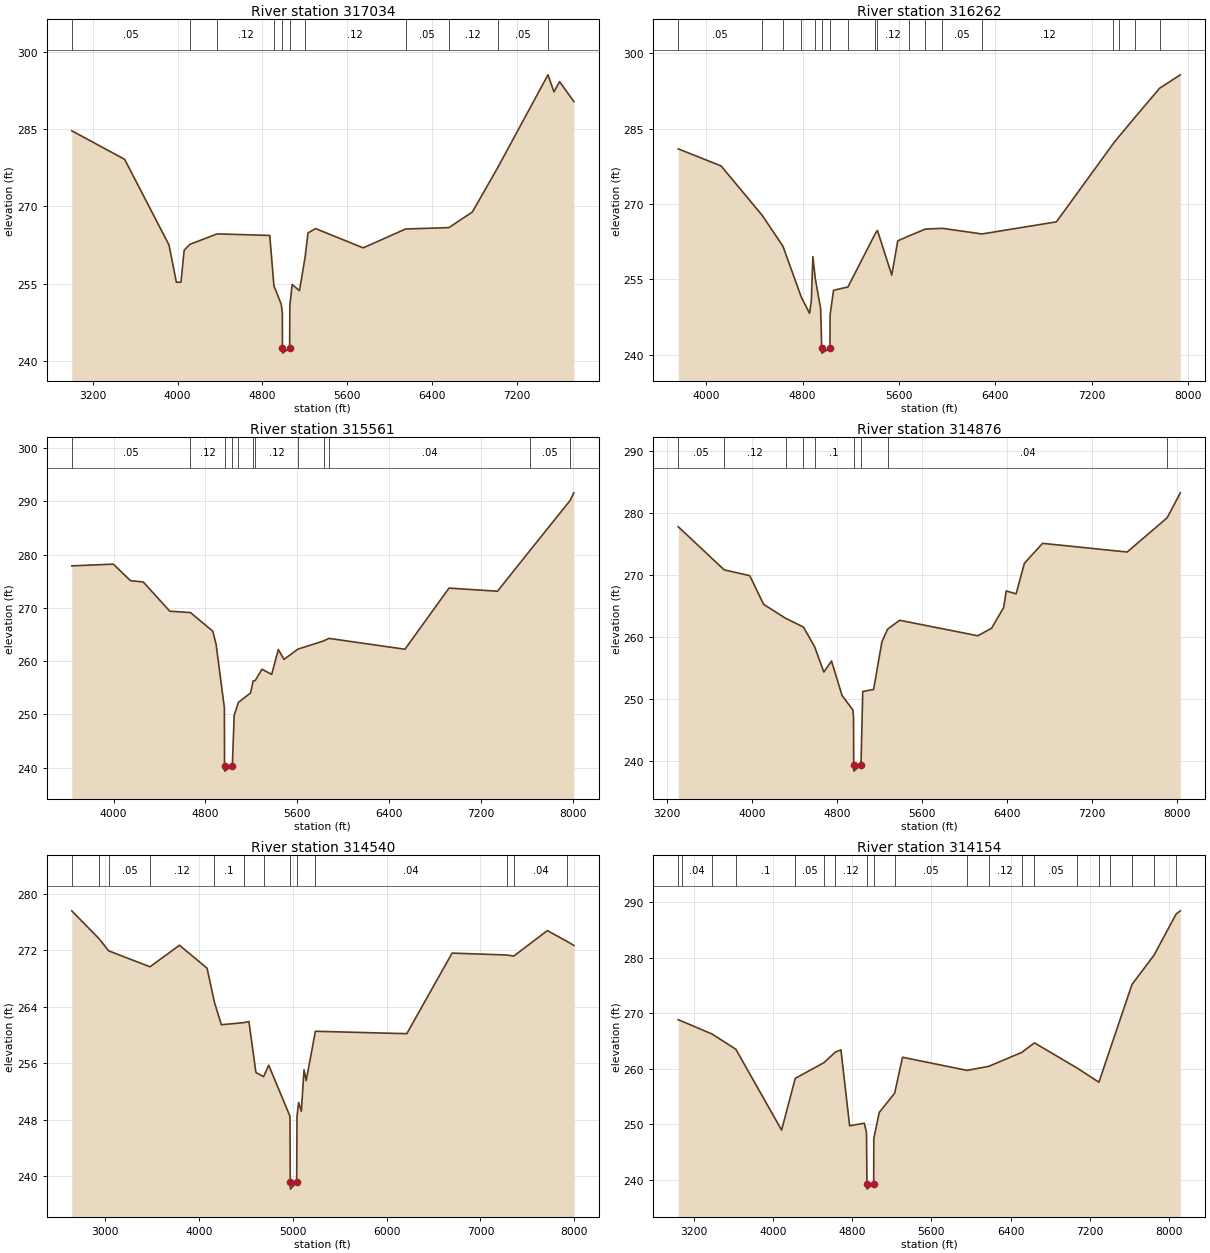
Type RM Length L Ch R = 1 ,317034  ,772,772,772
BEGIN DESCRIPTION:
Mapping XS 9a3287f7
END DESCRIPTION:
XS GIS Cut Line= 3
      2437328.13     13533222.89      2436942.95     13531339.77
      2435564.85     13528891.72
#Sta/Elev= 30
  3003.4  284.68  3501.4  279.15  3919.9  262.51  3989.2  255.28  4032.2   255.3
  4062.8  261.51  4116.3  262.64  4373.4  264.67  4869.1  264.37  4908.5   254.6
  4977.5  250.99  4987.7  249.38  4988.8  242.53  4990.3  241.53  5056.7  242.53
  5058.4  250.72  5080.2  254.84    5149  253.66  5201.6  260.05  5229.4  264.85
  5301.2   265.7  5749.2  261.96  6149.5  265.62  6557.6  265.89  6778.6  268.92
  7018.3  277.56  7491.1  295.54  7547.4  292.24  7600.5  294.22  7734.8  290.35
#Mann= 11 ,-1 , 0
  3003.4     .05       0  4116.3      .1       0  4373.4     .12       0
  4908.5      .1       0  4988.8     .05       0  5056.7      .1       0
  5201.6     .12       0  6149.5     .05       0  6557.6     .12       0
  7018.3     .05       0  7491.1     .04       0
Bank Sta=4988.8,5056.7
XS Rating Curve= 0 ,0
Exp/Cntr=0.3,0.1

Type RM Length L Ch R = 1 ,316262  ,701,701,701
BEGIN DESCRIPTION:
Mapping XS 5e2f30b8
END DESCRIPTION:
XS GIS Cut Line= 3
      2438346.75     13532101.59      2437610.61      13531142.9
      2435761.71     13528831.77
#Sta/Elev= 30
  3768.3  280.96  4123.8  277.57  4465.2  267.74  4637.4  261.61  4789.4   251.5
  4858.8  248.23  4873.3  250.73  4886.1  259.51  4906.4   255.1  4950.3  249.23
  4959.8  241.32  4961.3  240.32  5027.8  241.32    5029  247.92  5057.8  252.83
  5177.3  253.48  5404.4  264.11  5422.1  264.74  5541.2  255.85  5590.9  262.66
  5680.1   263.6  5819.9     265  5961.7  265.15  6290.2  264.03  6908.1  266.44
    7379  281.98  7424.7  283.34    7562  287.29  7766.2  293.05  7936.7  295.69
#Mann= 18 ,-1 , 0
  3768.3     .05       0  4465.2     .12       0  4637.4      .1       0
  4789.4     .12       0  4906.4      .1       0  4959.8     .05       0
  5027.8      .1       0  5177.3     .12       0  5404.4     .05       0
  5422.1     .12       0  5680.1     .05       0  5819.9     .04       0
  5961.7     .05       0  6290.2     .12       0    7379     .05       0
  7424.7     .12       0    7562     .05       0  7766.2     .04       0
Bank Sta=4959.8,5027.8
XS Rating Curve= 0 ,0
Exp/Cntr=0.3,0.1

Type RM Length L Ch R = 1 ,315561  ,685,685,685
BEGIN DESCRIPTION:
Mapping XS 14c6dc25
END DESCRIPTION:
XS GIS Cut Line= 4
      2438697.69     13532007.42      2438261.15     13530954.58
      2436942.95     13529285.44      2435925.59     13528849.43
#Sta/Elev= 30
  3635.2  277.89  3997.6  278.21  4146.3  275.11    4258  274.86  4489.2  269.37
  4669.2  269.11  4863.7  265.61  4892.6  263.13  4964.8  251.18    4966  240.32
  4967.5  239.32  5034.2  240.32  5049.7  249.77  5086.5  252.22  5192.4  254.01
    5215  256.26  5233.1  256.33  5291.8  258.47  5376.7  257.49  5434.5  262.16
  5484.2  260.31  5604.6  262.24  5828.4  263.78  5875.5  264.26  6537.4  262.22
  6921.4  273.71  7343.7  273.12  7627.8  280.81  7975.5  290.15  8008.7  291.61
#Mann= 12 ,-1 , 0
  3635.2     .05       0  4669.2     .12       0    4966     .05       0
  5034.2     .12       0  5086.5     .12       0    5215     .05       0
  5233.1     .12       0  5604.6     .04       0  5828.4     .05       0
  5875.5     .04       0  7627.8     .05       0  7975.5     .04       0
Bank Sta=4966,5034.2
XS Rating Curve= 0 ,0
Exp/Cntr=0.3,0.1

Type RM Length L Ch R = 1 ,314876  ,336,336,336
BEGIN DESCRIPTION:
Mapping XS 7a31f2be
END DESCRIPTION:
XS GIS Cut Line= 4
      2438714.81     13531853.36      2438834.65     13530689.23
      2437670.53     13528968.73      2436208.44     13528806.27
#Sta/Elev= 30
  3308.4  277.83  3740.8  270.87  3980.3  269.94    4111  265.31  4317.9  263.06
  4485.3  261.64  4590.2  258.47    4677  254.38    4749  256.17    4848  250.61
  4949.8  248.27  4955.8   247.1  4957.7   239.4  4959.2   238.4  5025.9   239.4
  5042.7  251.25  5144.5  251.58  5222.5  259.26  5276.3  261.31  5389.3  262.74
  6124.2  260.24  6253.1  261.45  6367.3  264.81  6390.9  267.47  6483.8     267
  6561.6  271.93  6732.6  275.15  7527.5  273.75  7903.6  279.28  8027.1   283.3
#Mann= 9 ,-1 , 0
  3308.4     .05       0  3740.8     .12       0  4317.9      .1       0
  4485.3     .12       0  4590.2      .1       0  4957.7     .05       0
  5025.9      .1       0  5276.3     .04       0  7903.6     .05       0
Bank Sta=4957.7,5025.9
XS Rating Curve= 0 ,0
Exp/Cntr=0.3,0.1

Type RM Length L Ch R = 1 ,314540  ,386,386,386
BEGIN DESCRIPTION:
Mapping XS eb5a942b
END DESCRIPTION:
XS GIS Cut Line= 4
       2438928.8     13532307.05      2439168.48     13530868.98
      2438218.35     13528771.85      2436653.62     13528489.69
#Sta/Elev= 30
    2645  277.59  2938.3  273.61  3037.8  271.92  3478.8  269.66  3792.7  272.71
  4086.7  269.46  4165.8  264.61    4239  261.45  4476.2  261.74  4532.7   261.9
  4607.4  254.68  4689.1  254.09    4744  255.71  4970.3  248.47  4973.4  239.15
  4974.9  238.15  5041.6  239.15  5045.1  248.46  5062.4  250.43  5091.3  249.17
  5119.9  255.07    5143  253.53  5241.1  260.52  6215.1  260.18  6697.8   271.6
  7280.2  271.33  7355.4  271.18    7713  274.79  7920.9  273.27  7995.2  272.69
#Mann= 13 ,-1 , 0
    2645     .05       0  2938.3     .12       0  3037.8     .05       0
  3478.8     .12       0  4165.8      .1       0  4476.2     .12       0
  4689.1      .1       0  4973.4     .05       0  5041.6      .1       0
  5241.1     .04       0  7280.2     .05       0  7355.4     .04       0
  7920.9     .05       0
Bank Sta=4973.4,5041.6
XS Rating Curve= 0 ,0
Exp/Cntr=0.3,0.1

Type RM Length L Ch R = 1 ,314154  ,464,464,464
BEGIN DESCRIPTION:
Mapping XS 1ad0420e
END DESCRIPTION:
XS GIS Cut Line= 4
      2440007.34     13531553.77      2439082.88     13529807.58
       2438522.3     13528590.33      2437751.41     13527016.08
#Sta/Elev= 30
  3044.1  268.82  3077.2  268.57  3385.5  266.24  3625.9  263.49  4087.5  248.92
  4225.5  258.24  4515.8  261.08    4629  262.96  4686.6  263.38  4774.6  249.69
  4922.9  250.17  4944.9  248.42  4949.2  239.28  4950.7  238.28  5017.4  239.28
  5018.5  247.39  5073.4   252.1  5228.9  255.57  5308.6  262.05  5960.2  259.68
  6180.1  260.42  6511.9  262.92  6640.5  264.64  7068.6  260.13  7291.2  257.55
  7407.7  263.71  7625.2  275.17  7847.9  280.46  8070.6  287.86  8112.9  288.44
#Mann= 20 ,-1 , 0
  3044.1     .03       0  3077.2     .04       0  3385.5     .05       0
  3625.9      .1       0  4225.5     .05       0  4515.8     .12       0
    4629     .12       0  4949.2     .05       0  5017.4      .1       0
  5228.9     .05       0  5960.2     .05       0  6180.1     .12       0
  6511.9    .013       0  6640.5     .05       0  7068.6     .12       0
  7291.2     .12       0  7407.7     .03       0  7625.2     .04       0
  7847.9     .05       0  8070.6     .03       0
Bank Sta=4949.2,5017.4
XS Rating Curve= 0 ,0
Exp/Cntr=0.3,0.1

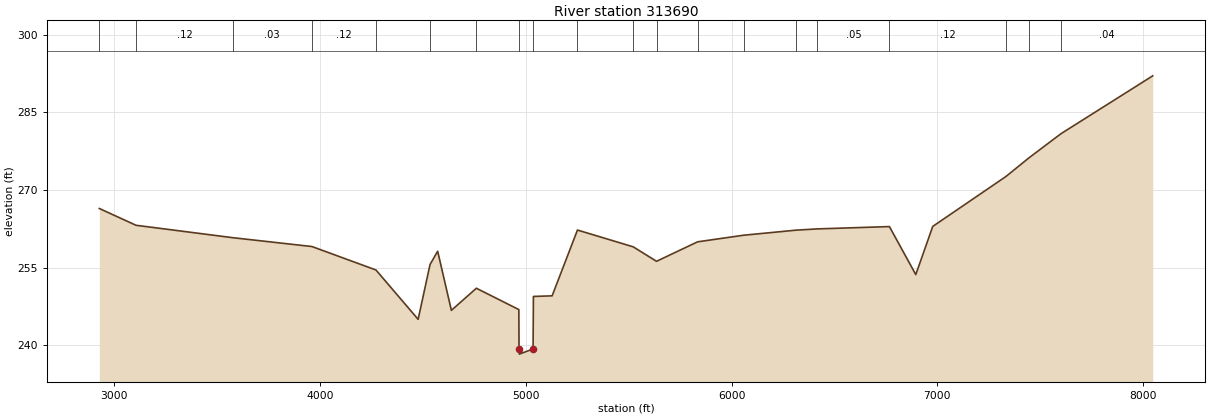
Type RM Length L Ch R = 1 ,313690  ,376,376,376
BEGIN DESCRIPTION:
Mapping XS e1425907
END DESCRIPTION:
XS GIS Cut Line= 3
      2440512.33     13531296.94      2439399.59     13529465.19
      2438011.81     13526833.76
#Sta/Elev= 30
  2928.3  266.42  3106.7  263.17  3576.3  260.77  3961.1  259.06  4272.4  254.52
  4477.3  244.97  4535.1  255.58  4572.2  258.15  4638.8  246.71  4760.2  250.99
  4966.5  246.86  4967.5  239.24    4969  238.24  5035.7  239.24  5037.4   249.4
  5128.3  249.52  5251.4  262.25  5522.3     259  5635.5   256.2  5835.1  259.97
  6059.4  261.25  6314.5  262.23    6417  262.47  6767.1  262.92  6895.2  253.63
  6977.6  262.95  7332.9   272.6  7446.1  276.25  7600.6  280.89  8046.5  292.09
#Mann= 20 ,-1 , 0
  2928.3     .03       0  3106.7     .12       0  3576.3     .03       0
  3961.1     .12       0  4272.4      .1       0  4535.1     .12       0
  4760.2      .1       0  4967.5     .05       0  5035.7      .1       0
  5251.4     .05       0  5522.3     .12       0  5635.5     .04       0
  5835.1     .04       0  6059.4     .05       0  6314.5    .013       0
    6417     .05       0  6767.1     .12       0  7332.9     .12       0
  7446.1     .05       0  7600.6     .04       0
Bank Sta=4967.5,5035.7
XS Rating Curve= 0 ,0
Exp/Cntr=0.3,0.1