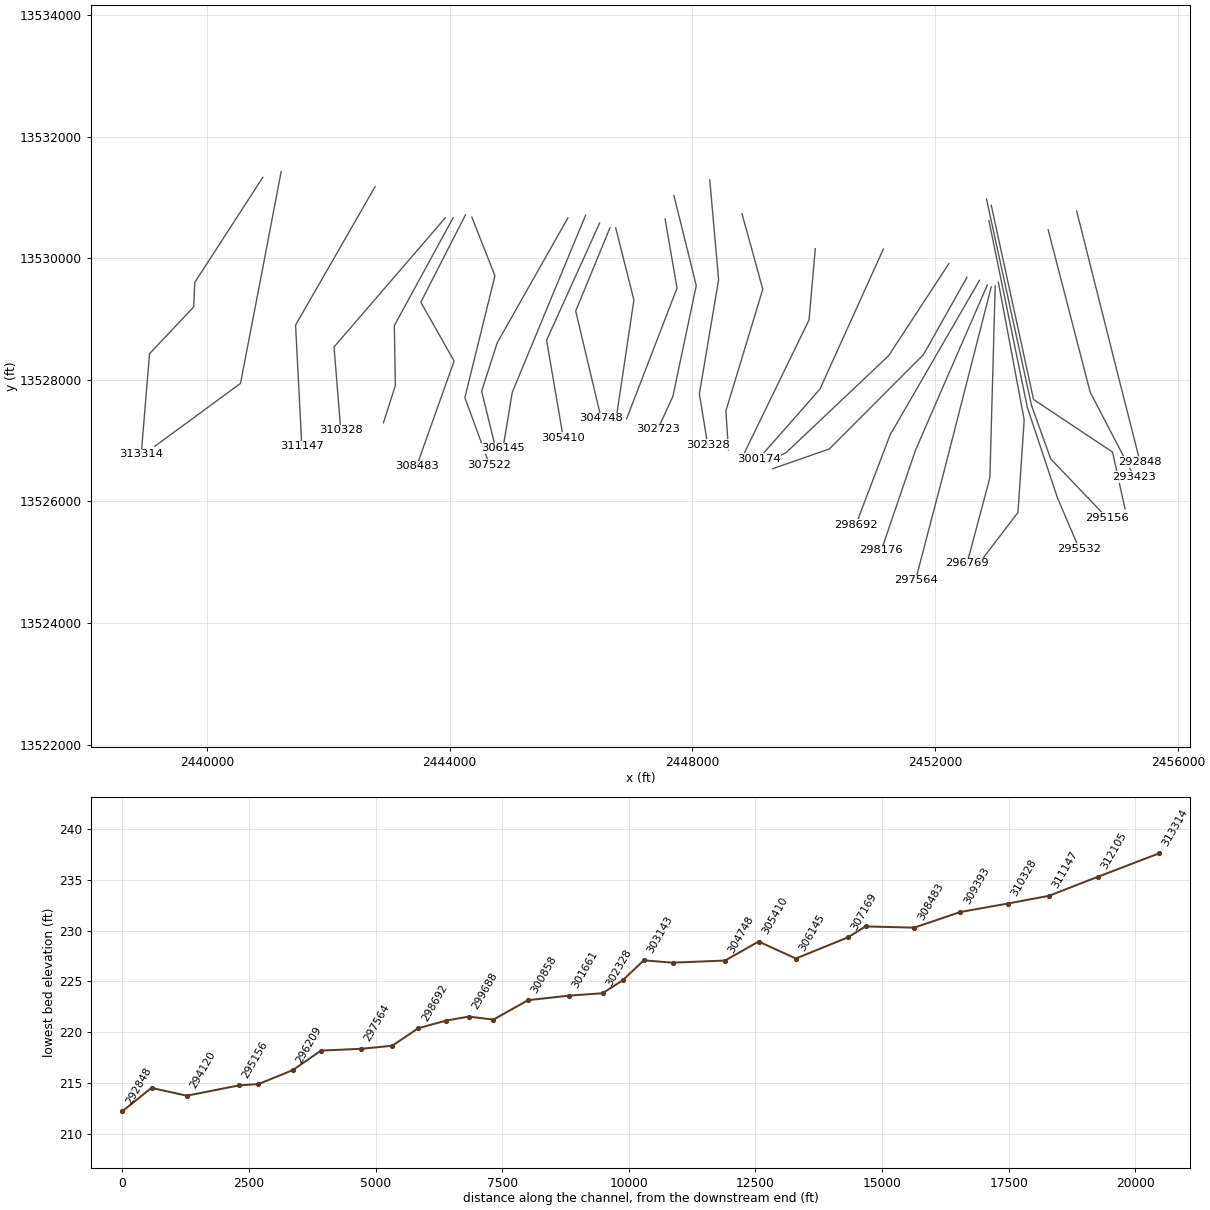
HEC-RAS study COLETO CREEK.prj: COLETO CREEK Base Level Engineering

--- COLETO CREEK.g01 (geometry) --- (continued)

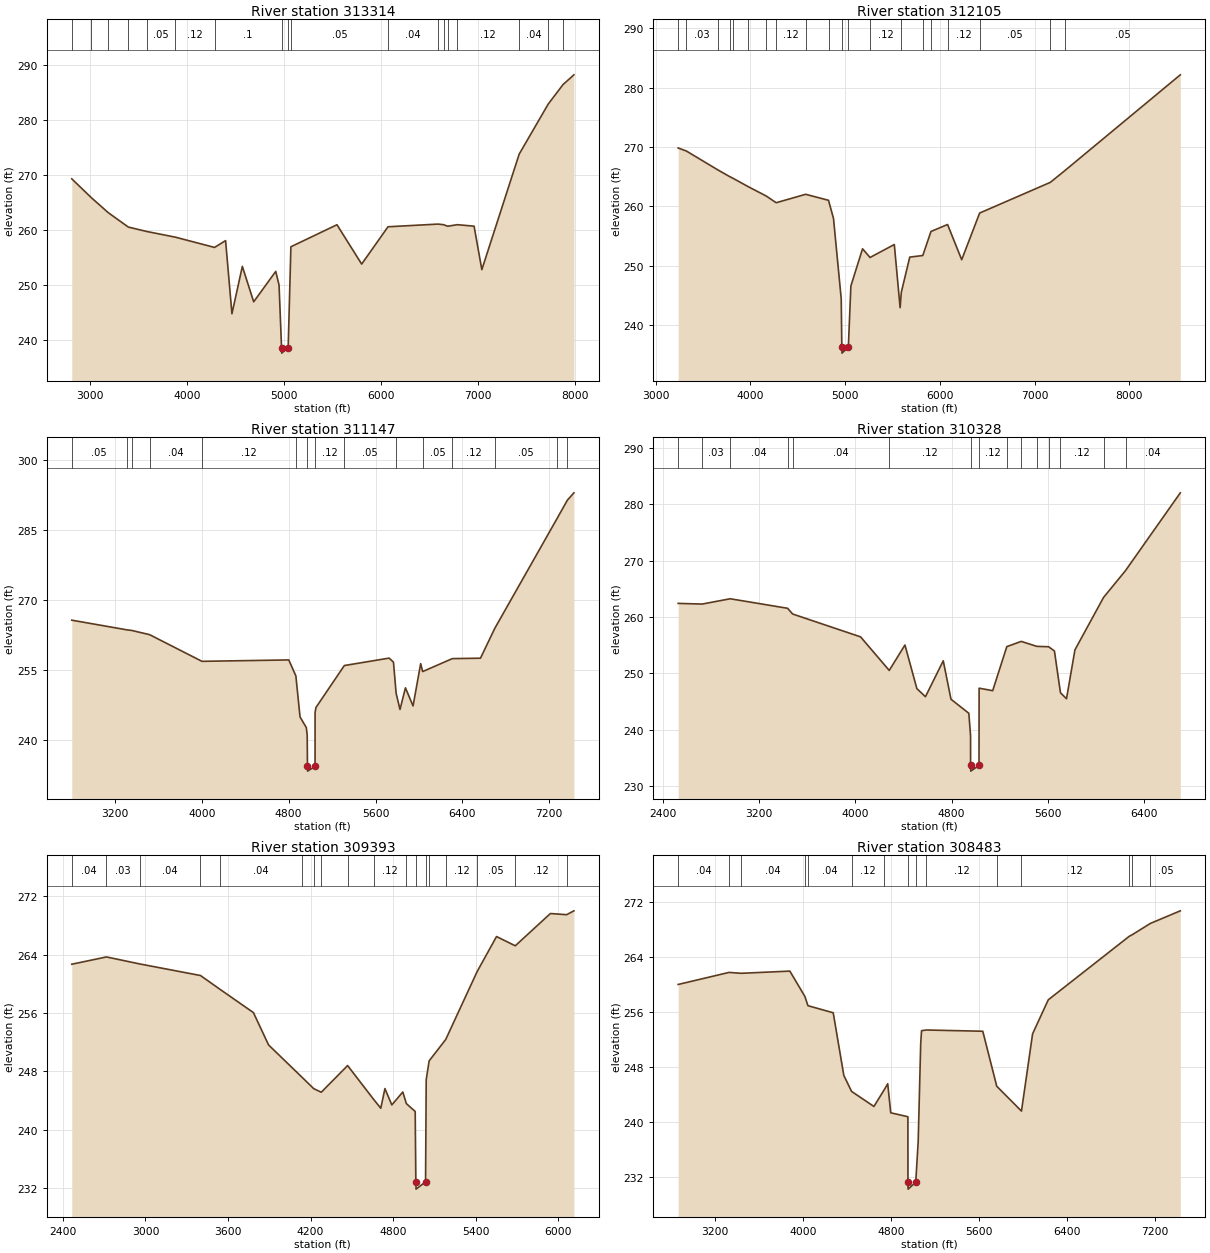
Type RM Length L Ch R = 1 ,313314  ,1209,1209,1209
BEGIN DESCRIPTION:
Mapping XS 5705ee22
END DESCRIPTION:
XS GIS Cut Line= 5
      2440923.23     13531331.23       2439801.9     13529602.15
      2439784.78     13529199.84       2439057.2     13528429.46
      2438920.35     13526778.69
#Sta/Elev= 30
  2812.2  269.33  3015.6  265.87  3188.6  263.17  3395.3  260.55  3586.7  259.74
  3880.9  258.71    4285  256.84  4398.8  258.08  4464.4  244.77  4571.7  253.39
  4688.8  246.94  4916.4  252.48  4950.3  249.99  4976.2   238.6  4977.7   237.6
  5044.4   238.6  5072.5  256.96  5547.7  260.97  5802.6  253.81  6074.3   260.6
  6590.9  261.09  6647.5  260.98    6690   260.7  6789.2  260.98    6962  260.71
  7042.2   252.8  7427.5  273.83  7727.4  282.95  7879.9  286.49  7991.8  288.26
#Mann= 18 ,-1 , 0
  2812.2     .03       0  3015.6     .12       0  3188.6     .05       0
  3395.3     .12       0  3586.7     .05       0  3880.9     .12       0
    4285      .1       0  4976.2     .05       0  5044.4      .1       0
  5072.5     .05       0  6074.3     .04       0  6590.9    .013       0
  6647.5     .12       0    6690     .05       0  6789.2     .12       0
  7427.5     .04       0  7727.4     .05       0  7879.9     .03       0
Bank Sta=4976.2,5044.4
XS Rating Curve= 0 ,0
Exp/Cntr=0.3,0.1

Type RM Length L Ch R = 1 ,312105  ,958,958,958
BEGIN DESCRIPTION:
SMITH CREEK 49.0
END DESCRIPTION:
XS GIS Cut Line= 4
      2441224.99     13531424.95        2440900.     13529725.05
      2440555.15     13527941.56      2439142.82     13526905.85
#Sta/Elev= 30
  3238.3  269.84  3325.7  269.32  3657.8  266.14  3780.5  265.03  3817.2  264.73
  3978.2  263.32  4168.4  261.74  4272.6  260.62  4583.7  262.04  4824.6  261.03
  4877.4  257.97  4958.9  244.42  4965.2  236.29  4966.7  235.29    5034  236.29
  5060.7   246.6  5183.9  252.86  5262.9   251.4    5519  253.58  5580.2  242.95
  5593.2  245.56    5682  251.46  5819.4  251.73  5905.9  255.78  6081.1  256.95
  6230.1  251.02  6419.5  258.88  7165.6  264.05  7316.4     266  8536.9  282.16
#Mann= 20 ,-1 , 0
  3238.3     .05       0  3325.7     .03       0  3657.8     .04       0
  3780.5     .05       0  3817.2     .12       0  3978.2     .05       0
  4168.4     .04       0  4272.6     .12       0  4583.7     .04       0
  4824.6      .1       0  4965.2     .05       0    5034      .1       0
  5262.9     .12       0  5593.2      .1       0  5819.4     .12       0
  5905.9     .05       0  6081.1     .12       0  6419.5     .05       0
  7165.6    .013       0  7316.4     .05       0
Bank Sta=4965.2,5034
XS Rating Curve= 0 ,0
Exp/Cntr=0.3,0.1

Type RM Length L Ch R = 1 ,311147  ,819,819,819
BEGIN DESCRIPTION:
Mapping XS 2a801557
END DESCRIPTION:
XS GIS Cut Line= 3
      2442772.12     13531177.13      2441462.48     13528900.25
       2441565.2     13526905.85
#Sta/Elev= 30
  2803.2   265.7  3308.2  263.64  3354.2  263.51    3520   262.6    4002   256.9
  4801.4   257.2  4866.7  253.79  4905.2  245.01  4962.9  242.74  4971.1   241.1
  4973.5  234.43    4975  233.43  5043.4  234.43  5043.7  245.98  5051.6  247.03
  5313.1     256  5725.5  257.59  5765.5  256.72  5789.9  250.08  5825.6  246.61
  5875.7  251.24  5945.8  247.37  6015.9   256.4  6034.2  254.71  6307.5  257.48
  6566.6  257.57  6698.6  263.96  7268.3  287.28  7366.8  291.35  7426.9  292.92
#Mann= 15 ,-1 , 0
  2803.2     .05       0  3308.2     .12       0  3354.2     .05       0
    3520     .04       0    4002     .12       0  4866.7      .1       0
  4973.5     .05       0  5043.4     .12       0  5313.1     .05       0
  5789.9     .12       0  6034.2     .05       0  6307.5     .12       0
  6698.6     .05       0  7268.3    .013       0  7366.8     .05       0
Bank Sta=4973.5,5043.4
XS Rating Curve= 0 ,0
Exp/Cntr=0.3,0.1

Type RM Length L Ch R = 1 ,310328  ,935,935,935
BEGIN DESCRIPTION:
Mapping XS 3b0b64ea
END DESCRIPTION:
XS GIS Cut Line= 3
       2443927.7     13530663.58       2442095.9     13528540.74
      2442207.18     13527171.17
#Sta/Elev= 30
  2524.8  262.41  2724.2  262.29  2957.9  263.23  3435.6  261.54  3476.9  260.53
  4042.6  256.47    4281  250.52  4411.7  255.03    4511  247.29  4582.3  245.86
  4730.4  252.23  4794.8  245.41  4943.2  242.92  4957.5  238.99  4957.9  233.66
  4959.4  232.66  5027.8  233.66  5028.8  247.37  5141.8  246.93  5259.3  254.74
  5379.4  255.67  5508.4  254.79    5607  254.72  5655.5  253.97  5705.7  246.56
  5755.9   245.5  5826.1  254.17    6064  263.46  6247.1  268.23  6702.8  282.02
#Mann= 15 ,-1 , 0
  2524.8     .04       0  2724.2     .03       0  2957.9     .04       0
  3435.6    .013       0  3476.9     .04       0    4281     .12       0
  4957.9     .05       0  5027.8     .12       0  5259.3     .12       0
  5379.4     .05       0  5508.4     .12       0    5607      .1       0
  5705.7     .12       0    6064     .05       0  6247.1     .04       0
Bank Sta=4957.9,5027.8
XS Rating Curve= 0 ,0
Exp/Cntr=0.3,0.1

Type RM Length L Ch R = 1 ,309393  ,910,910,910
BEGIN DESCRIPTION:
Mapping XS e638f882
END DESCRIPTION:
XS GIS Cut Line= 4
       2444056.1     13530663.59      2443088.83     13528891.69
      2443105.95     13527907.32      2442909.54     13527292.47
#Sta/Elev= 30
  2464.5   262.7  2716.8   263.7  2958.3  262.74  3399.8  261.15  3542.1  259.25
  3784.5  256.06  3894.6  251.62  4137.4  247.19  4222.8  245.62  4277.5  245.13
  4468.9  248.79  4660.1   244.1  4709.9  242.93    4740  245.63    4790  243.39
    4870  245.16  4895.7  243.57    4960  242.49  4964.7  232.83  4966.2  231.83
  5035.3  232.83    5040  246.86  5061.3  249.43  5182.1  252.38    5410  261.69
    5551   266.5  5687.2  265.23  5942.3  269.66  6060.5   269.5  6113.2  270.03
#Mann= 18 ,-1 , 0
  2464.5     .04       0  2716.8     .03       0  2958.3     .04       0
  3399.8    .013       0  3542.1     .04       0  4137.4     .12       0
  4222.8     .04       0  4277.5     .12       0  4468.9     .05       0
  4660.1     .12       0  4895.7      .1       0  4964.7     .05       0
  5035.3      .1       0  5061.3      .1       0  5182.1     .12       0
    5410     .05       0  5687.2     .12       0  6060.5     .05       0
Bank Sta=4964.7,5035.3
XS Rating Curve= 0 ,0
Exp/Cntr=0.3,0.1

Type RM Length L Ch R = 1 ,308483  ,961,961,961
BEGIN DESCRIPTION:
Mapping XS b021438a
END DESCRIPTION:
XS GIS Cut Line= 4
      2444261.52     13530714.92      2443525.37     13529276.88
       2444073.2     13528309.63      2443456.91      13526580.6
#Sta/Elev= 30
  2866.9     260    3329  261.75  3440.1  261.62  3881.6  261.94  4018.4  258.26
    4046  256.92  4275.7  255.89  4372.2  246.79  4442.3  244.48  4645.5  242.29
  4739.2  244.71    4771  245.59  4798.4  241.37  4954.3   240.8  4954.9  231.29
  4956.4  230.29  5025.5  231.29  5047.7  237.15  5070.7  251.41  5078.3  253.29
  5122.8  253.39  5634.7  253.21  5761.8  245.22  5986.4  241.62  6087.3  252.83
  6229.8  257.77  6965.5  266.99  6993.7  267.23  7157.5  268.86  7429.6  270.69
#Mann= 15 ,-1 , 0
  2866.9     .04       0    3329     .03       0  3440.1     .04       0
  4018.4    .013       0    4046     .04       0  4442.3     .12       0
  4739.2      .1       0  4954.9     .05       0  5025.5      .1       0
  5122.8     .12       0  5761.8      .1       0  5986.4     .12       0
  6965.5     .05       0  6993.7     .12       0  7157.5     .05       0
Bank Sta=4954.9,5025.5
XS Rating Curve= 0 ,0
Exp/Cntr=0.3,0.1

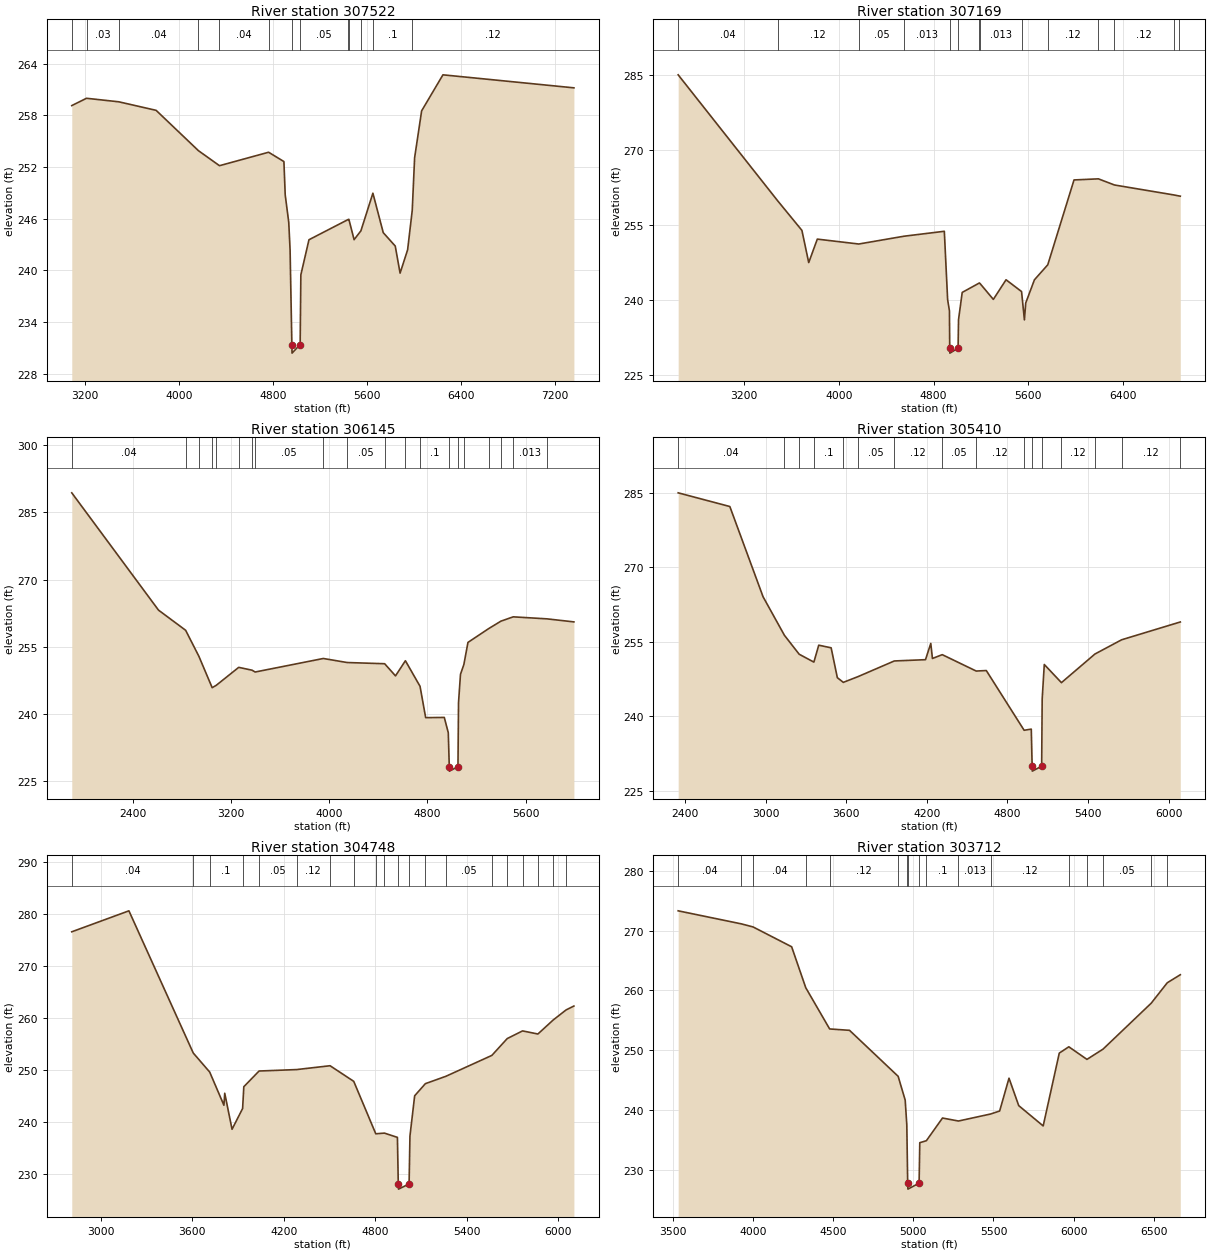
Type RM Length L Ch R = 1 ,307522  ,353,353,353
BEGIN DESCRIPTION:
Mapping XS 887713ba
END DESCRIPTION:
XS GIS Cut Line= 4
      2444366.13     13530676.19       2444745.9     13529711.96
      2444251.11     13527706.75      2444655.24     13526606.29
#Sta/Elev= 30
  3089.1  259.12  3214.5  259.97  3489.5  259.56  3807.1  258.57  4167.5  253.89
  4346.4  252.15  4764.5  253.71  4894.8  252.63  4905.8  248.77    4936  245.58
  4947.3  242.39  4962.5  231.41    4964  230.41  5033.1  231.41    5039  239.49
    5108  243.56    5442  245.91  5447.7  245.93  5492.2  243.57  5549.9  244.59
  5652.2  248.96  5740.4  244.38  5842.4  242.83  5883.6  239.69  5947.7  242.39
  5987.1  246.97  6007.2  253.06    6067  258.51  6248.4  262.69  7363.1  261.18
#Mann= 13 ,-1 , 0
  3089.1     .04       0  3214.5     .03       0  3489.5     .04       0
  4167.5     .05       0  4346.4     .04       0  4764.5     .05       0
  4962.5     .05       0  5033.1     .05       0    5442     .05       0
  5447.7      .1       0  5549.9     .12       0  5652.2      .1       0
  5987.1     .12       0
Bank Sta=4962.5,5033.1
XS Rating Curve= 0 ,0
Exp/Cntr=0.3,0.1

Type RM Length L Ch R = 1 ,307169  ,1024,1024,1024
BEGIN DESCRIPTION:
Mapping XS 179b407b
END DESCRIPTION:
XS GIS Cut Line= 4
      2445947.77     13530663.55      2444783.65     13528609.22
      2444526.86     13527813.16       2444775.1     13526803.11
#Sta/Elev= 30
    2644  285.05  3483.6  259.83  3688.3   253.9  3745.8  247.45  3818.2  252.15
  4168.2  251.17  4549.6  252.73  4890.2  253.72  4918.1  240.03  4933.4  237.79
  4935.7  230.32  4937.2  229.32  5006.3  230.32  5010.1  236.02  5041.2  241.48
  5186.4  243.37  5194.3  243.18  5303.9  240.08  5411.1  244.01  5542.1  241.65
  5566.1  235.98  5577.1  239.35  5650.6     244  5763.3  247.01  5984.8     264
  6190.5  264.22  6326.2  262.99  6826.3     261  6867.6  260.81  6881.8  260.75
#Mann= 14 ,-1 , 0
    2644     .04       0  3483.6     .12       0  4168.2     .05       0
  4549.6    .013       0  4935.7     .03       0  5006.3      .1       0
  5186.4      .1       0  5194.3    .013       0  5542.1      .1       0
  5763.3     .12       0  6190.5     .05       0  6326.2     .12       0
  6826.3    .013       0  6867.6     .12       0
Bank Sta=4935.7,5006.3
XS Rating Curve= 0 ,0
Exp/Cntr=0.3,0.1

Type RM Length L Ch R = 1 ,306145  ,735,735,735
BEGIN DESCRIPTION:
Mapping XS 9f74c5f1
END DESCRIPTION:
XS GIS Cut Line= 3
      2446238.81     13530706.35      2445031.89     13527796.04
      2444877.82     13526871.63
#Sta/Elev= 30
  1904.4  289.39  2610.5   263.2  2831.4   258.7  2939.4  252.88  3047.4  245.88
  3080.6  246.41  3263.5  250.42  3371.5  249.79  3397.5  249.38  3952.1   252.4
  4145.8   251.5  4451.5  251.23  4539.9  248.52  4620.5   251.9  4739.6  246.19
  4785.5  239.19  4937.1  239.24  4969.6  235.82  4977.6  228.25  4979.1  227.25
  5048.4  228.25  5052.9  242.54  5068.9  248.87  5096.4  251.05  5129.7  255.99
  5297.2  259.05  5397.7  260.73  5498.1   261.7  5772.7  261.25  5992.2  260.57
#Mann= 20 ,-1 , 0
  1904.4     .04       0  2831.4    .013       0  2939.4     .04       0
  3047.4      .1       0  3080.6     .05       0  3263.5    .013       0
  3371.5    .013       0  3397.5     .05       0  3952.1     .12       0
  4145.8     .05       0  4451.5     .12       0  4620.5     .12       0
  4739.6      .1       0  4977.6     .03       0  5048.4    .013       0
  5096.4     .12       0  5297.2     .05       0  5397.7     .12       0
  5498.1    .013       0  5772.7     .12       0
Bank Sta=4977.6,5048.4
XS Rating Curve= 0 ,0
Exp/Cntr=0.3,0.1

Type RM Length L Ch R = 1 ,305410  ,662,662,662
BEGIN DESCRIPTION:
Mapping XS 55cf19a3
END DESCRIPTION:
XS GIS Cut Line= 3
      2446469.93     13530577.99      2445596.83     13528652.02
      2445870.74     13527051.32
#Sta/Elev= 30
  2349.2  284.98  2733.9  282.22  2981.3  264.04  3140.3  256.28    3250  252.47
  3359.6  250.88  3395.8  254.29  3488.1  253.76  3534.3  247.74  3578.9   246.8
  3688.6  247.96  3958.3  251.11  4190.6  251.37    4230  254.65  4242.3  251.61
  4315.4  252.38  4568.1  249.08  4643.4  249.18    4925  237.15  4978.2  237.38
  4984.6  229.92  4986.1  228.92  5055.5  229.92  5059.4  243.44  5075.1   250.4
  5202.7  246.74  5452.2  252.51  5651.2  255.38  6084.7  258.94  6087.8  258.96
#Mann= 16 ,-1 , 0
  2349.2     .04       0  3140.3    .013       0    3250     .04       0
  3359.6      .1       0  3578.9    .013       0  3688.6     .05       0
  3958.3     .12       0  4315.4     .05       0  4568.1     .12       0
    4925      .1       0  4984.6     .05       0  5055.5      .1       0
  5202.7     .12       0  5452.2    .013       0  5651.2     .12       0
  6084.7     .05       0
Bank Sta=4984.6,5055.5
XS Rating Curve= 0 ,0
Exp/Cntr=0.3,0.1

Type RM Length L Ch R = 1 ,304748  ,1036,1036,1036
BEGIN DESCRIPTION:
Mapping XS b8ee2b16
END DESCRIPTION:
XS GIS Cut Line= 3
      2446641.11     13530500.91      2446076.17     13529131.36
      2446495.37     13527369.02
#Sta/Elev= 30
  2808.9  276.62  3183.7  280.66  3605.6  253.27  3713.5   249.6  3806.7  243.21
  3812.1  245.52    3860  238.58  3929.3  242.58  3937.2  246.78  4037.2   249.8
  4283.6  250.08  4502.8  250.82  4658.1  247.81  4802.6  237.71  4859.4  237.84
  4944.5  237.02  4950.2  228.05  4951.7  227.05  5021.1  228.05  5026.7  237.27
  5057.6  245.03    5128  247.37    5262  248.78  5563.9  252.81  5664.6  256.05
  5765.2  257.53  5865.8  256.93  5966.5  259.64  6050.7  261.57  6101.9  262.32
#Mann= 20 ,-1 , 0
  2808.9     .04       0  3605.6    .013       0  3713.5      .1       0
  3929.3    .013       0  4037.2     .05       0  4283.6     .12       0
  4502.8     .05       0  4658.1     .12       0  4802.6     .05       0
  4859.4      .1       0  4950.2     .05       0  5021.1      .1       0
    5128     .12       0    5262     .05       0  5563.9     .12       0
  5664.6    .013       0  5765.2     .05       0  5865.8    .013       0
  5966.5     .04       0  6050.7     .05       0
Bank Sta=4950.2,5021.1
XS Rating Curve= 0 ,0
Exp/Cntr=0.3,0.1

Type RM Length L Ch R = 1 ,303712  ,569,569,569
BEGIN DESCRIPTION:
Mapping XS 11f3ceac
END DESCRIPTION:
XS GIS Cut Line= 3
      2446735.28     13530500.89      2447034.86     13529311.12
      2446752.54     13527428.98
#Sta/Elev= 30
  3534.6   273.3  3928.9  271.12  4001.4  270.61  4241.9   267.3    4330  260.46
  4478.8  253.58  4602.8  253.35  4905.9  245.67  4949.7   241.7  4959.8  237.58
  4962.3  233.15  4965.3  227.84  4966.8  226.84  5036.5  227.84  5040.7  234.59
  5081.7  234.92  5182.3  238.71  5281.9  238.21  5482.2  239.38  5538.5  239.88
  5596.9  245.36  5657.5  240.78  5809.9  237.39  5910.3  249.55  5969.8   250.6
  6082.8   248.5    6183  250.21  6483.3  257.88  6583.4  261.29  6664.7  262.63
#Mann= 17 ,-1 , 0
  3534.6     .04       0  3928.9     .12       0  4001.4     .04       0
    4330    .013       0  4478.8     .12       0  4905.9      .1       0
  4962.3     .12       0  4965.3     .05       0  5036.5     .12       0
  5081.7      .1       0  5281.9    .013       0  5482.2     .12       0
  5969.8    .013       0  6082.8     .12       0    6183     .05       0
  6483.3    .013       0  6583.4     .05       0
Bank Sta=4965.3,5036.5
XS Rating Curve= 0 ,0
Exp/Cntr=0.3,0.1

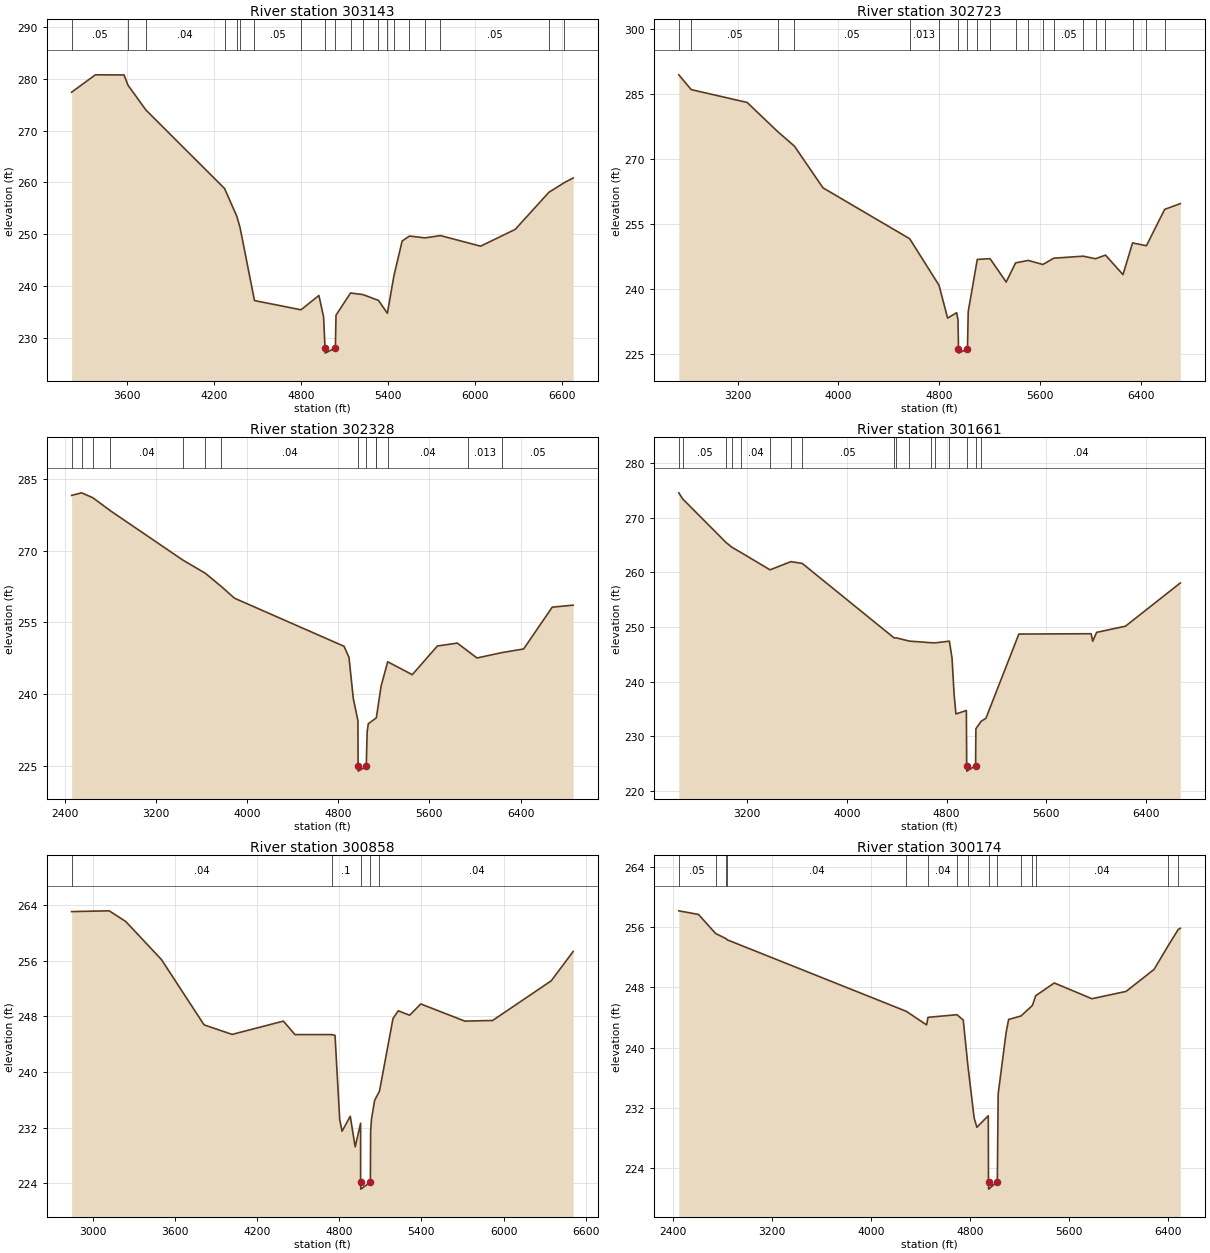
Type RM Length L Ch R = 1 ,303143  ,420,420,420
BEGIN DESCRIPTION:
Mapping XS 233788c7
END DESCRIPTION:
XS GIS Cut Line= 3
      2447548.44     13530646.45      2447745.32     13529507.99
      2446915.13     13527359.78
#Sta/Elev= 30
  3219.9   277.4  3383.7  280.75  3581.4  280.73  3609.1  278.73  3731.6  273.99
  4274.6  258.82  4358.7  253.49  4381.3   251.3  4480.9  237.21  4801.6  235.43
  4925.2  238.19  4957.4  234.07  4967.4  228.07  4968.9  227.07  5038.6  228.07
  5043.1  234.39  5143.3  238.67    5229  238.36  5335.9  237.24  5397.3  234.76
  5442.8  242.04  5499.2   248.7  5549.6  249.65  5656.5   249.3  5763.4  249.74
  6040.2   247.7  6278.9  250.94  6511.5   258.1  6618.3  259.97  6678.3  260.85
#Mann= 20 ,-1 , 0
  3219.9     .05       0  3609.1    .013       0  3731.6     .04       0
  4274.6    .013       0  4358.7     .04       0  4381.3     .04       0
  4480.9     .05       0  4801.6     .12       0  4967.4     .05       0
  5038.6     .12       0  5143.3     .05       0    5229      .1       0
  5335.9     .12       0  5397.3      .1       0  5442.8     .12       0
  5549.6    .013       0  5656.5     .12       0  5763.4     .05       0
  6511.5    .013       0  6618.3     .05       0
Bank Sta=4967.4,5038.6
XS Rating Curve= 0 ,0
Exp/Cntr=0.3,0.1

Type RM Length L Ch R = 1 ,302723  ,395,395,395
BEGIN DESCRIPTION:
Mapping XS 2efe5bf6
END DESCRIPTION:
XS GIS Cut Line= 4
      2447693.96     13531031.62      2448062.03     13529550.79
      2447676.84     13527727.57      2447428.61     13527188.31
#Sta/Elev= 30
  2731.9  289.45  2830.5  286.03  3274.5  283.06  3519.2  276.27  3650.4  272.95
  3876.8  263.32  4565.2  251.55  4798.2   240.8  4866.7   233.2  4938.3  234.44
  4949.2  232.79  4953.1  226.09  4954.6  225.09  5024.4  226.09  5030.3  234.69
  5102.3  246.76  5203.7  246.94  5331.8  241.53  5406.4  245.96  5507.8  246.53
  5622.6  245.59  5710.5  247.05  5943.7  247.51  6041.6  246.92  6120.4  247.76
  6259.4  243.25  6335.5  250.58  6445.5  249.93  6590.5  258.34  6714.9  259.67
#Mann= 20 ,-1 , 0
  2731.9     .04       0  2830.5     .05       0  3519.2    .013       0
  3650.4     .05       0  4565.2    .013       0  4798.2     .05       0
  4953.1     .05       0  5024.4      .1       0  5102.3     .05       0
  5203.7     .05       0  5406.4     .12       0  5507.8    .013       0
  5622.6     .12       0  5710.5     .05       0  5943.7     .12       0
  6041.6     .12       0  6120.4     .05       0  6335.5    .013       0
  6445.5     .05       0  6590.5     .12       0
Bank Sta=4953.1,5024.4
XS Rating Curve= 0 ,0
Exp/Cntr=0.3,0.1

Type RM Length L Ch R = 1 ,302328  ,667,667,667
BEGIN DESCRIPTION:
Mapping XS 05ad027d
END DESCRIPTION:
XS GIS Cut Line= 4
      2448284.58     13531288.44       2448430.1     13529644.94
      2448113.39     13527770.37      2448250.17     13526932.53
#Sta/Elev= 30
    2461  281.61  2549.2  282.15  2647.9  281.11  2799.7  278.42  3437.6  268.05
    3635  265.28  3774.4  262.52    3890  260.07  4851.2  249.99  4894.4  247.66
  4932.3  239.05  4972.9  234.43  4974.5  224.83    4976  223.83  5045.8  224.83
    5054  232.13  5064.2  233.77  5133.6  234.98  5134.7  235.05  5175.8  241.61
    5234  246.75  5449.6  244.04  5669.9  250.05  5845.1  250.66  5937.3  248.99
  6017.5  247.54  6236.3  248.67  6426.7  249.43  6677.5  258.19    6861  258.61
#Mann= 14 ,-1 , 0
    2461     .05       0  2549.2    .013       0  2647.9     .05       0
  2799.7     .04       0  3437.6     .05       0    3635    .013       0
  3774.4     .04       0  4974.5     .04       0  5045.8     .04       0
  5133.6     .04       0  5134.7     .12       0    5234     .04       0
  5937.3    .013       0  6236.3     .05       0
Bank Sta=4974.5,5045.8
XS Rating Curve= 0 ,0
Exp/Cntr=0.3,0.1

Type RM Length L Ch R = 1 ,301661  ,803,803,803
BEGIN DESCRIPTION:
Mapping XS 49b809cd
END DESCRIPTION:
XS GIS Cut Line= 4
      2448815.28     13530732.05      2449157.67     13529490.87
      2448549.93     13527487.89      2448592.73      13526845.9
#Sta/Elev= 30
    2651  274.55    2682  273.44  3030.3  265.45  3078.2  264.57  3149.4  263.63
    3383  260.45  3550.7  261.95  3641.7  261.62  4378.7  247.98  4396.3  247.99
  4500.2   247.4  4675.9   247.1    4708  247.08  4821.9  247.39  4843.4  244.27
  4859.8  237.68  4874.7  234.06  4958.3  234.69  4960.9  224.59  4962.4  223.59
  5032.2  224.59  5034.7  231.36  5078.1  232.74  5115.1  233.26  5379.3  248.69
  5959.4  248.75    5972  247.38  6003.4     249    6235  250.13  6675.1  258.05
#Mann= 17 ,-1 , 0
    2651     .04       0    2682     .05       0  3030.3     .04       0
  3078.2     .05       0  3149.4     .04       0    3383     .05       0
  3550.7     .04       0  3641.7     .05       0  4378.7     .04       0
  4396.3     .05       0  4500.2     .04       0  4675.9     .05       0
    4708     .12       0  4821.9      .1       0  4960.9     .05       0
  5032.2      .1       0  5078.1     .04       0
Bank Sta=4960.9,5032.2
XS Rating Curve= 0 ,0
Exp/Cntr=0.3,0.1

Type RM Length L Ch R = 1 ,300858  ,684,684,684
BEGIN DESCRIPTION:
Mapping XS 56704ee2
END DESCRIPTION:
XS GIS Cut Line= 3
       2450022.2     13530158.53      2449919.49     13528985.85
       2448832.4     13526751.76
#Sta/Elev= 30
  2846.1  263.06  3120.7  263.17  3241.1  261.64  3502.1  256.16  3813.3  246.77
  4018.2   245.4  4392.3  247.31  4476.9  245.37  4745.9  245.37  4769.3  245.26
  4803.7  233.12  4820.7  231.48  4880.5  233.63  4916.4  229.23    4956  232.63
  4956.1  224.15  4957.6  223.15  5027.4  224.15  5029.2   231.5  5036.2   233.3
  5058.5  235.92  5093.9  237.24  5192.6  247.69  5230.8  248.79  5314.2  248.16
  5395.5  249.78  5716.8  247.31  5919.7   247.4  6348.1  253.11  6507.8  257.32
#Mann= 5 ,-1 , 0
  2846.1     .04       0  4745.9      .1       0  4956.1     .05       0
  5027.4      .1       0  5093.9     .04       0
Bank Sta=4956.1,5027.4
XS Rating Curve= 0 ,0
Exp/Cntr=0.3,0.1

Type RM Length L Ch R = 1 ,300174  ,486,486,486
BEGIN DESCRIPTION:
Mapping XS 9f1516ff
END DESCRIPTION:
XS GIS Cut Line= 3
      2451143.54     13530149.99      2450099.24      13527847.4
      2449089.57     13526700.82
#Sta/Elev= 30
  2445.2  258.15  2604.5  257.67  2743.2  255.14  2829.2  254.44    2836  254.31
  4285.1  244.82  4449.1  243.02  4460.3  244.02  4694.9  244.37  4745.6  243.66
  4782.9  237.67  4833.4   230.7  4855.8  229.44  4948.1  230.97  4949.8  222.23
  4951.3  221.23  5021.1  222.23  5028.1  233.87  5091.7  241.95  5112.6  243.74
  5212.3   244.2    5305   245.6    5331  246.88  5481.6  248.58  5786.2  246.49
  6062.3  247.46    6289  250.38  6402.1   253.5  6483.9  255.67  6501.3  255.84
#Mann= 15 ,-1 , 0
  2445.2     .05       0  2743.2     .12       0  2829.2     .05       0
    2836     .04       0  4285.1     .12       0  4460.3     .04       0
  4694.9     .03       0  4782.9      .1       0  4949.8     .05       0
  5021.1      .1       0  5212.3     .12       0    5305     .05       0
    5331     .04       0  6402.1     .05       0  6483.9     .12       0
Bank Sta=4949.8,5021.1
XS Rating Curve= 0 ,0
Exp/Cntr=0.3,0.1

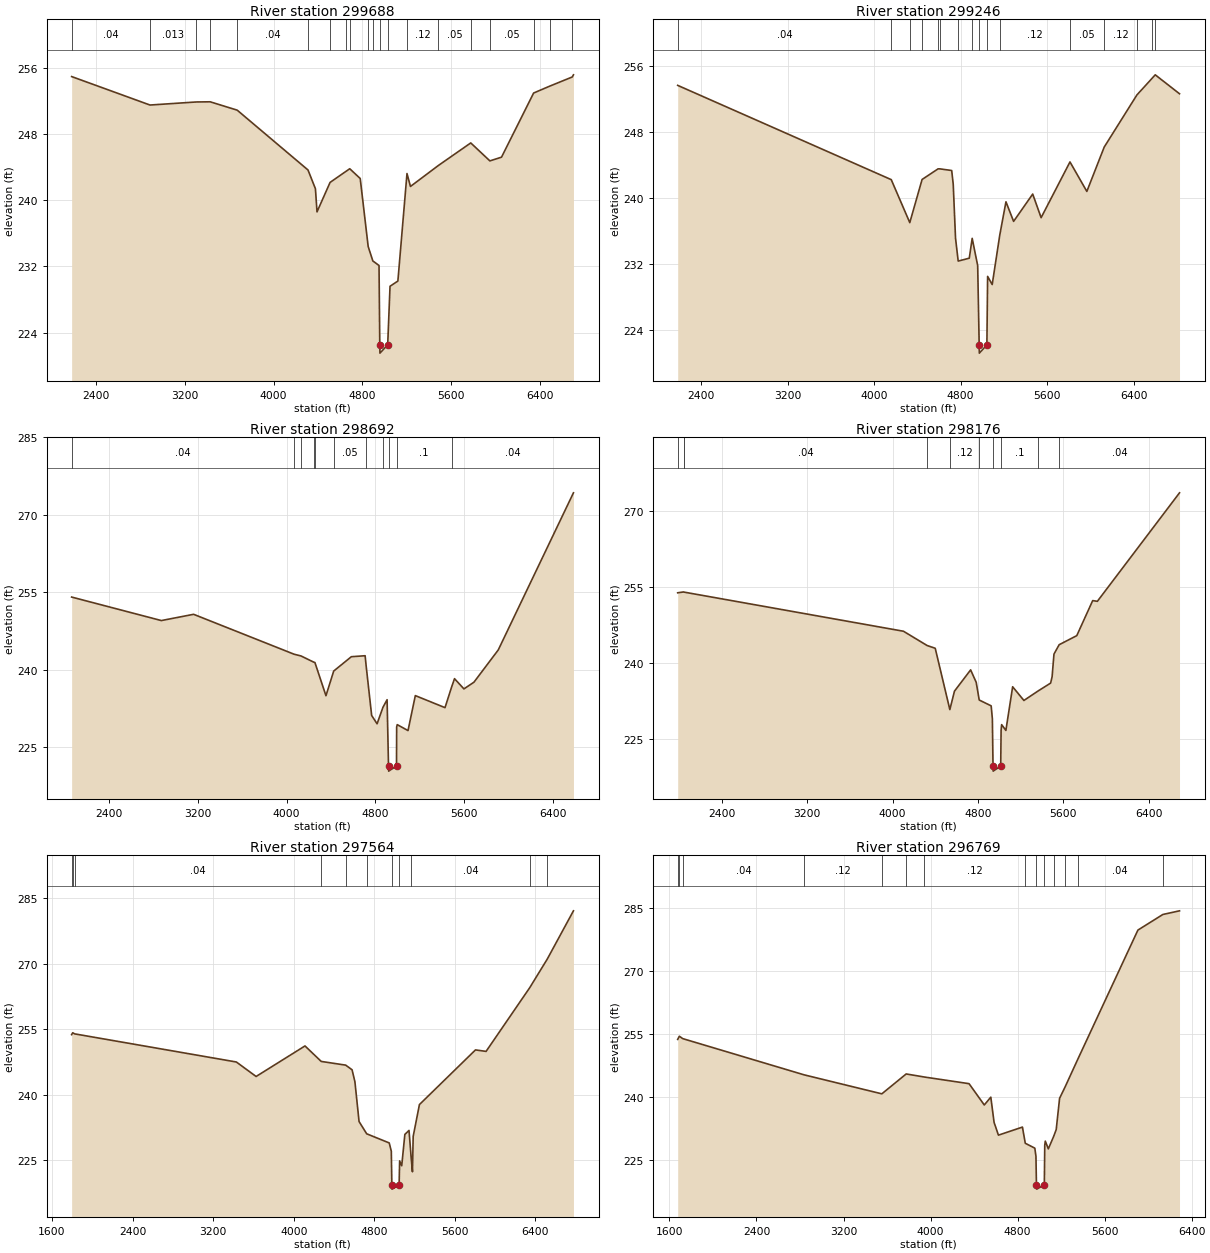
Type RM Length L Ch R = 1 ,299688  ,442,442,442
BEGIN DESCRIPTION:
Mapping XS c1cfaca8
END DESCRIPTION:
XS GIS Cut Line= 4
      2452222.04     13529910.28      2451229.12     13528395.22
      2449542.86     13526803.12      2449191.93     13526631.93
#Sta/Elev= 30
  2181.1  254.95  2887.2  251.51  3304.9  251.88  3429.5   251.9  3672.8  250.89
  4310.7  243.66  4377.6  241.39  4391.8   238.6  4509.6  242.16  4648.9  243.46
  4686.8  243.81    4781  242.63  4852.8  234.41  4894.8  232.67  4950.5  232.12
  4957.3  222.53  4958.8  221.53  5028.6  222.53  5049.6  229.61  5120.4  230.24
  5202.4  243.23  5233.7  241.67  5484.7   244.2  5776.9  246.93  5949.2  244.76
  6054.1  245.21  6343.3  252.96  6489.7   253.8  6691.3   254.9  6702.1  255.16
#Mann= 20 ,-1 , 0
  2181.1     .04       0  2887.2    .013       0  3304.9     .04       0
  3429.5    .013       0  3672.8     .04       0  4310.7     .12       0
  4509.6     .05       0  4648.9     .12       0  4686.8     .03       0
  4852.8     .12       0  4894.8      .1       0  4957.3     .05       0
  5028.6      .1       0  5202.4     .12       0  5484.7     .05       0
  5776.9     .12       0  5949.2     .05       0  6343.3     .04       0
  6489.7     .05       0  6691.3     .12       0
Bank Sta=4957.3,5028.6
XS Rating Curve= 0 ,0
Exp/Cntr=0.3,0.1

Type RM Length L Ch R = 1 ,299246  ,554,554,554
BEGIN DESCRIPTION:
Mapping XS d8e021ad
END DESCRIPTION:
XS GIS Cut Line= 4
      2452521.63     13529687.73      2451802.63     13528412.34
      2450253.32     13526863.03      2449320.34     13526537.78
#Sta/Elev= 30
    2182  253.66    4158  242.21  4329.5  236.99  4443.3  242.23  4591.4  243.52
  4607.1  243.52  4717.3  243.32  4731.5  241.65  4752.7  235.11  4777.4  232.32
    4880  232.67  4906.9  235.08  4957.8  231.77  4971.6  222.14  4973.1  221.14
  5042.9  222.14  5049.7  230.46  5092.1  229.47  5162.5  235.51  5219.4  239.52
  5290.1  237.14  5466.9  240.46  5544.7  237.59  5811.7  244.36  5967.8  240.78
  6128.7  246.17  6431.2   252.5  6566.8  254.45  6600.7  254.94  6825.2  252.64
#Mann= 16 ,-1 , 0
    2182     .04       0    4158     .12       0  4329.5     .05       0
  4443.3     .12       0  4591.4     .05       0  4607.1     .03       0
  4777.4     .12       0  4906.9      .1       0  4971.6     .05       0
  5042.9      .1       0  5162.5     .12       0  5811.7     .05       0
  6128.7     .12       0  6431.2     .05       0  6566.8     .04       0
  6600.7     .05       0
Bank Sta=4971.6,5042.9
XS Rating Curve= 0 ,0
Exp/Cntr=0.3,0.1

Type RM Length L Ch R = 1 ,298692  ,516,516,516
BEGIN DESCRIPTION:
Mapping XS 9db6ae4e
END DESCRIPTION:
XS GIS Cut Line= 3
      2452727.06     13529636.35       2451254.8     13527094.15
      2450689.93     13525613.48
#Sta/Elev= 30
    2063  254.09  2871.5  249.54  3162.4  250.75  4068.4  243.02    4130  242.69
  4245.8  241.48  4255.4  241.43  4355.1  234.99  4424.7  239.76  4583.7  242.54
  4708.1  242.73  4717.1   240.8  4766.9  231.17  4815.7  229.55  4868.6  232.74
    4906  234.22  4918.8  221.39  4920.3  220.39  4990.9  221.39  4992.2  228.94
  4997.4  229.39  5094.6  228.24  5160.4  235.01    5428  232.68  5487.2  236.65
  5513.6  238.29  5598.6  236.31  5688.9  237.61  5908.1  243.86  6585.5  274.27
#Mann= 11 ,-1 , 0
    2063     .04       0  4068.4     .05       0    4130     .12       0
  4245.8     .05       0  4255.4     .12       0  4424.7     .05       0
  4717.1     .12       0  4868.6      .1       0  4918.8     .05       0
  4990.9      .1       0  5487.2     .04       0
Bank Sta=4918.8,4990.9
XS Rating Curve= 0 ,0
Exp/Cntr=0.3,0.1

Type RM Length L Ch R = 1 ,298176  ,612,612,612
BEGIN DESCRIPTION:
Mapping XS 3d9fbf13
END DESCRIPTION:
XS GIS Cut Line= 3
      2452855.46     13529559.33      2451674.23     13526845.92
      2451109.65     13525194.96
#Sta/Elev= 30
  1985.4  253.87  2041.3  254.04  2043.7  254.01    4102  246.28  4323.7  243.46
  4399.6  242.92  4536.7  230.81    4580  234.45  4731.5  238.65  4783.8  236.19
    4812   232.7    4924  231.55  4935.3  229.01  4941.4  219.66  4942.9  218.66
  5013.5  219.66  5017.1  226.75  5022.3  227.84    5062   226.7  5125.4  235.32
  5230.9  232.61  5364.9   234.5  5481.4  236.04  5495.3   237.3  5512.7  241.76
  5561.3  243.62  5726.5  245.41  5875.8  252.33  5919.6  252.19  6689.6  273.61
#Mann= 10 ,-1 , 0
  1985.4     .04       0  2041.3    .013       0  2043.7     .04       0
  4323.7     .05       0  4536.7     .12       0    4812      .1       0
  4941.4     .05       0  5013.5      .1       0  5364.9     .12       0
  5561.3     .04       0
Bank Sta=4941.4,5013.5
XS Rating Curve= 0 ,0
Exp/Cntr=0.3,0.1

Type RM Length L Ch R = 1 ,297564  ,795,795,795
BEGIN DESCRIPTION:
Mapping XS b5a9dd58
END DESCRIPTION:
XS GIS Cut Line= 3
      2452920.67     13529529.11      2452136.45     13526469.29
      2451674.23     13524705.98
#Sta/Elev= 30
  1795.6  253.77  1806.5   254.2    1825  253.95  3430.9   247.5    3627  244.18
  4112.2  251.18  4273.3  247.63  4516.3  246.78  4579.7  245.71  4607.8  242.97
    4649  233.85  4724.7  231.04  4948.4  228.95  4969.1  227.05  4974.3  219.36
  4975.8  218.36  5046.6  219.36  5051.8  224.83  5072.5  223.72  5103.5   230.9
  5144.8  231.82  5167.4  225.21    5179  222.34  5186.2  230.45  5248.2  237.74
  5804.6  250.27  5909.8  249.93  6342.9  264.52  6517.3  271.09  6777.2  282.15
#Mann= 11 ,-1 , 0
  1795.6     .04       0  1806.5    .013       0    1825     .04       0
  4273.3     .05       0  4516.3     .12       0  4724.7      .1       0
  4974.3     .05       0  5046.6      .1       0  5167.4     .04       0
  6342.9     .05       0  6517.3     .04       0
Bank Sta=4974.3,5046.6
XS Rating Curve= 0 ,0
Exp/Cntr=0.3,0.1

Type RM Length L Ch R = 1 ,296769  ,560,560,560
BEGIN DESCRIPTION:
Mapping XS 5be67976
END DESCRIPTION:
XS GIS Cut Line= 3
      2452985.77     13529542.08      2452898.27     13526392.25
      2452521.66     13524979.95
#Sta/Elev= 30
  1675.9   253.8  1691.2  254.56    1722  253.99  2836.5  245.38  3552.4  240.85
  3776.3  245.58  3943.6  244.85    4354  243.27  4494.1   238.2  4554.1  240.06
  4584.1  234.07  4624.1  231.02  4844.8  232.94  4870.9  229.09  4958.6  227.93
    4969  226.01  4973.6  219.18  4975.1  218.18    5046  219.18  5049.9  228.64
    5055   229.6  5082.8  227.76  5131.8  230.72  5155.3  232.35  5186.3  239.79
  5235.4  242.41  5352.4  249.01  5906.3  279.81  6135.5  283.52  6288.6  284.39
#Mann= 14 ,-1 , 0
  1675.9     .04       0  1691.2    .013       0    1722     .04       0
  2836.5     .12       0  3552.4     .05       0  3776.3     .04       0
  3943.6     .12       0  4870.9      .1       0  4973.6     .05       0
    5046      .1       0  5131.8     .12       0  5235.4     .05       0
  5352.4     .04       0  6135.5     .05       0
Bank Sta=4973.6,5046
XS Rating Curve= 0 ,0
Exp/Cntr=0.3,0.1

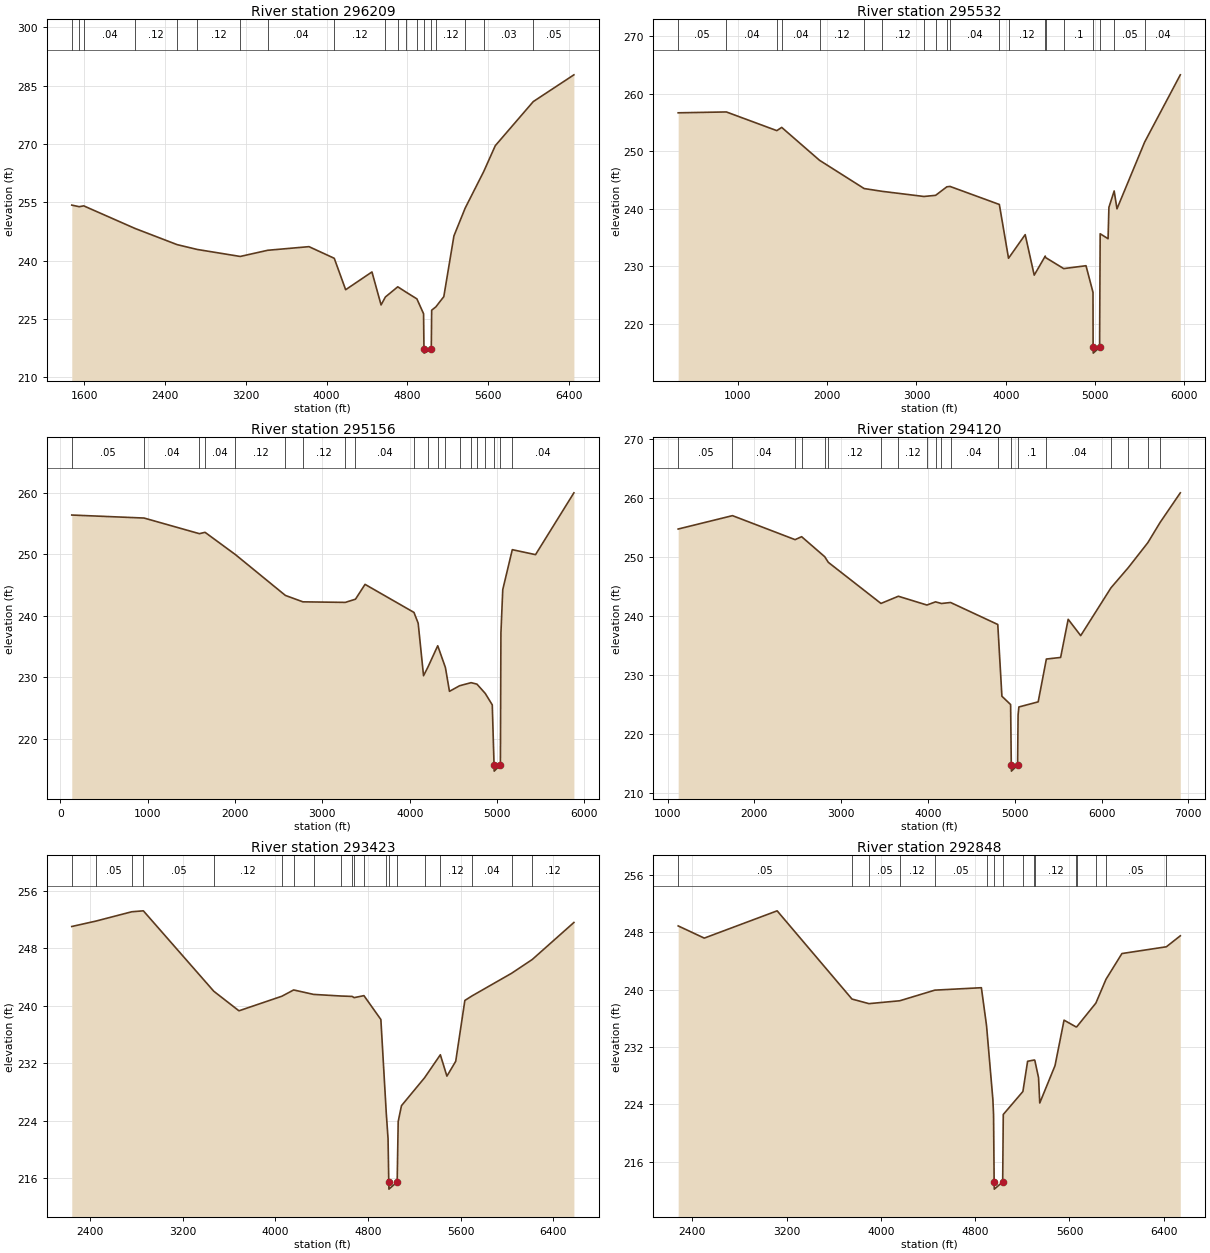
Type RM Length L Ch R = 1 ,296209  ,677,677,677
BEGIN DESCRIPTION:
Mapping XS 3dfc46d6
END DESCRIPTION:
XS GIS Cut Line= 4
      2453037.85     13529607.18      2453463.21     13527342.38
      2453360.49     13525818.75      2452667.16     13524911.42
#Sta/Elev= 30
  1475.4   254.3    1549  253.89  1593.5  254.11  2101.8   248.3  2518.7  244.14
  2718.2   242.9  3143.7   241.1  3416.6  242.69  3824.9  243.62  4075.2  240.63
  4188.1  232.55  4448.7  237.12  4538.9  228.64  4581.7  230.68  4704.2   233.3
  4788.6  231.89  4893.6   230.2  4959.9  226.37  4963.7  217.25  4965.2  216.25
  5036.1  217.25    5040  227.28  5081.1  228.13  5160.3  230.77  5260.5  246.38
  5371.9  253.53    5555   262.9  5670.2  269.58  6046.3  280.91  6448.8  287.79
#Mann= 19 ,-1 , 0
  1475.4     .04       0    1549    .013       0  1593.5     .04       0
  2101.8     .12       0  2518.7     .05       0  2718.2     .12       0
  3143.7     .05       0  3416.6     .04       0  4075.2     .12       0
  4581.7     .05       0  4704.2     .12       0  4788.6     .05       0
  4893.6      .1       0  4963.7     .05       0  5036.1      .1       0
  5081.1     .12       0  5371.9     .05       0    5555     .03       0
  6046.3     .05       0
Bank Sta=4963.7,5036.1
XS Rating Curve= 0 ,0
Exp/Cntr=0.3,0.1

Type RM Length L Ch R = 1 ,295532  ,376,376,376
BEGIN DESCRIPTION:
Mapping XS 33a045b5
END DESCRIPTION:
XS GIS Cut Line= 4
       2452881.6     13530622.79      2453514.57     13527547.81
      2454011.03     13526058.42      2454370.17     13525220.44
#Sta/Elev= 30
   332.5   256.7   871.9  256.85  1436.7   253.6  1491.6  254.16  1914.7  248.44
  2414.2  243.52  2614.3  243.04  3083.1  242.14  3214.7  242.34  3339.8  243.82
  3375.2  243.89  3927.8  240.75  4030.7  231.39  4217.2   235.5  4318.2  228.45
  4441.9  231.77  4444.8  231.52  4648.3  229.59  4897.9  230.09  4976.2  225.46
  4977.6  215.88  4979.1  214.88  5050.1  215.88  5056.5  235.65  5144.9  234.79
  5154.4  240.25  5213.3   243.1  5244.6  239.99  5554.8  251.62  5953.6  263.31
#Mann= 20 ,-1 , 0
   332.5     .05       0   871.9     .04       0  1436.7    .013       0
  1491.6     .04       0  1914.7     .12       0  2414.2     .05       0
  2614.3     .12       0  3083.1     .05       0  3214.7     .04       0
  3339.8     .05       0  3375.2     .04       0  3927.8     .05       0
  4030.7     .12       0  4441.9     .05       0  4444.8     .12       0
  4648.3      .1       0  4977.6     .05       0  5050.1      .1       0
  5213.3     .05       0  5554.8     .04       0
Bank Sta=4977.6,5050.1
XS Rating Curve= 0 ,0
Exp/Cntr=0.3,0.1

Type RM Length L Ch R = 1 ,295156  ,1036,1036,1036
BEGIN DESCRIPTION:
Mapping XS 1039039a
END DESCRIPTION:
XS GIS Cut Line= 4
      2452842.53     13530974.41      2453583.05     13527582.05
      2453899.76      13526700.4      2454824.19     13525733.17
#Sta/Elev= 30
   132.2  256.39   959.9   255.9  1592.8  253.36  1657.6  253.58    2005  249.96
  2577.2  243.32  2777.8  242.28  3262.7  242.19  3379.4  242.71  3488.8  245.12
  4048.5  240.56  4096.8  238.81  4158.3  230.27  4211.4  231.76  4320.6  235.14
  4408.6   231.6    4455  227.73  4570.9  228.64  4702.5  229.14  4769.6   228.9
  4864.1   227.4  4944.9  225.53  4965.3  215.76  4966.8  214.76  5037.8  215.76
    5044  237.23    5065  244.27  5174.1  250.76  5439.9  249.95  5879.2     260
#Mann= 20 ,-1 , 0
   132.2     .05       0   959.9     .04       0  1592.8    .013       0
  1657.6     .04       0    2005     .12       0  2577.2     .05       0
  2777.8     .12       0  3262.7     .05       0  3379.4     .04       0
  4048.5     .12       0  4211.4     .05       0  4320.6     .12       0
  4408.6     .05       0  4570.9     .12       0  4702.5     .05       0
  4769.6     .12       0  4864.1      .1       0  4965.3     .05       0
  5037.8      .1       0  5174.1     .04       0
Bank Sta=4965.3,5037.8
XS Rating Curve= 0 ,0
Exp/Cntr=0.3,0.1

Type RM Length L Ch R = 1 ,294120  ,697,697,697
BEGIN DESCRIPTION:
Mapping XS f55226fb
END DESCRIPTION:
XS GIS Cut Line= 4
      2452920.67     13530870.19      2453617.29     13527676.21
      2454918.36     13526811.68      2455123.66      13525879.3
#Sta/Elev= 30
  1121.9   254.8  1747.6  257.07    2469     253  2544.3   253.5  2810.2  250.11
    2852  249.15  3458.6  242.18  3659.1   243.4  3987.8  241.91  4087.3  242.45
  4155.7  242.17  4260.7  242.34  4804.6  238.61  4852.2  226.44  4952.5  225.03
  4960.3  214.74  4961.8  213.74  5032.8  214.74  5038.6  223.26  5047.6  224.62
  5270.1  225.49  5364.5  232.75  5528.8  233.02  5615.8  239.49  5760.2  236.72
  6108.9  244.83  6309.5  248.27  6533.7  252.49  6673.8  255.89  6907.8  260.94
#Mann= 20 ,-1 , 0
  1121.9     .05       0  1747.6     .04       0    2469    .013       0
  2544.3     .04       0  2810.2     .05       0    2852     .12       0
  3458.6     .05       0  3659.1     .12       0  3987.8     .05       0
  4087.3     .12       0  4155.7     .05       0  4260.7     .04       0
  4804.6     .12       0  4960.3     .05       0  5032.8      .1       0
  5364.5     .04       0  6108.9     .05       0  6309.5     .12       0
  6533.7     .05       0  6673.8     .04       0
Bank Sta=4960.3,5032.8
XS Rating Curve= 0 ,0
Exp/Cntr=0.3,0.1

Type RM Length L Ch R = 1 ,293423  ,575,575,575
BEGIN DESCRIPTION:
Mapping XS f57bc0aa
END DESCRIPTION:
XS GIS Cut Line= 3
      2453858.16     13530466.57       2454550.3     13527796.04
      2455277.87     13526400.82
#Sta/Elev= 30
  2244.4  251.02  2454.3  251.78  2762.1  253.07  2862.1   253.2  3469.7  242.02
  3686.9   239.3  4057.6  241.33  4158.7   242.2  4330.9  241.58    4563  241.36
  4664.1   241.3  4680.4  241.13  4765.2  241.41  4911.3  238.09  4957.9  225.06
  4973.2  221.53  4979.4  215.51  4980.9  214.51  5051.9  215.51  5060.7  223.91
    5089  226.11  5288.2  229.99  5424.4  233.19    5481  230.22    5557  232.28
  5635.9  240.74  5697.5  241.37  6040.3  244.53  6217.1  246.43  6576.7  251.58
#Mann= 20 ,-1 , 0
  2244.4     .12       0  2454.3     .05       0  2762.1     .12       0
  2862.1     .05       0  3469.7     .12       0  4057.6     .05       0
  4158.7     .12       0  4330.9     .05       0    4563     .12       0
  4664.1     .04       0  4680.4     .05       0  4765.2     .12       0
  4957.9      .1       0  4979.4     .05       0  5051.9      .1       0
  5288.2     .05       0  5424.4     .12       0  5697.5     .04       0
  6040.3     .05       0  6217.1     .12       0
Bank Sta=4979.4,5051.9
XS Rating Curve= 0 ,0
Exp/Cntr=0.3,0.1

Type RM Length L Ch R = 1 ,292848  ,836,836,836
BEGIN DESCRIPTION:
Mapping XS f3640e66
END DESCRIPTION:
XS GIS Cut Line= 3
      2454326.91     13530779.05       2454995.4     13528129.87
      2455371.91     13526649.52
#Sta/Elev= 30
  2280.5  248.88  2501.9  247.18  3120.1  250.98  3754.9  238.69  3898.8  238.05
  4160.1  238.45  4457.8  239.93  4852.7  240.27  4896.4  234.99  4950.2   224.7
  4955.9  222.62  4960.9  213.21  4962.4  212.21  5033.4  213.21  5038.4  222.61
  5204.9  225.81  5244.8  230.02  5301.9   230.2  5305.9  230.16  5337.6  227.73
  5347.9  224.21  5477.3  229.41    5554  235.75  5656.6   234.8  5662.6  234.84
  5824.1  238.13  5909.7  241.44    6045  245.03  6421.8  245.97  6540.2   247.5
#Mann= 16 ,-1 , 0
  2280.5     .05       0  3754.9     .12       0  3898.8     .05       0
  4160.1     .12       0  4457.8     .05       0  4896.4     .12       0
  4960.9     .05       0  5033.4     .12       0  5204.9     .12       0
  5301.9      .1       0  5305.9     .12       0  5656.6     .05       0
  5662.6     .12       0  5824.1     .04       0  5909.7     .05       0
  6421.8     .12       0
Bank Sta=4960.9,5033.4
XS Rating Curve= 0 ,0
Exp/Cntr=0.3,0.1