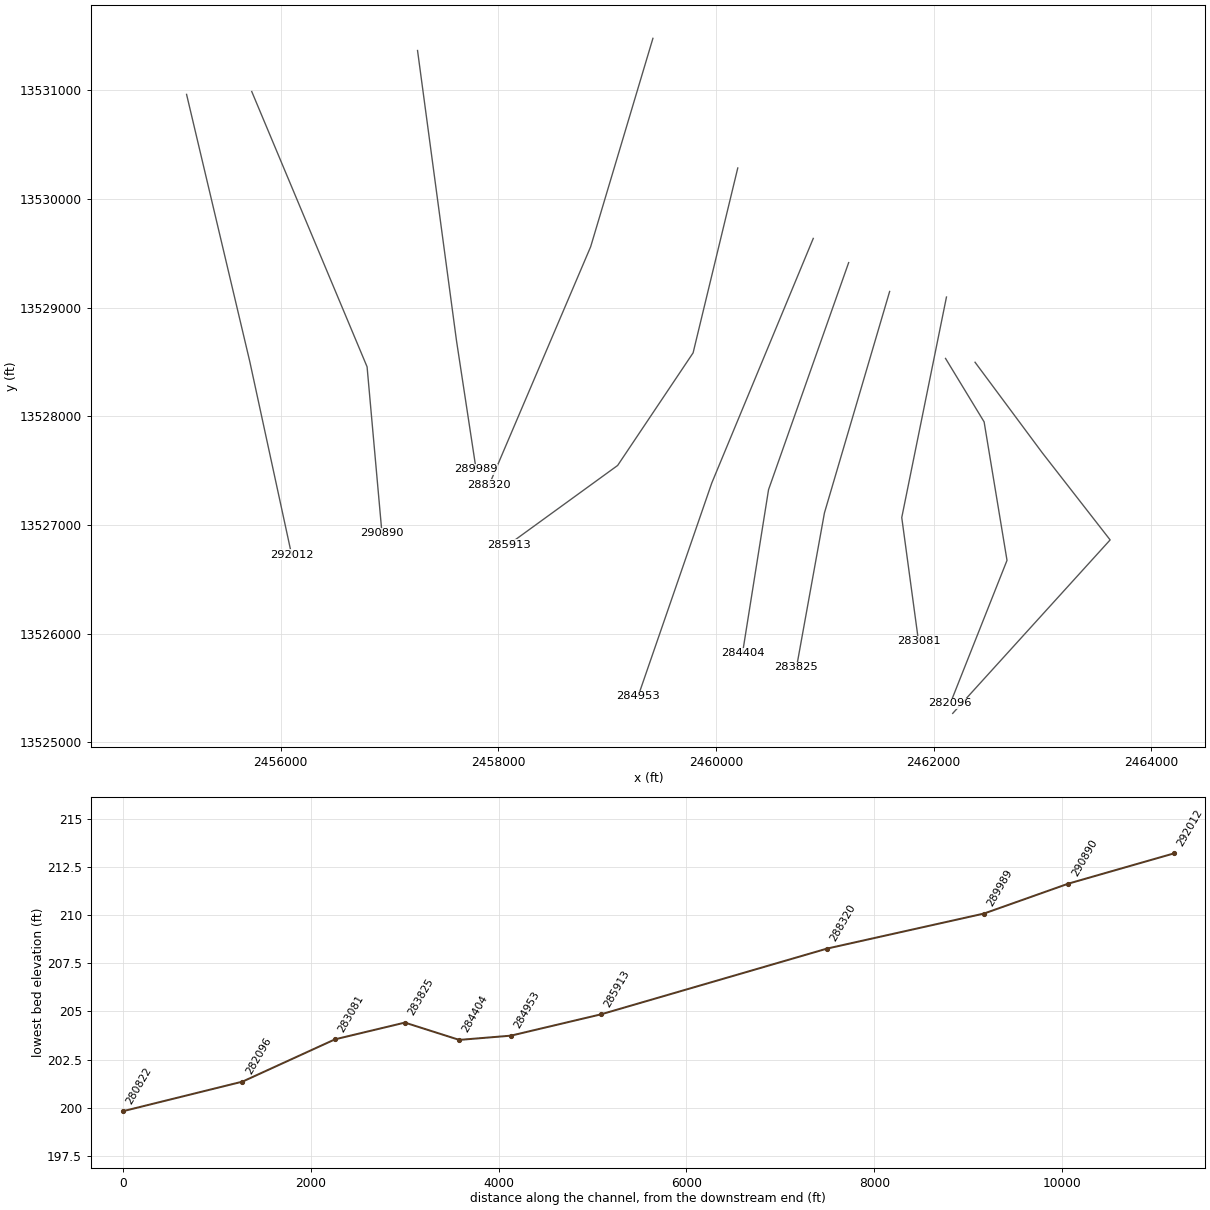
HEC-RAS study COLETO CREEK.prj: COLETO CREEK Base Level Engineering

--- COLETO CREEK.g01 (geometry) --- (continued)

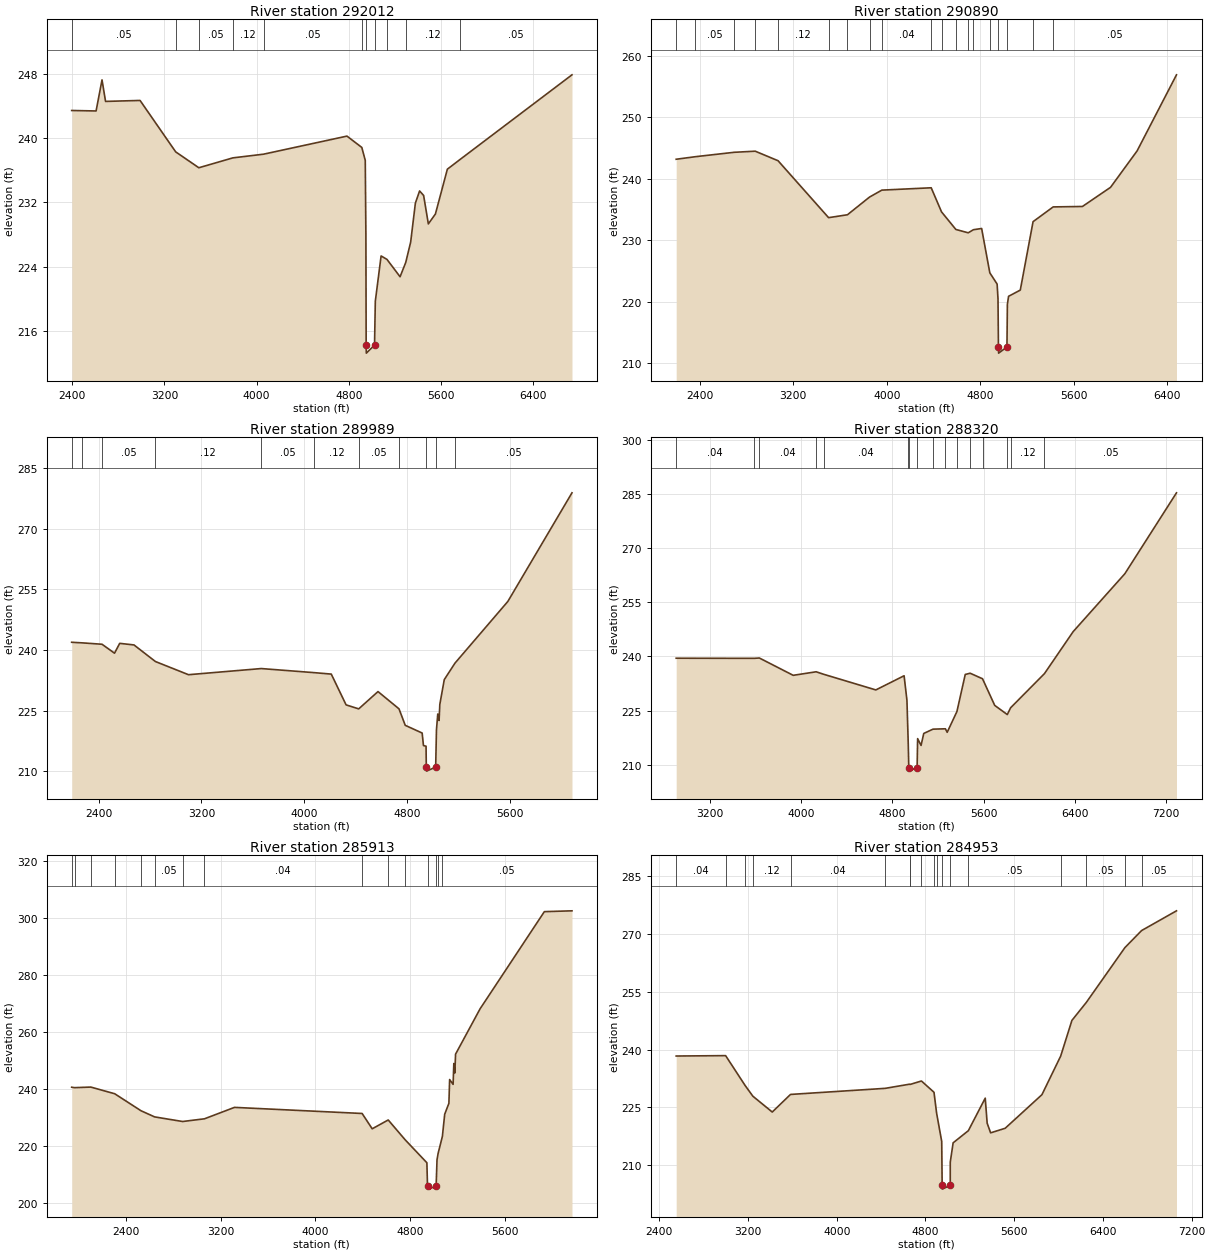
Type RM Length L Ch R = 1 ,292012  ,1122,1122,1122
BEGIN DESCRIPTION:
Mapping XS 4b35aebe
END DESCRIPTION:
XS GIS Cut Line= 3
      2455134.21     13530961.32      2455714.42      13528506.5
      2456099.61     13526726.05
#Sta/Elev= 30
  2394.5  243.43  2606.5  243.37  2657.9  247.24  2688.7  244.56  2988.3  244.68
  3297.5  238.28  3498.7   236.3  3793.9  237.53  4060.7  237.99  4784.9  240.24
  4913.6  238.83  4943.7  237.22  4949.2  227.92  4951.5  214.22    4953  213.22
  5024.2  214.22    5031  219.68  5081.2  225.32  5132.2  224.89  5245.9  222.73
    5295   224.5    5338  227.05  5378.9   231.9  5415.5  233.41  5450.5  232.85
  5491.4  229.31  5552.8  230.54  5656.5  236.12  5770.5  237.37  6738.6  247.87
#Mann= 11 ,-1 , 0
  2394.5     .05       0  3297.5     .12       0  3498.7     .05       0
  3793.9     .12       0  4060.7     .05       0  4913.6     .12       0
  4951.5     .05       0  5024.2     .12       0  5132.2      .1       0
    5295     .12       0  5770.5     .05       0
Bank Sta=4951.5,5024.2
XS Rating Curve= 0 ,0
Exp/Cntr=0.3,0.1

Type RM Length L Ch R = 1 ,290890  ,901,901,901
BEGIN DESCRIPTION:
Mapping XS 0021216f
END DESCRIPTION:
XS GIS Cut Line= 3
      2455733.18     13530987.37      2456792.94     13528455.14
      2456929.89       13526923.
#Sta/Elev= 30
  2197.7  243.18  2359.6  243.59    2694  244.31  2874.4  244.49  3069.9  242.94
  3502.5  233.68  3663.7  234.15    3853  237.03  3958.6  238.16    4381  238.54
  4469.4  234.62  4592.2  231.76  4697.8  231.22  4742.7  231.72  4812.8  231.92
  4882.8  224.71  4945.3  222.88  4952.9  220.49  4956.7  212.65  4958.2  211.65
  5029.5  212.65  5033.2  219.58  5043.3  220.89  5143.7   221.9  5253.1  233.03
  5425.4  235.43  5675.8   235.5  5916.2  238.61  6143.9  244.54    6481  256.91
#Mann= 19 ,-1 , 0
  2197.7     .12       0  2359.6     .05       0    2694     .12       0
  2874.4     .05       0  3069.9     .12       0  3502.5     .05       0
  3663.7     .12       0    3853     .05       0  3958.6     .04       0
    4381     .05       0  4469.4     .12       0  4592.2     .05       0
  4697.8     .12       0  4742.7     .05       0  4882.8      .1       0
  4956.7     .05       0  5029.5      .1       0  5253.1     .12       0
  5425.4     .05       0
Bank Sta=4956.7,5029.5
XS Rating Curve= 0 ,0
Exp/Cntr=0.3,0.1

Type RM Length L Ch R = 1 ,289989  ,1669,1669,1669
BEGIN DESCRIPTION:
Mapping XS 5a8f8676
END DESCRIPTION:
XS GIS Cut Line= 3
       2457256.6     13531365.01      2457614.68     13528694.82
      2457794.42     13527513.61
#Sta/Elev= 30
  2191.3  241.95  2274.4   241.8  2427.2  241.46  2524.3  239.25  2564.6  241.68
  2675.6  241.29  2842.1  237.19  3099.4  233.93  3664.7  235.45  4075.7  234.44
  4209.2  234.08  4324.4  226.47  4422.4  225.48  4572.4  229.76  4735.6  225.49
  4784.3  221.41  4915.6  219.51  4925.8  216.42  4945.9  216.25  4947.9  211.09
  4949.4  210.09  5020.7  211.09  5026.8  220.27  5036.9  224.22  5047.1  222.61
  5052.9  226.58  5087.5  232.71  5170.7  236.79  5581.8  252.05  6080.2   278.9
#Mann= 11 ,-1 , 0
  2191.3    .013       0  2274.4     .12       0  2427.2     .05       0
  2842.1     .12       0  3664.7     .05       0  4075.7     .12       0
  4422.4     .05       0  4735.6      .1       0  4947.9     .05       0
  5020.7      .1       0  5170.7     .05       0
Bank Sta=4947.9,5020.7
XS Rating Curve= 0 ,0
Exp/Cntr=0.3,0.1

Type RM Length L Ch R = 1 ,288320  ,2407,2407,2407
BEGIN DESCRIPTION:
Mapping XS a00ba95f
END DESCRIPTION:
XS GIS Cut Line= 3
      2459419.61     13531476.98      2458847.28     13529559.35
      2457914.69     13527369.05
#Sta/Elev= 30
  2907.3   239.5  3589.3  239.47  3635.8  239.56  3932.1  234.77  4133.2  235.75
  4197.9  235.07  4655.8  230.73  4903.4  234.65  4928.3  227.87  4939.6  216.02
  4944.5  209.27    4946  208.27  5017.5  209.27  5021.9  217.26  5051.9  215.38
  5075.6  218.69  5156.5  219.88  5264.9  219.98  5280.9  219.01    5366  224.75
    5439  235.01  5481.9  235.35  5590.3  233.82  5697.1  226.45  5807.3  223.92
  5836.5   225.8  6132.7  235.24    6384  246.85  6836.6  262.86  7289.1  285.25
#Mann= 16 ,-1 , 0
  2907.3     .04       0  3589.3    .013       0  3635.8     .04       0
  4133.2     .05       0  4197.9     .04       0  4939.6      .1       0
  4944.5     .05       0  5017.5      .1       0  5156.5     .12       0
  5264.9     .04       0    5366     .12       0  5481.9     .05       0
  5590.3     .12       0  5807.3     .04       0  5836.5     .12       0
  6132.7     .05       0
Bank Sta=4944.5,5017.5
XS Rating Curve= 0 ,0
Exp/Cntr=0.3,0.1

Type RM Length L Ch R = 1 ,285913  ,960,960,960
BEGIN DESCRIPTION:
Mapping XS 0dcfca42
END DESCRIPTION:
XS GIS Cut Line= 4
      2460199.31     13530284.27      2459788.85     13528583.54
      2459095.51     13527547.81      2458094.03     13526820.24
#Sta/Elev= 30
  1936.8  240.62  1962.1  240.48  2098.7  240.68  2300.8  238.34  2524.3  232.35
    2639  230.21  2875.4  228.59  3060.6  229.54  3314.5  233.55  4394.7  231.41
    4480  226.03  4615.5  229.13  4759.1  222.16  4942.8  214.11    4948  205.85
  4949.5  204.85    5021  205.85  5028.6  215.22  5038.2  217.47    5074  223.38
  5093.5  231.15  5129.1  234.99  5135.2  243.33  5164.6  241.63  5170.8  248.96
  5179.3  245.63  5185.5  252.24  5392.6  268.13  5936.8  302.27  6170.6  302.56
#Mann= 15 ,-1 , 0
  1936.8    .013       0  1962.1     .04       0  2098.7     .03       0
  2300.8     .04       0  2524.3     .03       0    2639     .05       0
  2875.4     .03       0  3060.6     .04       0  4394.7     .12       0
  4615.5     .03       0  4759.1      .1       0    4948     .05       0
    5021      .1       0  5038.2     .12       0    5074     .05       0
Bank Sta=4948,5021
XS Rating Curve= 0 ,0
Exp/Cntr=0.3,0.1

Type RM Length L Ch R = 1 ,284953  ,549,549,549
BEGIN DESCRIPTION:
Mapping XS dffc4d8f
END DESCRIPTION:
XS GIS Cut Line= 3
      2460893.04     13529636.37      2459960.04     13527385.18
      2459283.83     13525425.02
#Sta/Elev= 30
  2552.4  238.32  2998.1  238.42  3174.6  230.63  3243.7  227.88  3418.4  223.77
  3583.1  228.34  4436.4  229.92  4656.3     231  4660.3  230.93  4763.4  231.83
  4876.7   228.9  4900.6   223.4  4946.2  216.13  4950.2  204.74  4951.7  203.74
  5023.2  204.74  5023.3  210.77  5049.2  215.77  5186.3  218.92  5338.6  227.38
  5355.9  220.88  5387.1  218.36  5518.4  219.55  5849.8  228.28  6018.6  238.29
    6120  247.57  6249.7  252.24    6598  266.49  6748.1  270.91  7062.8  276.04
#Mann= 18 ,-1 , 0
  2552.4     .04       0  2998.1     .05       0  3174.6     .04       0
  3243.7     .12       0  3583.1     .04       0  4436.4     .12       0
  4656.3     .05       0  4660.3     .04       0  4763.4     .05       0
  4876.7      .1       0  4900.6     .05       0  4950.2     .05       0
  5023.2     .05       0  5186.3     .05       0  6018.6     .12       0
  6249.7     .05       0    6598     .12       0  6748.1     .05       0
Bank Sta=4950.2,5023.2
XS Rating Curve= 0 ,0
Exp/Cntr=0.3,0.1

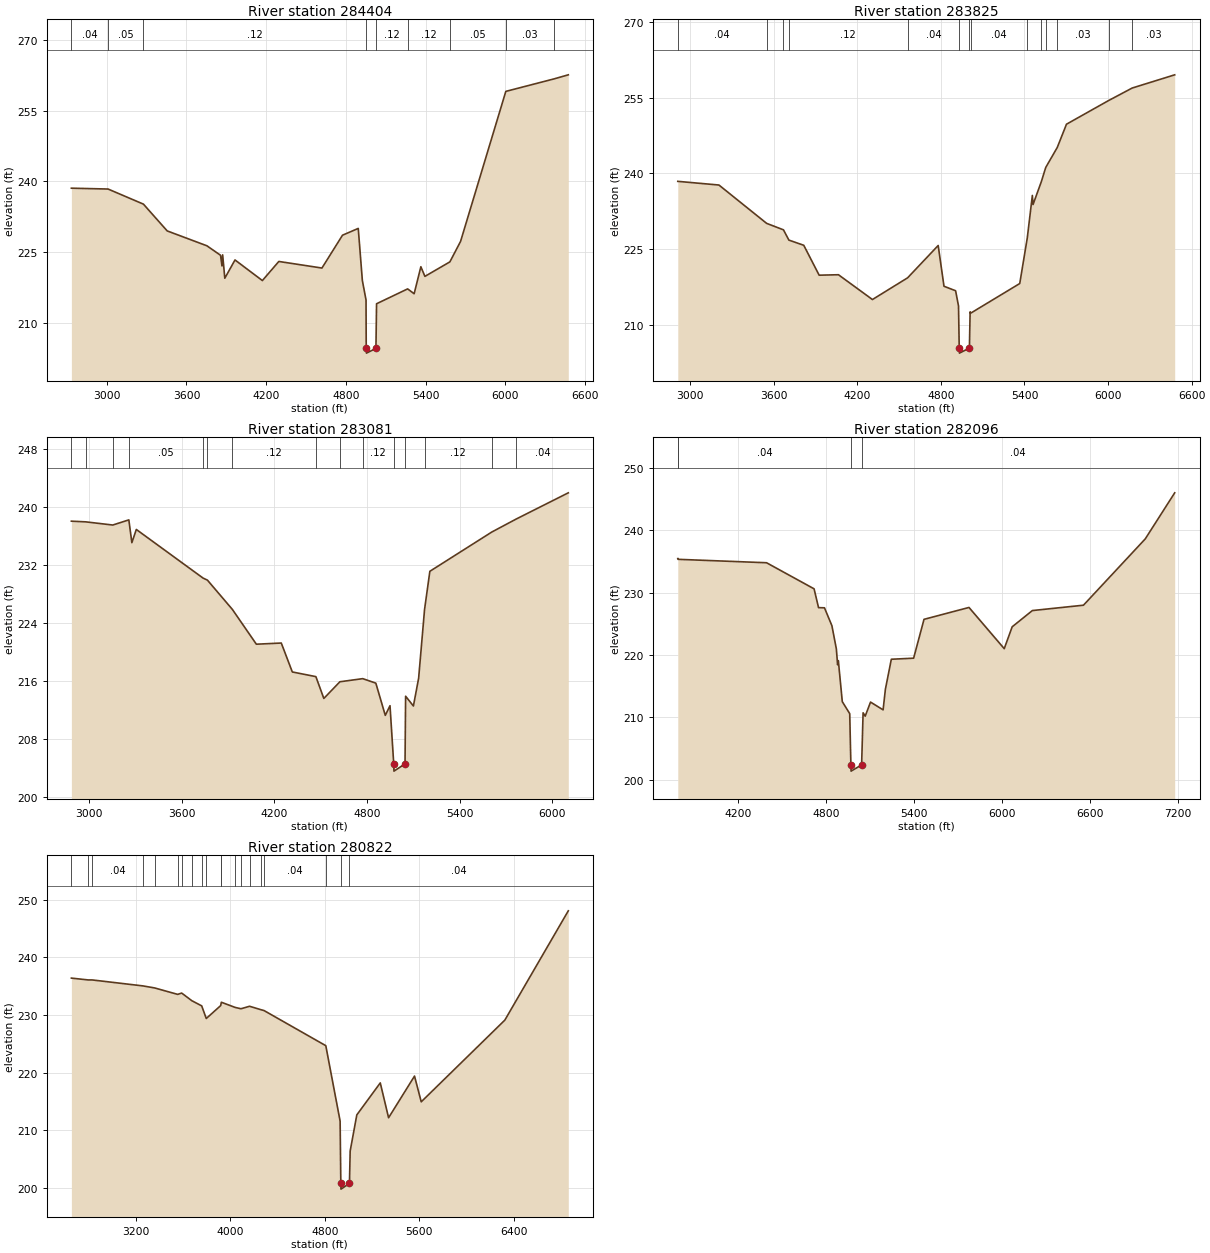
Type RM Length L Ch R = 1 ,284404  ,579,579,579
BEGIN DESCRIPTION:
Mapping XS 010c50de
END DESCRIPTION:
XS GIS Cut Line= 3
      2461218.31     13529413.82      2460482.18     13527325.26
      2460242.61     13525819.39
#Sta/Elev= 30
  2734.2  238.57  3010.4  238.39  3276.4  235.18  3455.2  229.49    3754  226.33
  3856.9  224.31  3867.2  222.06  3872.5  224.41  3888.7  219.44  3965.4  223.32
  4171.4  218.94  4295.2     223  4619.7   221.6  4774.4  228.58  4892.9  230.02
  4923.8  218.95  4951.4  214.82  4952.9  204.52  4954.4  203.52    5026  204.52
  5030.6  214.01  5264.5  217.17  5313.5  216.14  5364.1  221.88  5394.5  219.83
  5582.4  222.91  5662.8  227.26  6003.3  259.14  6368.1  261.81  6473.5  262.66
#Mann= 9 ,-1 , 0
  2734.2     .04       0  3010.4     .05       0  3276.4     .12       0
  4952.9     .05       0    5026     .12       0  5264.5     .12       0
  5582.4     .05       0  6003.3     .03       0  6368.1     .05       0
Bank Sta=4952.9,5026
XS Rating Curve= 0 ,0
Exp/Cntr=0.3,0.1

Type RM Length L Ch R = 1 ,283825  ,744,744,744
BEGIN DESCRIPTION:
Mapping XS db7cba5f
END DESCRIPTION:
XS GIS Cut Line= 3
      2461594.94     13529148.47      2460995.77     13527111.27
      2460738.98     13525690.37
#Sta/Elev= 30
    2911  238.43  3206.5   237.7    3549  230.11  3669.7  228.83  3708.5   226.8
  3815.4  225.77  3925.9  219.85  4064.5  219.94  4308.4  215.03    4561  219.33
  4780.4  225.73  4822.1  217.66  4905.5  216.77  4926.4  213.75  4931.5  205.42
    4933  204.42  5004.6  205.42  5009.7   212.6  5013.1  212.32    5366   218.2
  5420.1  227.23  5456.5  235.64  5461.5  233.84  5520.8  238.36  5552.6  241.18
  5635.5  245.15  5701.4  249.74  6003.3  254.42  6173.6  256.91  6478.4  259.52
#Mann= 14 ,-1 , 0
    2911     .04       0    3549     .03       0  3669.7     .05       0
  3708.5     .12       0    4561     .04       0  4931.5     .05       0
  5004.6     .04       0  5013.1     .04       0  5420.1     .05       0
  5520.8     .03       0  5552.6     .05       0  5635.5     .03       0
  6003.3     .05       0  6173.6     .03       0
Bank Sta=4931.5,5004.6
XS Rating Curve= 0 ,0
Exp/Cntr=0.3,0.1

Type RM Length L Ch R = 1 ,283081  ,985,985,985
BEGIN DESCRIPTION:
Mapping XS 6f81d50e
END DESCRIPTION:
XS GIS Cut Line= 3
      2462117.08     13529097.09      2461706.22     13527068.47
      2461860.15     13525931.15
#Sta/Elev= 30
    2886  238.01  2977.6  237.92    3154  237.48    3258  238.19  3277.6  235.05
  3306.5  236.87  3738.3  230.17    3767  229.88  3928.6  225.84  4083.7  221.05
  4245.1  221.21  4316.6  217.22  4469.1  216.58  4520.6  213.57  4624.6  215.87
  4772.6   216.3  4857.3  215.68  4918.5  211.24  4949.1  212.57  4973.2  204.55
  4974.7  203.55  5046.3  204.55  5050.1  213.88  5100.6  212.53  5134.5  216.37
  5172.8  225.84  5207.1   231.1  5607.8  236.51  5767.4  238.32  6103.5  241.92
#Mann= 15 ,-1 , 0
    2886     .04       0  2977.6     .05       0    3154    .013       0
    3258     .05       0  3738.3     .04       0    3767     .05       0
  3928.6     .12       0  4469.1      .1       0  4624.6     .03       0
  4772.6     .12       0  4973.2     .05       0  5046.3     .12       0
  5172.8     .12       0  5607.8     .05       0  5767.4     .04       0
Bank Sta=4973.2,5046.3
XS Rating Curve= 0 ,0
Exp/Cntr=0.3,0.1

Type RM Length L Ch R = 1 ,282096  ,1274,1274,1274
BEGIN DESCRIPTION:
Mapping XS 29cc7cef
END DESCRIPTION:
XS GIS Cut Line= 4
      2462108.51     13528532.22       2462463.1     13527948.45
      2462673.47     13526674.72      2462152.01     13525358.25
#Sta/Elev= 30
  3786.7  235.49  3788.1  235.37  4392.2  234.82  4716.5  230.63  4746.9  227.61
  4787.4  227.58  4838.1  224.71  4868.5  220.98  4876.9  218.43    4882   219.1
    4909  212.51  4959.7  210.58  4967.6  202.35  4969.1  201.35  5040.8  202.35
  5050.9  210.72  5065.3  210.18  5101.6  212.44  5187.4  211.19    5203   214.5
  5243.5  219.32  5395.6  219.49  5466.5  225.73  5773.3  227.64  6013.8  221.02
  6067.9  224.53  6205.7  227.14  6554.3     228  6975.8  238.65  7176.7  246.05
#Mann= 4 ,-1 , 0
  3786.7     .05       0  3788.1     .04       0  4967.6     .04       0
  5040.8     .04       0
Bank Sta=4967.6,5040.8
XS Rating Curve= 0 ,0
Exp/Cntr=0.3,0.1

Type RM Length L Ch R = 1 ,280822  ,2151,2151,2151
BEGIN DESCRIPTION:
Mapping XS 6add1652
END DESCRIPTION:
XS GIS Cut Line= 4
      2462379.74      13528497.1      2462997.83     13527663.72
      2463621.07     13526862.67      2462174.49       13525267.
#Sta/Elev= 30
  2655.8  236.38  2799.2  236.06    2833  236.06  3261.2  235.03  3361.8  234.67
  3555.6  233.56  3589.3  233.79  3675.7  232.46  3758.8  231.57  3797.6  229.38
  3919.8  231.62  3925.1   232.2    4042   231.3  4091.3  231.07  4164.2   231.5
  4257.5  230.92  4286.4  230.76  4809.4  224.67  4930.6   211.6  4936.5  200.81
    4938  199.81  5009.7  200.81  5015.6   206.4  5071.8  212.67  5270.5  218.22
  5340.8  212.18  5560.4   219.4  5617.2  214.94  6324.9   229.1  6862.1  248.04
#Mann= 20 ,-1 , 0
  2655.8     .04       0  2799.2    .013       0    2833     .04       0
  3261.2    .013       0  3361.8     .04       0  3555.6    .013       0
  3589.3     .04       0  3675.7    .013       0  3758.8     .12       0
  3797.6    .013       0  3919.8     .05       0  3925.1    .013       0
    4042     .05       0  4091.3    .013       0  4164.2     .05       0
  4257.5    .013       0  4286.4     .04       0  4809.4     .05       0
  4936.5     .04       0  5009.7     .04       0
Bank Sta=4936.5,5009.7
XS Rating Curve= 0 ,0
Exp/Cntr=0.3,0.1