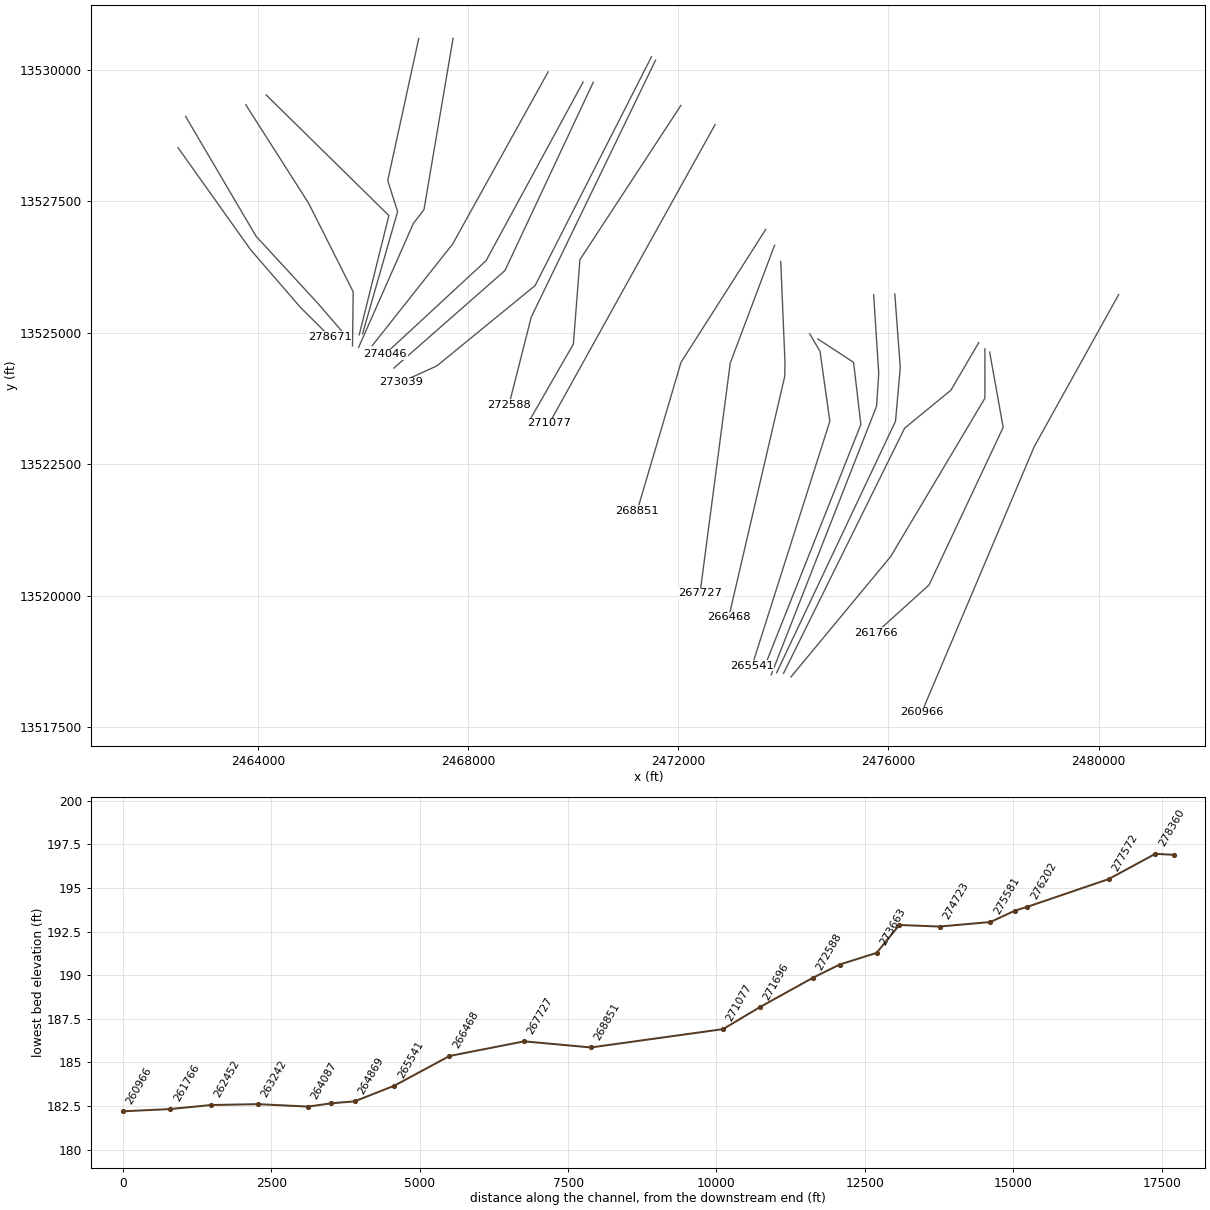
HEC-RAS study COLETO CREEK.prj: COLETO CREEK Base Level Engineering

--- COLETO CREEK.g01 (geometry) --- (continued)

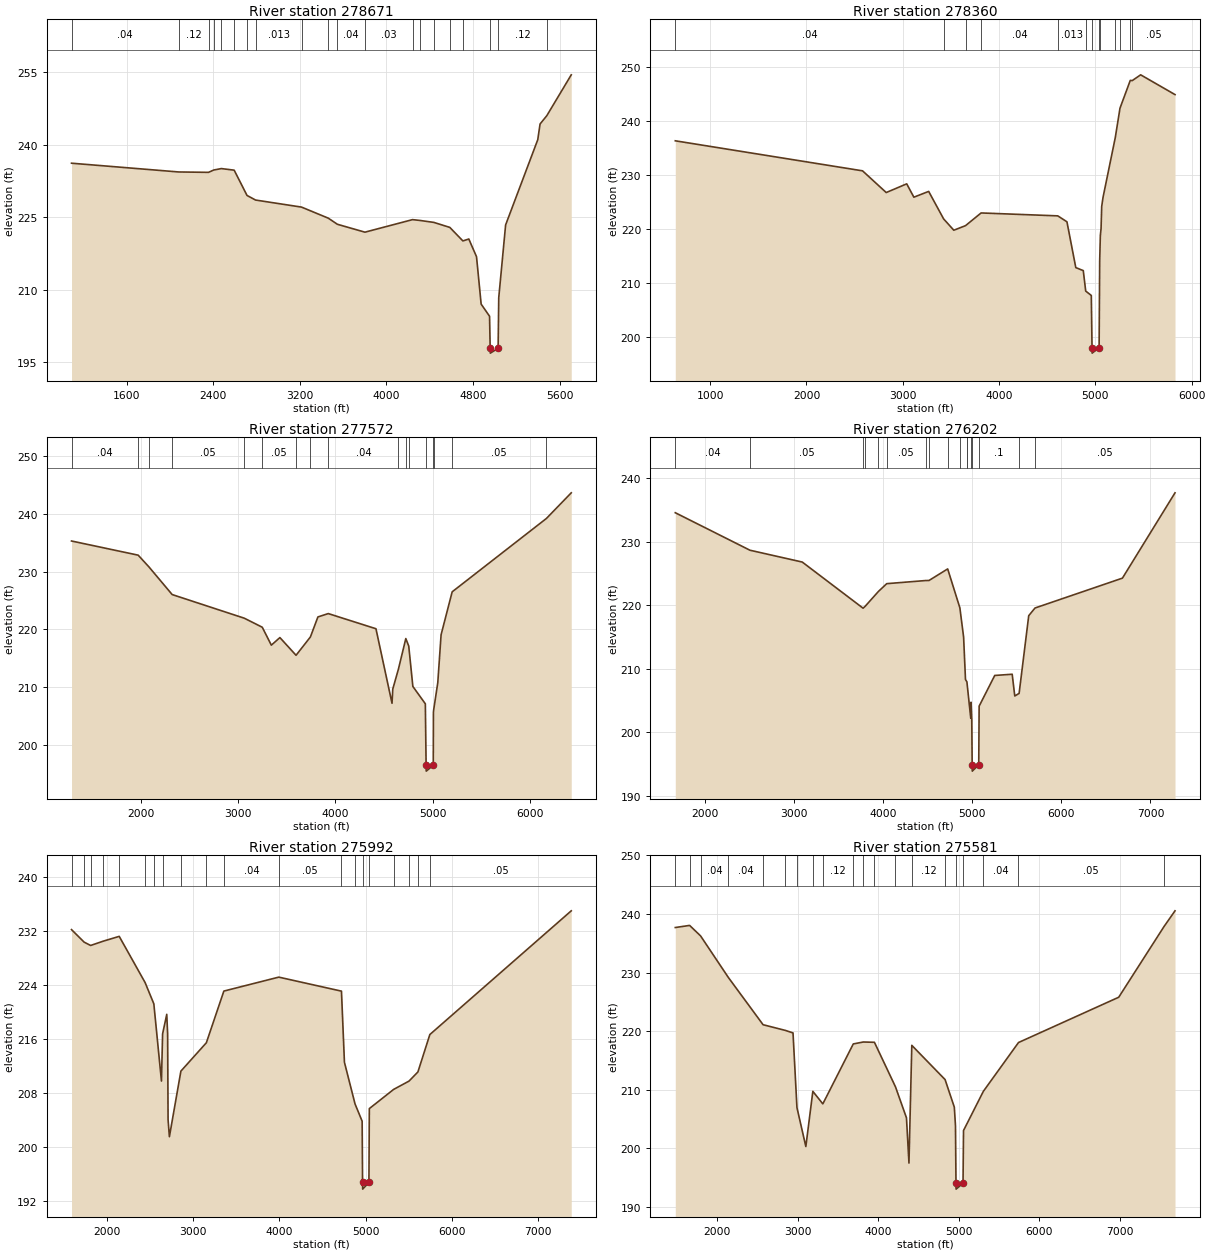
Type RM Length L Ch R = 1 ,278671  ,311,311,311
BEGIN DESCRIPTION:
Mapping XS e628781d
END DESCRIPTION:
XS GIS Cut Line= 4
      2462476.99      13528517.9      2463862.41     13526573.45
       2464813.4     13525476.36      2465366.38     13524928.84
#Sta/Elev= 30
  1089.8  236.14  2079.6  234.33  2355.5  234.25  2403.6  234.73  2474.1  235.03
  2592.7   234.7  2711.4  229.48  2790.2  228.53  3215.2  227.07  3462.7  224.78
  3546.5  223.52  3801.1  221.89  4240.5  224.48  4310.3  224.31  4437.6  223.91
    4585  222.88  4706.2  220.08  4760.8  220.48  4832.1  216.82  4874.8  207.03
  4952.5  204.52  4958.2   197.9  4959.7   196.9  5031.7   197.9  5037.4  208.33
    5101  223.39    5398     241  5419.2  244.24  5481.3  245.95  5707.4   254.4
#Mann= 20 ,-1 , 0
  1089.8     .04       0  2079.6     .12       0  2355.5    .013       0
  2403.6     .04       0  2474.1    .013       0  2592.7    .013       0
  2711.4     .04       0  2790.2    .013       0  3215.2     .04       0
  3462.7     .05       0  3546.5     .04       0  3801.1     .03       0
  4240.5     .04       0  4310.3     .05       0  4437.6     .05       0
    4585     .12       0  4706.2    .013       0  4958.2     .05       0
  5031.7     .12       0  5481.3     .05       0
Bank Sta=4958.2,5031.7
XS Rating Curve= 0 ,0
Exp/Cntr=0.3,0.1

Type RM Length L Ch R = 1 ,278360  ,788,788,788
BEGIN DESCRIPTION:
Mapping XS bb63c48f
END DESCRIPTION:
XS GIS Cut Line= 4
       2462621.2     13529112.37       2463962.9     13526834.28
      2465121.55     13525579.08      2465669.37     13524945.66
#Sta/Elev= 30
   637.7  236.28  2582.3  230.72  2828.2   226.7  3041.1  228.31  3115.3  225.84
  3269.1  226.91  3424.3  221.82  3530.1  219.72  3651.9  220.57  3813.6  222.92
  4609.6  222.38    4705  221.28  4796.9   212.8  4874.6  212.24  4899.9  208.45
    4958  207.64  4965.5  197.96    4967  196.96    5039  197.96    5045  214.02
  5051.8  218.73  5059.2  219.99  5065.8  224.11  5080.1  225.84  5207.2   236.9
  5255.8  242.32  5362.7  247.47    5383  247.43  5470.5   248.5  5827.2  244.84
#Mann= 13 ,-1 , 0
   637.7     .04       0  3424.3     .12       0  3651.9    .013       0
  3813.6     .04       0  4609.6    .013       0  4899.9      .1       0
  4965.5     .05       0    5039      .1       0  5051.8     .05       0
  5207.2     .12       0  5255.8     .05       0  5362.7     .12       0
    5383     .05       0
Bank Sta=4965.5,5039
XS Rating Curve= 0 ,0
Exp/Cntr=0.3,0.1

Type RM Length L Ch R = 1 ,277572  ,1370,1370,1370
BEGIN DESCRIPTION:
Mapping XS c1c04ee9
END DESCRIPTION:
XS GIS Cut Line= 4
      2463767.01     13529333.76      2464964.93     13527458.76
      2465811.29     13525779.07      2465798.27     13524750.43
#Sta/Elev= 30
  1290.4   235.3  1975.3  232.85  2085.3  230.83  2324.5  226.04  3065.8  221.95
  3250.2  220.39  3343.4  217.29  3431.4   218.6  3597.4  215.54  3744.8  218.71
    3822  222.17  3928.4  222.75  4418.3  220.13  4583.4  207.24  4591.2   209.7
  4649.3  213.15  4725.2  218.43  4755.3  217.13  4797.6  210.15  4925.8  207.15
  4933.7  196.51  4935.2  195.51  5007.2  196.51  5008.9  205.73  5010.9  206.04
  5053.7  210.82  5087.6  219.09  5201.4  226.51    6170   239.2    6425  243.63
#Mann= 17 ,-1 , 0
  1290.4     .04       0  1975.3     .03       0  2085.3     .04       0
  2324.5     .05       0  3065.8     .04       0  3250.2     .05       0
  3597.4     .04       0  3744.8    .013       0  3928.4     .04       0
  4649.3      .1       0  4725.2     .04       0  4755.3      .1       0
  4933.7     .05       0  5007.2      .1       0  5010.9     .12       0
  5201.4     .05       0    6170     .03       0
Bank Sta=4933.7,5007.2
XS Rating Curve= 0 ,0
Exp/Cntr=0.3,0.1

Type RM Length L Ch R = 1 ,276202  ,210,210,210
BEGIN DESCRIPTION:
Mapping XS 431b3b7c
END DESCRIPTION:
XS GIS Cut Line= 3
      2464155.46     13529519.81      2466490.52     13527228.15
      2465926.28     13524962.49
#Sta/Elev= 30
  1669.2  234.57  2507.1  228.67  3093.7  226.81  3776.3  219.55  3798.2  219.83
  3948.7  222.19  4041.5  223.41  4477.9   223.9  4515.6  223.91  4725.3  225.73
  4862.1  219.61    4904  215.01  4925.1  208.33  4940.8  207.97  4941.2  207.94
  4984.2  202.24  4987.5  204.76  4995.7  201.94  5000.1  194.92  5001.6  193.92
  5073.8  194.92  5078.2  204.14  5253.3  208.97  5449.1  209.16    5478  205.74
  5526.8  206.15  5634.6  218.37  5705.2  219.58    6686  224.28  7275.8   237.7
#Mann= 17 ,-1 , 0
  1669.2     .04       0  2507.1     .05       0  3776.3     .12       0
  3798.2     .05       0  3948.7    .013       0  4041.5     .05       0
  4477.9     .04       0  4515.6     .05       0  4725.3     .04       0
  4862.1     .05       0  4940.8      .1       0  4941.2     .05       0
  4984.2      .1       0  5000.1     .05       0  5073.8      .1       0
  5526.8     .12       0  5705.2     .05       0
Bank Sta=5000.1,5073.8
XS Rating Curve= 0 ,0
Exp/Cntr=0.3,0.1

Type RM Length L Ch R = 1 ,275992  ,411,411,411
BEGIN DESCRIPTION:
Mapping XS 9b678326
END DESCRIPTION:
XS GIS Cut Line= 4
      2467059.13     13530594.23      2466468.86     13527892.88
      2466656.36      13527302.6      2465989.86     13524983.71
#Sta/Elev= 30
  1587.4  232.21  1734.1  230.35  1809.1  229.86  1951.3  230.48  2140.6  231.21
  2440.8  224.36  2542.3   221.2  2630.7  209.74  2643.9  216.73  2692.1  219.64
  2702.3  216.73  2707.5     204  2722.8  201.48  2856.1  211.21  3151.5  215.42
  3354.6  223.09  3991.6  225.16  4718.9  223.08  4753.4  212.52  4876.4  206.34
  4958.8  203.78  4963.7   194.7  4965.2   193.7  5037.4   194.7  5042.2  205.65
  5324.4   208.5  5502.4  209.73  5605.8  211.09  5744.2  216.64  7384.6     235
#Mann= 20 ,-1 , 0
  1587.4     .04       0  1734.1     .05       0  1809.1     .04       0
  1951.3     .05       0  2140.6     .05       0  2440.8     .05       0
  2542.3     .12       0  2643.9      .1       0  2856.1     .03       0
  3151.5     .05       0  3354.6     .04       0  3991.6     .05       0
  4718.9     .03       0  4876.4      .1       0  4963.7     .05       0
  5037.4      .1       0  5324.4     .12       0  5502.4     .05       0
  5605.8     .12       0  5744.2     .05       0
Bank Sta=4963.7,5037.4
XS Rating Curve= 0 ,0
Exp/Cntr=0.3,0.1

Type RM Length L Ch R = 1 ,275581  ,858,858,858
BEGIN DESCRIPTION:
Mapping XS 4c3b863b
END DESCRIPTION:
XS GIS Cut Line= 4
      2467712.32     13530596.75      2467158.26     13527339.25
      2466955.45     13527075.44      2465915.43     13524724.34
#Sta/Elev= 30
  1481.1   237.7  1659.2  238.06  1795.4  236.27  2140.2  229.18  2571.8  221.11
  2848.5  220.14  2943.6  219.71  2992.6  206.96    3103  200.32  3189.9  209.74
    3314   207.6  3692.2  217.83  3816.4  218.16    3955  218.11  4216.2  210.52
    4353  205.22    4384   197.5  4419.3  217.59  4832.6  211.75  4947.5  207.04
    4962  203.84  4968.2  194.05  4969.7  193.05  5055.6  194.05  5061.7  203.05
  5308.1  209.74  5744.7  218.07  6989.7   225.8  7551.2  237.84    7689  240.55
#Mann= 20 ,-1 , 0
  1481.1     .04       0  1659.2     .05       0  1795.4     .04       0
  2140.2     .04       0  2571.8     .12       0  2848.5      .1       0
  2992.6     .12       0  3189.9      .1       0    3314     .12       0
  3692.2     .04       0  3816.4     .05       0    3955     .04       0
  4216.2      .1       0  4419.3     .12       0  4832.6      .1       0
  4968.2     .05       0  5055.6      .1       0  5308.1     .04       0
  5744.7     .05       0  7551.2     .03       0
Bank Sta=4968.2,5055.6
XS Rating Curve= 0 ,0
Exp/Cntr=0.3,0.1

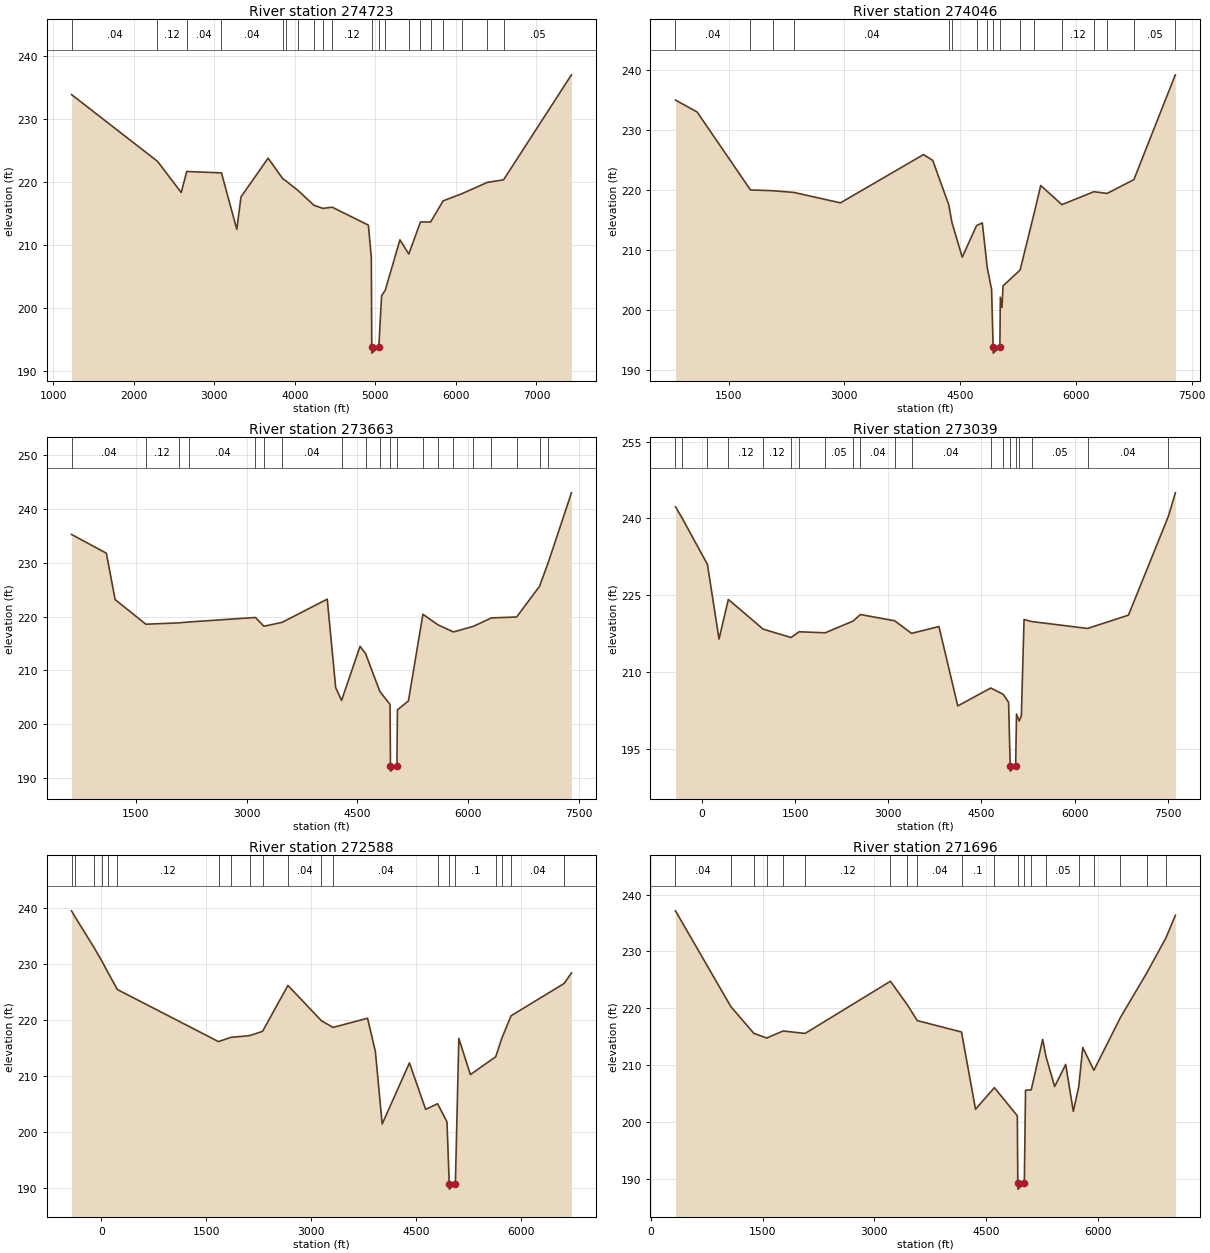
Type RM Length L Ch R = 1 ,274723  ,677,677,677
BEGIN DESCRIPTION:
Mapping XS 25af1151
END DESCRIPTION:
XS GIS Cut Line= 3
      2469522.21     13529958.72      2467705.13     13526688.21
      2466173.85     13524755.88
#Sta/Elev= 30
  1227.8   233.9    2295  223.29  2589.5  218.33  2658.6  221.67  3089.3  221.45
  3279.8  212.48  3331.9  217.63  3668.7  223.79  3851.6  220.51  3891.4  220.16
  4044.2  218.61  4236.8   216.3  4349.8   215.8  4464.4  215.99    4914  213.14
    4950  207.95  4955.7  193.79  4957.2  192.79  5043.1  193.79  5077.9  201.93
  5123.2  202.79  5305.4   210.8  5415.5  208.55  5560.5  213.65  5686.2  213.64
  5841.8     217  6075.2  218.14  6388.5  219.93  6592.3  220.35  7434.7  237.04
#Mann= 20 ,-1 , 0
  1227.8     .04       0    2295     .12       0  2658.6     .04       0
  3089.3     .04       0  3851.6     .12       0  3891.4     .05       0
  4044.2     .05       0  4236.8     .05       0  4349.8     .12       0
  4464.4     .12       0  4955.7     .05       0  5043.1     .12       0
  5123.2     .05       0  5415.5     .04       0  5560.5     .05       0
  5686.2     .12       0  5841.8     .05       0  6075.2     .05       0
  6388.5     .12       0  6592.3     .05       0
Bank Sta=4955.7,5043.1
XS Rating Curve= 0 ,0
Exp/Cntr=0.3,0.1

Type RM Length L Ch R = 1 ,274046  ,383,383,383
BEGIN DESCRIPTION:
Mapping XS 57152a7f
END DESCRIPTION:
XS GIS Cut Line= 3
      2470186.28     13529763.44      2468340.55      13526370.5
      2466419.36     13524595.09
#Sta/Elev= 30
   810.6  234.97  1091.8  232.97  1782.4  220.02  2069.3  219.89  2345.9   219.6
    2949  217.87  4025.1   225.9  4144.3  224.94  4352.5  217.55    4393  214.64
  4526.7  208.83  4712.3  214.09  4787.2  214.54  4851.1   207.1  4907.4  203.46
  4927.2  193.88  4928.7  192.88  5014.7  193.88  5020.8  202.18  5041.8  200.47
    5056  204.07    5277   206.7  5462.8  216.35  5544.2  220.76  5818.5  217.57
    6232  219.72  6404.9  219.44  6751.6  221.73  7288.2  239.16    7289  239.13
#Mann= 17 ,-1 , 0
   810.6     .04       0  1782.4     .12       0  2069.3     .05       0
  2345.9     .04       0  4352.5     .05       0    4393     .12       0
  4712.3     .05       0  4851.1     .12       0  4927.2     .05       0
  5014.7     .12       0    5277     .12       0  5462.8     .05       0
  5818.5     .12       0    6232     .05       0  6404.9     .12       0
  6751.6     .05       0  7288.2     .03       0
Bank Sta=4927.2,5014.7
XS Rating Curve= 0 ,0
Exp/Cntr=0.3,0.1

Type RM Length L Ch R = 1 ,273663  ,624,624,624
BEGIN DESCRIPTION:
Mapping XS 8ab762e9
END DESCRIPTION:
XS GIS Cut Line= 3
      2470381.61     13529763.46      2468699.92       13526183.
      2466586.01     13524329.42
#Sta/Elev= 30
   630.8  235.29  1101.8  231.81  1221.4  223.17  1636.9   218.6  2084.1  218.85
  2225.5  219.02  3120.9  219.85    3235  218.22  3480.7  218.94  4092.5  223.26
  4206.6  206.82  4286.4  204.43  4536.9  214.49  4612.9  213.09  4804.2   206.1
  4942.7  203.68  4948.3  192.28  4949.8  191.28  5035.8  192.28  5042.4  202.67
  5191.3  204.33  5387.4  220.45    5590  218.49  5800.8  217.16  6067.6  218.19
  6314.7  219.77  6656.3  219.94  6966.4  225.65  7086.2  230.15    7398  243.03
#Mann= 20 ,-1 , 0
   630.8     .04       0  1636.9     .12       0  2084.1     .05       0
  2225.5     .04       0  3120.9    .013       0    3235     .04       0
  3480.7     .04       0  4286.4     .12       0  4612.9     .12       0
  4804.2     .05       0  4948.3     .05       0  5035.8      .1       0
  5387.4     .05       0    5590     .12       0  5800.8     .05       0
  6067.6     .12       0  6314.7     .04       0  6656.3     .12       0
  6966.4     .04       0  7086.2     .05       0
Bank Sta=4948.3,5035.8
XS Rating Curve= 0 ,0
Exp/Cntr=0.3,0.1

Type RM Length L Ch R = 1 ,273039  ,451,451,451
BEGIN DESCRIPTION:
Mapping XS 9ae37aa8
END DESCRIPTION:
XS GIS Cut Line= 4
      2471488.36      13530245.2      2469272.84     13525896.54
      2467403.05      13524370.5      2466715.53     13524057.99
#Sta/Elev= 30
  -427.4  242.28  -327.1  240.23      87  231.03   274.1  216.43   423.8  224.17
   985.2  218.36  1434.2  216.73  1562.9  217.85    1984  217.65  2433.9  219.95
  2549.9  221.22  3102.5     220  3373.6  217.54    3815  218.87  4118.1  203.35
  4648.7  206.86  4850.2  205.62  4936.1  204.06  4962.7  191.61  4964.2  190.61
  5050.2  191.61  5063.9  201.76  5108.4  200.42  5142.2  201.44  5185.3  220.25
  5307.5  219.85  6207.8   218.5  6866.6   221.1  7509.6  240.43  7621.8  245.01
#Mann= 20 ,-1 , 0
  -427.4     .04       0  -327.1    .013       0      87     .05       0
   423.8     .12       0   985.2     .12       0  1434.2    .013       0
  1562.9     .12       0    1984     .05       0  2433.9     .12       0
  2549.9     .04       0  3102.5     .12       0  3373.6     .04       0
  4648.7     .04       0  4850.2     .12       0  4962.7     .05       0
  5050.2     .12       0  5108.4     .03       0  5307.5     .05       0
  6207.8     .04       0  7509.6     .05       0
Bank Sta=4962.7,5050.2
XS Rating Curve= 0 ,0
Exp/Cntr=0.3,0.1

Type RM Length L Ch R = 1 ,272588  ,892,892,892
BEGIN DESCRIPTION:
Mapping XS cef1050f
END DESCRIPTION:
XS GIS Cut Line= 3
      2471566.51     13530180.13      2469199.92     13525297.58
      2468778.06     13523636.17
#Sta/Elev= 30
    -424  239.45  -371.5  238.33  -101.9   232.9     9.2   230.5   103.6  228.31
   231.3  225.42  1675.4  216.14  1849.1  216.89  2119.8  217.21  2304.6  217.97
  2666.9  226.15  3144.4  219.87  3311.4  218.67  3804.2  220.31  3915.7  214.38
    4013  201.46  4402.3  212.34  4633.7  204.07  4804.2  205.07  4938.3  201.85
  4971.1  190.85  4972.6  189.85  5058.6  190.85  5107.7  216.71  5272.8  210.26
  5634.4  213.44  5719.3  216.66  5853.6  220.74  6611.3   226.5    6716  228.38
#Mann= 20 ,-1 , 0
    -424     .04       0  -371.5    .013       0  -101.9     .05       0
     9.2     .12       0   103.6     .05       0   231.3     .12       0
  1675.4     .12       0  1849.1    .013       0  2119.8     .04       0
  2304.6     .12       0  2666.9     .04       0  3144.4     .12       0
  3311.4     .04       0  4804.2     .12       0  4971.1     .05       0
  5058.6      .1       0  5634.4     .12       0  5719.3     .05       0
  5853.6     .04       0  6611.3     .05       0
Bank Sta=4971.1,5058.6
XS Rating Curve= 0 ,0
Exp/Cntr=0.3,0.1

Type RM Length L Ch R = 1 ,271696  ,619,619,619
BEGIN DESCRIPTION:
Mapping XS ecca09c9
END DESCRIPTION:
XS GIS Cut Line= 4
      2472048.26     13529320.73      2470127.01      13526389.6
      2470002.01     13524785.43      2469203.41     13523396.56
#Sta/Elev= 30
   328.3  237.13  1072.4  220.28  1381.9  215.57  1553.8  214.76  1774.7  215.99
  2069.5  215.56  3216.1  224.74  3444.7  220.57  3576.5  217.82    4171  215.81
  4359.2  202.22  4612.3  206.02  4920.9  201.08  4927.3  189.17  4928.8  188.17
  5014.8  189.17  5031.2  205.57  5107.8  205.63  5261.9  214.52    5306  211.48
  5422.4  206.22  5570.8   210.1  5673.2  201.85  5745.8  206.18  5800.1  213.09
  5949.4  209.08  6306.3  218.37  6656.9  226.14  6916.1  232.33  7044.1  236.34
#Mann= 20 ,-1 , 0
   328.3     .04       0  1072.4     .05       0  1381.9    .013       0
  1553.8     .05       0  1774.7     .12       0  2069.5     .12       0
  3216.1     .04       0  3444.7     .05       0  3576.5     .04       0
    4171      .1       0  4612.3     .12       0  4927.3     .05       0
  5014.8     .12       0  5107.8     .04       0    5306     .05       0
  5745.8     .12       0  5949.4     .04       0  6306.3     .05       0
  6656.9     .04       0  6916.1     .04       0
Bank Sta=4927.3,5014.8
XS Rating Curve= 0 ,0
Exp/Cntr=0.3,0.1

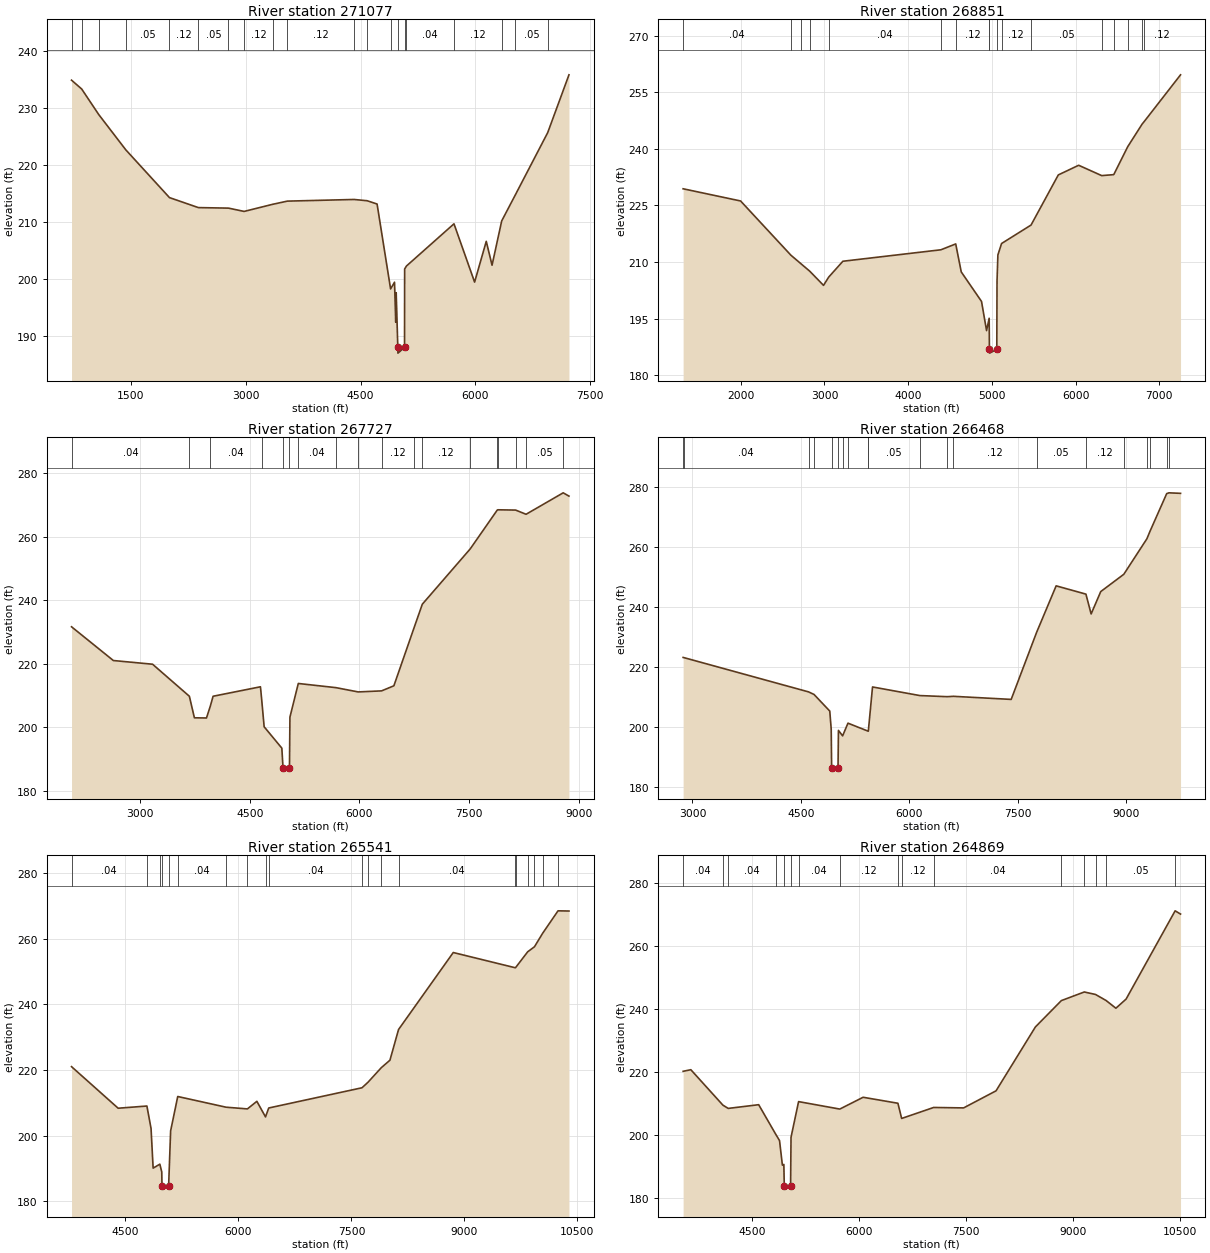
Type RM Length L Ch R = 1 ,271077  ,2226,2226,2226
BEGIN DESCRIPTION:
Mapping XS 1c335a73
END DESCRIPTION:
XS GIS Cut Line= 3
      2472699.29     13528956.12      2470939.51     13525792.37
      2469544.09     13523279.23
#Sta/Elev= 30
   726.4  234.91   858.8  233.36  1081.3  228.87  1434.9  222.66    2005  214.26
  2382.7   212.5  2775.2  212.41  2980.2  211.83  3352.1  213.08  3544.6  213.64
  4414.7  213.93  4585.6  213.71  4715.9  213.13  4892.3   198.2  4943.6  199.38
  4959.6  192.34  4965.3  197.53  4986.7  187.91  4988.2  186.91  5074.3  187.91
  5075.7   201.7  5099.5  202.23    5720  209.65  5989.3   199.4  6141.5  206.57
    6217  202.37    6343  210.16  6519.6   214.7  6943.9  225.69  7221.2  235.85
#Mann= 20 ,-1 , 0
   726.4     .05       0   858.8     .04       0  1081.3     .05       0
  1434.9     .05       0    2005     .12       0  2382.7     .05       0
  2775.2     .05       0  2980.2     .12       0  3352.1    .013       0
  3544.6     .12       0  4414.7     .04       0  4585.6     .12       0
  4892.3     .04       0  4986.7     .04       0  5074.3     .04       0
  5099.5     .04       0    5720     .12       0    6343     .04       0
  6519.6     .05       0  6943.9     .04       0
Bank Sta=4986.7,5074.3
XS Rating Curve= 0 ,0
Exp/Cntr=0.3,0.1

Type RM Length L Ch R = 1 ,268851  ,1124,1124,1124
BEGIN DESCRIPTION:
Mapping XS 674d77b1
END DESCRIPTION:
XS GIS Cut Line= 3
      2473662.84     13526963.94      2472050.62     13524438.21
      2471214.94     13521612.42
#Sta/Elev= 30
  1311.7   229.4  1998.5  226.17  2599.7   211.8  2724.5  209.45  2824.4  207.57
  2989.4  203.81  3050.7  205.99  3220.5   210.2  4392.2  213.24  4568.7  214.79
  4634.7  207.38  4877.2  199.55  4937.2  191.83  4968.4   195.1  4970.9  188.23
  4971.4  186.86  4972.9  185.86  5059.5  186.86  5062.3     205  5072.7  211.88
  5116.5   214.9  5468.7  219.79  5794.4  233.07  6037.7  235.63  6312.6  232.89
  6456.9  233.15  6624.4  240.57  6795.8  246.53  6818.1  247.14  7254.9  259.59
#Mann= 17 ,-1 , 0
  1311.7     .04       0  2599.7     .05       0  2724.5     .04       0
  2824.4     .05       0  3050.7     .04       0  4392.2     .05       0
  4568.7     .12       0  4970.9      .1       0  4971.4     .05       0
  5059.5      .1       0  5116.5     .12       0  5468.7     .05       0
  6312.6     .12       0  6456.9     .05       0  6624.4     .12       0
  6795.8     .05       0  6818.1     .12       0
Bank Sta=4971.4,5059.5
XS Rating Curve= 0 ,0
Exp/Cntr=0.3,0.1

Type RM Length L Ch R = 1 ,267727  ,1259,1259,1259
BEGIN DESCRIPTION:
Mapping XS e70cd309
END DESCRIPTION:
XS GIS Cut Line= 3
      2473832.13     13526664.51      2472988.12     13524424.32
      2472412.86     13520049.99
#Sta/Elev= 30
  2062.3  231.63  2634.5  221.01  3171.2  219.85  3674.5  209.77  3743.3  202.99
  3908.6  202.93  3961.3  206.67  3999.2  209.77  4647.2  212.75  4664.3  208.66
  4697.6  200.17  4939.7  193.44  4956.1  187.21  4957.6  186.21  5044.2  187.21
  5050.5  203.21    5165  213.79  5679.1  212.48  5984.5  211.13  6304.3  211.46
  6472.7  213.06  6751.6   231.5  6861.7  238.73  7517.7  256.15  7887.7  268.37
  7897.5  268.44  8139.1  268.35  8281.5  267.03  8789.2  273.78  8868.2  272.75
#Mann= 18 ,-1 , 0
  2062.3     .04       0  3674.5      .1       0  3961.3     .04       0
  4664.3     .05       0  4956.1     .05       0  5044.2     .05       0
    5165     .04       0  5679.1     .05       0  5984.5     .04       0
  6304.3     .12       0  6751.6     .05       0  6861.7     .12       0
  7517.7     .05       0  7887.7     .12       0  7897.5     .05       0
  8139.1     .12       0  8281.5     .05       0  8789.2    .013       0
Bank Sta=4956.1,5044.2
XS Rating Curve= 0 ,0
Exp/Cntr=0.3,0.1

Type RM Length L Ch R = 1 ,266468  ,927,927,927
BEGIN DESCRIPTION:
Mapping XS 6afe1868
END DESCRIPTION:
XS GIS Cut Line= 4
      2473949.31     13526352.01      2474029.79     13524438.21
      2474025.96     13524177.15      2472959.87     13519594.81
#Sta/Elev= 30
  2871.3  223.27  2880.6  223.22  4606.4  211.79  4682.4  210.93    4900  205.39
    4920  199.38  4925.9  186.37  4927.4  185.37  5014.2  186.37    5020  198.95
  5077.8  197.13  5151.8  201.36  5432.9  198.67  5435.8  199.31  5491.6  213.43
  6145.6  210.56  6523.4  210.19  6609.8  210.31  7409.7  209.28  7760.8  231.59
  8031.8  247.14  8443.7  244.38  8515.8  237.77  8648.7  245.23  8967.6  250.99
  9286.9  262.82  9330.3  265.34  9561.1  277.89  9593.2  278.15  9752.6  277.98
#Mann= 20 ,-1 , 0
  2871.3     .03       0  2880.6     .04       0  4606.4      .1       0
  4682.4     .12       0  4925.9     .05       0  5014.2     .12       0
  5077.8     .03       0  5151.8     .05       0  5432.9     .12       0
  5435.8     .05       0  6145.6     .12       0  6523.4     .05       0
  6609.8     .12       0  7760.8     .05       0  8443.7     .12       0
  8967.6     .05       0  9286.9     .12       0  9330.3     .05       0
  9561.1    .013       0  9593.2     .05       0
Bank Sta=4925.9,5014.2
XS Rating Curve= 0 ,0
Exp/Cntr=0.3,0.1

Type RM Length L Ch R = 1 ,265541  ,672,672,672
BEGIN DESCRIPTION:
Mapping XS 028935f7
END DESCRIPTION:
XS GIS Cut Line= 4
      2474502.04     13524979.06      2474696.45     13524646.54
      2474883.95     13523320.15      2473402.49     13518669.89
#Sta/Elev= 30
  3783.6  220.97  4402.6  208.31  4784.4  208.98  4839.5  202.14  4867.2  190.06
  4956.3  191.27  4981.7  188.91  4984.6  184.67  4986.1  183.67  5072.9  184.67
  5099.5  201.41  5193.9  211.88  5835.7  208.62    6119   208.1  6244.7  210.41
  6359.4  205.67  6402.2  208.38  7640.8  214.54  7720.7  216.23  7897.1  220.66
  8011.6  222.93    8126  232.28  8852.6  255.73  9674.4   251.1  9679.7  251.12
  9840.9  255.95  9930.6  257.48 10038.6  261.56 10243.8  268.43 10388.9  268.37
#Mann= 20 ,-1 , 0
  3783.6     .04       0  4784.4     .12       0  4956.3      .1       0
  4984.6     .05       0  5072.9      .1       0  5193.9     .04       0
  5835.7     .05       0    6119     .04       0  6359.4     .05       0
  6402.2     .04       0  7640.8     .05       0  7720.7     .04       0
  7897.1     .05       0    8126     .04       0  9674.4     .05       0
  9679.7     .04       0  9840.9     .05       0  9930.6     .04       0
 10038.6    .013       0 10243.8     .04       0
Bank Sta=4984.6,5072.9
XS Rating Curve= 0 ,0
Exp/Cntr=0.3,0.1

Type RM Length L Ch R = 1 ,264869  ,391,391,391
BEGIN DESCRIPTION:
Mapping XS aa8b2799
END DESCRIPTION:
XS GIS Cut Line= 4
      2474654.43     13524883.84      2475335.34     13524438.21
      2475474.23     13523257.65       2473636.8     13518643.63
#Sta/Elev= 30
  3532.6  220.21  3640.8  220.72  4090.4  209.45  4164.8  208.42  4591.3   209.6
  4830.4   200.2  4883.3   198.2  4923.5  190.38  4943.7  190.62  4949.9  183.77
  4951.4  182.77  5038.2  183.77  5044.4  199.25  5150.3  210.58  5727.6  208.21
  6054.6  211.96  6541.8  210.06  6594.2  205.23  7042.9  208.72  7462.4  208.58
  7916.7  214.01  8468.4  234.32  8831.7  242.68  9152.9  245.42  9310.2  244.63
  9457.8  242.72  9595.7  240.26  9738.6  243.16 10425.7  271.21 10501.5  270.18
#Mann= 16 ,-1 , 0
  3532.6     .04       0  4090.4     .12       0  4164.8     .04       0
  4830.4      .1       0  4949.9     .05       0  5038.2      .1       0
  5150.3     .04       0  5727.6     .12       0  6541.8     .05       0
  6594.2     .12       0  7042.9     .04       0  8831.7     .05       0
  9152.9     .04       0  9310.2      .1       0  9457.8     .05       0
 10425.7    .013       0
Bank Sta=4949.9,5038.2
XS Rating Curve= 0 ,0
Exp/Cntr=0.3,0.1

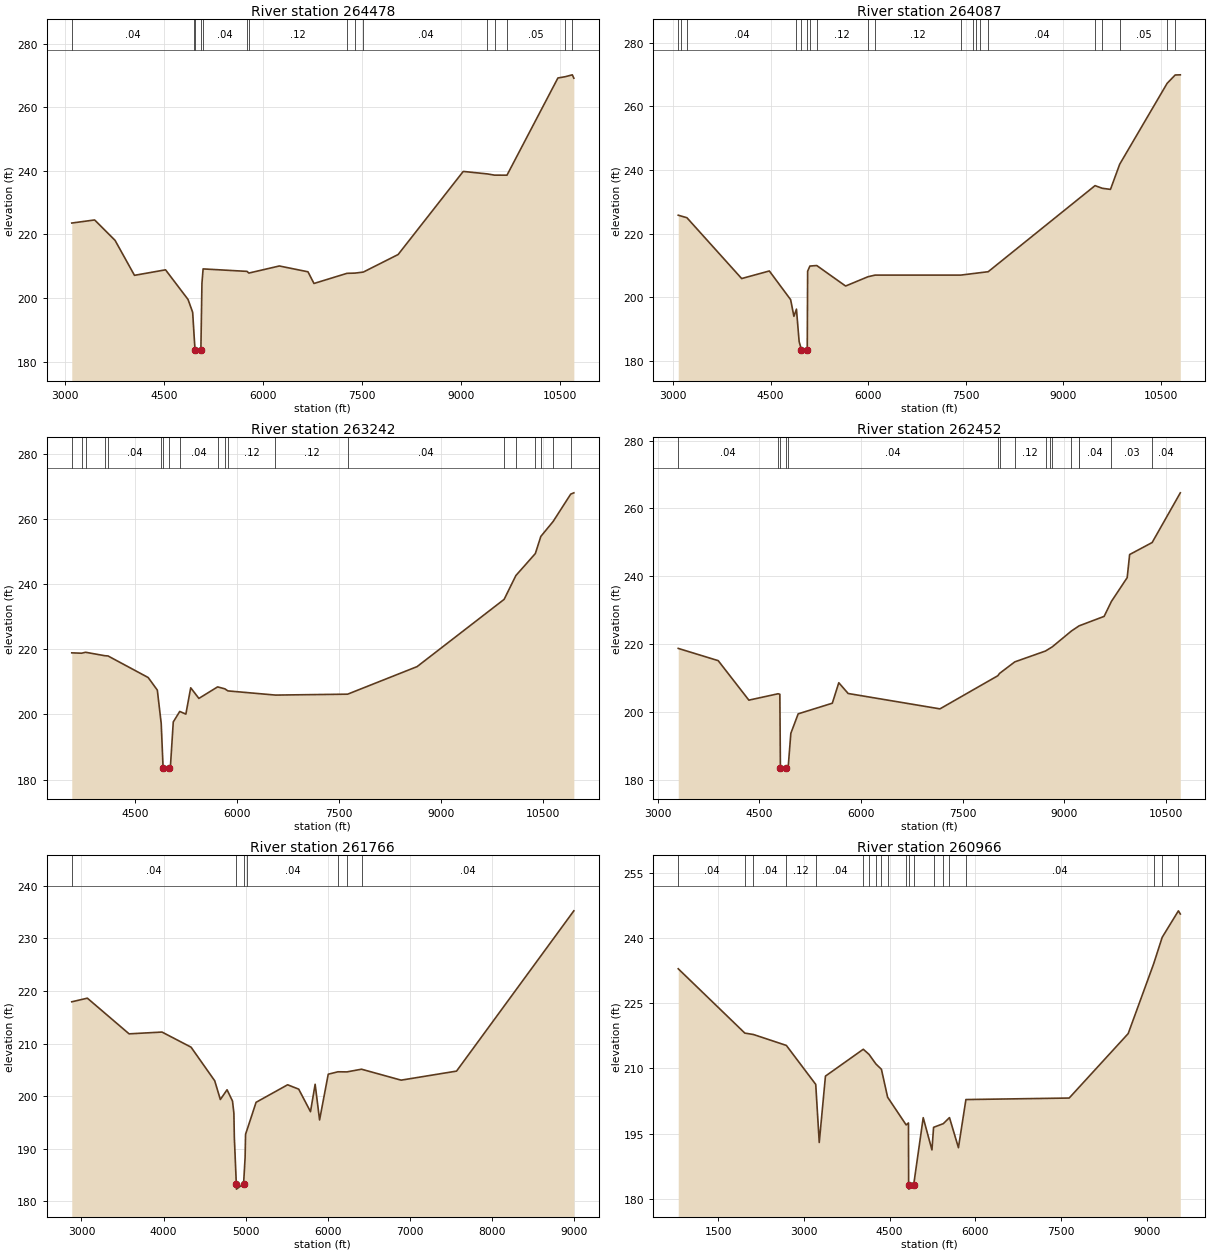
Type RM Length L Ch R = 1 ,264478  ,391,391,391
BEGIN DESCRIPTION:
Mapping XS d2a63f49
END DESCRIPTION:
XS GIS Cut Line= 4
      2475717.28     13525722.94      2475814.51     13524229.87
      2475772.84     13523604.87      2473767.03     13518500.45
#Sta/Elev= 30
    3098  223.56  3444.6  224.53  3753.8  218.12    4048  207.12  4518.9  208.85
  4859.7  199.53  4929.8  195.49  4952.4  187.84  4965.9  183.66  4967.4  182.66
  5054.2  183.66  5070.2  204.58  5087.9  209.14  5754.5  208.36  5780.5  207.83
  6243.3  210.06  6676.9  208.23  6767.7  204.56  7268.2  207.75  7389.3  207.82
  7514.8  208.14  8042.8  213.66  9029.2  239.79  9396.7     239  9503.8  238.62
    9692  238.61 10463.7  269.17   10575  269.57 10682.1  270.16   10705   269.1
#Mann= 15 ,-1 , 0
    3098     .04       0  4952.4      .1       0  4965.9     .05       0
  5054.2      .1       0  5087.9     .04       0  5754.5     .03       0
  5780.5     .12       0  7268.2     .04       0  7389.3     .03       0
  7514.8     .04       0  9396.7     .05       0  9503.8      .1       0
    9692     .05       0   10575     .04       0 10682.1    .013       0
Bank Sta=4965.9,5054.2
XS Rating Curve= 0 ,0
Exp/Cntr=0.3,0.1

Type RM Length L Ch R = 1 ,264087  ,845,845,845
BEGIN DESCRIPTION:
Mapping XS d39adaf3
END DESCRIPTION:
XS GIS Cut Line= 4
      2476120.07     13525736.79      2476224.23     13524340.98
      2476133.95     13523320.15      2473871.28      13518539.7
#Sta/Elev= 30
  3082.3   225.8    3129  225.52  3215.6  225.01  4056.8   205.9    4482  208.28
  4809.2  199.27  4859.4  194.03  4898.4  196.29  4939.8   186.1  4975.9  183.47
  4977.4  182.47  5064.3  183.47  5070.3  208.21    5105  209.82    5210  209.99
  5653.5  203.55  5996.6  206.46  6106.4  206.98  7422.2  206.98  7615.9  207.47
  7663.3  207.59  7722.4  207.74  7844.5  208.05    9486  235.09  9596.6  234.26
  9722.8  233.91  9864.4  241.81   10593  267.22   10717  269.85 10795.7   269.9
#Mann= 20 ,-1 , 0
  3082.3     .04       0    3129     .03       0  3215.6     .04       0
  4898.4      .1       0  4975.9     .05       0  5064.3      .1       0
    5105     .04       0    5210     .12       0  5996.6     .03       0
  6106.4     .12       0  7422.2     .04       0  7615.9     .03       0
  7663.3     .04       0  7722.4     .03       0  7844.5     .04       0
    9486     .05       0  9596.6      .1       0  9864.4     .05       0
   10593     .04       0   10717     .05       0
Bank Sta=4975.9,5064.3
XS Rating Curve= 0 ,0
Exp/Cntr=0.3,0.1

Type RM Length L Ch R = 1 ,263242  ,790,790,790
BEGIN DESCRIPTION:
Mapping XS b175015a
END DESCRIPTION:
XS GIS Cut Line= 4
      2477717.29     13524813.22      2477189.51     13523910.43
      2476307.56     13523188.21      2474002.26     13518528.22
#Sta/Elev= 30
  3563.6  218.93  3708.3  218.82  3766.7  219.11  4050.1  218.05  4096.7  217.98
  4687.6  211.35    4822  207.49  4879.2  197.24  4906.8  183.61  4908.3  182.61
  4995.3  183.61  5014.9   184.1  5056.5  197.71  5151.5  200.94  5241.7  200.12
  5313.1   208.2  5433.3  204.94  5708.8  208.48  5816.5  207.87  5859.2  207.25
  6560.1  205.96  7620.8  206.24  8642.5   214.7  9923.2  235.36 10095.4  242.66
 10381.9  249.42 10462.6  254.68 10643.6  259.27 10902.2  267.67 10948.3  268.07
#Mann= 20 ,-1 , 0
  3563.6     .04       0  3708.3     .03       0  3766.7     .04       0
  4050.1     .03       0  4096.7     .04       0  4879.2     .12       0
  4906.8     .05       0  4995.3     .12       0  5151.5     .04       0
  5708.8     .12       0  5816.5     .05       0  5859.2     .12       0
  6560.1     .12       0  7620.8     .04       0  9923.2     .03       0
 10095.4     .05       0 10381.9     .03       0 10462.6     .05       0
 10643.6     .04       0 10902.2     .05       0
Bank Sta=4906.8,4995.3
XS Rating Curve= 0 ,0
Exp/Cntr=0.3,0.1

Type RM Length L Ch R = 1 ,262452  ,686,686,686
BEGIN DESCRIPTION:
Mapping XS 65569394
END DESCRIPTION:
XS GIS Cut Line= 4
      2477835.34     13524695.16      2477835.34     13523757.65
      2476043.67     13520750.71      2474144.65     13518461.39
#Sta/Elev= 30
  3301.7  218.73  3891.9  215.12  4344.3  203.48  4775.8  205.36  4801.8  205.21
  4810.1  183.56  4811.6  182.56  4898.6  183.56  4927.4  184.37    4964  193.69
  5072.4  199.44  5576.6  202.58    5672  208.61  5810.3  205.44  7165.2  200.91
  8020.3  210.68  8045.2  211.36  8270.5  214.76  8723.7  217.96  8782.9  218.69
  8824.3   219.2    9106  223.85  9220.2  225.38  9221.6  225.39  9589.4  228.17
  9696.4  232.56  9929.7  239.59  9965.7  246.39   10298  249.93 10713.9  264.58
#Mann= 16 ,-1 , 0
  3301.7     .04       0  4775.8      .1       0  4810.1     .04       0
  4898.6      .1       0  4927.4     .04       0  8020.3     .05       0
  8045.2     .04       0  8270.5     .12       0  8723.7     .05       0
  8782.9     .12       0  8824.3     .05       0    9106     .04       0
  9220.2     .05       0  9221.6     .04       0  9696.4     .03       0
   10298     .04       0
Bank Sta=4810.1,4898.6
XS Rating Curve= 0 ,0
Exp/Cntr=0.3,0.1

Type RM Length L Ch R = 1 ,261766  ,800,800,800
BEGIN DESCRIPTION:
Mapping XS ab44832f
END DESCRIPTION:
XS GIS Cut Line= 4
      2477925.62     13524632.66      2478182.56      13523202.1
      2476772.84     13520209.04      2475766.28     13519299.66
#Sta/Elev= 30
  2881.7  217.93  3071.7  218.62  3580.3  211.84  3981.5  212.18  4335.2  209.31
  4623.8  202.92  4692.2  199.36  4774.1  201.21  4840.4  199.07  4857.2  196.79
  4862.8  192.16  4886.9  183.33  4888.4  182.33  4975.4  183.33    4994   188.3
  4999.5  192.76  5020.2  193.71  5127.8  198.83  5511.9  202.16  5647.3  201.33
  5790.9  197.05  5847.5  202.26  5901.6  195.48    6007  204.17  6125.4  204.63
  6235.2  204.61  6412.5  205.12  6895.1  203.04  7570.7  204.76  9000.1  235.22
#Mann= 7 ,-1 , 0
  2881.7     .04       0  4886.9     .05       0  4975.4     .04       0
  5020.2     .04       0  6125.4    .013       0  6235.2     .03       0
  6412.5     .04       0
Bank Sta=4886.9,4975.4
XS Rating Curve= 0 ,0
Exp/Cntr=0.3,0.1

Type RM Length L Ch R = 1 ,260966  ,1038,1038,1038
BEGIN DESCRIPTION:
Mapping XS bcff1614
END DESCRIPTION:
XS GIS Cut Line= 3
      2480381.61       13525727.      2478772.84     13522834.04
      2476631.59     13517784.25
#Sta/Elev= 30
     796  232.93  1962.7  218.12  2112.8   217.8  2690.3  215.28  3204.7  206.31
  3266.3  192.94  3374.9  208.22  4037.7   214.4  4138.5  213.22  4258.3  211.02
  4355.3  209.79  4463.7  203.37  4788.9  196.98  4829.1  197.43  4832.1   183.2
  4833.6   182.2  4920.6   183.2  5087.5  198.65  5240.4  191.23  5269.2  196.43
  5439.2  197.27  5547.6  198.67  5704.5  191.74  5835.4  202.82  7644.6  203.17
  8678.3  218.01  9124.5  234.08  9273.7  240.17    9558  246.27  9591.2  245.54
#Mann= 20 ,-1 , 0
     796     .04       0  1962.7     .04       0  2112.8     .04       0
  2690.3     .12       0  3204.7     .04       0  4037.7     .03       0
  4138.5     .05       0  4258.3     .03       0  4355.3    .013       0
  4463.7     .05       0  4788.9      .1       0  4832.1     .05       0
  4920.6      .1       0  5269.2     .04       0  5439.2     .05       0
  5547.6     .12       0  5835.4     .04       0  9124.5     .05       0
  9273.7     .12       0    9558     .04       0
Bank Sta=4832.1,4920.6
XS Rating Curve= 0 ,0
Exp/Cntr=0.3,0.1