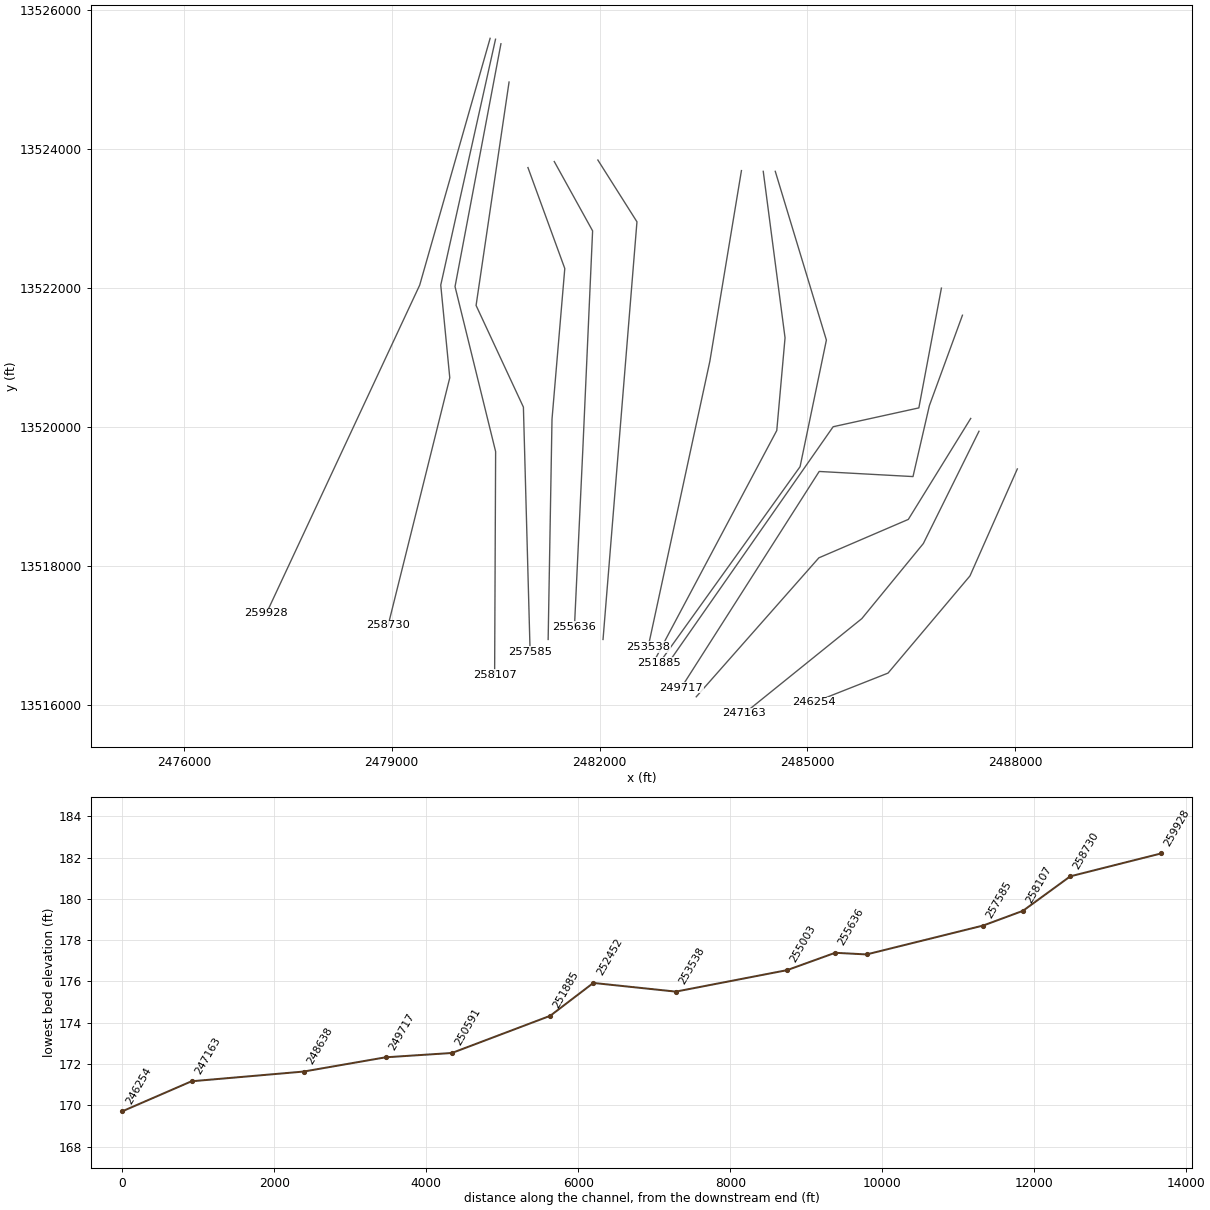
HEC-RAS study COLETO CREEK.prj: COLETO CREEK Base Level Engineering

--- COLETO CREEK.g01 (geometry) --- (continued)

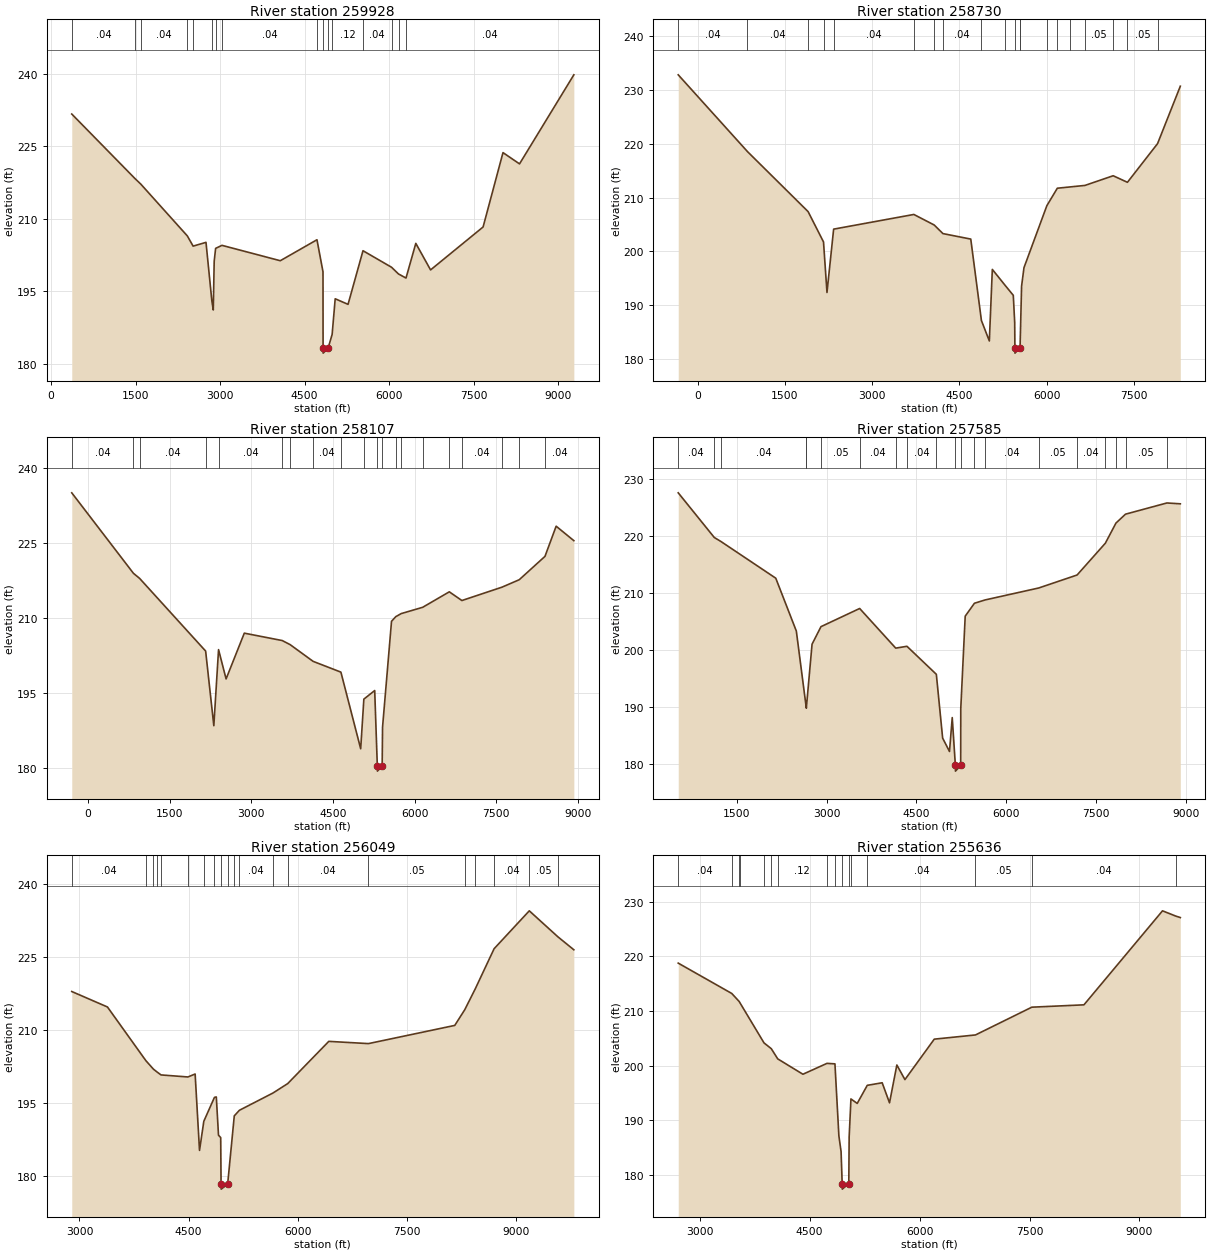
Type RM Length L Ch R = 1 ,259928  ,1198,1198,1198
BEGIN DESCRIPTION:
Mapping XS f62062c0
END DESCRIPTION:
XS GIS Cut Line= 3
      2480420.65     13525596.75      2479404.35     13522042.81
      2477191.48      13517315.5
#Sta/Elev= 30
   365.7  231.65    1487  218.32  1590.4  217.17  2417.4  206.45  2520.8  204.33
  2749.3  205.11  2853.3  193.02  2878.5  191.13  2894.9  201.18  2920.2  203.87
  3033.6  204.49  4068.8  201.31  4720.1  205.65  4827.1  199.02  4828.5   183.2
    4830   182.2  4917.1   183.2  4989.5  186.08  5043.7  193.44    5272  192.29
  5537.5  203.38  6044.3  199.96  6168.1  198.57  6301.1  197.73  6475.3   204.9
  6737.5  199.41  7670.2  208.29  8023.5  223.67  8317.1  221.34  9281.7  239.76
#Mann= 16 ,-1 , 0
   365.7     .04       0    1487    .013       0  1590.4     .04       0
  2417.4     .03       0  2520.8     .12       0  2853.3     .04       0
  2920.2     .12       0  3033.6     .04       0  4720.1      .1       0
  4828.5     .05       0  4917.1      .1       0  4989.5     .12       0
  5537.5     .04       0  6044.3     .03       0  6168.1     .12       0
  6301.1     .04       0
Bank Sta=4828.5,4917.1
XS Rating Curve= 0 ,0
Exp/Cntr=0.3,0.1

Type RM Length L Ch R = 1 ,258730  ,623,623,623
BEGIN DESCRIPTION:
Mapping XS 9a0207b5
END DESCRIPTION:
XS GIS Cut Line= 4
      2480498.79     13525583.79      2479708.17     13522042.81
      2479838.38     13520708.17      2478949.32      13517146.3
#Sta/Elev= 30
  -337.5  232.85   853.4  218.58  1897.5  207.41  2162.6  201.77  2222.3  192.37
  2336.9  204.15  3717.3  206.88  4067.3  204.92    4218  203.32  4696.8   202.3
    4880  187.16  5016.3  183.35  5067.8  196.66  5289.3  193.68  5428.5  191.84
  5452.6  186.83  5456.3  182.09  5457.8  181.09  5545.1  182.09  5546.9  182.93
  5571.2  193.54  5612.4  196.98  6005.7   208.5  6186.3  211.76  6406.1     212
  6661.5  212.28  7147.4  214.08  7392.9  212.86  7911.2  220.05  8302.8  230.73
#Mann= 20 ,-1 , 0
  -337.5     .04       0   853.4     .04       0  1897.5     .05       0
  2162.6     .12       0  2336.9     .04       0  3717.3     .03       0
  4067.3     .03       0    4218     .04       0    4880     .12       0
  5289.3      .1       0  5456.3     .05       0  5545.1      .1       0
  5546.9     .04       0  6005.7     .05       0  6186.3     .05       0
  6406.1     .04       0  6661.5     .05       0  7147.4     .12       0
  7392.9     .05       0  7911.2     .04       0
Bank Sta=5456.3,5545.1
XS Rating Curve= 0 ,0
Exp/Cntr=0.3,0.1

Type RM Length L Ch R = 1 ,258107  ,522,522,522
BEGIN DESCRIPTION:
Mapping XS f66d64ae
END DESCRIPTION:
XS GIS Cut Line= 4
      2480576.92     13525518.69      2479914.33     13522021.11
      2480500.27      13519644.8      2480485.77      13516430.1
#Sta/Elev= 30
  -298.6  235.05   834.4  218.96   946.3  217.96  2160.2  203.42  2310.7   188.5
  2397.5  203.71    2536  197.85  2870.5     207  3567.4  205.52  3711.7  204.71
  4134.7  201.36  4644.8  199.21  5008.1  183.89  5066.4  193.81  5265.6  195.53
  5313.9  180.42  5315.4  179.42  5402.7  180.42  5409.8  188.21  5574.6  209.37
  5653.1   210.3    5753  210.91  6147.3  212.17  6635.9  215.26  6867.3  213.52
  7603.4  216.19  7920.5  217.68  8393.3  222.35  8598.5  228.38  8923.4  225.49
#Mann= 20 ,-1 , 0
  -298.6     .04       0   834.4    .013       0   946.3     .04       0
  2160.2     .05       0  2397.5     .04       0  3567.4     .03       0
  3711.7     .04       0  4134.7     .04       0  4644.8     .12       0
  5066.4     .05       0  5313.9     .05       0  5402.7     .12       0
  5653.1     .05       0    5753     .12       0  6147.3     .04       0
  6635.9     .05       0  6867.3     .04       0  7603.4     .04       0
  7920.5     .05       0  8393.3     .04       0
Bank Sta=5313.9,5402.7
XS Rating Curve= 0 ,0
Exp/Cntr=0.3,0.1

Type RM Length L Ch R = 1 ,257585  ,1536,1536,1536
BEGIN DESCRIPTION:
Mapping XS 31cc418e
END DESCRIPTION:
XS GIS Cut Line= 4
       2480694.1     13524967.43      2480218.15     13521749.84
      2480901.18     13520285.43      2480997.92     13516764.33
#Sta/Elev= 30
   519.6  227.58  1121.9  219.74  1233.7  219.03  2149.6  212.59  2493.3  203.31
  2659.5  189.83  2660.3  189.76  2756.1     201  2905.3  204.08  3551.8  207.27
  4154.2  200.31  4342.1  200.63  4833.2  195.71  4938.7   184.5    5053  182.16
  5098.8  188.11  5151.3  179.71  5152.8  178.71  5240.1  179.71  5241.5   189.7
  5315.6  205.92    5470  208.19  5647.8  208.77  6544.3  210.87  7185.6  213.15
  7657.5  218.73  7835.1  222.27  7994.5  223.83  8686.6   225.8  8910.5  225.65
#Mann= 20 ,-1 , 0
   519.6     .04       0  1121.9    .013       0  1233.7     .04       0
  2659.5     .05       0  2660.3     .04       0  2905.3     .05       0
  3551.8     .04       0  4154.2     .12       0  4342.1     .04       0
  4833.2     .12       0  5151.3     .05       0  5240.1     .12       0
    5470     .05       0  5647.8     .04       0  6544.3     .05       0
  7185.6     .04       0  7657.5     .05       0  7835.1     .12       0
  7994.5     .05       0  8686.6     .12       0
Bank Sta=5151.3,5240.1
XS Rating Curve= 0 ,0
Exp/Cntr=0.3,0.1

Type RM Length L Ch R = 1 ,256049  ,413,413,413
BEGIN DESCRIPTION:
Mapping XS b9fdcc33
END DESCRIPTION:
XS GIS Cut Line= 4
      2480966.87     13523735.48      2481498.54     13522281.52
      2481314.07     13520111.38      2481258.35     13516938.95
#Sta/Elev= 30
  2893.8  217.94  3384.1  214.76  3912.8  203.71  4016.7  201.97  4067.5  201.37
  4120.6  200.79    4490  200.37    4589  200.98  4649.2  185.27  4708.3  191.26
  4854.4  196.18    4880  196.26  4910.1   188.4  4940.2  187.91  4945.3  178.31
  4946.8  177.31  5035.6  178.31  5126.9  192.37  5197.3  193.52  5659.6  197.08
  5861.3  199.01  6425.6  207.69  6970.5  207.23  8156.5  210.97  8293.2  214.18
  8437.9  218.48  8697.3  226.74  9180.6  234.53    9572  229.21  9792.8  226.52
#Mann= 20 ,-1 , 0
  2893.8     .04       0  3912.8     .05       0  4016.7     .12       0
  4067.5     .04       0  4120.6     .12       0    4490     .05       0
  4708.3     .12       0  4854.4     .05       0  4945.3     .05       0
  5035.6     .12       0  5126.9     .03       0  5197.3     .04       0
  5659.6     .03       0  5861.3     .04       0  6970.5     .05       0
  8293.2     .04       0  8437.9     .05       0  8697.3     .04       0
  9180.6     .05       0    9572     .12       0
Bank Sta=4945.3,5035.6
XS Rating Curve= 0 ,0
Exp/Cntr=0.3,0.1

Type RM Length L Ch R = 1 ,255636  ,633,633,633
BEGIN DESCRIPTION:
Mapping XS 2551a458
END DESCRIPTION:
XS GIS Cut Line= 4
      2481346.64      13523822.3      2481900.01     13522824.06
      2481758.95     13519677.36      2481638.11     13517122.34
#Sta/Elev= 30
  2708.2  218.74  3438.4  213.19  3540.5  211.71  3549.3   211.5  3878.6  204.14
  3977.5  203.09  4065.7  201.22  4409.2  198.41  4737.5   200.4    4846  200.31
  4899.7  187.14  4929.7  184.25  4944.6  178.39  4946.1  177.39  5034.9  178.39
  5039.8  186.91  5064.3  193.89  5149.9  193.07  5286.9  196.38  5490.3  196.85
  5590.4  193.18  5690.5   200.1  5800.6  197.43    6201  204.83  6763.1   205.6
  7531.7  210.68  8242.7  211.11  9314.4  228.31  9493.1  227.36  9557.3  227.08
#Mann= 16 ,-1 , 0
  2708.2     .04       0  3438.4     .05       0  3540.5     .12       0
  3549.3     .05       0  3878.6     .12       0  3977.5     .05       0
  4065.7     .12       0  4737.5     .05       0    4846     .12       0
  4944.6     .05       0  5034.9     .12       0  5064.3     .05       0
  5286.9     .04       0  6763.1     .05       0  7531.7     .04       0
  9493.1     .12       0
Bank Sta=4944.6,5034.9
XS Rating Curve= 0 ,0
Exp/Cntr=0.3,0.1

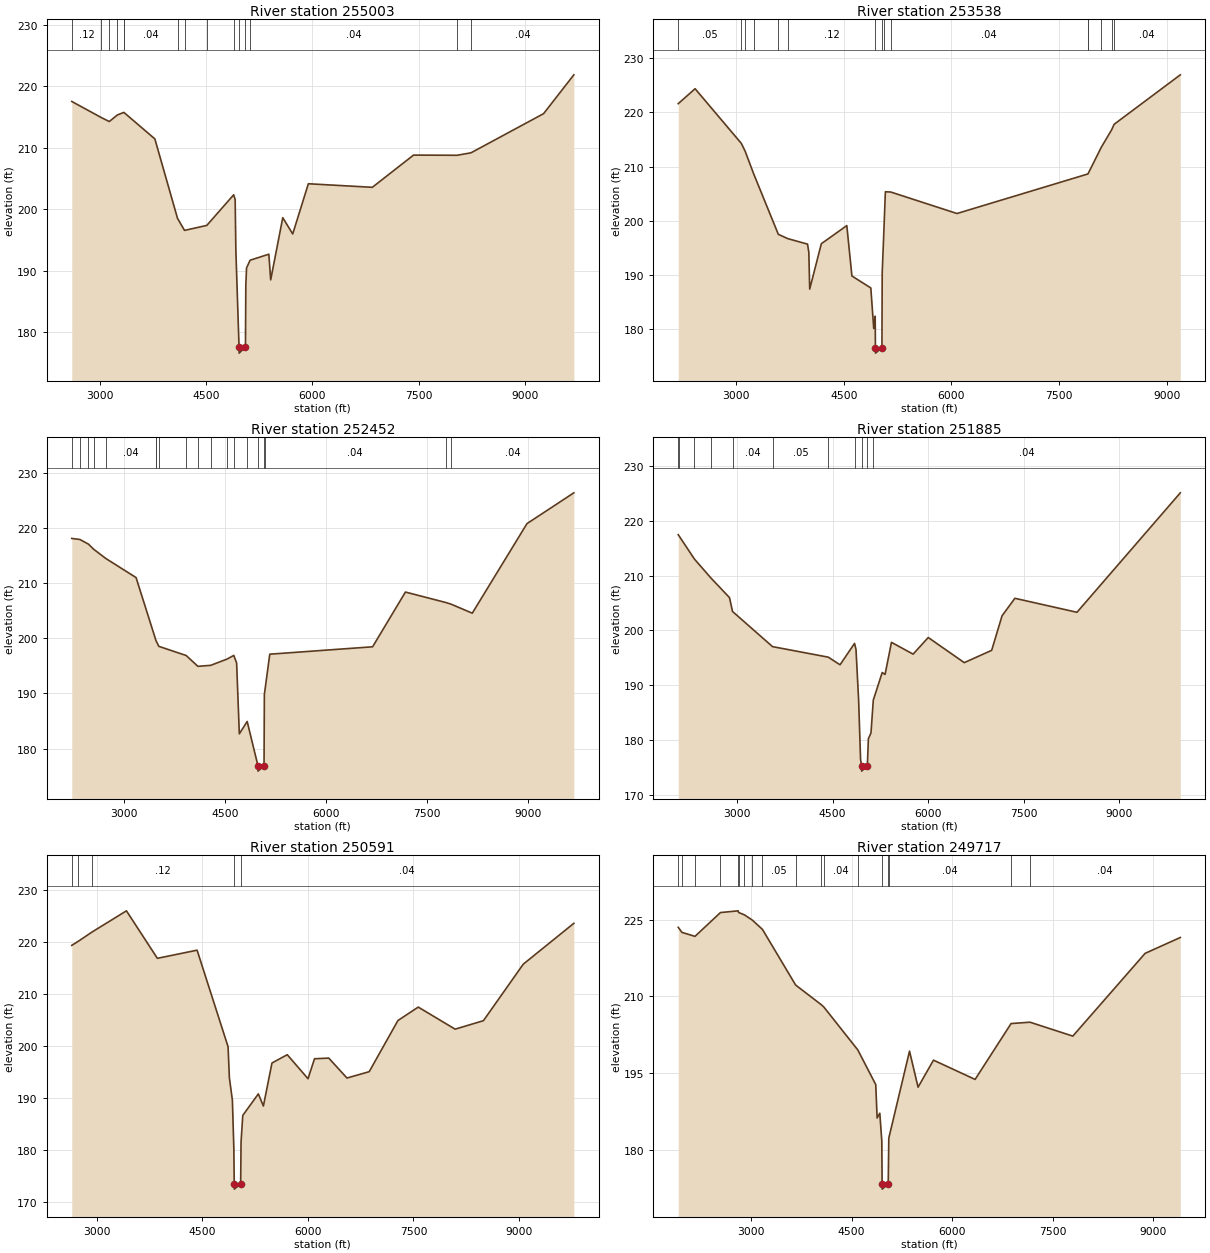
Type RM Length L Ch R = 1 ,255003  ,1465,1465,1465
BEGIN DESCRIPTION:
Mapping XS 52f63c07
END DESCRIPTION:
XS GIS Cut Line= 3
      2481975.99     13523843.98       2482540.2     13522954.27
      2482050.52       13516939.
#Sta/Elev= 30
  2604.1  217.56    3019  214.95  3133.7  214.29  3248.3  215.36  3339.3  215.78
  3344.8  215.73  3777.3  211.46  4096.9  198.52    4196  196.55  4510.4  197.36
    4890  202.35    4911  201.57  4921.1  193.24  4965.9  177.55  4967.4  176.55
  5056.2  177.55  5061.5  187.61  5071.6  190.42  5122.1  191.69  5386.6  192.67
  5412.7  188.49  5583.2  198.62  5723.7  195.97  5944.4  204.15  6847.4  203.57
  7429.3  208.82  8043.8  208.79  8240.2  209.19  9265.4  215.57  9692.8   221.9
#Mann= 15 ,-1 , 0
  2604.1     .12       0    3019     .04       0  3133.7     .05       0
  3248.3     .04       0  3339.3     .05       0  3344.8     .04       0
  4096.9     .12       0    4196     .05       0  4510.4     .04       0
    4890     .12       0  4965.9     .05       0  5056.2     .12       0
  5122.1     .04       0  8043.8     .03       0  8240.2     .04       0
Bank Sta=4965.9,5056.2
XS Rating Curve= 0 ,0
Exp/Cntr=0.3,0.1

Type RM Length L Ch R = 1 ,253538  ,1086,1086,1086
BEGIN DESCRIPTION:
Mapping XS 92ecb69e
END DESCRIPTION:
XS GIS Cut Line= 3
      2484048.45      13523692.1      2483592.72     13520946.89
      2482701.54     13516829.71
#Sta/Elev= 30
  2194.5  221.63  2429.5  224.39  3073.2  214.29  3125.7  212.88  3246.7  208.62
  3589.2  197.47  3720.1  196.68  3995.9  195.66    4014  194.16  4026.3  187.35
  4188.5  195.74  4543.3  199.09  4614.3  189.77  4877.8  187.56  4918.4  180.06
  4938.6  182.34    4942  176.51  4943.5  175.51  5032.4  176.51  5036.4  190.45
  5054.9  196.47  5080.5  205.35  5156.4  205.29  6078.2  201.32  7896.7  208.61
    7903  208.63  8090.3   213.6    8233  216.79  8267.5  217.81  9189.8  226.96
#Mann= 15 ,-1 , 0
  2194.5     .05       0  3073.2     .04       0  3125.7     .05       0
  3246.7     .04       0  3589.2     .05       0  3720.1     .12       0
    4942     .05       0  5032.4     .12       0  5054.9     .12       0
  5156.4     .04       0  7896.7     .05       0    7903     .03       0
  8090.3     .04       0    8233     .03       0  8267.5     .04       0
Bank Sta=4942,5032.4
XS Rating Curve= 0 ,0
Exp/Cntr=0.3,0.1

Type RM Length L Ch R = 1 ,252452  ,567,567,567
BEGIN DESCRIPTION:
Mapping XS ecffd5b9
END DESCRIPTION:
XS GIS Cut Line= 4
      2484363.12     13523681.26      2484677.79     13521283.26
      2484558.43     13519948.62      2482821.27     13516689.17
#Sta/Elev= 30
  2221.8  218.09  2341.9  217.91  2468.7  217.07  2546.6  216.14  2726.7  214.47
  3176.2     211    3468  199.73  3471.9  199.58  3514.2  198.54  3920.2  196.88
  4093.7  194.92  4283.9   195.1  4527.8  196.24  4626.8   196.9  4668.7  195.52
  4708.9  182.69  4825.3  184.93  4984.9  176.93  4986.4  175.93  5075.5  176.93
  5080.4   189.9  5082.9  190.04  5160.7  197.12    6687  198.46  7174.2  208.38
    7775  206.48  7848.7   206.2  8166.3  204.55  8978.2  220.78  9673.8  226.36
#Mann= 19 ,-1 , 0
  2221.8     .04       0  2341.9     .05       0  2468.7     .12       0
  2546.6     .05       0  2726.7     .04       0    3468     .12       0
  3471.9     .04       0  3514.2     .05       0  3920.2     .04       0
  4093.7     .05       0  4283.9     .04       0  4527.8     .05       0
  4626.8     .12       0  4825.3      .1       0  4984.9     .05       0
  5075.5      .1       0  5082.9     .04       0    7775     .03       0
  7848.7     .04       0
Bank Sta=4984.9,5075.5
XS Rating Curve= 0 ,0
Exp/Cntr=0.3,0.1

Type RM Length L Ch R = 1 ,251885  ,1294,1294,1294
BEGIN DESCRIPTION:
Mapping XS 271154d2
END DESCRIPTION:
XS GIS Cut Line= 4
      2484536.74     13523681.23      2485274.58     13521250.71
       2484894.8     13519427.79      2482864.22     13516601.53
#Sta/Elev= 30
  2076.5  217.45  2089.6  217.22  2330.6  213.01  2592.2  209.52    2881  205.98
  2928.8  203.45    3557  197.04    4432  195.12  4616.6  193.73  4844.6  197.63
  4867.5  196.49  4908.4  187.32    4939  176.46    4955  175.34  4956.5  174.34
  5045.6  175.34  5061.6  180.25  5102.5   181.3  5138.8  187.29  5278.8  192.32
  5323.8  191.97  5423.9  197.82    5764  195.67  6001.4   198.7  6567.3  194.12
    6997  196.36  7160.3  202.66  7361.7  205.85  8336.5   203.3  9958.7  225.08
#Mann= 11 ,-1 , 0
  2076.5     .04       0  2089.6     .12       0  2330.6     .05       0
  2592.2     .12       0  2928.8     .04       0    3557     .05       0
    4432     .04       0  4844.6      .1       0    4955     .05       0
  5045.6      .1       0  5138.8     .04       0
Bank Sta=4955,5045.6
XS Rating Curve= 0 ,0
Exp/Cntr=0.3,0.1

Type RM Length L Ch R = 1 ,250591  ,874,874,874
BEGIN DESCRIPTION:
Mapping XS 6899cb2e
END DESCRIPTION:
XS GIS Cut Line= 4
      2486934.74     13521999.42      2486609.21     13520274.14
      2485372.23     13520002.88      2483016.16     13516634.12
#Sta/Elev= 30
  2646.2  219.38  2737.9  220.16  2935.7  221.96  3422.9  226.02  3862.5  216.89
  4426.7  218.46  4866.9   199.9  4885.2  193.98  4928.3  189.62  4948.8  180.37
  4954.5  173.54    4956  172.54  5045.6  173.54  5051.2  181.63  5075.8  186.71
  5296.9  190.84  5368.6  188.51  5490.6  196.78  5707.7  198.37  6002.5  193.76
  6094.9  197.59  6297.2  197.72  6556.2  193.89  6871.9  195.11    7280  204.94
  7568.7  207.52  8092.7  203.28  8494.7  204.91  9060.7  215.77  9779.2  223.62
#Mann= 5 ,-1 , 0
  2646.2     .04       0  2737.9     .05       0  2935.7     .12       0
  4954.5     .05       0  5045.6     .04       0
Bank Sta=4954.5,5045.6
XS Rating Curve= 0 ,0
Exp/Cntr=0.3,0.1

Type RM Length L Ch R = 1 ,249717  ,1079,1079,1079
BEGIN DESCRIPTION:
Mapping XS a182971c
END DESCRIPTION:
XS GIS Cut Line= 5
      2487238.57     13521608.82      2486761.12      13520306.7
      2486524.75     13519284.96      2485170.59     13519358.74
      2483179.45     13516244.33
#Sta/Elev= 30
    1914  223.49  1969.4   222.5    2164  221.72  2543.4  226.37  2808.9  226.71
    2813   226.4  2900.6  225.93  3020.5  224.88  3170.7  223.07    3665  212.21
  4050.3  208.34  4086.4   207.9  4592.3  199.53  4860.1  192.75  4880.2  186.23
  4920.2  187.17  4950.3  181.75  4954.8  173.33  4956.3  172.33  5045.9  173.33
  5054.5   182.3  5363.6  199.29  5491.1  192.25  5720.8  197.53  6341.7  193.77
  6878.5  204.68  7159.8  204.95    7799  202.23  8877.4   218.4  9402.3   221.5
#Mann= 18 ,-1 , 0
    1914     .04       0  1969.4     .05       0    2164     .12       0
  2543.4     .05       0  2808.9     .12       0    2813     .05       0
  2900.6     .12       0  3020.5     .03       0  3170.7     .05       0
    3665     .03       0  4050.3     .12       0  4086.4     .04       0
  4592.3     .12       0  4954.8     .05       0  5045.9     .12       0
  5054.5     .04       0  6878.5     .03       0  7159.8     .04       0
Bank Sta=4954.8,5045.9
XS Rating Curve= 0 ,0
Exp/Cntr=0.3,0.1

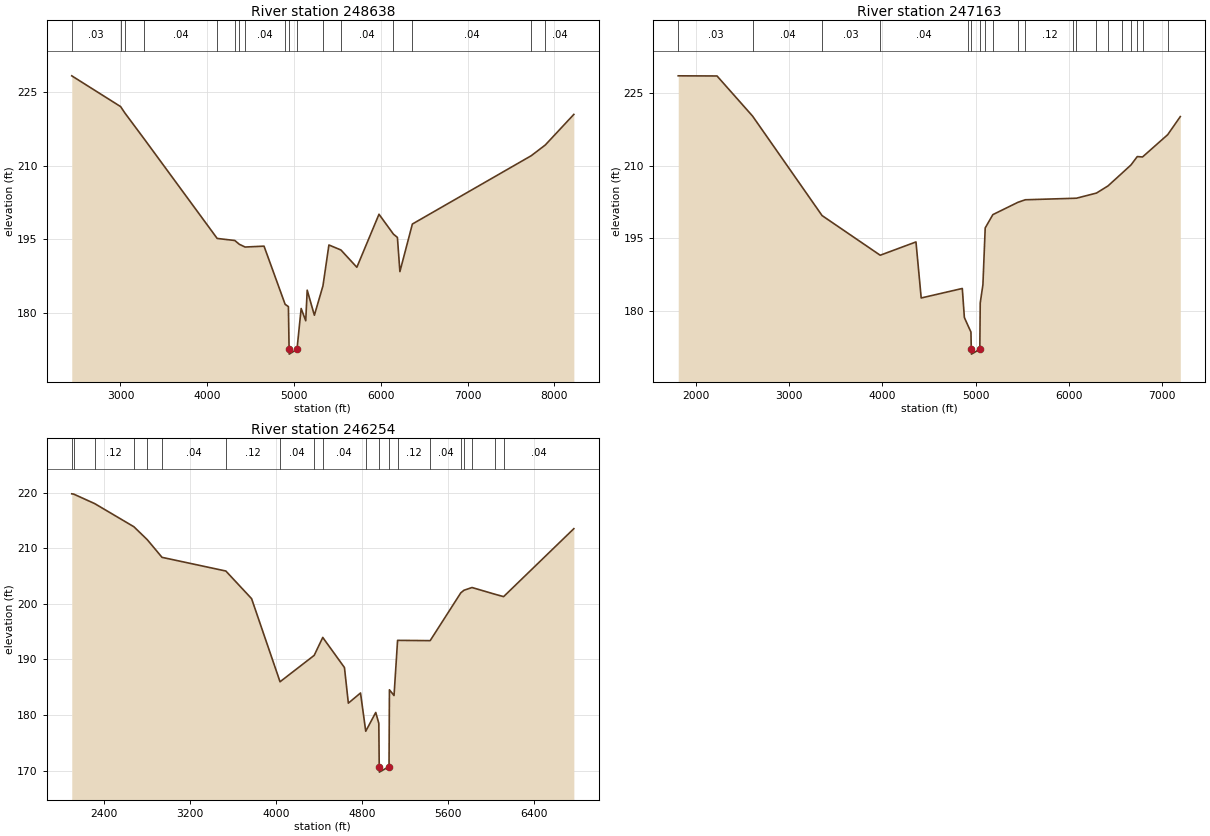
Type RM Length L Ch R = 1 ,248638  ,1475,1475,1475
BEGIN DESCRIPTION:
Mapping XS e34244ae
END DESCRIPTION:
XS GIS Cut Line= 4
      2487357.93     13520122.27       2486457.3     13518668.24
      2485166.07     13518114.86      2483395.93     13516113.28
#Sta/Elev= 30
  2438.5  228.29  3001.2  222.03  3052.6  220.68  3275.2   215.4  4114.6  195.19
  4317.7  194.77    4370     194  4436.4  193.44  4654.7  193.62  4897.8  181.78
  4935.7  181.31  4943.5  172.64    4945  171.64  5034.7  172.64  5082.6  180.93
  5135.2  178.43  5152.3  184.66  5234.9  179.56  5333.9  185.54  5402.5  193.86
    5541  192.84  5724.6  189.32  5979.7  200.11  6146.5  196.06  6192.2  195.39
  6220.7  188.44  6364.5  198.12  7734.8  212.03  7896.5  214.21  8225.7  220.44
#Mann= 17 ,-1 , 0
  2438.5     .03       0  3001.2     .04       0  3052.6     .03       0
  3275.2     .04       0  4114.6     .03       0  4317.7     .04       0
    4370     .03       0  4436.4     .04       0  4897.8      .1       0
  4943.5     .05       0  5034.7      .1       0  5333.9     .12       0
    5541     .04       0  6146.5     .12       0  6364.5     .04       0
  7734.8     .05       0  7896.5     .04       0
Bank Sta=4943.5,5034.7
XS Rating Curve= 0 ,0
Exp/Cntr=0.3,0.1

Type RM Length L Ch R = 1 ,247163  ,909,909,909
BEGIN DESCRIPTION:
Mapping XS e4662b30
END DESCRIPTION:
XS GIS Cut Line= 4
      2487477.25     13519937.73      2486674.32     13518321.02
      2485786.01     13517239.33      2484090.34     13515874.53
#Sta/Elev= 30
  1812.5  228.52  2228.3  228.49  2609.4  220.22  3354.4  199.72  3977.4  191.55
  4360.7  194.29  4416.7  182.74  4857.3   184.7  4879.5  178.71  4921.1  176.93
  4949.9  175.73  4953.7  172.17  4955.2  171.17    5045  172.17  5049.4  181.71
  5078.2  185.48  5102.8  197.18  5184.9  199.92  5455.1  202.47  5532.9  202.98
  6048.6  203.28  6080.7   203.3  6295.4  204.36  6418.8  205.83  6569.7  208.47
  6665.6  210.16  6732.7  211.88    6789   211.8  7058.7  216.39    7194  220.12
#Mann= 20 ,-1 , 0
  1812.5     .03       0  2609.4     .04       0  3354.4     .03       0
  3977.4     .04       0  4921.1     .12       0  4953.7     .05       0
    5045     .12       0  5102.8      .1       0  5184.9     .12       0
  5455.1     .05       0  5532.9     .12       0  6048.6     .04       0
  6080.7     .12       0  6295.4     .05       0  6418.8     .12       0
  6569.7     .12       0  6665.6     .05       0  6732.7     .04       0
    6789     .05       0  7058.7     .04       0
Bank Sta=4953.7,5045
XS Rating Curve= 0 ,0
Exp/Cntr=0.3,0.1

Type RM Length L Ch R = 1 ,246254  ,982,982,982
BEGIN DESCRIPTION:
Mapping XS c6d85279
END DESCRIPTION:
XS GIS Cut Line= 4
      2488030.64     13519395.21      2487347.06     13517854.44
      2486164.33      13516454.7      2485090.11     13516031.52
#Sta/Elev= 30
    2098   219.8  2117.1  219.74  2311.3  218.04  2675.9  213.88  2800.6  211.55
    2938  208.37  3531.9  205.91  3771.5  200.94  4036.4  185.98  4354.1  190.73
  4433.9  193.96  4635.8  188.54  4672.1  182.13  4785.3  183.96    4834  177.08
    4927  180.46  4955.6   178.5  4959.4  170.72  4960.9  169.72  5050.7  170.72
  5054.4  184.54  5097.3   183.5  5130.2  193.43  5433.5  193.38  5718.5  201.98
  5748.5  202.45    5823  202.94  6038.4  201.72    6117   201.3  6770.7  213.53
#Mann= 20 ,-1 , 0
    2098     .12       0  2117.1     .05       0  2311.3     .12       0
  2675.9     .04       0  2800.6     .05       0    2938     .04       0
  3531.9     .12       0  4036.4     .04       0  4354.1     .12       0
  4433.9     .04       0    4834      .1       0  4959.4     .05       0
  5050.7      .1       0  5130.2     .12       0  5433.5     .04       0
  5718.5     .12       0  5748.5     .05       0    5823     .12       0
  6038.4     .05       0    6117     .04       0
Bank Sta=4959.4,5050.7
XS Rating Curve= 0 ,0
Exp/Cntr=0.3,0.1