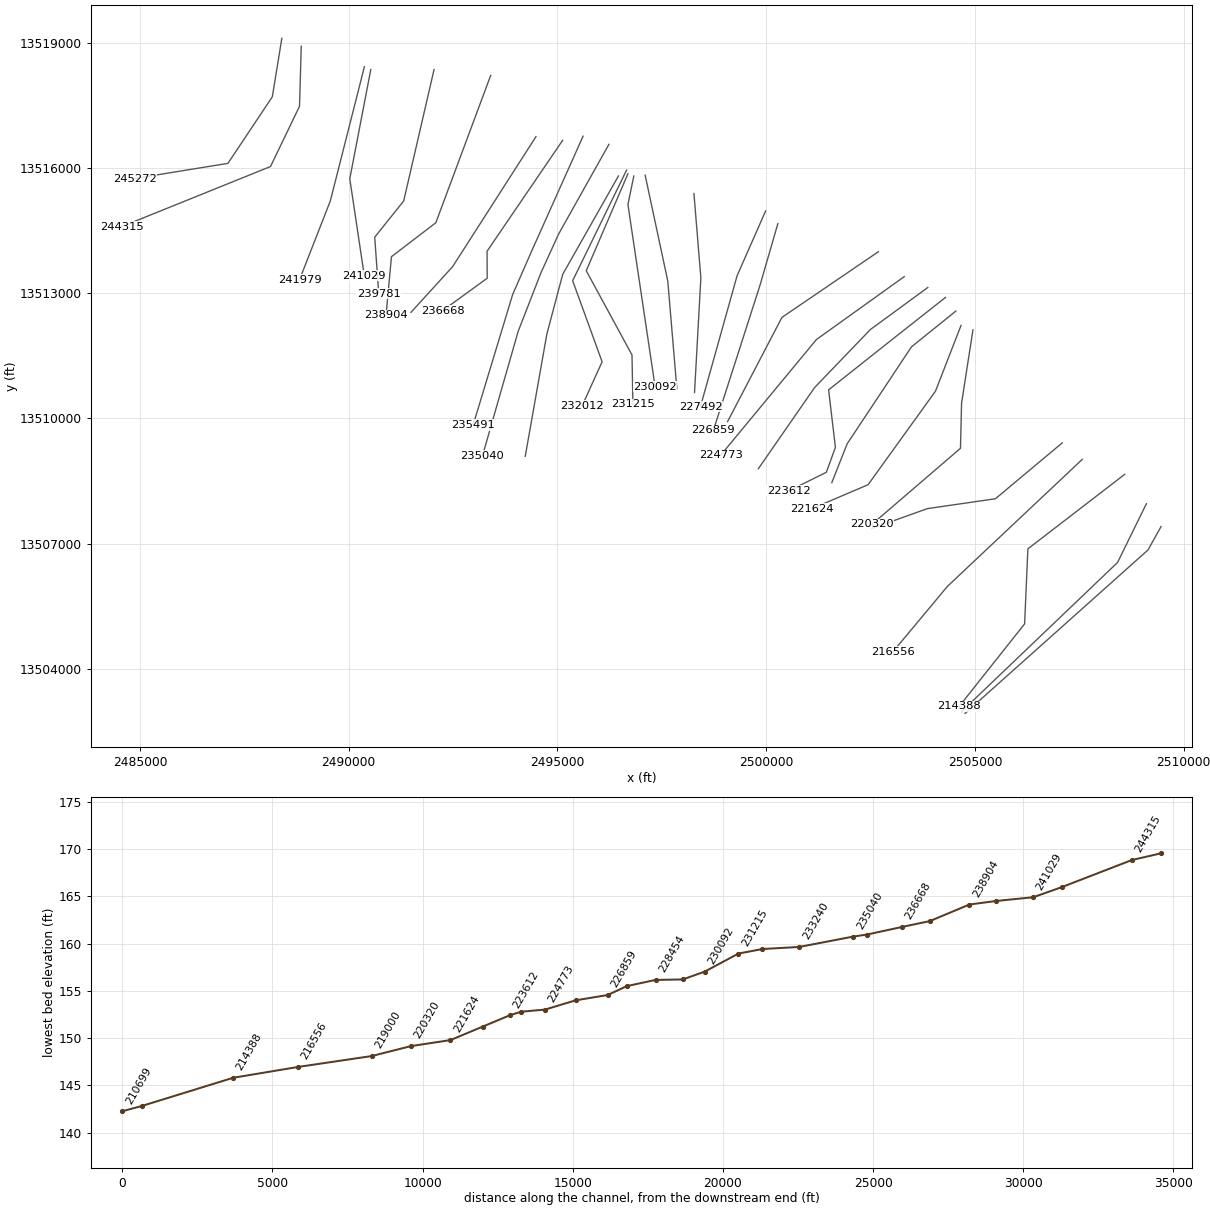
HEC-RAS study COLETO CREEK.prj: COLETO CREEK Base Level Engineering

--- COLETO CREEK.g01 (geometry) --- (continued)

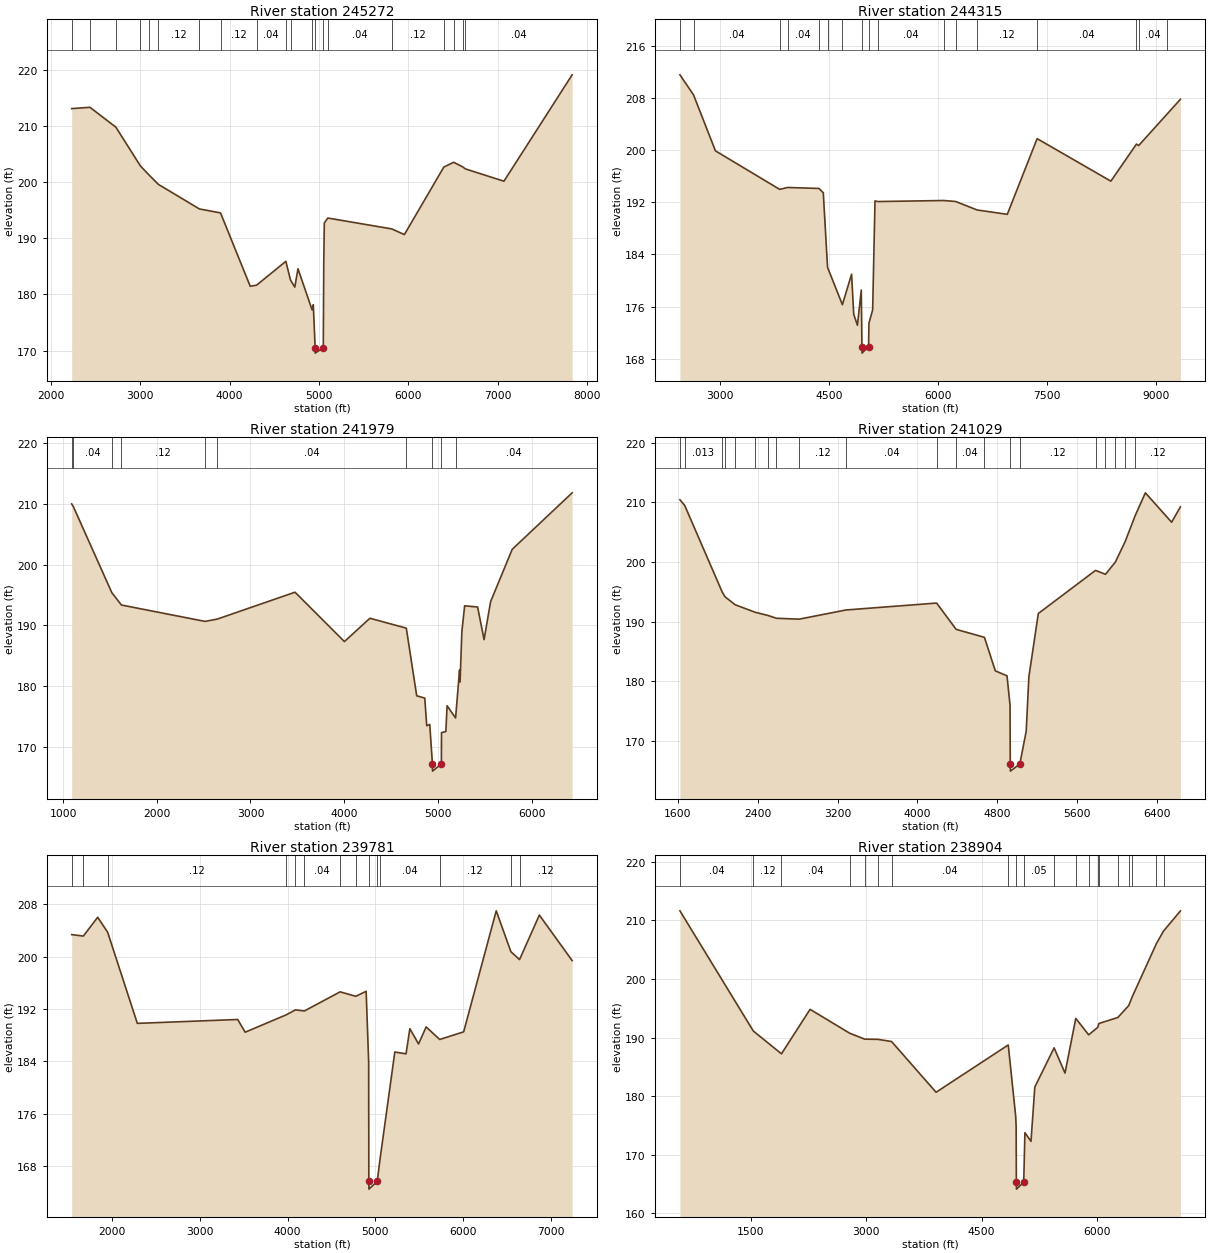
Type RM Length L Ch R = 1 ,245272  ,957,957,957
BEGIN DESCRIPTION:
Mapping XS bb044904
END DESCRIPTION:
XS GIS Cut Line= 4
      2488399.57     13519102.25      2488171.71     13517702.53
      2487108.34     13516107.48      2484871.59     13515744.34
#Sta/Elev= 30
  2233.1  213.06  2437.4  213.29    2728  209.75  3002.7  202.85  3102.9  201.18
  3203.2  199.58    3662  195.21    3899   194.5  4231.2  181.45  4302.3  181.64
  4629.9  185.88  4682.1  182.56  4729.9   181.3    4766  184.56  4923.6  177.25
  4937.3  178.16  4957.7  170.55  4959.2  169.55    5049  170.55  5054.4  185.65
  5060.5  192.71  5099.3  193.59  5816.1  191.65  5956.6  190.64  6398.2  202.66
  6508.3  203.51  6607.4  202.71  6639.8  202.33    7071  200.14  7834.3  219.07
#Mann= 20 ,-1 , 0
  2233.1     .05       0  2437.4     .12       0    2728     .05       0
  3002.7     .12       0  3102.9    .013       0  3203.2     .12       0
    3662     .04       0    3899     .12       0  4302.3     .04       0
  4629.9     .03       0  4682.1     .12       0  4923.6      .1       0
  4957.7     .05       0    5049      .1       0  5099.3     .04       0
  5816.1     .12       0  6398.2     .05       0  6508.3     .04       0
  6607.4     .05       0  6639.8     .04       0
Bank Sta=4957.7,5049
XS Rating Curve= 0 ,0
Exp/Cntr=0.3,0.1

Type RM Length L Ch R = 1 ,244315  ,2336,2336,2336
BEGIN DESCRIPTION:
Mapping XS 0ea9785d
END DESCRIPTION:
XS GIS Cut Line= 4
      2488864.67     13518912.77      2488822.75     13517474.66
      2488128.31     13516031.52      2484568.86      13514594.6
#Sta/Elev= 30
  2452.4  211.54  2639.1  208.47  2940.4  199.88  3823.4  193.97  3932.2  194.26
  4363.6  194.11  4422.9  193.45  4481.2  182.02  4685.4  176.28  4811.8  180.96
  4841.3  174.81  4892.1  173.13    4945  178.53  4954.1  169.85  4955.6  168.85
  5045.4  169.85  5050.5  173.45  5101.3  175.48  5133.7   192.2  5171.7   192.1
  6078.4  192.26  6241.8  192.11    6537  190.81  6952.1  190.14    7362  201.75
  8375.6  195.23  8727.6  200.92  8757.6  200.69  9144.2  205.47  9331.2  207.79
#Mann= 17 ,-1 , 0
  2452.4    .013       0  2639.1     .04       0  3823.4    .013       0
  3932.2     .04       0  4363.6     .03       0  4481.2     .04       0
  4685.4      .1       0  4954.1     .05       0  5045.4      .1       0
  5171.7     .04       0  6078.4     .12       0  6241.8     .04       0
    6537     .12       0    7362     .04       0  8727.6     .03       0
  8757.6     .04       0  9144.2    .013       0
Bank Sta=4954.1,5045.4
XS Rating Curve= 0 ,0
Exp/Cntr=0.3,0.1

Type RM Length L Ch R = 1 ,241979  ,950,950,950
BEGIN DESCRIPTION:
Mapping XS 06a96dbc
END DESCRIPTION:
XS GIS Cut Line= 3
      2490376.86     13518420.66       2489560.6     13515206.87
      2488822.97     13513319.41
#Sta/Elev= 30
  1091.4  209.99  1110.3  209.51  1520.1  195.37  1622.5  193.34  2515.1  190.64
  2647.1  191.03  3475.4  195.45  4002.5  187.32    4275  191.16  4663.4  189.53
  4774.3  178.39  4860.2  178.01  4881.6  173.46  4913.8  173.67  4942.2  167.18
  4943.7  165.98  5037.9  167.18    5039  172.32  5085.6  172.51  5098.7  176.75
  5189.5  174.73  5231.8  182.63  5237.2  180.66  5256.3  188.91  5286.1  193.21
  5424.6  193.01  5493.6  187.64  5563.1  193.89  5794.2  202.52  6433.7  211.82
#Mann= 10 ,-1 , 0
  1091.4     .12       0  1110.3     .04       0  1520.1     .05       0
  1622.5     .12       0  2515.1    .013       0  2647.1     .04       0
  4663.4     .12       0  4942.2     .05       0  5037.9     .12       0
  5189.5     .04       0
Bank Sta=4942.2,5037.9
XS Rating Curve= 0 ,0
Exp/Cntr=0.3,0.1

Type RM Length L Ch R = 1 ,241029  ,1248,1248,1248
BEGIN DESCRIPTION:
Mapping XS 5af1fb17
END DESCRIPTION:
XS GIS Cut Line= 3
      2490530.35      13518355.1      2490027.18     13515738.55
      2490374.14     13513418.24
#Sta/Elev= 30
  1622.4  210.43  1670.3  209.47  2045.7  194.95  2074.1  194.15  2175.1  192.82
  2376.9  191.55  2499.5  191.04  2588.9  190.55  2815.9   190.4  3285.4  191.94
  4192.2   193.1  4387.9  188.69  4671.1  187.35  4780.1  181.73  4897.1  180.89
  4927.5  175.96  4929.7  166.11  4931.2  164.91  5025.5  166.11  5089.3   171.6
    5116  180.72  5210.6  191.35  5783.7  198.58    5883  197.92  5982.2  199.98
  6081.5  203.47  6180.7  207.78  6282.4  211.59  6545.3  206.66    6633  209.23
#Mann= 20 ,-1 , 0
  1622.4     .04       0  1670.3    .013       0  2045.7     .04       0
  2074.1     .05       0  2175.1     .12       0  2376.9    .013       0
  2499.5     .12       0  2588.9    .013       0  2815.9     .12       0
  3285.4     .04       0  4192.2     .12       0  4387.9     .04       0
  4671.1      .1       0  4929.7     .05       0  5025.5     .12       0
  5783.7     .05       0    5883     .05       0  5982.2     .12       0
  6081.5     .05       0  6180.7     .12       0
Bank Sta=4929.7,5025.5
XS Rating Curve= 0 ,0
Exp/Cntr=0.3,0.1

Type RM Length L Ch R = 1 ,239781  ,877,877,877
BEGIN DESCRIPTION:
Mapping XS b1ebd116
END DESCRIPTION:
XS GIS Cut Line= 4
      2492045.41     13518353.59      2491318.41     13515206.87
      2490623.97     13514338.81      2490721.62     13512982.49
#Sta/Elev= 30
  1540.9  203.34  1673.8  203.12  1837.1  205.99  1950.7   203.7  2288.7   189.8
  3431.9  190.39  3517.4  188.45  3987.7  191.12  4089.6  191.86  4191.4  191.69
  4598.8  194.61  4776.8  193.93  4895.3  194.69  4924.1  183.89  4925.8  165.71
  4927.3  164.51  5021.6  165.71  5053.8  169.11  5221.9  185.43  5349.9  185.15
  5393.1  188.99  5492.4  186.66  5578.8  189.26  5733.3  187.34  6006.3  188.51
  6377.3  206.97    6544  200.74  6642.7  199.53  6868.5  206.32    7242  199.38
#Mann= 14 ,-1 , 0
  1540.9    .013       0  1673.8     .04       0  1950.7     .12       0
  3987.7     .04       0  4089.6    .013       0  4191.4     .04       0
  4598.8     .05       0  4776.8     .12       0  4925.8     .05       0
  5021.6     .05       0  5053.8     .04       0  5733.3     .12       0
    6544     .04       0  6642.7     .12       0
Bank Sta=4925.8,5021.6
XS Rating Curve= 0 ,0
Exp/Cntr=0.3,0.1

Type RM Length L Ch R = 1 ,238904  ,1314,1314,1314
BEGIN DESCRIPTION:
Mapping XS e413a5d1
END DESCRIPTION:
XS GIS Cut Line= 4
      2493401.75     13518212.53      2492088.81     13514686.04
      2491025.45     13513872.23      2490895.24     13512472.49
#Sta/Elev= 30
   576.8  211.63  1531.1  191.12  1897.3  187.23  2269.1  194.82  2786.4  190.73
  2980.9  189.73  3149.8   189.7  3328.8  189.33  3907.6  180.67  4846.1  188.74
  4942.4  176.64    4949   174.8  4951.5  165.34    4953  164.14  5047.3  165.34
  5062.9  173.77  5141.8  172.29  5191.7  181.56  5442.4  188.25  5584.3  183.94
  5724.2  193.27    5892  190.47  6009.5  191.74  6024.6   192.4    6271  193.43
  6411.7  195.44  6459.3  196.99  6773.7  206.06    6865  208.17  7084.6  211.61
#Mann= 20 ,-1 , 0
   576.8     .04       0  1531.1     .12       0  1897.3     .04       0
  2786.4     .03       0  2980.9     .04       0  3149.8     .12       0
  3328.8     .04       0  4846.1     .05       0  4951.5     .04       0
  5047.3     .05       0  5442.4     .03       0  5724.2     .04       0
    5892     .12       0  6009.5     .04       0  6024.6     .12       0
    6271     .05       0  6411.7     .12       0  6459.3     .04       0
  6773.7     .12       0    6865     .04       0
Bank Sta=4951.5,5047.3
XS Rating Curve= 0 ,0
Exp/Cntr=0.3,0.1

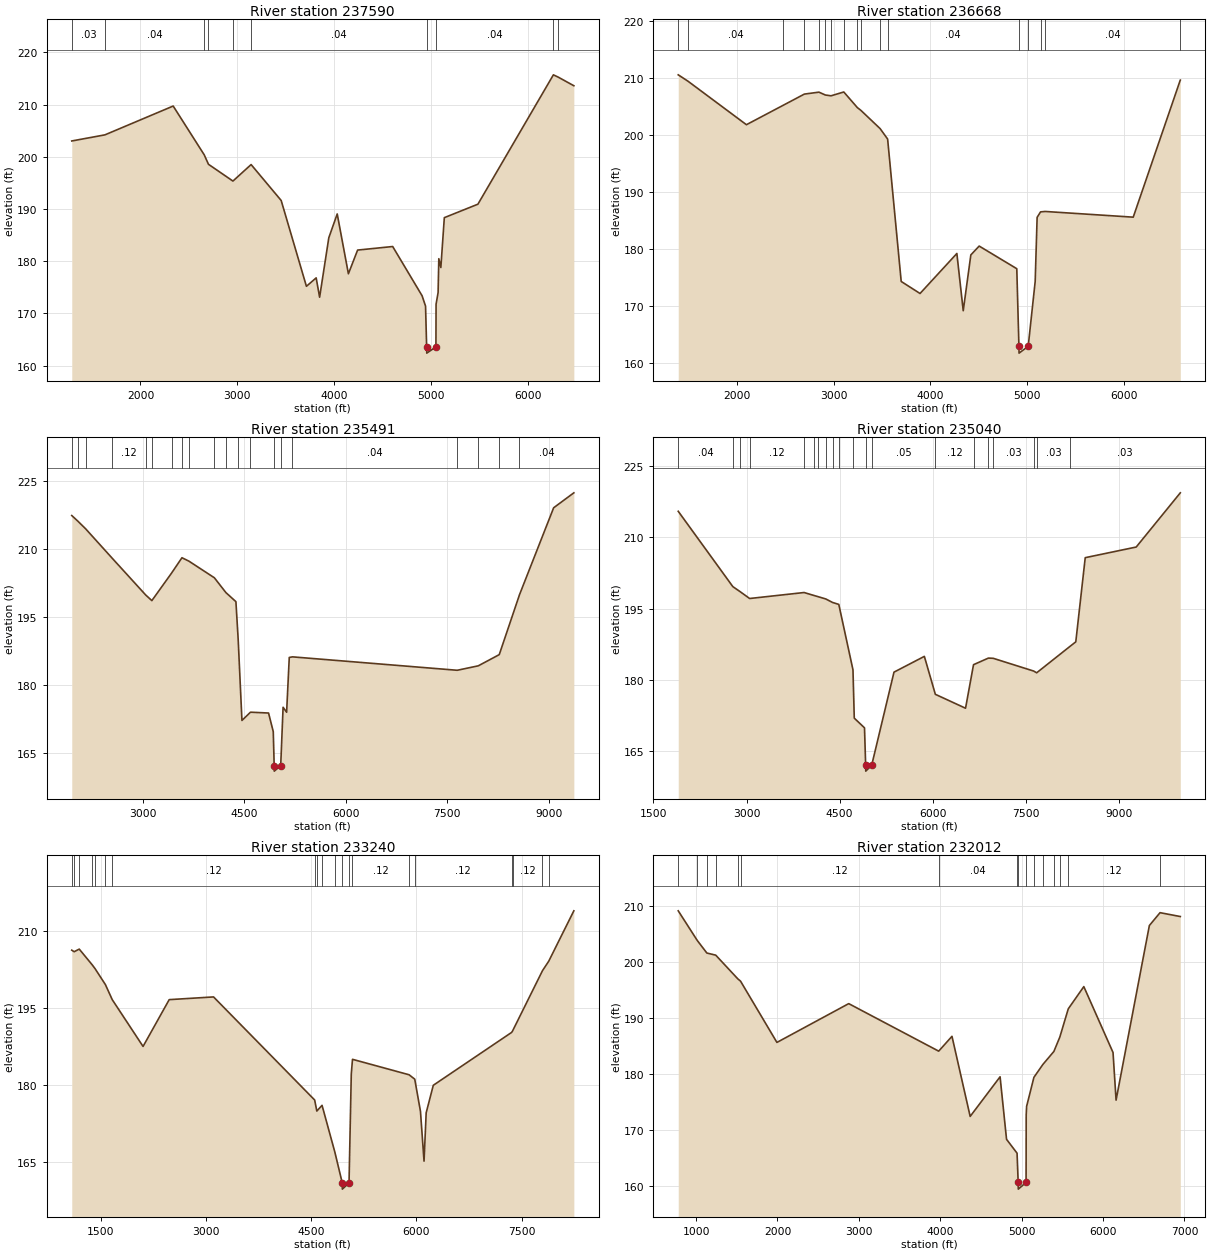
Type RM Length L Ch R = 1 ,237590  ,922,922,922
BEGIN DESCRIPTION:
Mapping XS 8f941a69
END DESCRIPTION:
XS GIS Cut Line= 3
      2494486.82     13516747.68      2492490.29     13513633.52
      2491493.12      13512538.8
#Sta/Elev= 30
    1291  203.03  1633.2   204.2  2337.4  209.72  2657.7  200.37  2701.5  198.56
  2953.8  195.35  3141.3  198.51  3451.5  191.63  3711.9  175.19  3812.5   176.8
  3848.1   173.1  3943.1   184.5  4029.7  189.05  4145.1  177.59  4240.1  182.13
    4602  182.81  4905.3  173.38    4941   171.4  4952.3  163.59  4953.8  162.39
  5048.1  163.59  5049.6  171.75  5070.5  173.99  5077.9  180.48  5098.9  178.79
  5134.7  188.34  5481.3  190.92    6260   215.7  6311.7  215.24    6471  213.61
#Mann= 10 ,-1 , 0
    1291     .03       0  1633.2     .04       0  2657.7     .05       0
  2701.5     .04       0  2953.8     .05       0  3141.3     .04       0
  4952.3     .04       0  5048.1     .04       0    6260     .03       0
  6311.7     .04       0
Bank Sta=4952.3,5048.1
XS Rating Curve= 0 ,0
Exp/Cntr=0.3,0.1

Type RM Length L Ch R = 1 ,236668  ,1177,1177,1177
BEGIN DESCRIPTION:
Mapping XS cd4d5c19
END DESCRIPTION:
XS GIS Cut Line= 4
      2495127.01     13516660.86      2493314.94     13514002.44
      2493318.86     13513356.09      2492251.55     13512580.98
#Sta/Elev= 30
  1397.2  210.59    1498  209.47  2101.1  201.84  2478.9  205.23  2699.3  207.21
  2849.5  207.55  2915.8  207.05  2974.7  206.91  3106.2  207.58  3246.7  204.83
  3281.1  204.38  3481.4  201.15  3558.7  199.32  3698.8  174.34  3893.3  172.23
  4273.4  179.25  4339.1  169.21  4417.7     179  4503.7  180.55  4891.9  176.58
    4914  162.97  4915.5  161.77  5009.8  162.97  5081.9  174.35  5101.9  185.59
  5137.5  186.55  5185.4  186.62  6093.9  185.62  6578.9  209.63  6579.9  209.66
#Mann= 17 ,-1 , 0
  1397.2     .03       0    1498     .04       0  2478.9    .013       0
  2699.3     .04       0  2849.5     .03       0  2915.8     .04       0
  2974.7     .03       0  3106.2     .04       0  3246.7     .03       0
  3281.1     .04       0  3481.4     .05       0  3558.7     .04       0
    4914     .04       0  5009.8     .04       0  5137.5     .12       0
  5185.4     .04       0  6578.9     .03       0
Bank Sta=4914,5009.8
XS Rating Curve= 0 ,0
Exp/Cntr=0.3,0.1

Type RM Length L Ch R = 1 ,235491  ,451,451,451
BEGIN DESCRIPTION:
Mapping XS 1b2bb353
END DESCRIPTION:
XS GIS Cut Line= 4
       2495615.3     13516758.55      2494367.46     13513969.89
      2493928.36     13512966.24      2492981.44     13509839.39
#Sta/Elev= 30
  1950.6  217.35  2039.9  216.12  2155.6  214.42    2548  207.93  3044.2   199.8
  3133.9  198.58    3425  204.65  3578.6  208.04  3680.9  207.29  4057.2  203.62
  4227.9  200.35  4375.7  198.35  4409.1  190.04  4464.8  172.14  4590.9  173.96
  4857.9  173.78  4927.5  169.67    4941  162.16  4942.5  160.96  5037.4  162.16
  5072.7  175.05  5124.9  173.95  5163.9  186.04  5211.6  186.17  7645.2  183.21
  7956.1  184.19  8266.2  186.66    8565  199.86  9069.9  219.06  9368.3  222.36
#Mann= 20 ,-1 , 0
  1950.6     .04       0  2039.9    .013       0  2155.6     .04       0
    2548     .12       0  3044.2    .013       0  3133.9     .05       0
    3425     .12       0  3578.6     .05       0  3680.9     .12       0
  4057.2    .013       0  4227.9     .05       0  4409.1     .12       0
  4590.9      .1       0    4941     .05       0  5037.4     .12       0
  5211.6     .04       0  7645.2     .05       0  7956.1     .04       0
  8266.2     .05       0    8565     .04       0
Bank Sta=4941,5037.4
XS Rating Curve= 0 ,0
Exp/Cntr=0.3,0.1

Type RM Length L Ch R = 1 ,235040  ,1800,1800,1800
BEGIN DESCRIPTION:
Mapping XS 1351f9c0
END DESCRIPTION:
XS GIS Cut Line= 5
      2496233.77     13516563.18      2495029.35     13514414.77
      2494606.69     13513487.97      2494059.34     13512080.38
      2493205.43     13509102.36
#Sta/Elev= 30
    1900  215.48  2779.4  199.62  2894.3  198.58  3050.7  197.11  3927.9  198.37
  4086.8  197.75  4157.6  197.48  4278.2  197.01  4386.2  196.28  4487.2  195.87
  4715.6  182.09  4736.4  171.91  4901.3  169.87  4920.1  161.95  4921.6  160.75
  5016.5  161.95  5376.5   181.6  5865.7  184.92  6042.8  176.93  6529.4     174
  6657.9  183.17    6898  184.56  6975.9  184.51  7626.9  181.83  7675.3  181.46
  8216.8  187.07  8305.8  187.98  8457.9  205.71  9279.3  207.95  9989.9  219.37
#Mann= 20 ,-1 , 0
    1900     .04       0  2779.4    .013       0  2894.3     .05       0
  3050.7     .12       0  3927.9     .12       0  4086.8    .013       0
  4157.6     .12       0  4278.2    .013       0  4386.2     .12       0
  4487.2    .013       0  4715.6    .013       0  4920.1     .03       0
  5016.5     .05       0  6042.8     .12       0  6657.9     .03       0
    6898    .013       0  6975.9     .03       0  7626.9    .013       0
  7675.3     .03       0  8216.8     .03       0
Bank Sta=4920.1,5016.5
XS Rating Curve= 0 ,0
Exp/Cntr=0.3,0.1

Type RM Length L Ch R = 1 ,233240  ,1228,1228,1228
BEGIN DESCRIPTION:
Mapping XS da7a0a0d
END DESCRIPTION:
XS GIS Cut Line= 4
      2496461.63     13515803.64      2495127.01     13513449.06
      2494747.23     13512016.77      2494230.13     13509091.74
#Sta/Elev= 30
  1086.4  206.22  1120.9  205.92    1193  206.43  1375.8   203.4  1418.9  202.61
  1565.7  199.52  1663.9  196.57  2102.9  187.46  2475.7  196.58  3107.9  197.11
  4549.6  177.02  4580.5  174.87    4655  175.98  4837.6  166.86  4943.2  160.85
  4944.7  159.65  5039.6  160.85  5071.8  182.06    5089  184.95  5895.8  181.94
  5976.6  181.08  6058.2  174.81  6109.2   165.1  6139.7  174.53  6241.2  179.89
  7357.7  190.19  7370.5  190.45  7797.9  202.22  7887.9  204.09  8245.1  213.89
#Mann= 20 ,-1 , 0
  1086.4     .04       0  1120.9     .12       0    1193     .04       0
  1375.8     .05       0  1418.9     .12       0  1565.7     .05       0
  1663.9     .12       0  4549.6     .04       0  4580.5     .12       0
    4655     .04       0  4837.6      .1       0  4943.2     .05       0
  5039.6      .1       0    5089     .12       0  5895.8      .1       0
  5976.6     .12       0  7357.7     .05       0  7370.5     .12       0
  7797.9     .05       0  7887.9     .12       0
Bank Sta=4943.2,5039.6
XS Rating Curve= 0 ,0
Exp/Cntr=0.3,0.1

Type RM Length L Ch R = 1 ,232012  ,797,797,797
BEGIN DESCRIPTION:
Mapping XS 9b3a3461
END DESCRIPTION:
XS GIS Cut Line= 4
      2496656.96     13515944.74      2495365.72     13513297.15
      2496071.02     13511354.87      2495593.58     13510302.34
#Sta/Elev= 30
     781  209.15  1015.1  203.85  1132.7  201.61  1241.8  201.23    1512  197.01
  1546.7  196.58  1993.4  185.64  2875.4  192.57  3980.7  184.08  4143.9  186.73
  4367.3  172.42  4734.8   179.5  4814.1  168.33  4943.4  165.85  4957.1  160.63
  4958.6  159.43  5054.1  160.63  5055.6  172.67  5060.9  174.23  5150.6  179.41
    5261  181.71  5395.9  184.03  5468.6  186.59  5572.5  191.64  5763.5  195.61
  6122.3  183.84  6159.7  175.33  6568.6  206.52  6699.8  208.82  6948.8  208.13
#Mann= 16 ,-1 , 0
     781     .04       0  1015.1     .12       0  1132.7     .04       0
  1241.8     .12       0    1512     .05       0  1546.7     .12       0
  3980.7     .04       0  4943.4      .1       0  4957.1     .05       0
  5054.1      .1       0  5150.6     .12       0    5261     .05       0
  5395.9     .12       0  5468.6     .05       0  5572.5     .12       0
  6699.8     .05       0
Bank Sta=4957.1,5054.1
XS Rating Curve= 0 ,0
Exp/Cntr=0.3,0.1

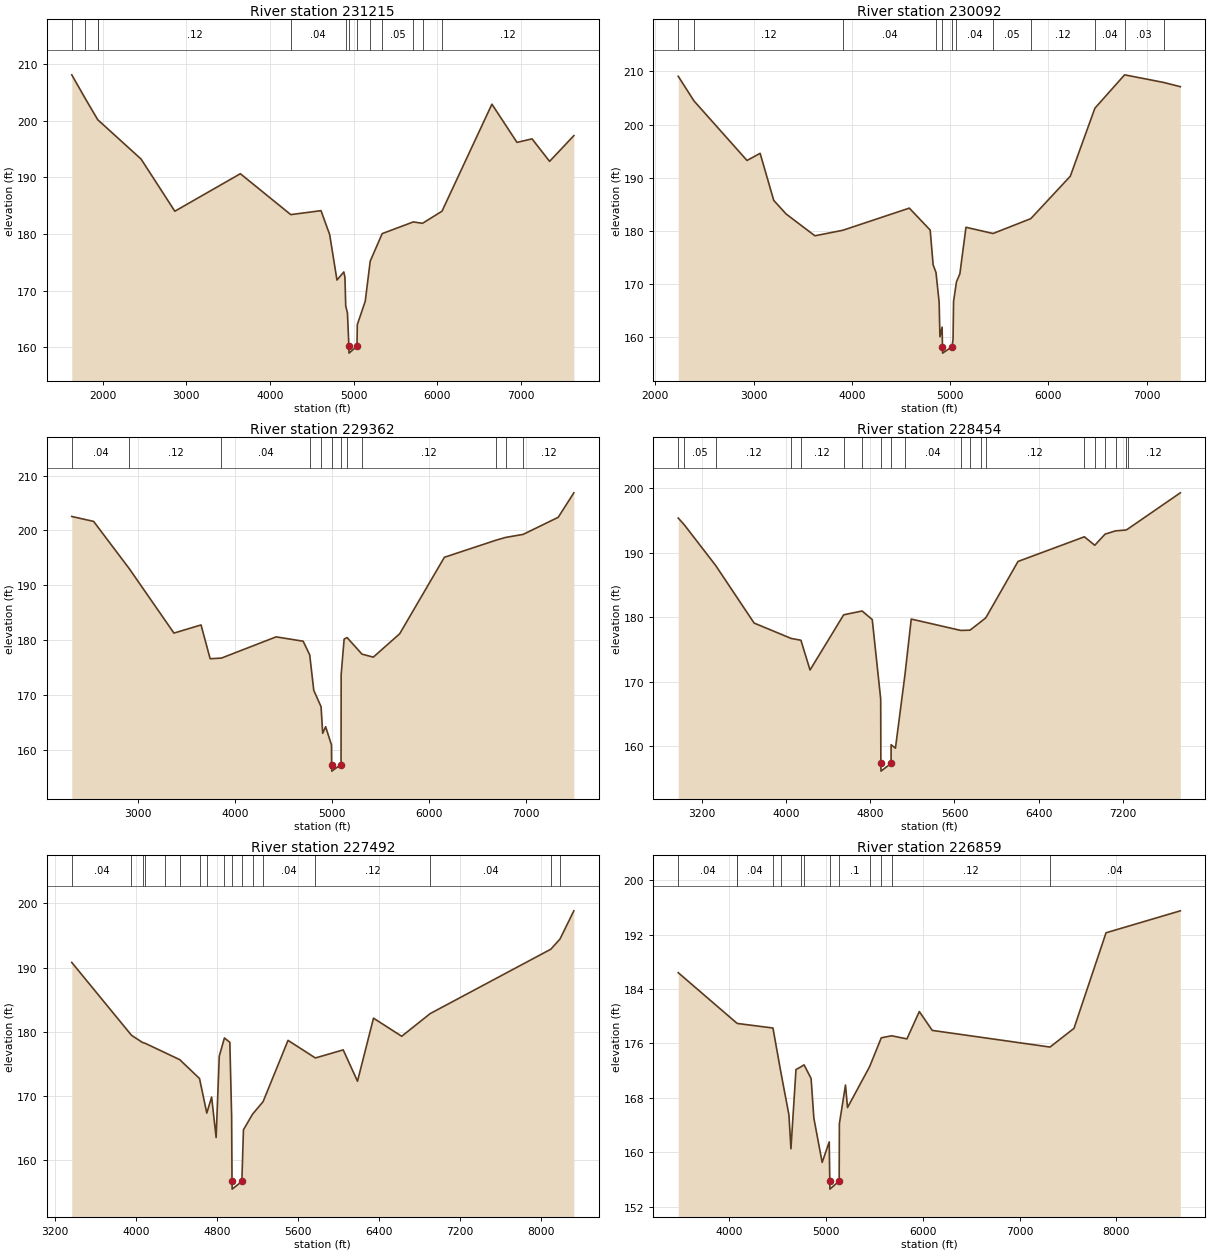
Type RM Length L Ch R = 1 ,231215  ,1123,1123,1123
BEGIN DESCRIPTION:
Mapping XS 421e9b78
END DESCRIPTION:
XS GIS Cut Line= 4
       2496689.5      13515857.9      2495691.24     13513535.86
      2496787.16     13511517.63      2496808.86     13510334.94
#Sta/Elev= 30
  1628.5  208.06  1790.8  203.86  1939.2  200.14  1942.8  200.09  2458.1  193.19
  2861.7  183.99  3645.4  190.61  4248.9  183.39  4610.5  184.09  4714.1  179.87
  4801.5  171.85  4883.2  173.27  4896.7  172.37  4906.2  167.28  4926.9  166.03
    4944  160.15  4945.5  158.95    5041  160.15  5044.6  163.97  5139.8  168.11
  5199.1  175.17  5342.5  180.04  5714.6   182.1  5825.1  181.86  6057.8  183.99
  6655.3  202.88  6955.3  196.14  7135.4  196.76  7345.4  192.79  7635.5  197.33
#Mann= 13 ,-1 , 0
  1628.5     .04       0  1790.8     .12       0  1939.2     .04       0
  1942.8     .12       0  4248.9     .04       0  4906.2      .1       0
    4944     .05       0    5041      .1       0  5199.1     .12       0
  5342.5     .05       0  5714.6     .12       0  5825.1      .1       0
  6057.8     .12       0
Bank Sta=4944,5041
XS Rating Curve= 0 ,0
Exp/Cntr=0.3,0.1

Type RM Length L Ch R = 1 ,230092  ,730,730,730
BEGIN DESCRIPTION:
Mapping XS d78e61c0
END DESCRIPTION:
XS GIS Cut Line= 3
      2496830.57     13515803.66      2496689.51     13515120.06
      2497340.55     13510758.08
#Sta/Elev= 30
  2233.7  209.09  2393.8  204.46  2933.4  193.26  3066.9   194.6  3205.4  185.76
  3331.1   183.2  3624.4   179.1    3909  180.14  4584.9   184.3  4797.2  180.17
  4827.1  173.64  4856.3   172.2  4888.2  166.61  4896.4  160.11  4918.5  161.93
  4922.2  158.24  4923.7  157.04  5019.2  158.24  5029.7  159.61  5034.9  166.75
  5064.6  170.45  5099.1  171.94  5161.2   180.7  5436.7  179.53  5820.6  182.32
  6222.8   190.3  6472.8  203.08  6775.2  209.36  7172.1  207.93    7342  207.13
#Mann= 12 ,-1 , 0
  2233.7     .04       0  2393.8     .12       0    3909     .04       0
  4856.3      .1       0  4922.2     .05       0  5019.2      .1       0
  5064.6     .04       0  5436.7     .05       0  5820.6     .12       0
  6472.8     .04       0  6775.2     .03       0  7172.1     .04       0
Bank Sta=4922.2,5019.2
XS Rating Curve= 0 ,0
Exp/Cntr=0.3,0.1

Type RM Length L Ch R = 1 ,229362  ,908,908,908
BEGIN DESCRIPTION:
Mapping XS c0aab9db
END DESCRIPTION:
XS GIS Cut Line= 3
      2497101.84     13515825.35      2497644.37      13513286.3
      2497861.38     13510714.71
#Sta/Elev= 30
  2318.4  202.55  2543.7  201.65  2911.9  193.04    3372  181.33  3651.4  182.81
  3745.3  176.66  3862.2  176.78  4425.3  180.64  4704.5  179.85    4772  177.36
  4813.8  170.91  4888.9  167.94  4905.9  163.09  4936.1  164.29  4996.4  160.97
    4998  157.41  4999.5  156.21    5095  157.41  5096.2  173.78  5126.8  180.24
  5157.2  180.51  5310.9   177.5  5427.9  176.95  5699.6   181.2  6160.5  195.12
  6692.7  198.23  6791.4  198.73  6973.1  199.29  7334.6   202.4  7495.5  206.85
#Mann= 12 ,-1 , 0
  2318.4     .04       0  2911.9     .12       0  3862.2     .04       0
    4772     .12       0  4888.9      .1       0    4998     .05       0
    5095      .1       0  5157.2     .04       0  5310.9     .12       0
  6692.7     .04       0  6791.4     .05       0  6973.1     .12       0
Bank Sta=4998,5095
XS Rating Curve= 0 ,0
Exp/Cntr=0.3,0.1

Type RM Length L Ch R = 1 ,228454  ,962,962,962
BEGIN DESCRIPTION:
Mapping XS 7fb02493
END DESCRIPTION:
XS GIS Cut Line= 3
      2498270.58     13515385.01      2498436.47     13513362.25
      2498284.64      13510618.5
#Sta/Elev= 30
  2971.5  195.35  3026.3  194.37    3329  187.98  3693.7  179.09  4046.3  176.71
    4139  176.43  4225.7  171.82  4545.8  180.37  4721.3  180.96  4817.7  179.63
    4898  167.33  4899.6  157.36  4901.1  156.16  4996.6  157.36  4997.2  160.25
  5038.4  159.72  5128.7  171.07  5188.6  179.71  5660.1  177.95  5748.3  177.99
  5852.3  179.31  5898.5  179.91  6204.6  188.63  6836.1  192.45    6935  191.14
  7033.9  192.87  7132.8  193.37  7231.7   193.5  7247.9  193.64    7749  199.26
#Mann= 20 ,-1 , 0
  2971.5     .04       0  3026.3     .05       0    3329     .12       0
  4046.3     .05       0    4139     .12       0  4545.8     .04       0
  4721.3     .12       0  4899.6     .05       0  4996.6     .12       0
  5128.7     .04       0  5660.1     .05       0  5748.3     .12       0
  5852.3     .05       0  5898.5     .12       0  6836.1     .04       0
    6935     .12       0  7033.9     .05       0  7132.8     .12       0
  7231.7     .04       0  7247.9     .12       0
Bank Sta=4899.6,4996.6
XS Rating Curve= 0 ,0
Exp/Cntr=0.3,0.1

Type RM Length L Ch R = 1 ,227492  ,633,633,633
BEGIN DESCRIPTION:
Mapping XS 4d260ba9
END DESCRIPTION:
XS GIS Cut Line= 3
      2499988.12     13514968.15      2499304.53     13513416.51
      2498426.38     13510279.97
#Sta/Elev= 30
  3368.4  190.81  3957.4  179.47  4066.4  178.34  4090.5  178.23  4284.6  176.78
  4433.9  175.66  4628.6  172.73  4700.4  167.34    4748  169.84  4792.4  163.54
  4823.4  176.22  4874.4  179.05  4927.7  178.37  4945.4  166.85  4949.2   156.7
  4950.7   155.5  5046.2   156.7    5062  164.75  5152.3  167.19  5255.5  169.12
  5501.7  178.67  5771.5  175.93    6046  177.19    6187  172.31  6344.9  182.13
  6623.2  179.31  6903.9  182.84    8095  192.88  8184.9  194.47  8321.1  198.85
#Mann= 17 ,-1 , 0
  3368.4     .04       0  3957.4     .05       0  4066.4     .12       0
  4090.5     .05       0  4284.6     .03       0  4433.9     .12       0
  4628.6     .05       0  4700.4     .12       0  4874.4      .1       0
  4949.2     .05       0  5046.2      .1       0  5152.3     .05       0
  5255.5     .04       0  5771.5     .12       0  6903.9     .04       0
    8095     .12       0  8184.9     .04       0
Bank Sta=4949.2,5046.2
XS Rating Curve= 0 ,0
Exp/Cntr=0.3,0.1

Type RM Length L Ch R = 1 ,226859  ,1064,1064,1064
BEGIN DESCRIPTION:
Mapping XS 83ff4b08
END DESCRIPTION:
XS GIS Cut Line= 3
      2500281.08     13514664.31      2499855.22     13513195.09
      2498735.08     13509708.92
#Sta/Elev= 30
  3470.3   186.4  4074.4     179  4082.2  178.93  4449.7  178.26  4529.3  171.93
  4614.9  165.47  4635.7   160.5  4687.7  172.15  4736.3  172.53  4771.5  172.84
  4844.1  170.84  4872.5  165.02  4958.4  158.49  5031.6  161.51  5037.4  155.76
  5038.9  154.56  5134.4  155.76  5136.6  164.19  5199.7  169.87  5220.7  166.56
  5449.6  172.59  5569.8  176.82  5676.4  177.12  5834.7  176.66  5963.1  180.68
  6096.8  177.91  7314.5  175.46  7562.3  178.21  7893.8  192.27  8661.7   195.5
#Mann= 13 ,-1 , 0
  3470.3     .04       0  4074.4     .12       0  4082.2     .04       0
  4449.7     .12       0  4529.3     .05       0  4736.3     .12       0
  4771.5      .1       0  5037.4     .05       0  5134.4      .1       0
  5449.6     .12       0  5569.8     .05       0  5676.4     .12       0
  7314.5     .04       0
Bank Sta=5037.4,5134.4
XS Rating Curve= 0 ,0
Exp/Cntr=0.3,0.1

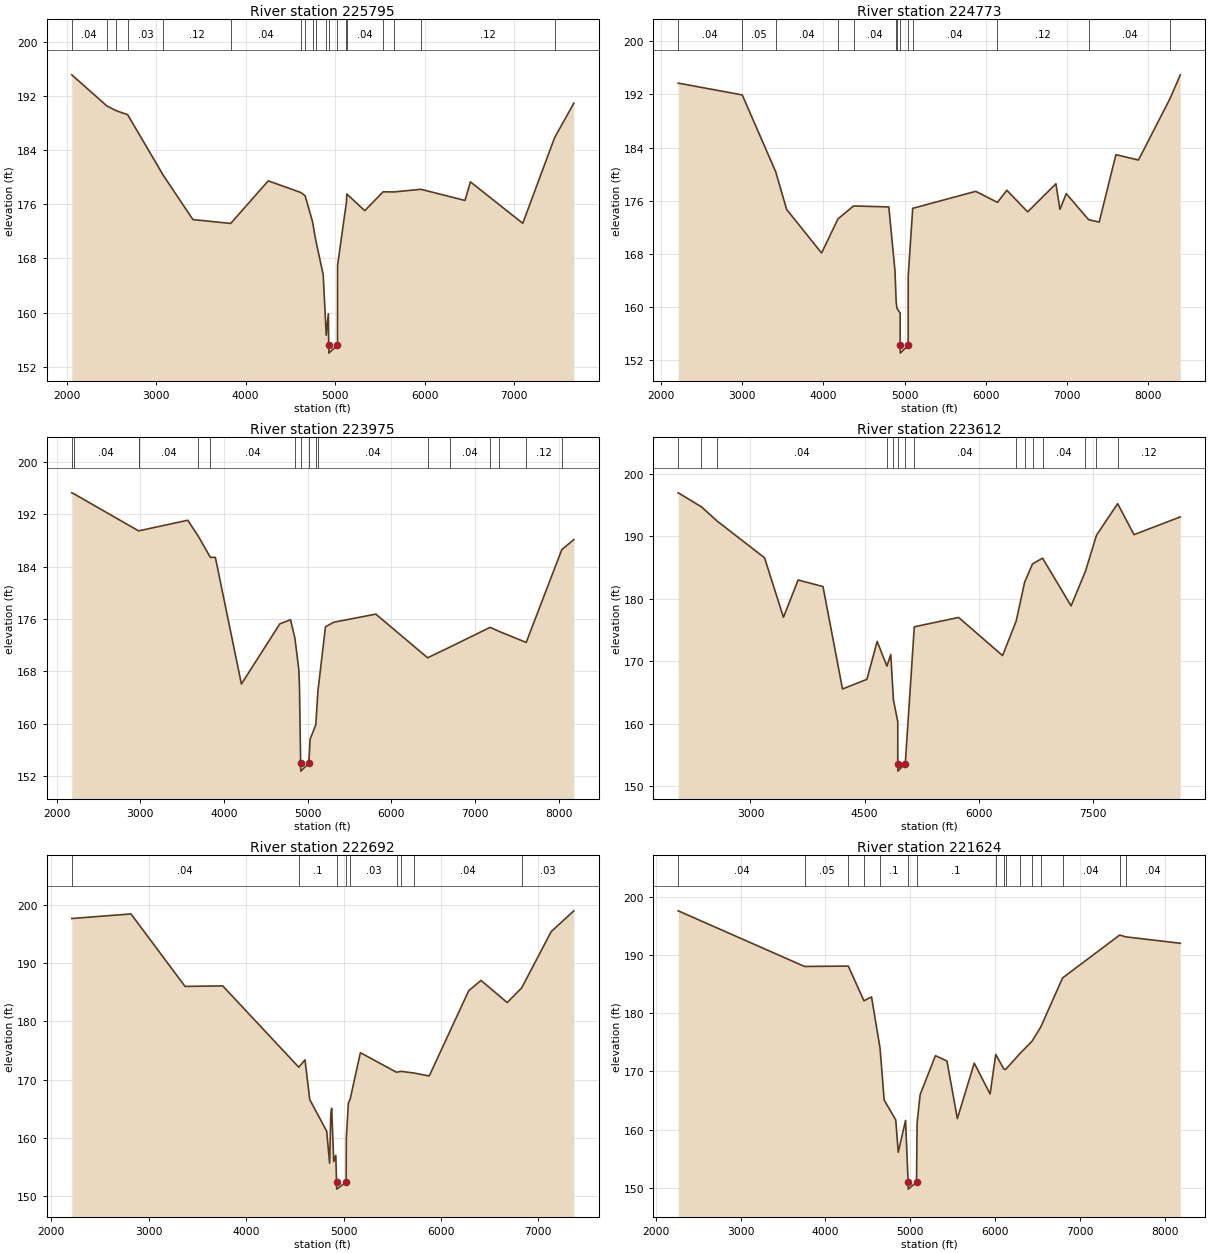
Type RM Length L Ch R = 1 ,225795  ,1022,1022,1022
BEGIN DESCRIPTION:
Mapping XS 97926a34
END DESCRIPTION:
XS GIS Cut Line= 3
      2502689.95      13513991.6      2500378.74     13512418.24
      2499076.67      13509922.6
#Sta/Elev= 30
  2057.7  195.16  2448.7  190.57  2554.3  189.85  2682.1  189.27  3080.9  180.29
  3411.8  173.75    3834  173.18  4253.3  179.48  4618.5  177.75  4665.9  177.27
    4748  173.45  4782.6  170.81  4867.7  165.58  4901.3  156.65  4924.9  159.82
  4929.1   155.2  4930.6     154  5027.2   155.2    5028  166.96    5127  176.34
  5131.2  177.54  5331.6  175.07  5537.4  177.86  5657.4  177.84  5959.3  178.23
    6452  176.58  6512.6  179.33  7097.7   173.2  7453.5  185.87  7668.5  190.97
#Mann= 19 ,-1 , 0
  2057.7     .04       0  2448.7     .05       0  2554.3     .04       0
  2682.1     .03       0  3080.9     .12       0    3834     .04       0
  4618.5     .05       0  4665.9     .12       0    4748     .04       0
  4782.6     .12       0  4901.3      .1       0  4929.1     .05       0
  5027.2      .1       0    5127     .05       0  5131.2     .04       0
  5537.4     .03       0  5657.4     .04       0  5959.3     .12       0
  7453.5     .04       0
Bank Sta=4929.1,5027.2
XS Rating Curve= 0 ,0
Exp/Cntr=0.3,0.1

Type RM Length L Ch R = 1 ,224773  ,798,798,798
BEGIN DESCRIPTION:
Mapping XS 55262cc9
END DESCRIPTION:
XS GIS Cut Line= 3
       2503308.4     13513394.78       2501203.4     13511886.56
      2498914.08     13509119.85
#Sta/Elev= 30
    2212  193.71  2999.8  191.93  3411.9  180.35  3546.6  174.67  3976.5  168.11
  4178.5  173.25  4369.8   175.2  4804.2  175.05  4880.1  165.43  4894.9   160.7
  4905.4  159.76    4944  159.05  4944.4  154.22  4945.9  153.02  5042.5  154.22
  5042.9  164.55  5098.5  174.84    5874   177.4  6142.1  175.74  6257.3  177.56
  6513.5  174.31  6861.3  178.54  6910.8  174.69  6988.9  177.05  7264.1  173.13
    7394  172.76  7599.8  182.93  7877.3  182.12  8265.9  191.38  8392.6  194.96
#Mann= 13 ,-1 , 0
    2212     .04       0  2999.8     .05       0  3411.9     .04       0
  4178.5     .03       0  4369.8     .04       0  4894.9     .12       0
  4905.4      .1       0  4944.4     .05       0  5042.5      .1       0
  5098.5     .04       0  6142.1     .12       0  7264.1     .04       0
  8265.9    .013       0
Bank Sta=4944.4,5042.5
XS Rating Curve= 0 ,0
Exp/Cntr=0.3,0.1

Type RM Length L Ch R = 1 ,223975  ,363,363,363
BEGIN DESCRIPTION:
Mapping XS 50530bb0
END DESCRIPTION:
XS GIS Cut Line= 4
      2503872.67     13513134.39      2502494.63     13512125.27
      2501159.99     13510736.38      2499814.51     13508794.11
#Sta/Elev= 30
  2181.7  195.24  2207.4  195.09    2981  189.43  2982.1  189.44    3567  191.06
  3691.3  188.66  3836.8   185.4  3896.7   185.4    4208  166.08  4667.5  175.26
  4794.8  175.88  4847.2  173.05  4893.9  168.26  4901.1  165.96  4915.5  153.99
    4917  152.79  5013.8  153.99  5028.2  157.64  5096.7  159.87  5121.9     165
  5212.1  174.81  5311.2   175.5  5813.4  176.74  6432.1  170.08  6698.1  171.71
  7178.6  174.72  7284.7  174.11  7609.7  172.42    8035  186.58  8178.7  188.11
#Mann= 17 ,-1 , 0
  2181.7     .05       0  2207.4     .04       0    2981     .05       0
  2982.1     .04       0  3691.3     .05       0  3836.8     .04       0
  4847.2      .1       0  4915.5     .05       0  5013.8      .1       0
  5096.7      .1       0  5121.9     .04       0  6432.1      .1       0
  6698.1     .04       0  7178.6     .12       0  7284.7     .05       0
  7609.7     .12       0    8035     .04       0
Bank Sta=4915.5,5013.8
XS Rating Curve= 0 ,0
Exp/Cntr=0.3,0.1

Type RM Length L Ch R = 1 ,223612  ,920,920,920
BEGIN DESCRIPTION:
Mapping XS a54ae4ec
END DESCRIPTION:
XS GIS Cut Line= 6
      2504295.82     13512895.65      2503015.46     13511886.56
      2501496.37     13510682.13      2501659.13     13509304.09
      2501442.11      13508707.3      2500541.48     13508262.42
#Sta/Elev= 30
  2051.5  196.94  2357.1  194.69  2565.1   192.4  3185.4  186.55  3433.9  177.03
  3626.3     183  3953.2  181.95  4209.6  165.57  4530.1  167.11    4665  173.18
  4793.2  169.21  4843.6  171.09  4878.4  163.84  4935.5  160.34    4936  153.63
  4937.5  152.43  5034.3  153.63  5152.8  175.51  5734.9  177.01  6312.3  170.91
  6491.9  176.45    6602  182.64  6705.7  185.57  6838.1  186.49  7212.4  178.86
  7400.7  184.37  7546.4  190.16  7824.4  195.21  8039.5  190.25  8647.5  193.09
#Mann= 15 ,-1 , 0
  2051.5     .04       0  2357.1     .03       0  2565.1     .04       0
  4793.2     .03       0  4878.4      .1       0    4936     .05       0
  5034.3      .1       0  5152.8     .04       0  6491.9     .03       0
    6602     .04       0  6705.7     .03       0  6838.1     .04       0
  7400.7     .03       0  7546.4     .04       0  7824.4     .12       0
Bank Sta=4936,5034.3
XS Rating Curve= 0 ,0
Exp/Cntr=0.3,0.1

Type RM Length L Ch R = 1 ,222692  ,1068,1068,1068
BEGIN DESCRIPTION:
Mapping XS 565b484a
END DESCRIPTION:
XS GIS Cut Line= 4
      2504545.37     13512570.12      2503482.04     13511712.95
      2501941.24      13509390.9      2501572.76     13508458.85
#Sta/Elev= 30
  2209.2  197.68  2817.3  198.47  3372.3  186.02  3759.1  186.11  4539.5  172.15
  4604.1  173.41  4652.7  166.58  4826.7  161.15  4856.7  155.65  4868.8  164.21
  4877.8  165.08  4898.8  155.94  4919.9  157.01  4927.9  152.41  4929.4  151.21
  5026.2  152.41  5028.1  160.01  5049.2  165.96  5067.7  166.68  5172.5  174.64
  5543.4  171.28  5589.4  171.44  5721.9  171.15  5879.2  170.64  6284.8  185.28
  6411.1  187.05  6679.9  183.25  6828.9  185.78  7131.8  195.44    7364     199
#Mann= 9 ,-1 , 0
  2209.2     .04       0  4539.5      .1       0  4927.9     .05       0
  5026.2      .1       0  5067.7     .03       0  5543.4     .04       0
  5589.4     .03       0  5721.9     .04       0  6828.9     .03       0
Bank Sta=4927.9,5026.2
XS Rating Curve= 0 ,0
Exp/Cntr=0.3,0.1

Type RM Length L Ch R = 1 ,221624  ,1304,1304,1304
BEGIN DESCRIPTION:
Mapping XS 449f0064
END DESCRIPTION:
XS GIS Cut Line= 4
      2504668.01     13512225.07      2504056.04     13510649.58
      2502441.46     13508409.99      2501100.29     13507837.07
#Sta/Elev= 30
    2267  197.57  3753.3  188.02  4268.7  188.08    4453  182.12  4542.2   182.8
  4642.3     174    4691  165.08  4827.2  161.67  4856.6  156.12  4942.5  161.59
    4973  150.99  4974.5  149.79  5071.5  150.99  5078.7  161.16  5114.3  166.02
  5294.2   172.7  5429.8  171.79  5552.4   161.9  5751.2  171.42  5937.7  166.13
  6004.1  172.92  6099.1  170.42  6119.3  170.33  6295.1  173.16  6430.1  175.16
  6533.3   177.6  6790.9  186.05  7462.8  193.41  7535.5   193.1  8176.5     192
#Mann= 16 ,-1 , 0
    2267     .04       0  3753.3     .05       0  4268.7     .04       0
    4453     .03       0  4642.3      .1       0    4973     .05       0
  5071.5      .1       0  6004.1     .05       0  6099.1     .04       0
  6119.3     .05       0  6295.1     .12       0  6430.1     .04       0
  6533.3     .12       0  6790.9     .04       0  7462.8     .03       0
  7535.5     .04       0
Bank Sta=4973,5071.5
XS Rating Curve= 0 ,0
Exp/Cntr=0.3,0.1

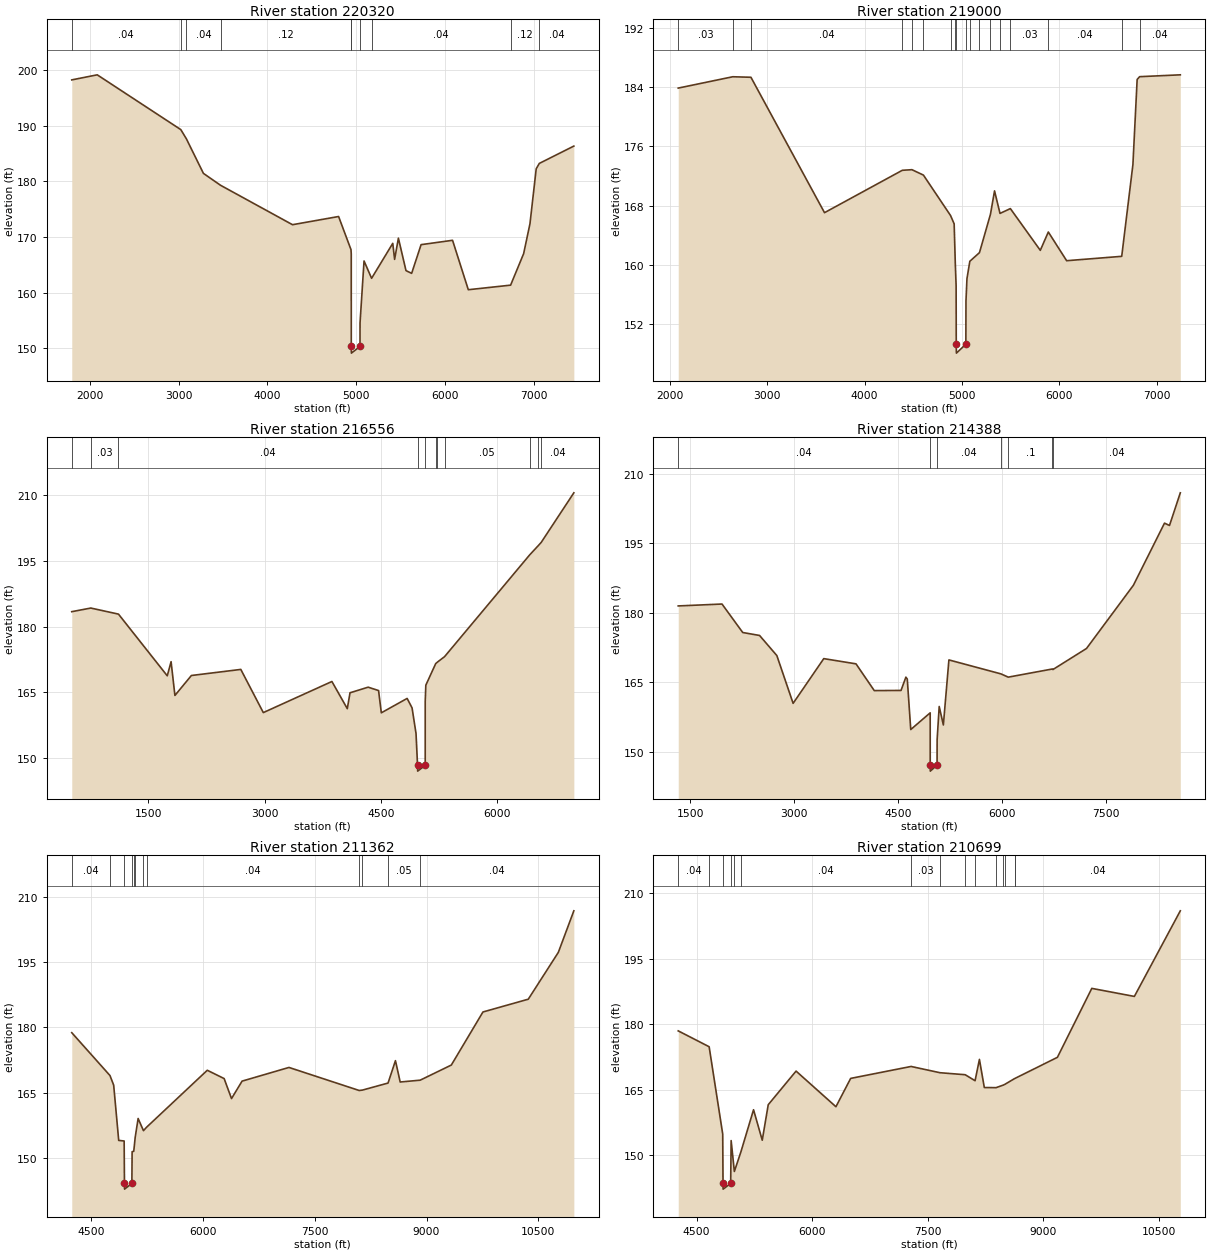
Type RM Length L Ch R = 1 ,220320  ,1320,1320,1320
BEGIN DESCRIPTION:
Mapping XS 838ce936
END DESCRIPTION:
XS GIS Cut Line= 4
      2504954.49     13512120.98      2504681.04     13510363.12
        2504655.     13509282.39      2502532.93     13507459.75
#Sta/Elev= 30
  1794.7   198.2  2081.6  199.11  3023.1  189.28  3085.7  187.64  3278.3  181.42
  3470.8  179.29    4282  172.21  4801.4  173.68  4941.1  167.73  4944.1  166.94
  4944.2  150.36  4945.7  149.16  5042.7  150.36  5042.9  154.58  5088.1   165.7
  5173.2  162.59  5411.6  168.86  5432.5  165.99  5475.2  169.79  5560.8  163.97
  5624.5  163.48  5730.9  168.63  6085.4  169.41    6263  160.54  6739.6  161.36
  6886.5  167.02  6957.8  172.39  7028.1  182.25  7063.1  183.21  7452.1  186.32
#Mann= 10 ,-1 , 0
  1794.7     .04       0  3023.1     .12       0  3085.7     .04       0
  3470.8     .12       0  4941.1      .1       0  4944.2     .05       0
  5042.7      .1       0  5173.2     .04       0  6739.6     .12       0
  7063.1     .04       0
Bank Sta=4944.2,5042.7
XS Rating Curve= 0 ,0
Exp/Cntr=0.3,0.1

Type RM Length L Ch R = 1 ,219000  ,2444,2444,2444
BEGIN DESCRIPTION:
Mapping XS 9f260856
END DESCRIPTION:
XS GIS Cut Line= 4
      2507092.17     13509411.94      2505491.82     13508073.47
      2503860.73     13507837.08      2502527.23     13507359.11
#Sta/Elev= 30
  2088.5  183.86  2647.9  185.39  2834.4  185.32  3589.2  167.05  4387.5  172.77
  4486.4  172.85  4604.1  172.12  4882.1  166.67  4919.3  165.54  4930.8  160.29
  4939.5  157.15  4940.8   149.3  4942.3   148.1  5039.3   149.3  5040.6  155.16
  5050.7  158.15    5080  160.49    5179  161.66  5291.9  166.84  5333.6  169.99
  5389.7  166.95  5496.1   167.6    5803  161.97  5885.5  164.44  6073.3  160.57
  6638.4  161.16  6753.2  173.53  6796.7  185.02  6822.2   185.4  7239.5  185.65
#Mann= 18 ,-1 , 0
  2088.5     .03       0  2647.9    .013       0  2834.4     .04       0
  4387.5     .12       0  4486.4     .04       0  4604.1     .12       0
  4882.1      .1       0  4930.8     .12       0  4940.8     .05       0
  5039.3     .12       0    5080     .03       0    5179     .05       0
  5291.9     .03       0  5389.7     .05       0  5496.1     .03       0
  5885.5     .04       0  6638.4     .12       0  6822.2     .04       0
Bank Sta=4940.8,5039.3
XS Rating Curve= 0 ,0
Exp/Cntr=0.3,0.1

Type RM Length L Ch R = 1 ,216556  ,2168,2168,2168
BEGIN DESCRIPTION:
Mapping XS 7d3a5bdf
END DESCRIPTION:
XS GIS Cut Line= 3
      2507572.47     13509016.99       2504342.5      13505975.1
      2503040.41     13504412.59
#Sta/Elev= 30
     515   183.4   760.6  184.23  1117.1  182.84  1745.7  168.74    1795  171.97
  1844.4  164.25  2056.8  168.81  2693.6   170.2  2983.7  160.33  3867.7  167.44
    4066  161.23  4101.2  164.86  4334.6  166.14    4469  165.37  4504.6  160.28
  4837.2  163.57  4900.7  161.41  4951.9  155.55  4971.5  148.25    4973  146.95
  5070.3  148.25  5070.4  162.96  5078.2   166.6  5205.8  171.54  5227.7  171.87
  5319.7  173.12    6416  196.37  6520.2  198.36  6564.5  199.22  6985.8  210.57
#Mann= 11 ,-1 , 0
     515     .04       0   760.6     .03       0  1117.1     .04       0
  4971.5     .05       0  5070.3     .04       0  5205.8     .05       0
  5227.7     .04       0  5319.7     .05       0    6416     .04       0
  6520.2     .05       0  6564.5     .04       0
Bank Sta=4971.5,5070.3
XS Rating Curve= 0 ,0
Exp/Cntr=0.3,0.1

Type RM Length L Ch R = 1 ,214388  ,3026,3026,3026
BEGIN DESCRIPTION:
Mapping XS ac6f3f73
END DESCRIPTION:
XS GIS Cut Line= 4
      2508587.28     13508657.38      2506269.59     13506873.54
      2506191.46     13505076.66      2504626.46     13503103.64
#Sta/Elev= 30
  1326.1  181.48  1957.4  181.89  2256.4  175.74  2499.3   175.1  2748.4  170.76
  2983.1  160.44  3425.2   170.1  3890.1  168.97  4153.8  163.19  4539.6  163.23
  4609.7   166.1  4629.7  165.68  4679.7  154.78    4960  158.39  4960.6   147.1
  4962.1   145.8  5059.5   147.1  5060.1  152.55  5090.1  159.76  5150.2  155.77
  5230.2  169.82  5979.1  166.81  6086.5   166.1  6722.4  167.86  6730.2  167.74
  7214.8  172.29    7891  185.94  8339.7  199.36  8411.8  198.86  8567.7  205.91
#Mann= 7 ,-1 , 0
  1326.1     .04       0  4960.6     .04       0  5059.5     .04       0
  5979.1     .05       0  6086.5      .1       0  6722.4     .12       0
  6730.2     .04       0
Bank Sta=4960.6,5059.5
XS Rating Curve= 0 ,0
Exp/Cntr=0.3,0.1

Type RM Length L Ch R = 1 ,211362  ,663,663,663
BEGIN DESCRIPTION:
Mapping XS 7e41f3ab
END DESCRIPTION:
XS GIS Cut Line= 4
      2509108.14      13507954.3      2508756.56     13507238.12
      2508418.02     13506548.02      2504679.92     13502975.65
#Sta/Elev= 30
  4239.5   178.8    4752  168.95  4801.9  166.74  4869.4  154.03  4942.4   153.9
  4946.5  144.13    4948  142.83  5045.9  144.13  5049.3  151.44  5071.2  151.53
  5090.3   154.7  5129.9  159.07  5201.6  156.27  5242.7  157.05  6057.9  170.16
  6284.1  168.25  6383.1  163.65  6524.7  167.66    7154  170.81  8096.1  165.51
  8139.6   165.6  8483.6  167.22  8582.8  172.37  8646.3  167.46  8914.5  167.88
  9332.6  171.36  9756.9  183.56 10365.1   186.5 10768.3  197.26 10976.6  206.82
#Mann= 12 ,-1 , 0
  4239.5     .04       0    4752     .12       0  4946.5     .05       0
  5045.9     .12       0  5071.2      .1       0  5090.3     .04       0
  5201.6     .05       0  5242.7     .04       0  8096.1     .05       0
  8139.6      .1       0  8483.6     .05       0  8914.5     .04       0
Bank Sta=4946.5,5045.9
XS Rating Curve= 0 ,0
Exp/Cntr=0.3,0.1

Type RM Length L Ch R = 1 ,210699  ,1458,1458,1458
BEGIN DESCRIPTION:
Mapping XS 2e3bfa12
END DESCRIPTION:
XS GIS Cut Line= 3
      2509459.67     13507407.36      2509147.19     13506847.49
      2504765.25      13502932.9
#Sta/Elev= 30
  4261.5  178.46  4662.7  174.83  4838.9  154.86  4842.9  143.56  4844.4  142.26
  4942.3  143.56  4948.2  153.36    4990   146.3  5074.7  150.77  5239.1  160.42
    5352  153.45  5429.8  161.57  5790.9  169.26  6308.4  161.11  6499.8  167.59
    7284  170.32  7658.1  168.89    7986  168.43  8114.6  167.06  8170.9  171.93
  8234.5   165.5  8387.3  165.47  8479.1  166.05  8500.3  166.22  8628.9  167.56
  8631.9  167.58  9183.3  172.41  9629.7  188.18 10182.3  186.34 10778.5  205.92
#Mann= 15 ,-1 , 0
  4261.5     .04       0  4662.7     .12       0  4842.9     .05       0
  4942.3     .12       0    4990     .05       0  5074.7     .04       0
    7284     .03       0  7658.1     .04       0    7986     .05       0
  8114.6      .1       0  8387.3     .05       0  8479.1      .1       0
  8500.3     .04       0  8628.9     .05       0  8631.9     .04       0
Bank Sta=4842.9,4942.3
XS Rating Curve= 0 ,0
Exp/Cntr=0.3,0.1