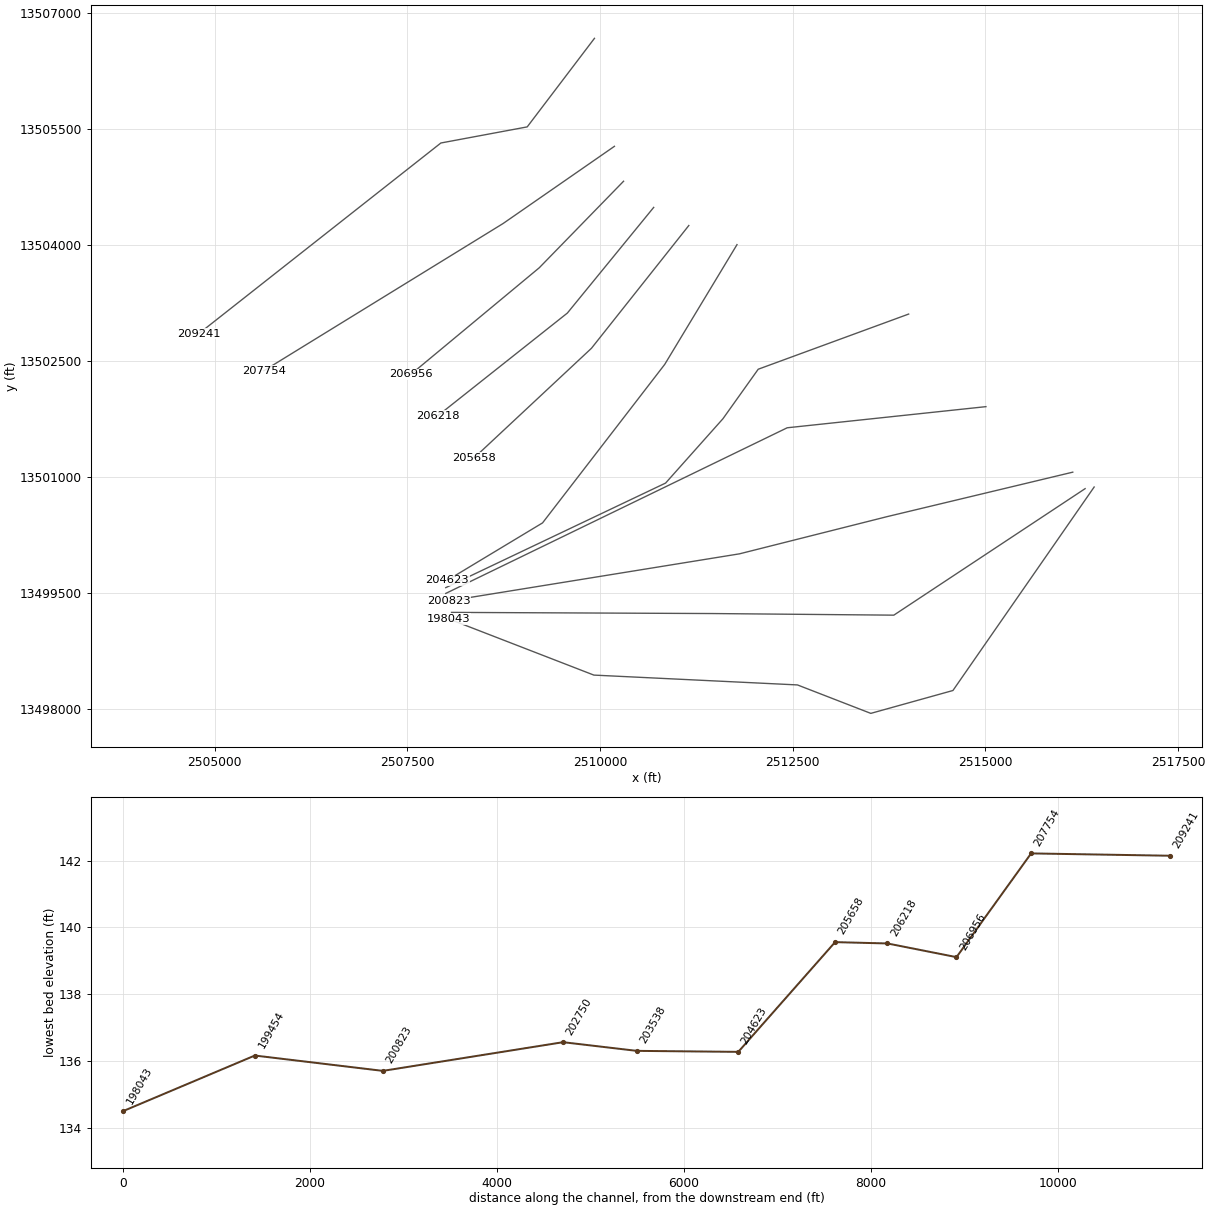
HEC-RAS study COLETO CREEK.prj: COLETO CREEK Base Level Engineering

--- COLETO CREEK.g01 (geometry) --- (continued)

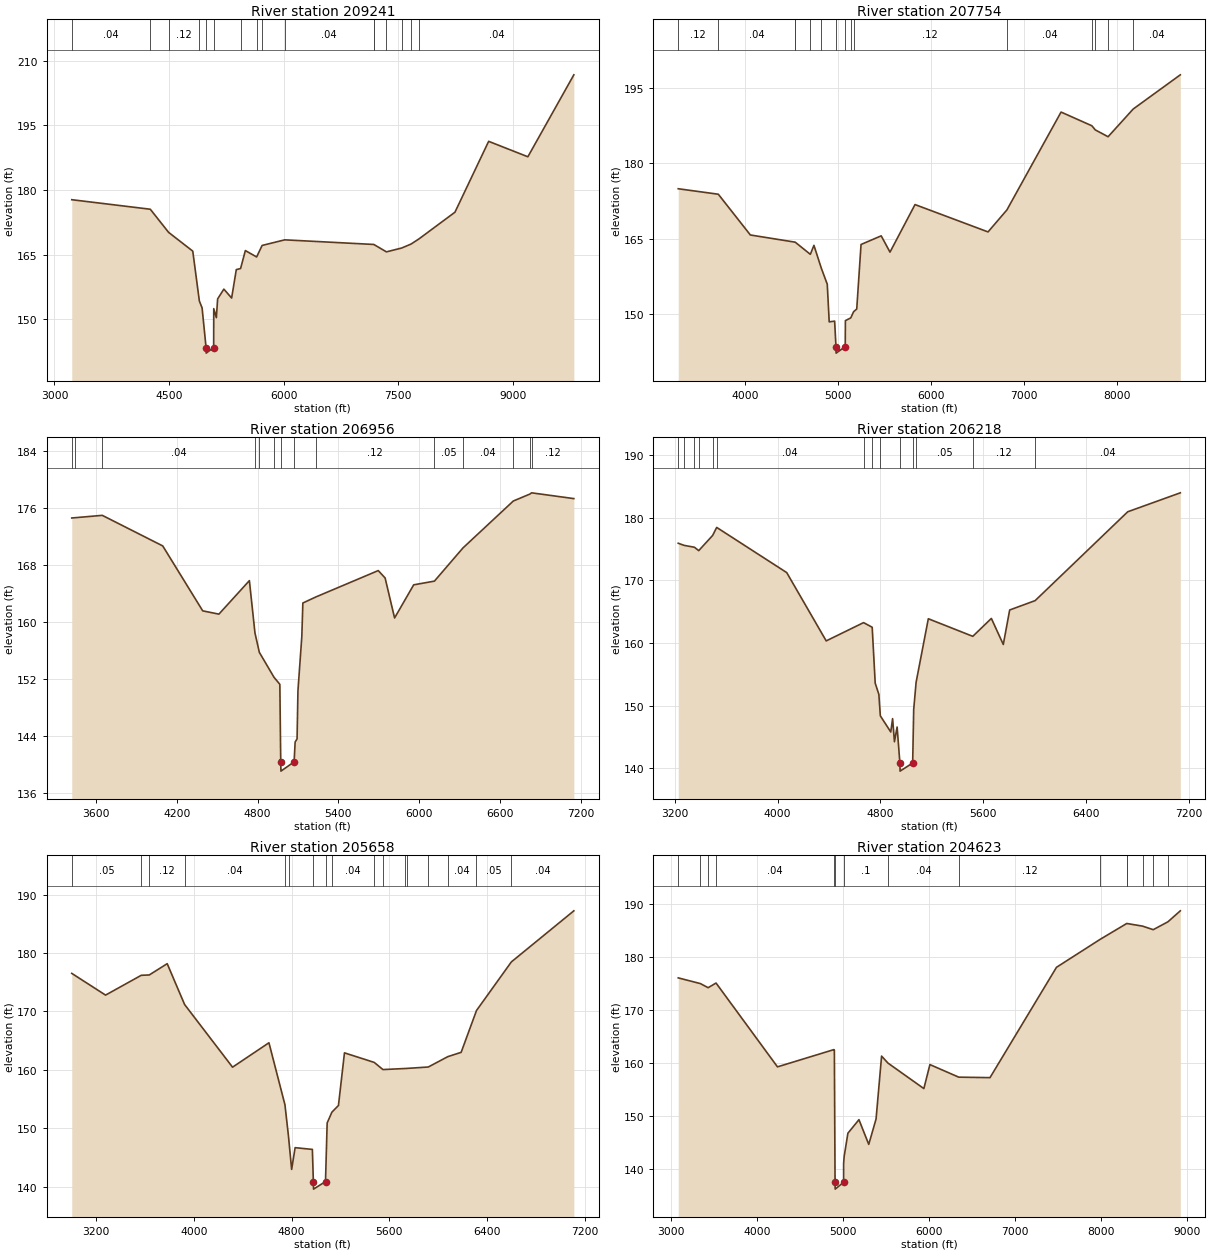
Type RM Length L Ch R = 1 ,209241  ,1487,1487,1487
BEGIN DESCRIPTION:
Mapping XS 8b66ff45
END DESCRIPTION:
XS GIS Cut Line= 4
      2509928.44     13506678.23      2509056.04     13505532.39
      2507936.25     13505324.06      2504797.25     13502858.15
#Sta/Elev= 30
  3226.5  177.74  4254.2  175.53  4494.1  170.16  4810.1  165.81  4896.3  154.25
  4932.2  152.64  4984.2  143.45  4985.7  142.15  5083.6  143.45  5084.7  152.47
  5118.7  150.38  5135.6  154.73    5217     157  5318.7  154.93  5379.7  161.52
    5436  161.78  5498.2  165.94  5646.1  164.46  5717.8  167.13  6013.6  168.43
  7178.4  167.36  7179.4  167.36  7344.9  165.64  7545.3  166.54  7667.7  167.46
  7771.3  168.66  8241.4  174.84  8682.5  191.28  9195.8   187.7  9797.4  206.71
#Mann= 16 ,-1 , 0
  3226.5     .04       0  4254.2     .05       0  4494.1     .12       0
  4896.3      .1       0  4984.2     .05       0  5083.6      .1       0
    5436     .12       0  5646.1     .04       0  5717.8     .03       0
  6013.6     .04       0  7178.4     .05       0  7179.4      .1       0
  7344.9     .12       0  7545.3      .1       0  7667.7     .05       0
  7771.3     .04       0
Bank Sta=4984.2,5083.6
XS Rating Curve= 0 ,0
Exp/Cntr=0.3,0.1

Type RM Length L Ch R = 1 ,207754  ,798,798,798
BEGIN DESCRIPTION:
Mapping XS 48aedbb6
END DESCRIPTION:
XS GIS Cut Line= 3
      2510187.59     13505281.15      2508743.54     13504282.39
      2505640.49     13502377.84
#Sta/Elev= 30
  3282.3  174.93    3713  173.84  4057.7  165.73  4536.2  164.31  4538.2  164.32
  4702.3  161.88  4740.9  163.67  4819.6  159.16  4884.2  155.93  4905.1  148.44
  4963.4  148.59  4977.8  143.52  4979.3  142.22  5077.2  143.52  5079.2  148.69
  5136.9  149.23  5166.9  150.45    5201     151  5247.3  163.84  5463.9  165.56
  5558.5  162.32  5827.4  171.78  6612.4  166.34  6814.9  170.71  7397.3  190.19
  7728.4  187.46  7765.3  186.64  7902.7  185.28  8172.4  190.79    8679   197.6
#Mann= 15 ,-1 , 0
  3282.3     .12       0    3713     .04       0  4536.2     .03       0
  4538.2     .04       0  4702.3    .013       0  4819.6      .1       0
  4977.8     .05       0  5077.2      .1       0  5136.9     .05       0
  5166.9     .12       0  6814.9     .04       0  7728.4     .03       0
  7765.3     .04       0  7902.7     .03       0  8172.4     .04       0
Bank Sta=4977.8,5077.2
XS Rating Curve= 0 ,0
Exp/Cntr=0.3,0.1

Type RM Length L Ch R = 1 ,206956  ,738,738,738
BEGIN DESCRIPTION:
Mapping XS f36b403d
END DESCRIPTION:
XS GIS Cut Line= 3
      2510306.05     13504829.27      2509212.29     13503709.47
      2507546.08     13502329.64
#Sta/Elev= 30
  3419.6  174.63  3445.1  174.67  3646.2     175  4095.2  170.71  4392.1   161.6
  4512.4  161.14  4738.7  165.84  4780.1   158.5  4812.6  155.78  4921.9  152.27
  4964.9  151.29  4971.5  140.41    4973  139.11  5070.9  140.41  5078.5   143.2
  5092.8  143.63  5099.3  150.37    5128  157.96  5135.8   162.7  5233.8  163.56
  5695.8  167.25  5746.7  166.21    5817   160.6  5958.9  165.25    6113  165.77
  6324.5  170.42  6698.7  177.01  6823.5     178  6834.3  178.16  7148.3  177.35
#Mann= 14 ,-1 , 0
  3419.6     .05       0  3445.1     .12       0  3646.2     .04       0
  4780.1     .12       0  4812.6     .04       0  4921.9      .1       0
  4971.5     .05       0  5070.9      .1       0  5233.8     .12       0
    6113     .05       0  6324.5     .04       0  6698.7    .013       0
  6823.5     .04       0  6834.3     .12       0
Bank Sta=4971.5,5070.9
XS Rating Curve= 0 ,0
Exp/Cntr=0.3,0.1

Type RM Length L Ch R = 1 ,206218  ,560,560,560
BEGIN DESCRIPTION:
Mapping XS 3eee2cf6
END DESCRIPTION:
XS GIS Cut Line= 3
      2510696.68     13504490.73      2509576.88     13503123.54
      2507898.58     13501796.51
#Sta/Elev= 30
  3226.9  175.95  3272.5  175.61    3353  175.31  3386.3  174.77  3494.8   177.2
  3526.2  178.48    4071  171.26  4378.3  160.34    4669  163.26  4736.2  162.52
  4759.6  153.58    4788   151.8  4799.5  148.36  4880.6  145.78  4894.9  147.91
  4909.3  144.22  4930.1  146.57  4951.7  140.82  4953.2  139.52  5051.1  140.82
  5059.1  149.37  5077.9  153.73  5172.9  163.88  5518.9  161.07  5663.4  163.93
  5756.3  159.77    5806  165.28  6004.3  166.78  6724.5  180.98  7133.7  184.01
#Mann= 14 ,-1 , 0
  3226.9     .05       0  3272.5     .12       0    3353     .05       0
  3386.3     .04       0  3494.8     .05       0  3526.2     .04       0
    4669      .1       0  4736.2     .12       0  4799.5      .1       0
  4951.7     .05       0  5051.1      .1       0  5077.9     .05       0
  5518.9     .12       0  6004.3     .04       0
Bank Sta=4951.7,5051.1
XS Rating Curve= 0 ,0
Exp/Cntr=0.3,0.1

Type RM Length L Ch R = 1 ,205658  ,1035,1035,1035
BEGIN DESCRIPTION:
Mapping XS 947fb77a
END DESCRIPTION:
XS GIS Cut Line= 3
       2511152.4     13504256.35      2509889.38     13502667.81
      2508366.72     13501249.27
#Sta/Elev= 30
  3000.8   176.5  3277.5  172.78  3569.6  176.17  3635.3  176.23  3782.1  178.16
  3924.6  171.17  4317.1  160.44  4615.1  164.62  4746.2     154  4775.2  148.59
  4800.9  142.94  4829.4  146.66  4970.7  146.36  4978.7  140.86  4980.2  139.56
  5078.1  140.86  5091.7  150.89  5130.6  152.74  5184.1  153.88  5233.4  162.89
  5476.8  161.26  5548.3  160.03  5727.8  160.21  5745.7  160.23  5919.8  160.47
  6079.2  162.24  6188.6  162.98  6314.3  170.14  6599.6  178.46  7111.3  187.21
#Mann= 17 ,-1 , 0
  3000.8     .05       0  3569.6     .04       0  3635.3     .12       0
  3924.6     .04       0  4746.2     .12       0  4775.2      .1       0
  4978.7     .05       0  5078.1      .1       0  5130.6     .04       0
  5476.8     .05       0  5548.3     .04       0  5727.8      .1       0
  5745.7     .04       0  5919.8     .05       0  6079.2     .04       0
  6314.3     .05       0  6599.6     .04       0
Bank Sta=4978.7,5078.1
XS Rating Curve= 0 ,0
Exp/Cntr=0.3,0.1

Type RM Length L Ch R = 1 ,204623  ,1085,1085,1085
BEGIN DESCRIPTION:
Mapping XS e0c7aa30
END DESCRIPTION:
XS GIS Cut Line= 4
      2511777.38     13504008.92       2510839.9     13502459.47
       2509255.1     13500408.56      2508020.75     13499666.67
#Sta/Elev= 30
  3082.3  176.06  3341.2  174.98  3430.1  174.21  3522.4  175.09  4237.2   159.3
  4893.8  162.55  4899.3  162.48  4907.4  137.57  4908.9  136.27  5006.9  137.57
    5007  141.08  5013.3  142.42  5056.8   146.8  5185.4  149.35  5299.5   144.7
  5384.6  149.48  5448.9  161.33  5523.2  160.01  5940.7  155.21  6011.3  159.73
  6346.8  157.36  6710.5  157.27  7484.2  178.05  7992.7  183.32  8300.4  186.29
  8301.4  186.31  8485.4  185.81  8610.2  185.14  8781.1  186.62  8925.3  188.69
#Mann= 15 ,-1 , 0
  3082.3     .04       0  3341.2     .05       0  3430.1     .12       0
  3522.4     .04       0  4893.8      .1       0  4907.4     .05       0
  5006.9      .1       0  5523.2     .04       0  6346.8     .12       0
  7992.7     .03       0  8300.4     .05       0  8301.4     .04       0
  8485.4     .05       0  8610.2     .04       0  8781.1     .05       0
Bank Sta=4907.4,5006.9
XS Rating Curve= 0 ,0
Exp/Cntr=0.3,0.1

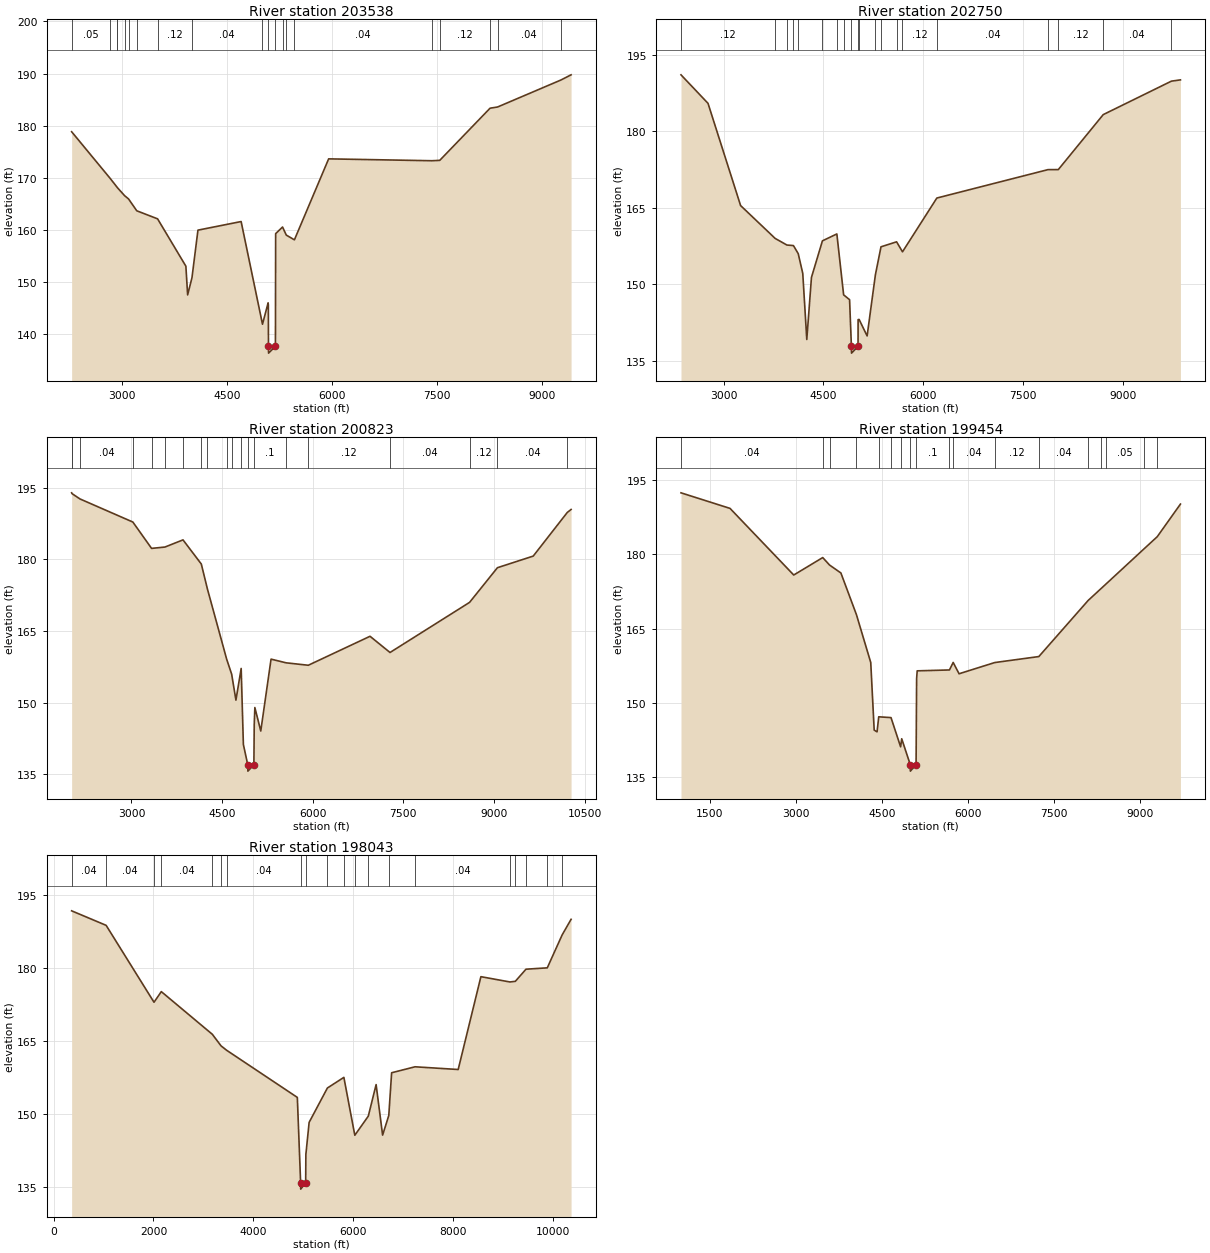
Type RM Length L Ch R = 1 ,203538  ,788,788,788
BEGIN DESCRIPTION:
Mapping XS 08c33f3d
END DESCRIPTION:
XS GIS Cut Line= 5
      2514003.97     13503110.52       2512052.6     13502396.83
      2511595.11     13501756.35      2510851.62     13500924.15
      2507999.69     13499570.74
#Sta/Elev= 30
  2280.6  178.82  2830.5  169.87  2934.4  168.09  2935.9  168.06  3037.7  166.54
  3094.2  165.91  3211.1  163.64  3508.9  162.09  3913.2     153  3938.4  147.48
  4000.5   150.8  4085.7  159.92  4702.8  161.57  5008.1  141.85  5088.6  145.96
  5091.8  145.55  5093.5   137.6    5095   136.3    5193   137.6  5196.2  159.25
  5294.8  160.52  5348.2  158.97  5464.3  158.06  5953.6  173.61  7426.7  173.25
  7541.2  173.32  8260.4  183.34  8367.8  183.57  9272.2  188.75  9418.2  189.75
#Mann= 20 ,-1 , 0
  2280.6     .05       0  2830.5     .12       0  2934.4     .05       0
  2935.9     .12       0  3037.7     .05       0  3094.2     .12       0
  3211.1     .05       0  3508.9     .12       0  4000.5     .04       0
  5008.1      .1       0  5093.5     .04       0    5193      .1       0
  5294.8     .04       0  5348.2     .12       0  5464.3     .04       0
  7426.7     .05       0  7541.2     .12       0  8260.4     .05       0
  8367.8     .04       0  9272.2     .05       0
Bank Sta=5093.5,5193
XS Rating Curve= 0 ,0
Exp/Cntr=0.3,0.1

Type RM Length L Ch R = 1 ,202750  ,1927,1927,1927
BEGIN DESCRIPTION:
Mapping XS d49f6a7f
END DESCRIPTION:
XS GIS Cut Line= 3
      2515006.52     13501912.59      2512428.44     13501639.16
      2507999.68     13499496.02
#Sta/Elev= 30
  2356.7  191.04    2763  185.46  3253.2  165.45  3772.6  159.02  3949.7  157.72
  4048.3  157.61  4120.3  156.02  4188.4  152.17  4248.8  139.23  4319.2  151.39
    4484  158.54  4701.1  159.89  4803.1  147.97  4892.4  147.02  4920.1  137.86
  4921.6  136.56  5019.9  137.86  5020.7  143.12  5036.2  143.15  5156.3  139.92
    5281  151.91  5365.1  157.37  5599.5  158.35  5688.4  156.39  6205.1  166.92
  7876.8  172.48  8032.2  172.49  8707.9  183.25  9733.1   189.8  9869.3  190.05
#Mann= 20 ,-1 , 0
  2356.7     .12       0  3772.6     .05       0  3949.7      .1       0
  4048.3     .05       0  4120.3      .1       0    4484     .04       0
  4701.1     .12       0  4803.1     .04       0  4920.1     .04       0
  5019.9     .04       0  5036.2      .1       0    5281     .04       0
  5365.1     .04       0  5599.5     .05       0  5688.4     .12       0
  6205.1     .04       0  7876.8     .05       0  8032.2     .12       0
  8707.9     .04       0  9733.1     .05       0
Bank Sta=4920.1,5019.9
XS Rating Curve= 0 ,0
Exp/Cntr=0.3,0.1

Type RM Length L Ch R = 1 ,200823  ,1369,1369,1369
BEGIN DESCRIPTION:
Mapping XS 7aa48df1
END DESCRIPTION:
XS GIS Cut Line= 4
      2516132.91     13501064.95      2513720.61     13500488.56
      2511809.98     13500008.23      2508042.66     13499399.91
#Sta/Elev= 30
  2009.4   193.9  2016.1  193.73  2147.6  192.62  3022.8  187.79  3332.4  182.28
  3553.2  182.56  3852.7  184.06  4155.6  179.01    4256  173.83  4574.9  159.13
  4658.1  155.97  4728.6  150.55  4815.4  157.17    4852  141.26    4925     137
  4926.5   135.7  5025.8     137  5031.6  145.48  5041.9     149  5139.9  144.09
    5310  159.12  5558.9  158.35  5926.3  157.84  6948.2   163.9  7279.1  160.51
  8595.7  170.99  9056.7  178.24  9649.2  180.67 10212.6  189.79 10275.8  190.42
#Mann= 20 ,-1 , 0
  2009.4     .04       0  2016.1     .05       0  2147.6     .04       0
  3022.8     .12       0  3332.4     .12       0  3553.2     .05       0
  3852.7     .12       0  4155.6     .05       0    4256     .03       0
  4574.9     .12       0  4658.1      .1       0  4815.4      .1       0
    4925     .04       0  5025.8      .1       0  5558.9     .05       0
  5926.3     .12       0  7279.1     .04       0  8595.7     .12       0
  9056.7     .04       0 10212.6     .05       0
Bank Sta=4925,5025.8
XS Rating Curve= 0 ,0
Exp/Cntr=0.3,0.1

Type RM Length L Ch R = 1 ,199454  ,1411,1411,1411
BEGIN DESCRIPTION:
Mapping XS 83271790
END DESCRIPTION:
XS GIS Cut Line= 4
      2516292.98     13500851.45      2513811.69     13499214.68
      2511464.46     13499235.52      2508074.12     13499250.39
#Sta/Elev= 30
   995.6  192.47  1850.8  189.32  2961.7  175.84  3467.5  179.37  3585.5  177.87
  3784.4  176.25  4055.6  167.81  4304.8  158.14  4364.8  144.46  4414.8  144.11
  4444.2  147.15  4658.2  146.99  4825.7  141.08  4844.8  142.71  4994.4  137.46
  4995.9  136.16  5095.3  137.46  5104.8  154.86  5114.8  156.45  5677.3  156.63
  5742.5  158.15  5844.9  155.86  6467.6  158.13  7236.2  159.34  8096.3  170.69
  8317.8  173.06  8416.1  174.11  9067.9   181.1    9301  183.59  9705.8  190.19
#Mann= 18 ,-1 , 0
   995.6     .04       0  3467.5     .03       0  3585.5     .04       0
  4055.6     .12       0  4444.2     .04       0  4658.2     .03       0
  4825.7      .1       0  4994.4     .05       0  5095.3      .1       0
  5677.3     .12       0  5742.5     .04       0  6467.6     .12       0
  7236.2     .04       0  8096.3     .05       0  8317.8     .04       0
  8416.1     .05       0  9067.9     .04       0    9301     .05       0
Bank Sta=4994.4,5095.3
XS Rating Curve= 0 ,0
Exp/Cntr=0.3,0.1

Type RM Length L Ch R = 1 ,198043  ,2447,2447,2447
BEGIN DESCRIPTION:
Mapping XS 06801f50
END DESCRIPTION:
XS GIS Cut Line= 6
      2516410.42     13500872.82      2514578.32     13498239.75
      2513513.08     13497943.85      2512561.69      13498311.9
      2509920.71     13498439.18      2508042.12       13499165.
#Sta/Elev= 30
   362.7  191.84  1052.7  188.85  2010.5     173  2156.7  175.19  3177.9  166.39
    3351  164.02  3463.9   163.1  4877.7  153.39  4943.7  135.79  4945.2  134.49
  5044.6  135.79  5048.6  141.65  5113.9  148.25  5479.4  155.33  5808.9  157.52
  6027.6  145.59  6297.5  149.53  6453.7  156.03  6583.8  145.62  6707.4  149.67
  6764.1  158.47  7232.8   159.7  8095.6  159.14    8550  178.27  9130.6  177.18
  9238.8  177.31  9451.9  179.81  9878.1  180.09 10176.1  186.89 10354.1  190.09
#Mann= 20 ,-1 , 0
   362.7     .04       0  1052.7     .04       0  2010.5     .05       0
  2156.7     .04       0  3177.9     .04       0    3351     .03       0
  3463.9     .04       0  4943.7     .04       0  5044.6     .04       0
  5479.4     .04       0  5808.9     .05       0  6027.6     .04       0
  6297.5     .05       0  6707.4     .04       0  7232.8     .04       0
  9130.6     .03       0  9238.8     .04       0  9451.9     .12       0
  9878.1     .12       0 10176.1     .05       0
Bank Sta=4943.7,5044.6
XS Rating Curve= 0 ,0
Exp/Cntr=0.3,0.1