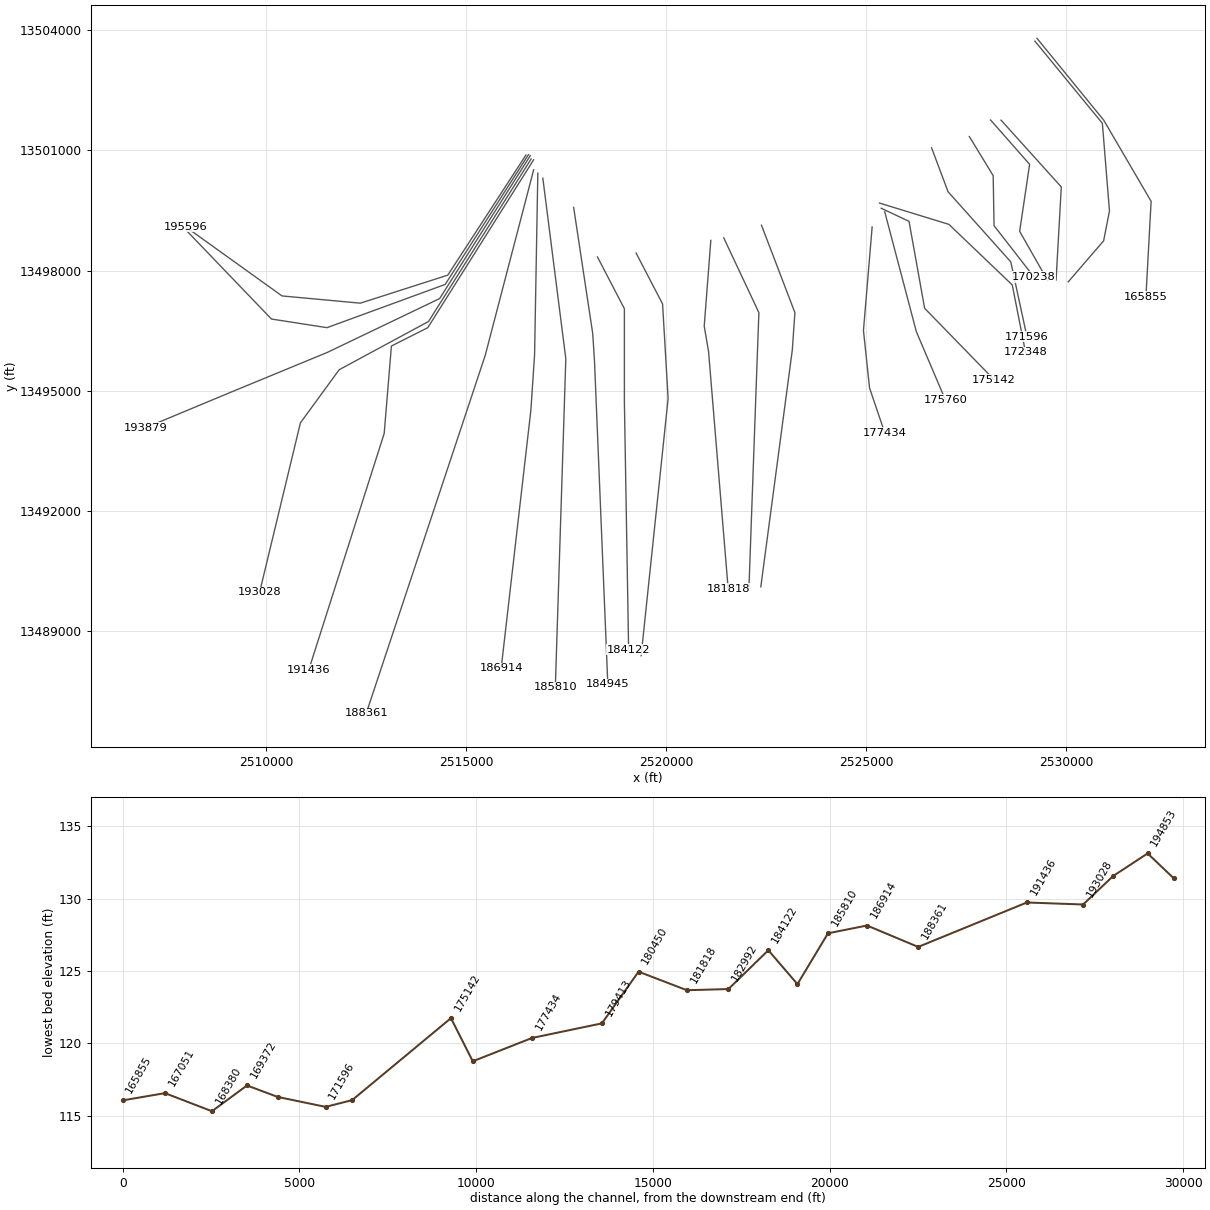
HEC-RAS study COLETO CREEK.prj: COLETO CREEK Base Level Engineering

--- COLETO CREEK.g01 (geometry) --- (continued)

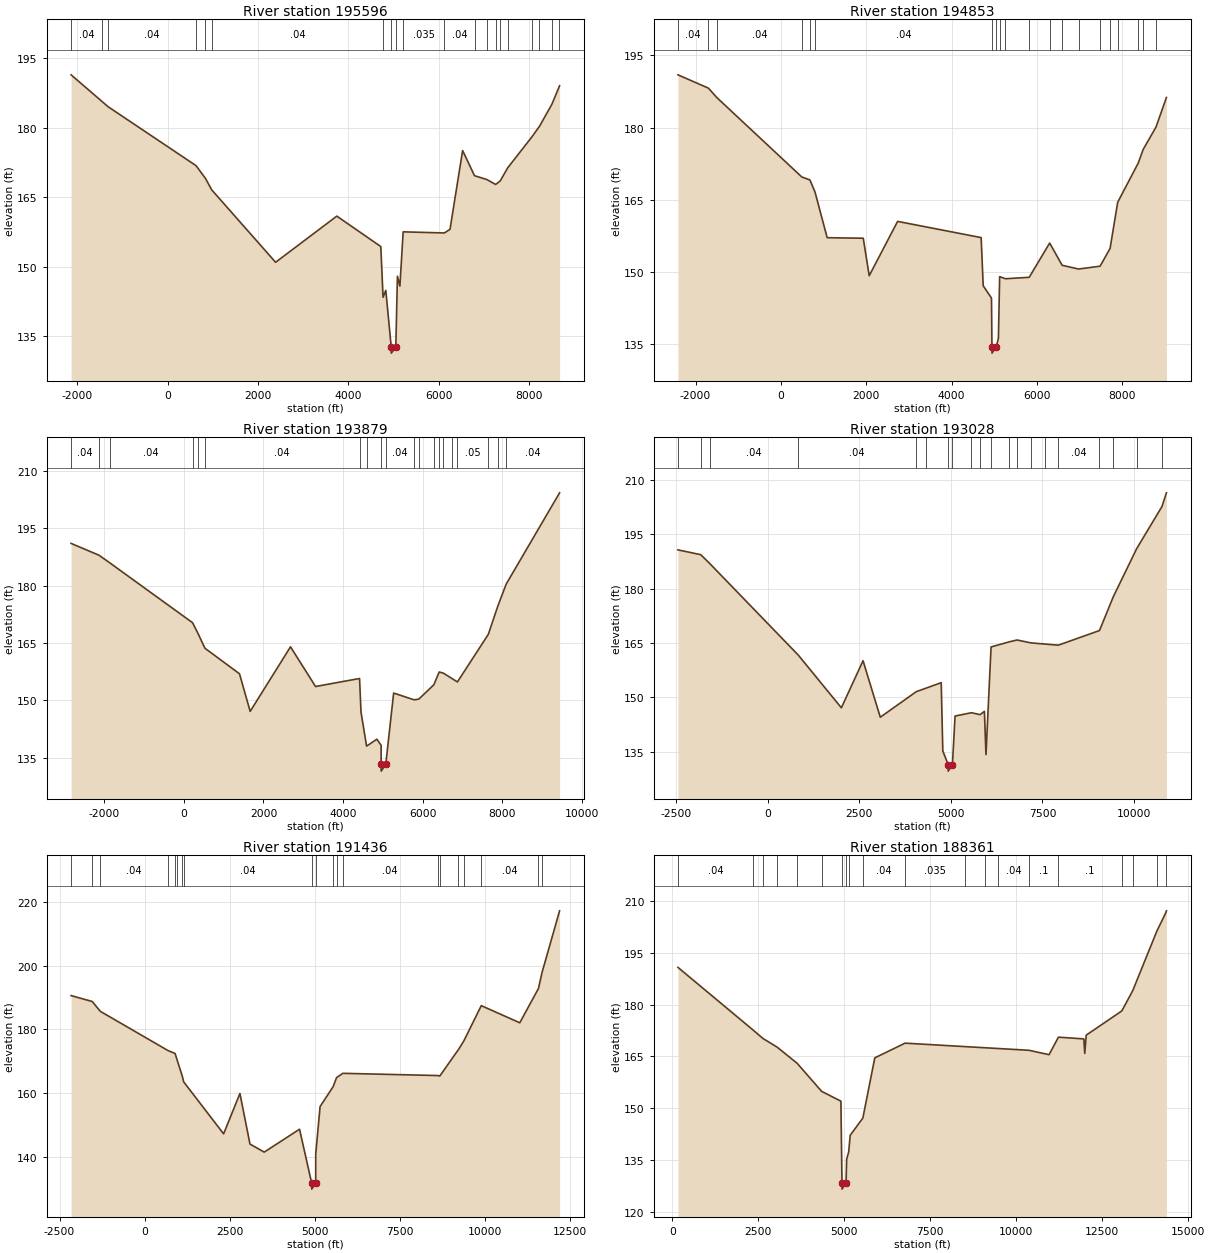
Type RM Length L Ch R = 1 ,195596  ,743,743,743
BEGIN DESCRIPTION:
Mapping XS 1b022d55
END DESCRIPTION:
XS GIS Cut Line= 5
       2516495.8     13500883.47      2514541.67     13497886.72
      2512353.35      13497186.9      2510395.02     13497367.46
      2507989.61     13499089.66
#Sta/Elev= 30
 -2132.2  191.38 -1443.9   185.6 -1311.4  184.49     631   171.8   839.3  169.05
   976.1   166.6  2389.4  150.98  3742.9  160.93  4715.3  154.37    4765  143.44
  4825.8  144.93    4946   132.7  4947.5   131.4    5047   132.7  5082.8  147.97
  5137.1  145.84  5209.8  157.54  6122.2   157.3  6245.5  158.09  6524.3  175.06
  6787.2  169.64  7060.9  168.81  7254.1  167.75  7356.2  168.52  7519.1  171.31
  8048.1  177.91  8223.8  180.29  8496.7  185.02  8659.7  188.83  8667.9  189.02
#Mann= 20 ,-1 , 0
 -2132.2     .04       0 -1443.9    .013       0 -1311.4     .04       0
     631     .03       0   839.3     .04       0   976.1     .04       0
    4765      .1       0    4946     .05       0    5047      .1       0
  5209.8    .035       0  6122.2     .04       0  6787.2     .04       0
  7060.9     .12       0  7254.1     .05       0  7356.2     .12       0
  7519.1     .05       0  8048.1     .04       0  8223.8     .12       0
  8496.7     .03       0  8659.7     .05       0
Bank Sta=4946,5047
XS Rating Curve= 0 ,0
Exp/Cntr=0.3,0.1

Type RM Length L Ch R = 1 ,194853  ,974,974,974
BEGIN DESCRIPTION:
Mapping XS 742eaf53
END DESCRIPTION:
XS GIS Cut Line= 5
      2516559.83     13500894.13      2514476.43     13497654.85
      2511520.02     13496575.79      2510131.13     13496791.07
      2508020.76     13498983.55
#Sta/Elev= 30
 -2413.3  190.97 -1698.3   188.2 -1501.7  186.24   489.2  169.74   678.6  169.13
     798  166.63  1083.7  157.12  1929.3  157.01  2068.9  149.22  2734.3  160.51
  4691.6  157.14  4740.2  147.12  4934.3  144.57  4944.7  134.43  4946.2  133.13
  5045.7  134.43  5096.4  136.23  5125.2  149.02  5262.2  148.59  5818.1  148.89
  6297.7  156.01  6589.7  151.39  6974.6  150.61  7479.1   151.2  7713.2  154.89
  7891.5  164.48  8372.4  172.62  8488.3  175.46    8788  180.09  9033.9  186.26
#Mann= 20 ,-1 , 0
 -2413.3     .04       0 -1698.3    .013       0 -1501.7     .04       0
   489.2     .03       0   678.6     .03       0     798     .04       0
  4944.7     .04       0  5045.7      .1       0  5125.2     .05       0
  5262.2     .12       0  5818.1     .04       0  6297.7     .12       0
  6589.7     .05       0  6974.6     .04       0  7479.1     .05       0
  7713.2     .04       0  7891.5     .12       0  8372.4     .05       0
  8488.3     .04       0    8788     .12       0
Bank Sta=4944.7,5045.7
XS Rating Curve= 0 ,0
Exp/Cntr=0.3,0.1

Type RM Length L Ch R = 1 ,193879  ,851,851,851
BEGIN DESCRIPTION:
Mapping XS 1b0d29a6
END DESCRIPTION:
XS GIS Cut Line= 5
      2516605.26     13500868.85      2514336.71     13497301.53
      2511526.96     13495957.74      2509096.41     13494957.74
      2506980.24     13494077.16
#Sta/Elev= 30
 -2828.9  190.99 -2128.5  187.91 -1864.3  185.97   220.1   170.3   350.8  167.64
   529.7  163.65  1398.6  156.97  1666.6  147.16  2678.9  164.01  3307.7  153.65
  4412.2  155.74  4448.9  146.97  4588.8   138.1    4847   139.9  4953.7  138.31
  4954.8  133.37  4956.3  131.57  5070.7  133.37  5268.1  151.94  5780.6  150.18
  5899.4  150.36  6277.3  154.11  6411.1  157.44  6516.2  157.14  6726.4  155.77
  6868.9  154.84  7644.6  167.26  7883.4  174.64  8093.9  180.39  9433.5  204.19
#Mann= 20 ,-1 , 0
 -2828.9     .04       0 -2128.5    .013       0 -1864.3     .04       0
   220.1     .05       0   350.8     .04       0   529.7     .04       0
  4412.2      .1       0  4588.8      .1       0  4954.8     .04       0
  5070.7     .04       0  5780.6     .04       0  5899.4     .12       0
  6277.3     .12       0  6411.1     .05       0  6516.2     .04       0
  6726.4      .1       0  6868.9     .05       0  7644.6     .04       0
  7883.4     .12       0  8093.9     .04       0
Bank Sta=4954.8,5070.7
XS Rating Curve= 0 ,0
Exp/Cntr=0.3,0.1

Type RM Length L Ch R = 1 ,193028  ,1592,1592,1592
BEGIN DESCRIPTION:
Mapping XS 8993da3b
END DESCRIPTION:
XS GIS Cut Line= 5
      2516626.09     13500785.51      2514059.72     13496730.18
      2511825.58     13495527.18      2510855.85     13494201.73
      2509834.41     13489972.95
#Sta/Elev= 30
 -2445.9  190.67 -1824.8  189.34 -1570.8  186.82   837.9  161.62  2013.2  147.08
  2604.8  160.07  3075.3  144.48  4057.6  151.53  4309.8  152.45  4737.6  154.02
  4781.4  135.17  4927.6   131.4  4929.1   129.6  5043.5   131.4  5115.3   144.8
  5562.9  145.72  5798.9  145.19    5916   146.1    5959  134.17  6098.3  163.87
  6599.9   165.3    6807  165.79  7181.9     165  7556.8  164.68  7931.8  164.36
  9056.6   168.4  9431.5  177.69 10072.6  191.03 10762.8  202.66 10883.4  206.41
#Mann= 20 ,-1 , 0
 -2445.9     .04       0 -1824.8    .013       0 -1570.8     .04       0
   837.9     .04       0  4057.6     .03       0  4309.8     .04       0
  4927.6     .04       0  5043.5      .1       0  5562.9     .12       0
  5798.9      .1       0  6098.3     .05       0  6599.9    .013       0
    6807    .035       0  7181.9     .04       0  7556.8     .04       0
  7931.8     .04       0  9056.6     .04       0  9431.5     .03       0
 10072.6     .04       0 10762.8     .05       0
Bank Sta=4927.6,5043.5
XS Rating Curve= 0 ,0
Exp/Cntr=0.3,0.1

Type RM Length L Ch R = 1 ,191436  ,3075,3075,3075
BEGIN DESCRIPTION:
Mapping XS c47796d7
END DESCRIPTION:
XS GIS Cut Line= 5
       2516688.6     13500764.69      2514040.85     13496575.79
      2513131.13     13496117.46      2512950.58      13493936.9
      2511063.58     13488035.48
#Sta/Elev= 30
   -2161  190.67 -1540.6  188.82 -1300.3  185.71   688.9  173.36   895.4  172.45
   962.6  170.16  1110.4  165.21  1147.7  163.52  2322.3  147.14  2801.1  159.85
  3097.1  143.93  3515.4  141.39  4553.6   148.6  4910.7  131.64  4912.2  129.74
  5028.6  131.64  5029.8  140.78  5157.6  155.73  5541.9  162.01  5641.1  164.83
  5826.8   166.2  8608.9   165.5  8676.7  165.36  9224.7  173.69    9381  176.37
  9895.6  187.51 11026.8  182.11 11576.5  192.92 11680.9  197.93   12197  217.36
#Mann= 20 ,-1 , 0
   -2161     .04       0 -1540.6    .013       0 -1300.3     .04       0
   688.9     .12       0   895.4     .05       0   962.6     .12       0
  1110.4     .05       0  1147.7     .04       0  4910.7    .035       0
  5028.6     .04       0  5541.9    .013       0  5641.1    .035       0
  5826.8     .04       0  8608.9     .03       0  8676.7     .04       0
  9224.7     .03       0    9381     .04       0  9895.6     .04       0
 11576.5    .013       0 11680.9     .04       0
Bank Sta=4910.7,5028.6
XS Rating Curve= 0 ,0
Exp/Cntr=0.3,0.1

Type RM Length L Ch R = 1 ,188361  ,1447,1447,1447
BEGIN DESCRIPTION:
Mapping XS 10d46d1a
END DESCRIPTION:
XS GIS Cut Line= 3
      2516688.58     13500514.66      2515478.35     13495888.29
      2512501.08     13486952.16
#Sta/Elev= 30
   165.7  190.75  2352.8  172.62  2632.8  170.23  3050.1   167.7  3635.3  162.99
  4342.2  154.93  4903.2  152.09  4934.3  128.57  4935.8  126.67  5052.4  128.57
  5070.8  135.36  5129.6  137.41  5172.6  142.22  5541.6  147.22  5887.8   164.6
  6767.9  168.85  8500.4  167.86  9090.7  167.52  9479.4   167.3   10372  166.79
 10953.7  165.52 11227.4  170.58 11965.9  170.08 11992.2  165.88 12034.4  171.16
 13070.6  178.17   13387  184.03 14089.9  201.26 14348.6  206.55 14366.8  207.09
#Mann= 20 ,-1 , 0
   165.7     .04       0  2352.8     .03       0  2632.8     .04       0
  3050.1     .04       0  3635.3     .04       0  4342.2     .03       0
  4934.3     .05       0  5052.4     .05       0  5129.6     .04       0
  5541.6     .04       0  6767.9    .035       0  8500.4     .04       0
  9090.7     .03       0  9479.4     .04       0   10372      .1       0
 11227.4      .1       0 13070.6      .1       0   13387     .12       0
 14089.9     .05       0 14348.6     .12       0
Bank Sta=4934.3,5052.4
XS Rating Curve= 0 ,0
Exp/Cntr=0.3,0.1

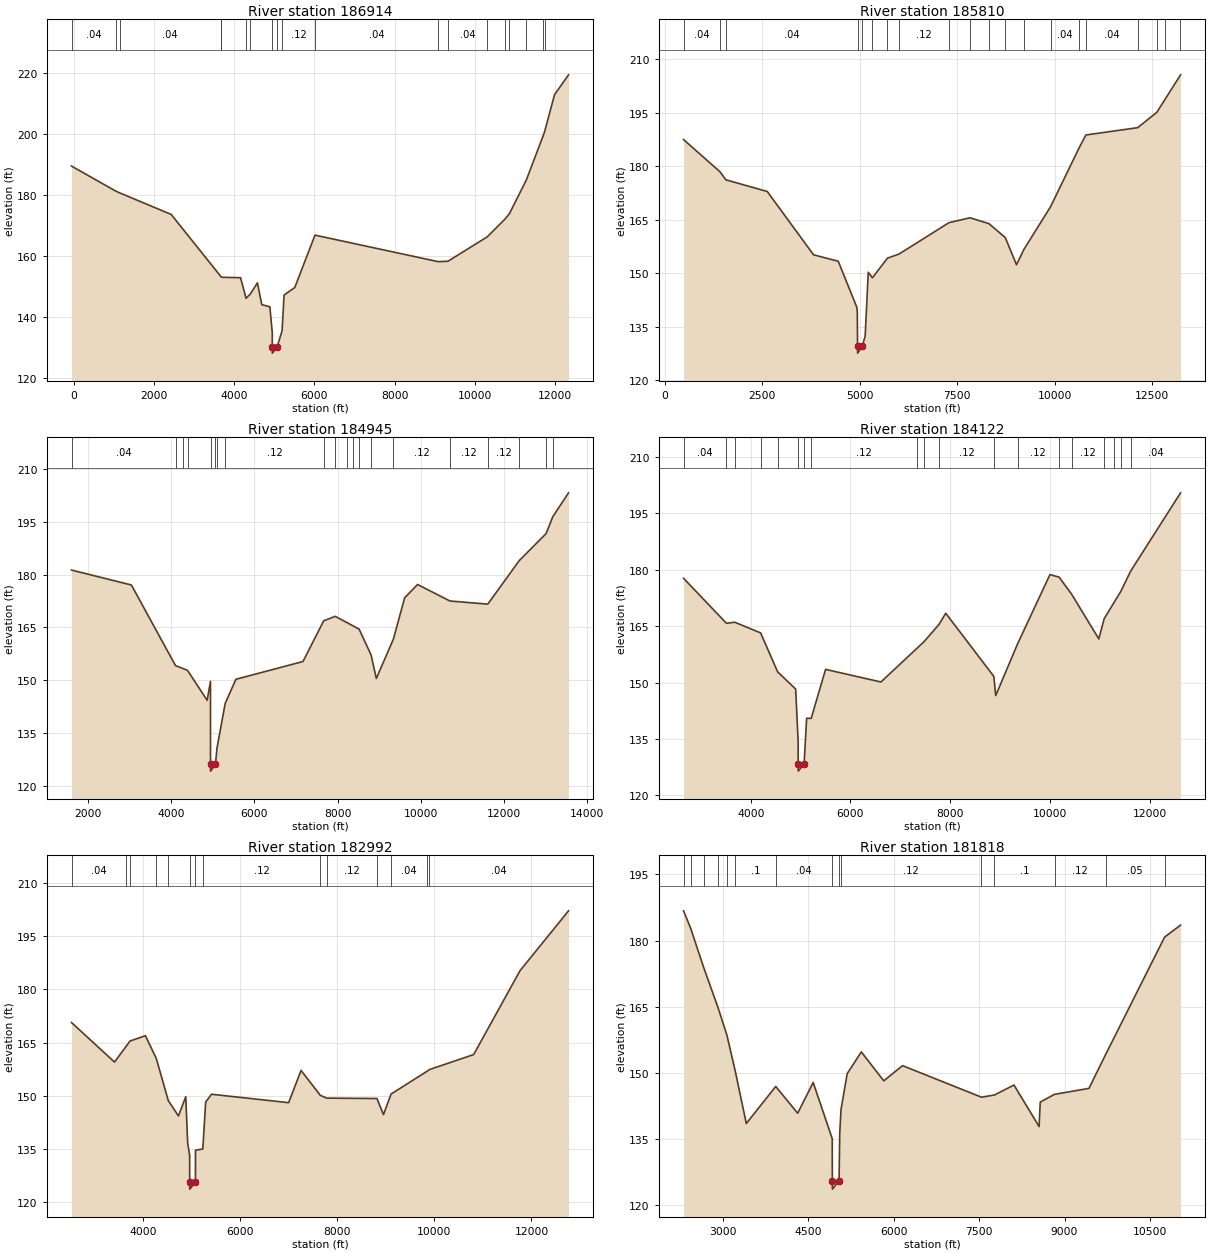
Type RM Length L Ch R = 1 ,186914  ,1104,1104,1104
BEGIN DESCRIPTION:
Mapping XS eb70c214
END DESCRIPTION:
XS GIS Cut Line= 4
      2516792.75     13500431.34      2516711.43     13495897.84
      2516618.59     13494513.77      2515876.25     13488078.55
#Sta/Elev= 30
   -57.8  189.42  1040.8  181.26  1139.4  180.66  2428.9  173.58  3661.4  153.36
  3683.8     153  4159.2  152.86  4296.7  146.11  4405.5  147.56  4579.5  151.17
  4689.7  144.02  4890.2  143.32  4950.7   134.9  4951.4  130.05  4952.9  128.15
  5069.5  130.05  5195.4   135.5  5245.4   147.2  5511.6  149.63  6016.4   166.8
  9085.9  158.12  9331.8  158.24 10311.9  166.22 10759.9  172.11 10867.6  173.85
   11289  184.88 11711.3  199.43 11750.8  200.99 11992.8  212.83 12341.5  219.31
#Mann= 19 ,-1 , 0
   -57.8     .04       0  1040.8     .03       0  1139.4     .04       0
  3661.4     .03       0  3683.8     .04       0  4296.7     .03       0
  4405.5     .04       0  4951.4     .04       0  5069.5     .04       0
  5195.4     .12       0  6016.4     .04       0  9085.9    .035       0
  9331.8     .04       0 10311.9     .12       0 10759.9     .04       0
 10867.6     .12       0   11289     .04       0 11711.3     .03       0
 11750.8     .04       0
Bank Sta=4951.4,5069.5
XS Rating Curve= 0 ,0
Exp/Cntr=0.3,0.1

Type RM Length L Ch R = 1 ,185810  ,865,865,865
BEGIN DESCRIPTION:
Mapping XS 52f00973
END DESCRIPTION:
XS GIS Cut Line= 3
      2516917.76     13500306.29      2517492.68     13495800.19
      2517230.28     13487599.02
#Sta/Elev= 30
   481.4  187.51  1413.1   178.5  1568.3  176.21  2628.7  172.94  3816.1  155.18
  4449.7  153.38  4928.7  140.39  4938.5  139.11  4944.4  129.51  4945.9  127.61
  5062.6  129.51  5139.3  132.36  5219.3   150.3  5325.8  148.74  5711.7  154.25
  6007.9  155.39  7291.6  164.21    7830  165.56  8313.1  163.94  8733.9  160.01
  9021.3   152.4  9214.4  156.75  9894.6  168.66 10625.8  185.14 10801.4  188.79
   12130  190.84 12621.1  195.15 12821.3  198.61 13216.2  205.43 13229.4  205.66
#Mann= 20 ,-1 , 0
   481.4     .04       0  1413.1     .03       0  1568.3     .04       0
  4944.4     .05       0  5062.6     .12       0  5325.8     .04       0
  5711.7     .12       0  6007.9     .12       0  7291.6     .05       0
    7830     .04       0  8313.1     .12       0  8733.9      .1       0
  9214.4     .12       0  9894.6     .04       0 10625.8     .12       0
 10801.4     .04       0   12130     .04       0 12621.1     .12       0
 12821.3     .03       0 13216.2     .04       0
Bank Sta=4944.4,5062.6
XS Rating Curve= 0 ,0
Exp/Cntr=0.3,0.1

Type RM Length L Ch R = 1 ,184945  ,823,823,823
BEGIN DESCRIPTION:
Mapping XS 150bf78e
END DESCRIPTION:
XS GIS Cut Line= 4
      2517688.59     13499577.12      2518165.42     13496429.53
      2518209.83     13495743.86      2518542.75     13487681.34
#Sta/Elev= 30
  1608.8  181.28  3047.1  177.03    4107  154.11  4283.3  153.29  4395.5  152.76
  4867.6  144.24  4947.2  149.64  4948.2     126  4949.7   124.1  5066.4     126
  5103.4  130.64  5300.7  143.36  5558.3  150.22  7169.7  155.27  7666.5  166.84
  7943.4  168.12    8225  166.34  8360.9  165.48  8517.7  164.48  8804.6  157.17
  8931.2  150.45  9342.2  161.66  9611.8  173.39  9922.1  177.17 10699.3  172.48
 11609.4  171.59 12362.3  183.94 13010.3  191.65 13170.4  196.44 13548.8  203.24
#Mann= 20 ,-1 , 0
  1608.8     .04       0    4107     .12       0  4283.3     .12       0
  4395.5     .04       0  4948.2     .05       0  5066.4     .04       0
  5103.4     .05       0  5300.7     .12       0  7666.5     .05       0
  7943.4     .12       0    8225     .05       0  8360.9     .12       0
  8517.7     .05       0  8804.6      .1       0  9342.2     .12       0
 10699.3     .12       0 11609.4     .12       0 12362.3     .04       0
 13010.3     .05       0 13170.4     .04       0
Bank Sta=4948.2,5066.4
XS Rating Curve= 0 ,0
Exp/Cntr=0.3,0.1

Type RM Length L Ch R = 1 ,184122  ,1130,1130,1130
BEGIN DESCRIPTION:
Mapping XS 5bd38d09
END DESCRIPTION:
XS GIS Cut Line= 4
      2518284.78     13498339.25      2518957.52     13497048.02
      2518957.52       13494723.      2519063.58      13488535.5
#Sta/Elev= 30
  2653.2  177.71  3513.7  165.75  3681.1  166.02  4199.2  163.19  4540.5  152.84
  4902.2  148.25  4952.2  134.23  4953.1  128.34  4954.6  126.44  5071.3  128.34
  5122.2   140.5  5213.6  140.46  5502.2  153.49  6612.2  150.14  7344.6  159.21
    7473   160.8  7776.8  165.44  7912.4  168.42  8877.5  151.62  8915.1  146.53
  9353.9  160.28 10002.7  178.69 10185.4  178.02 10438.2  173.46 10982.9  161.59
 11090.1  166.95 11288.6  171.28 11423.9  174.22   11621   179.6 12622.6  200.43
#Mann= 19 ,-1 , 0
  2653.2     .04       0  3513.7     .12       0  3681.1     .04       0
  4199.2     .03       0  4540.5     .04       0  4953.1     .05       0
  5071.3     .04       0  5213.6     .12       0  7344.6     .04       0
    7473     .05       0  7776.8     .12       0  8877.5      .1       0
  9353.9     .12       0 10185.4     .05       0 10438.2     .12       0
 11090.1      .1       0 11288.6     .05       0 11423.9     .12       0
   11621     .04       0
Bank Sta=4953.1,5071.3
XS Rating Curve= 0 ,0
Exp/Cntr=0.3,0.1

Type RM Length L Ch R = 1 ,182992  ,1174,1174,1174
BEGIN DESCRIPTION:
Mapping XS dcf51507
END DESCRIPTION:
XS GIS Cut Line= 4
      2519250.51     13498436.87      2519912.38     13497167.37
      2520051.24     13494806.83       2519376.1     13488389.85
#Sta/Elev= 30
  2516.2  170.68  3402.8  159.55  3630.1  163.74  3722.3  165.47  4040.4  166.97
  4265.2  160.52  4511.8  148.68  4721.6  144.37  4871.8  149.79  4911.9  136.65
    4952  133.36  4952.9  125.66  4954.4  123.76  5071.2  125.66  5072.2  134.73
  5223.4  135.06  5282.6  148.29  5402.8  150.48  6993.2  148.11  7249.5  157.19
  7647.8  150.16  7781.3  149.39  8814.2  149.28  8948.8  144.75  9106.1  150.54
  9848.2  156.96  9896.6  157.43   10809  161.66 11764.3  185.28 12764.9  202.14
#Mann= 14 ,-1 , 0
  2516.2     .04       0  3630.1     .03       0  3722.3     .04       0
  4265.2     .03       0  4511.8     .04       0  4952.9     .05       0
  5071.2     .04       0  5223.4     .12       0  7647.8     .05       0
  7781.3     .12       0  8814.2      .1       0  9106.1     .04       0
  9848.2      .1       0  9896.6     .04       0
Bank Sta=4952.9,5071.2
XS Rating Curve= 0 ,0
Exp/Cntr=0.3,0.1

Type RM Length L Ch R = 1 ,181818  ,1368,1368,1368
BEGIN DESCRIPTION:
Mapping XS 5e378b92
END DESCRIPTION:
XS GIS Cut Line= 4
      2521119.14     13498754.25      2520954.05     13496613.99
      2521062.12     13495981.56      2521553.02     13490058.18
#Sta/Elev= 30
  2306.6  186.74  2429.4  182.87  2657.6  174.01  2912.7  164.81  3069.2  158.53
  3213.8   150.5  3409.1  138.55  3926.3  146.94  4311.8  140.88  4584.1  147.85
  4918.9  135.11  4920.6  125.58  4922.1  123.68  5038.9  125.58  5050.7  136.36
  5073.2  141.73  5181.7  149.84  5429.9  154.77  5823.9  148.22  6154.4  151.66
  7541.1  144.51    7769  145.01  8111.7  147.27  8553.2  137.85  8573.3   143.4
  8824.3  145.16  9429.6  146.51  9720.1  154.13   10759   180.8 11038.5   183.5
#Mann= 15 ,-1 , 0
  2306.6     .03       0  2429.4     .12       0  2657.6     .04       0
  2912.7     .05       0  3069.2     .12       0  3213.8      .1       0
  3926.3     .04       0  4920.6     .05       0  5038.9     .04       0
  5073.2     .12       0  7541.1     .05       0    7769      .1       0
  8824.3     .12       0  9720.1     .05       0   10759     .04       0
Bank Sta=4920.6,5038.9
XS Rating Curve= 0 ,0
Exp/Cntr=0.3,0.1

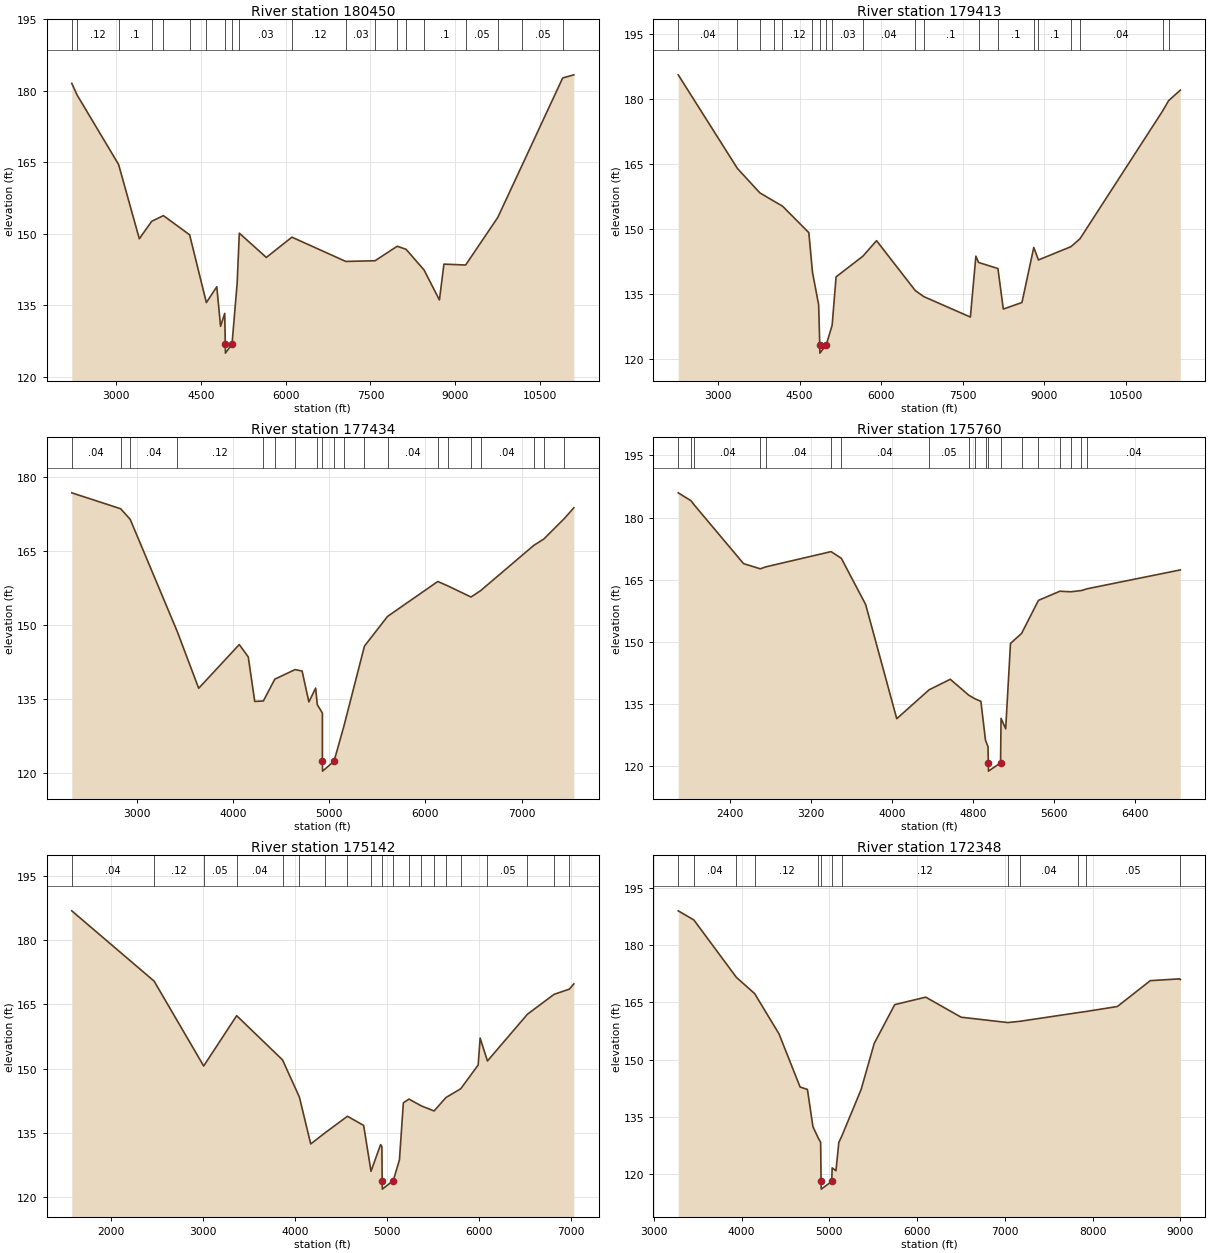
Type RM Length L Ch R = 1 ,180450  ,1037,1037,1037
BEGIN DESCRIPTION:
Mapping XS 1e26db42
END DESCRIPTION:
XS GIS Cut Line= 4
      2521442.33     13498816.67      2522321.24     13496950.36
      2522266.98     13495485.52        2522074.     13490125.75
#Sta/Elev= 30
  2210.8  181.53  2308.7  179.03  3040.3  164.52  3407.2  148.95  3627.6  152.62
  3834.2   153.8  4298.2  149.77  4594.5  135.56  4779.4  138.89  4845.9  130.59
  4919.5   133.3  4930.2  126.86  4931.7  124.96    5049  126.86  5139.7  139.61
  5178.4  150.12  5656.5  145.03  6109.6  149.28  7063.7  144.19  7582.4  144.34
  7974.9  147.38  8131.2  146.74  8449.4  142.41    8722  136.12  8802.1  143.63
  9186.3  143.44  9755.2  153.41 10183.9   164.3 10905.2  182.67 11102.8  183.33
#Mann= 20 ,-1 , 0
  2210.8     .03       0  2308.7     .12       0  3040.3      .1       0
  3627.6     .05       0  3834.2     .03       0  4298.2     .12       0
  4594.5      .1       0  4930.2     .05       0    5049      .1       0
  5178.4     .03       0  6109.6     .12       0  7063.7     .03       0
  7582.4     .05       0  7974.9     .03       0  8131.2     .05       0
  8449.4      .1       0  9186.3     .05       0  9755.2     .04       0
 10183.9     .05       0 10905.2     .04       0
Bank Sta=4930.2,5049
XS Rating Curve= 0 ,0
Exp/Cntr=0.3,0.1

Type RM Length L Ch R = 1 ,179413  ,1979,1979,1979
BEGIN DESCRIPTION:
Mapping XS f7ee4b6a
END DESCRIPTION:
XS GIS Cut Line= 4
      2522386.33     13499131.38      2523221.84     13496950.36
      2523156.74      13496017.2      2522369.24     13490109.16
#Sta/Elev= 30
  2268.6  185.51  3355.8  163.95    3770  158.31  4022.7  156.44  4185.3  155.26
  4669.7  149.15  4737.1     140  4850.1  132.56  4870.9  123.29  4872.4  121.39
  4989.7  123.29  5098.4  127.82  5170.9  138.96  5662.8  143.71  5915.1   147.3
  6627.6  135.79  6783.8  134.41  7640.2   129.7  7741.1  143.73  7790.7  142.28
  8146.4  140.88  8245.5  131.55  8588.5  133.05  8805.7  145.74  8891.7  142.86
  9488.1  145.91  9654.6  147.73 11172.6  177.14 11285.6  179.57 11499.9  181.98
#Mann= 20 ,-1 , 0
  2268.6     .04       0  3355.8     .05       0    3770      .1       0
  4022.7      .1       0  4185.3     .12       0  4737.1     .12       0
  4870.9     .05       0  4989.7     .12       0  5098.4     .03       0
  5662.8     .04       0  6627.6     .05       0  6783.8      .1       0
  7790.7     .05       0  8146.4      .1       0  8805.7     .04       0
  8891.7      .1       0  9488.1     .05       0  9654.6     .04       0
 11172.6     .05       0 11285.6     .04       0
Bank Sta=4870.9,4989.7
XS Rating Curve= 0 ,0
Exp/Cntr=0.3,0.1

Type RM Length L Ch R = 1 ,177434  ,1674,1674,1674
BEGIN DESCRIPTION:
Mapping XS d79bb030
END DESCRIPTION:
XS GIS Cut Line= 4
      2525153.26     13499087.93      2524936.25     13496505.48
      2525088.16     13495073.19      2525467.95     13493955.53
#Sta/Elev= 30
  2327.8  176.82  2835.3  173.59  2934.5  171.44  3422.6  148.71  3645.4  137.18
  4066.8  146.05  4160.1  143.54  4227.4  134.51    4317  134.61  4435.6  139.03
    4646  140.97  4719.1  140.68  4789.4  134.41  4859.6  137.22  4876.9  133.85
  4929.9  132.15    4930  122.38  4931.5  120.38  5050.5  122.38  5154.9  129.64
  5366.2  145.73  5605.7  151.75  6127.7  158.84  6229.1  157.97  6472.4  155.69
  6572.7  156.99  7124.9  166.17    7228  167.44  7440.8   171.6  7540.1  173.78
#Mann= 20 ,-1 , 0
  2327.8     .04       0  2835.3    .013       0  2934.5     .04       0
  3422.6     .12       0    4317     .04       0  4435.6     .05       0
    4646     .04       0  4876.9     .05       0    4930     .05       0
  5050.5     .12       0  5154.9     .04       0  5366.2     .04       0
  5605.7     .04       0  6127.7     .03       0  6229.1     .04       0
  6472.4     .03       0  6572.7     .04       0  7124.9     .05       0
    7228     .04       0  7440.8     .05       0
Bank Sta=4930,5050.5
XS Rating Curve= 0 ,0
Exp/Cntr=0.3,0.1

Type RM Length L Ch R = 1 ,175760  ,618,618,618
BEGIN DESCRIPTION:
Mapping XS ee4e2107
END DESCRIPTION:
XS GIS Cut Line= 3
      2525467.94     13499467.72      2526260.04     13496472.93
      2526986.89     13494769.71
#Sta/Elev= 30
  1892.2  185.98  2018.2  184.07  2051.1  183.02  2536.3  168.88  2701.3  167.63
  2756.9  168.11  3398.5  171.78  3499.7  170.18  3739.9  159.01  4046.3  131.43
  4365.8  138.42  4574.1  140.95  4757.4  137.09  4815.8  136.26  4875.9  135.62
  4921.3  126.22    4946  124.68  4949.2  120.77  4950.7  118.77  5069.7  120.77
  5074.7  131.51  5120.4  128.99  5167.7  149.61  5277.1  152.03  5443.3  160.01
  5655.2  162.22  5761.1  162.08    5867  162.38  5923.5  162.81  6841.8  167.36
#Mann= 19 ,-1 , 0
  1892.2     .04       0  2018.2     .05       0  2051.1     .04       0
  2701.3     .05       0  2756.9     .04       0  3398.5    .013       0
  3499.7     .04       0  4365.8     .05       0  4757.4     .03       0
  4815.8     .05       0  4921.3     .12       0  4949.2     .05       0
  5069.7     .12       0  5277.1     .04       0  5443.3     .12       0
  5655.2     .04       0  5761.1     .12       0    5867     .05       0
  5923.5     .04       0
Bank Sta=4949.2,5069.7
XS Rating Curve= 0 ,0
Exp/Cntr=0.3,0.1

Type RM Length L Ch R = 1 ,175142  ,2794,2794,2794
BEGIN DESCRIPTION:
Mapping XS d2064750
END DESCRIPTION:
XS GIS Cut Line= 4
      2525381.13     13499554.53      2526075.58     13499229.01
       2526466.2     13497058.87      2528200.86     13495280.84
#Sta/Elev= 30
  1573.4  186.94  2468.4  170.47  3006.8  150.59  3365.5  162.38  3863.9  152.02
    4047  143.31    4170  132.33    4322  134.87  4569.3  138.82  4745.3  136.67
  4825.2  125.93  4929.1  132.17  4943.2  131.73  4946.7  123.75  4948.2  121.75
  5067.2  123.75  5134.2   128.6  5176.7  141.96  5237.6  142.84  5371.6  141.25
  5510.8  140.06  5639.8  143.21  5800.7  145.27  5989.8  150.83  6011.1  157.13
  6090.6  151.77  6525.4  162.73  6815.3  167.39  6980.5  168.59  7029.4  169.83
#Mann= 20 ,-1 , 0
  1573.4     .04       0  2468.4     .12       0  3006.8     .05       0
  3365.5     .04       0  3863.9     .04       0    4047     .04       0
    4322     .12       0  4569.3     .12       0  4825.2     .12       0
  4946.7     .05       0  5067.2     .12       0  5237.6     .04       0
  5371.6     .05       0  5510.8     .03       0  5639.8     .05       0
  5800.7     .12       0  6090.6     .05       0  6525.4     .04       0
  6815.3     .03       0  6980.5     .04       0
Bank Sta=4946.7,5067.2
XS Rating Curve= 0 ,0
Exp/Cntr=0.3,0.1

Type RM Length L Ch R = 1 ,172348  ,752,752,752
BEGIN DESCRIPTION:
Mapping XS c995f295
END DESCRIPTION:
XS GIS Cut Line= 4
      2525337.73     13499684.73      2527073.84     13499153.05
      2528657.84     13497641.52      2528989.42     13495959.56
#Sta/Elev= 30
  3279.3  188.95    3458  186.55  3941.8  171.53  4149.3  167.29  4427.3  156.74
  4667.4  142.83  4751.1  142.18  4813.8  132.44  4875.2  129.42  4901.6  128.36
  4906.7  118.09  4908.2  116.09  5027.5  118.09  5032.7  121.65  5075.9  120.91
  5108.7   128.3  5144.9   130.1  5363.1  142.19  5511.6  154.22  5745.3  164.39
  6098.8  166.35    6502   161.1  7033.2   159.7  7172.8  160.03  7828.8  162.28
  7928.7  162.61  8281.4   163.9  8656.9  170.67  8992.3  171.14  8998.8  170.96
#Mann= 13 ,-1 , 0
  3279.3     .05       0    3458     .04       0  3941.8    .013       0
  4149.3     .12       0  4875.2      .1       0  4906.7     .05       0
  5027.5      .1       0  5144.9     .12       0  7033.2     .05       0
  7172.8     .04       0  7828.8    .013       0  7928.7     .05       0
  8992.3    .013       0
Bank Sta=4906.7,5027.5
XS Rating Curve= 0 ,0
Exp/Cntr=0.3,0.1

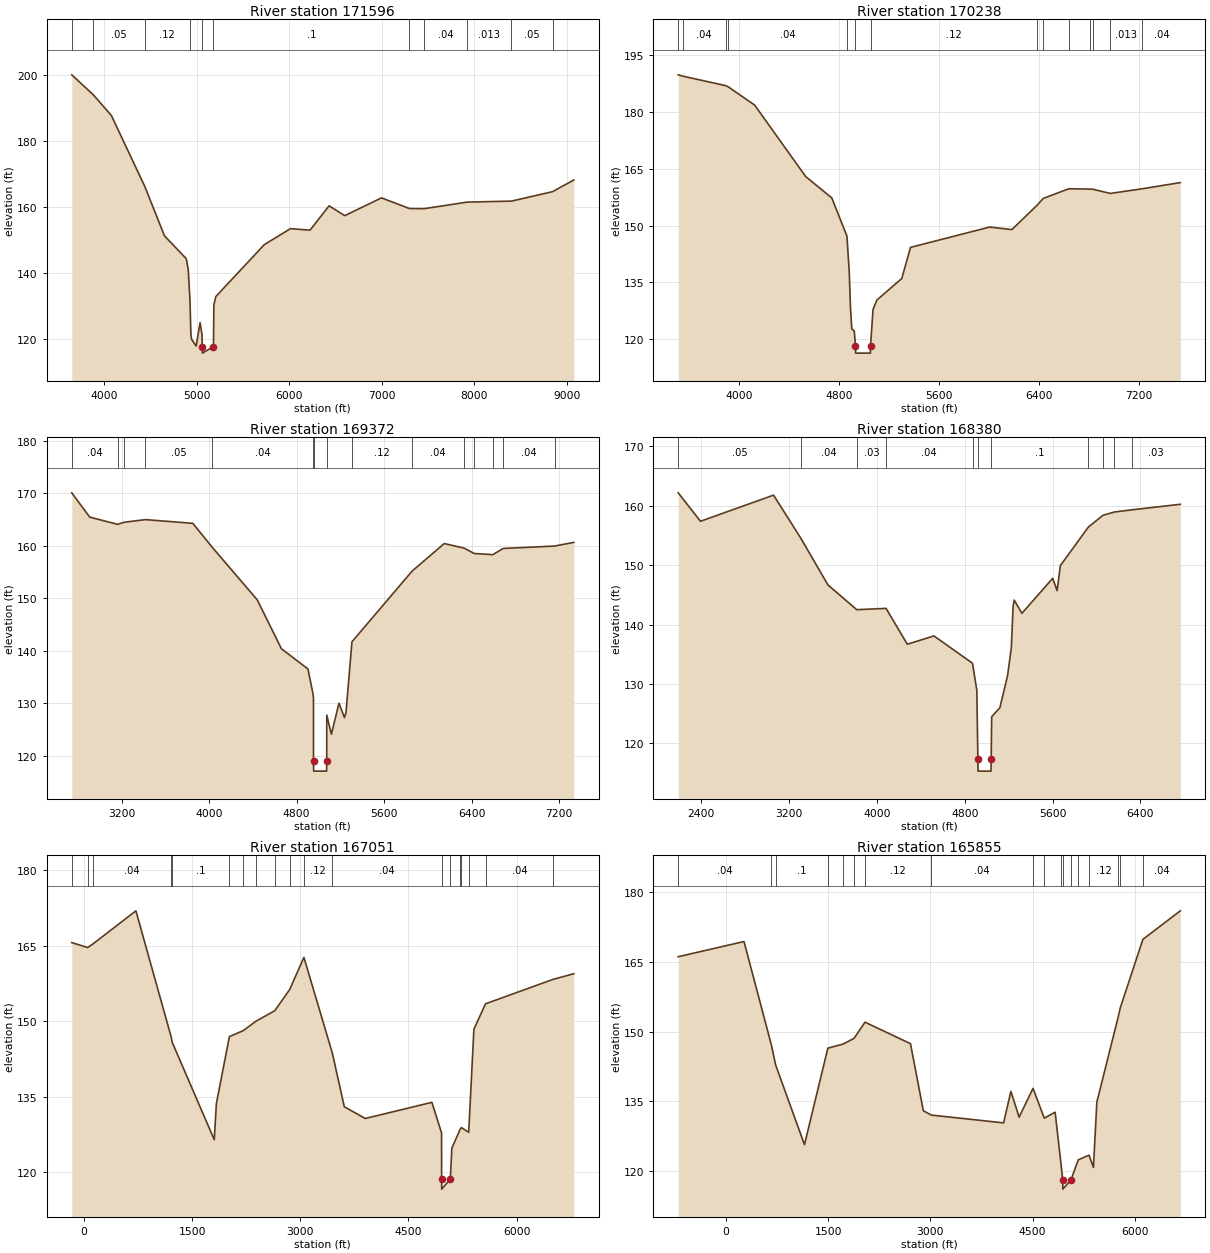
Type RM Length L Ch R = 1 ,171596  ,1358,1358,1358
BEGIN DESCRIPTION:
Mapping XS 56232aeb
END DESCRIPTION:
XS GIS Cut Line= 4
      2526639.97     13501063.29      2527052.14     13499966.85
      2528620.78     13498217.53      2529024.23     13496352.65
#Sta/Elev= 30
    3648  200.09  3882.8  193.98  4076.6  187.74  4437.4  166.22  4650.4  151.23
  4886.7  144.25  4907.6   140.9  4925.9  131.82    4936  121.64  4942.7  119.86
  4992.8  117.76  5035.4  124.87  5056.3  121.21  5059.5  117.62    5061  115.62
  5180.3  117.62  5184.2  130.11  5205.1  132.77  5729.2  148.53  6012.5   153.4
  6224.8  152.95  6430.4  160.33  6600.1  157.35    6997  162.74  7299.2  159.51
  7455.5  159.45  7923.8  161.46  8402.2  161.76  8847.6  164.63    9077  168.18
#Mann= 11 ,-1 , 0
    3648     .12       0  3882.8     .05       0  4437.4     .12       0
  4925.9      .1       0  5059.5     .05       0  5180.3      .1       0
  7299.2     .05       0  7455.5     .04       0  7923.8    .013       0
  8402.2     .05       0  8847.6     .04       0
Bank Sta=5059.5,5180.3
XS Rating Curve= 0 ,0
Exp/Cntr=0.3,0.1

Type RM Length L Ch R = 1 ,170238  ,866,866,866
BEGIN DESCRIPTION:
Mapping XS 8c43c5b9
END DESCRIPTION:
XS GIS Cut Line= 4
      2527583.82      13501344.9      2528180.61     13500368.33
      2528202.31      13499120.5       2529200.3     13497840.47
#Sta/Elev= 30
  3513.2  189.86  3548.8  189.52    3894  186.99  3911.1  186.73    4124  181.88
  4532.7  162.97    4741  157.34  4862.5  147.25    4881  137.69    4891  128.27
  4901.1  122.73  4921.1  122.15  4930.7  118.31  4932.2  116.31    5050  116.31
  5051.5  118.31  5071.1  127.85  5101.1   130.3  5301.1  136.04  5371.1  144.26
  6003.7  149.62  6181.9  148.96  6383.5   155.4  6433.2  157.21  6637.4  159.75
  6803.2  159.66  6832.6   159.6  6969.1  158.51  7224.9  159.75  7528.8  161.38
#Mann= 14 ,-1 , 0
  3513.2     .05       0  3548.8     .04       0    3894     .05       0
  3911.1     .04       0  4862.5     .12       0  4930.7     .05       0
  5051.5     .12       0  6383.5     .05       0  6433.2     .12       0
  6637.4     .05       0  6803.2     .04       0  6832.6     .05       0
  6969.1    .013       0  7224.9     .04       0
Bank Sta=4930.7,5051.5
XS Rating Curve= 0 ,0
Exp/Cntr=0.3,0.1

Type RM Length L Ch R = 1 ,169372  ,992,992,992
BEGIN DESCRIPTION:
Mapping XS 41e6b46f
END DESCRIPTION:
XS GIS Cut Line= 4
      2528115.53     13501757.19      2529092.07     13500650.45
       2528842.5     13498979.44      2529547.78     13497742.49
#Sta/Elev= 30
  2744.2  170.08    2908  165.46  3163.1  164.08  3224.5  164.48  3417.4  164.98
  3850.8  164.27  4026.1  159.77  4440.2  149.69  4660.5   140.4  4903.1  136.55
  4947.9  131.96  4953.7  131.01  4953.9   119.1  4955.4   117.1  5073.3   117.1
  5074.8   119.1    5075  127.76  5117.4  124.12  5186.6  130.03  5236.8  127.29
  5250.8  128.24  5305.3  141.72  5854.7  155.17  6148.9  160.42  6331.5  159.55
  6422.4  158.53  6592.9  158.31  6687.5  159.49  7158.4  159.95  7333.6  160.65
#Mann= 15 ,-1 , 0
  2744.2     .04       0  3163.1     .05       0  3224.5     .04       0
  3417.4     .05       0  4026.1     .04       0  4947.9     .05       0
  4953.9     .05       0  5074.8     .05       0  5305.3     .12       0
  5854.7     .04       0  6331.5    .013       0  6422.4     .04       0
  6592.9    .013       0  6687.5     .04       0  7158.4     .03       0
Bank Sta=4953.9,5074.8
XS Rating Curve= 0 ,0
Exp/Cntr=0.3,0.1

Type RM Length L Ch R = 1 ,168380  ,1329,1329,1329
BEGIN DESCRIPTION:
Mapping XS 7856642f
END DESCRIPTION:
XS GIS Cut Line= 3
      2528377.23     13501753.58      2529884.17     13500086.21
       2529753.4     13497764.64
#Sta/Elev= 30
  2190.2  162.19  2392.7   157.4  3058.5   161.8  3307.1  154.53    3554  146.67
  3816.4  142.51  4082.9  142.73  4276.5  136.69    4519  138.09  4870.3  133.49
  4909.6  128.93  4919.3  117.32  4920.8  115.32  5038.7  115.32  5040.2  117.32
    5045  124.48  5119.9  126.01    5190  131.45  5224.1  136.14  5240.1  143.12
  5250.1  144.12  5320.3   141.9  5600.7  147.79  5640.8  145.73  5670.8  149.94
  5925.8  156.43    6059  158.41  6162.7  158.96  6318.6  159.32  6762.9  160.26
#Mann= 11 ,-1 , 0
  2190.2     .05       0  3307.1     .04       0  3816.4     .03       0
  4082.9     .04       0  4870.3     .12       0  4919.3     .05       0
  5040.2      .1       0  5925.8     .05       0    6059     .03       0
  6162.7     .05       0  6318.6     .03       0
Bank Sta=4919.3,5040.2
XS Rating Curve= 0 ,0
Exp/Cntr=0.3,0.1

Type RM Length L Ch R = 1 ,167051  ,1196,1196,1196
BEGIN DESCRIPTION:
Mapping XS a657b567
END DESCRIPTION:
XS GIS Cut Line= 5
      2529223.92     13503725.27      2530910.78     13501675.52
       2531088.6     13499489.42      2530942.64     13498742.67
      2530057.91     13497719.17
#Sta/Elev= 30
  -167.9  165.65    52.3  164.66   122.7  165.34   721.3  171.97  1208.7  146.97
  1226.3  145.75  1808.1   126.4  1836.8  133.57  2017.6  146.92  2210.3  148.13
  2388.5  150.02  2648.3   152.1  2853.5   156.3  3050.9  162.71  3445.7  143.62
  3610.9  132.97  3901.9  130.63  4825.6  133.85  4959.7  127.75  4960.3  118.57
  4961.8  116.57  5081.2  118.57  5102.3  124.72  5216.2  128.46    5235  128.82
    5336  127.88    5408   148.4  5569.4  153.46  6506.7  158.33  6793.8  159.45
#Mann= 19 ,-1 , 0
  -167.9     .04       0    52.3     .05       0   122.7     .04       0
  1208.7     .05       0  1226.3      .1       0  2017.6     .12       0
  2210.3     .05       0  2388.5      .1       0  2648.3     .12       0
  2853.5     .05       0  3050.9     .12       0  3445.7     .04       0
  4960.3     .04       0  5081.2     .04       0  5216.2     .05       0
    5235     .12       0    5336     .05       0  5569.4     .04       0
  6506.7     .05       0
Bank Sta=4960.3,5081.2
XS Rating Curve= 0 ,0
Exp/Cntr=0.3,0.1

Type RM Length L Ch R = 1 ,165855  ,1475,1475,1475
BEGIN DESCRIPTION:
Mapping XS 53800766
END DESCRIPTION:
XS GIS Cut Line= 4
      2529275.95     13503794.79      2530944.04     13501754.16
      2532130.26     13499728.14      2532000.05     13497340.98
#Sta/Elev= 30
  -703.4  166.16   262.7  169.43   664.1  147.16   726.8  142.85  1150.7  125.65
  1494.2  146.45    1719  147.34    1879  148.57  2039.7  152.05  2707.7  147.42
  2896.5  132.97  3013.3  132.03  4075.1  130.35  4182.8  137.13  4303.2  131.58
  4507.3  137.79    4673  131.37  4832.3  132.65  4918.1   121.5  4943.6  118.07
  4945.1  116.07  5064.9  118.07  5171.6  122.37    5330  123.39  5394.8  120.76
  5444.9  134.82  5758.4  153.17  5790.1  155.18  6121.2   169.9  6670.7  176.05
#Mann= 18 ,-1 , 0
  -703.4     .04       0   664.1     .05       0   726.8      .1       0
  1494.2     .12       0    1719     .05       0    1879      .1       0
  2039.7     .12       0  3013.3     .04       0  4507.3     .12       0
    4673     .04       0  4918.1     .12       0  4943.6     .05       0
  5064.9     .12       0  5171.6     .05       0    5330     .12       0
  5758.4     .05       0  5790.1     .12       0  6121.2     .04       0
Bank Sta=4943.6,5064.9
XS Rating Curve= 0 ,0
Exp/Cntr=0.3,0.1