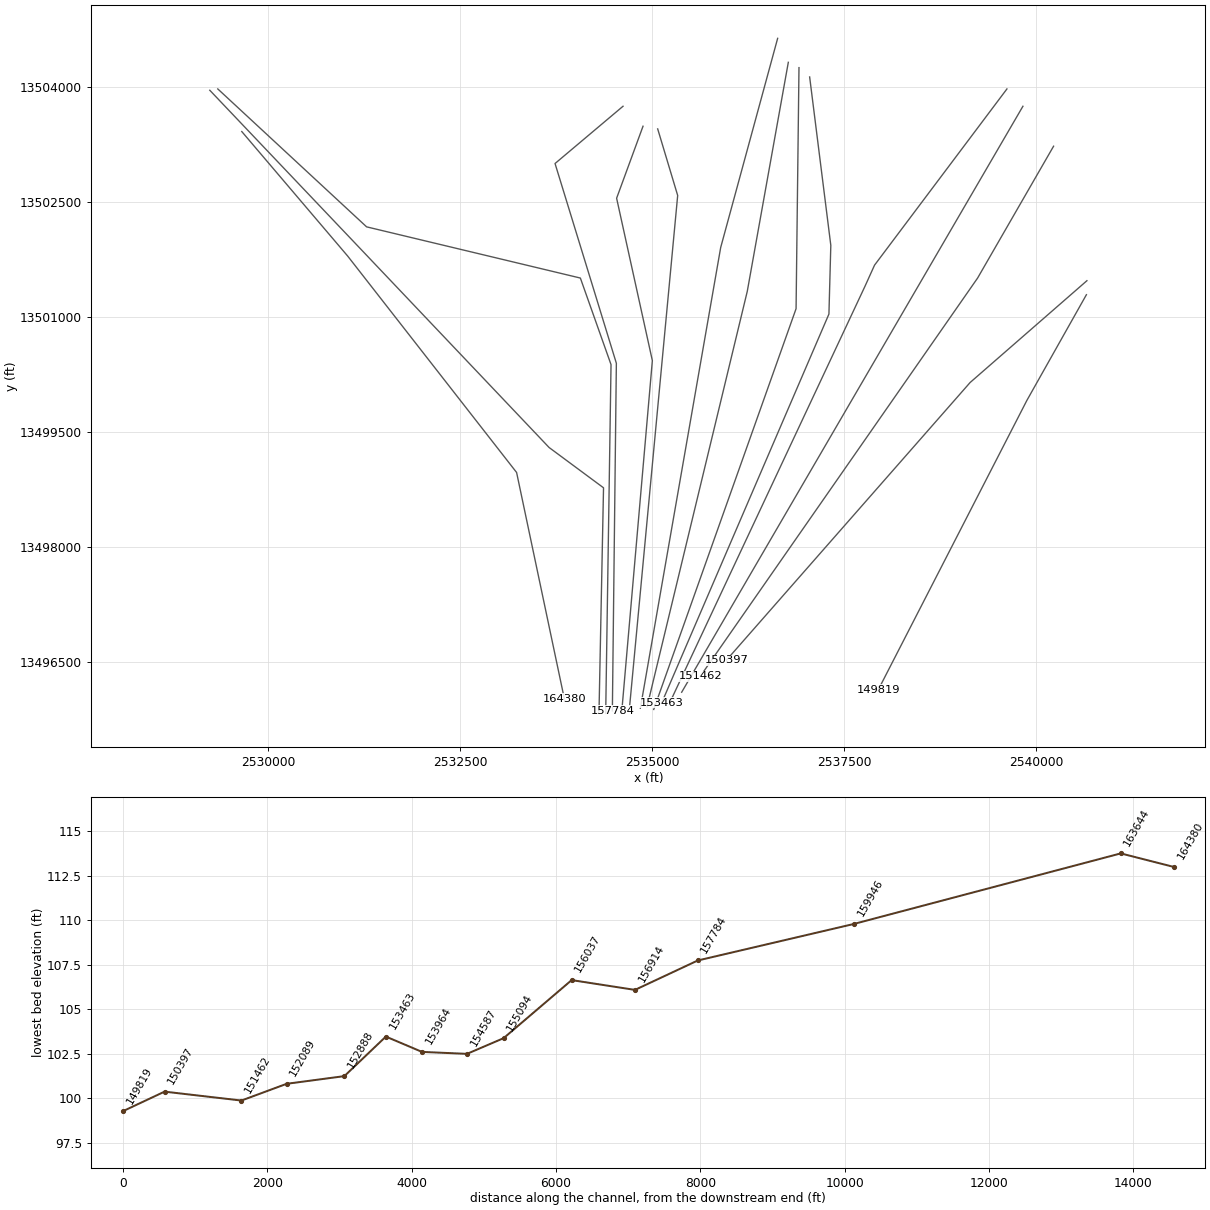
HEC-RAS study COLETO CREEK.prj: COLETO CREEK Base Level Engineering

--- COLETO CREEK.g01 (geometry) --- (continued)

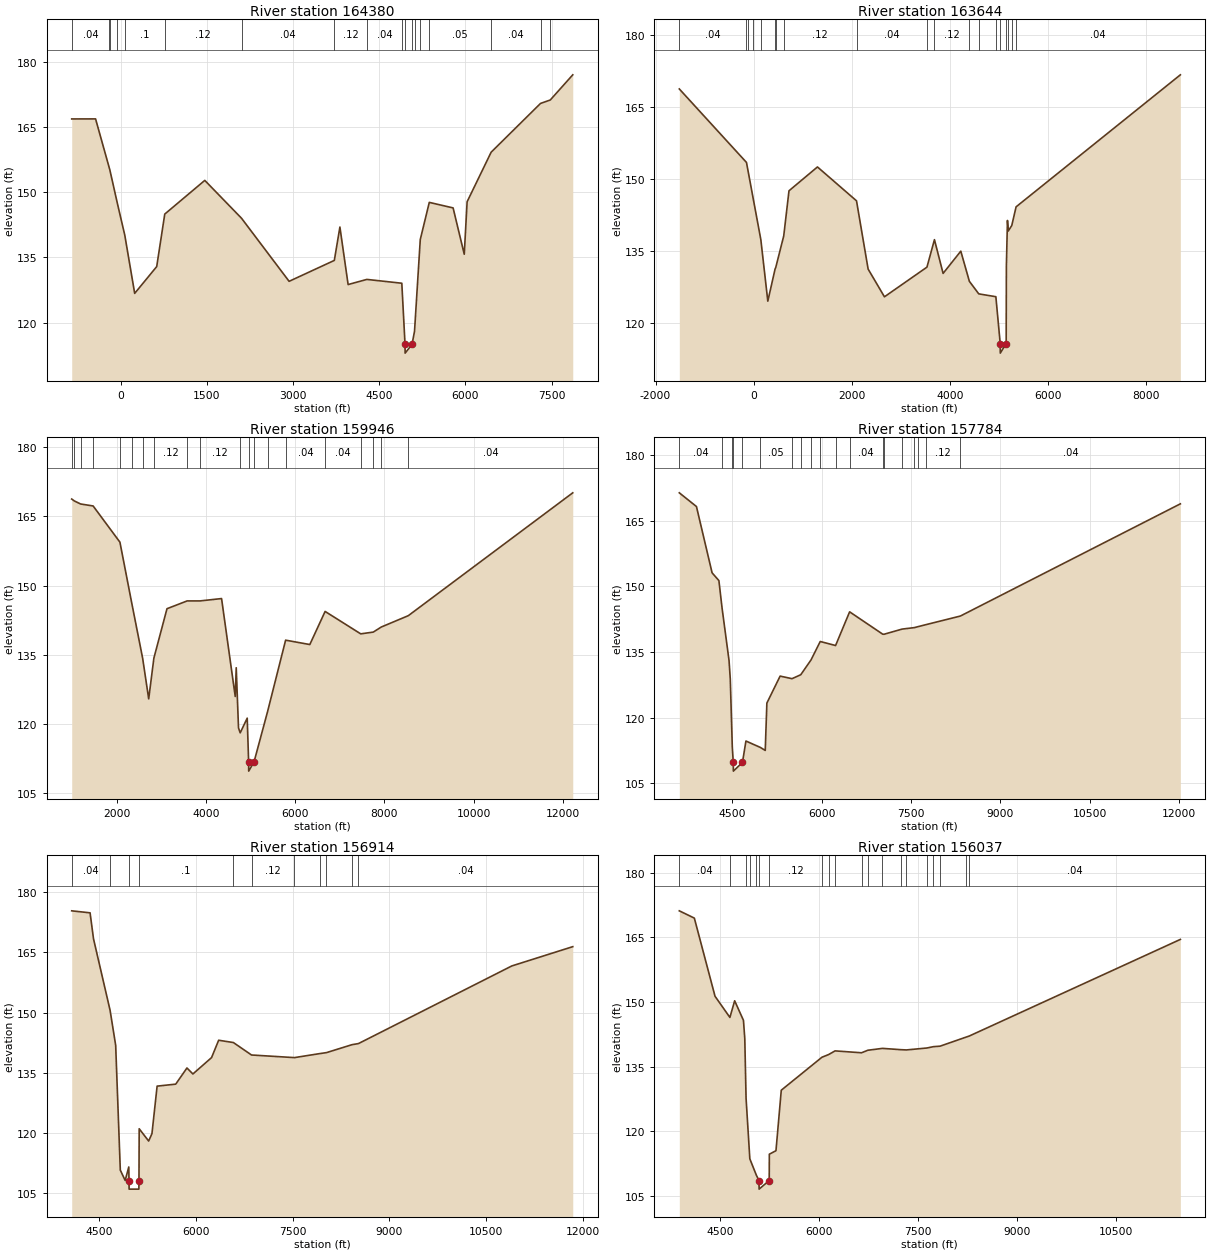
Type RM Length L Ch R = 1 ,164380  ,736,736,736
BEGIN DESCRIPTION:
Mapping XS ec9a932a
END DESCRIPTION:
XS GIS Cut Line= 4
       2529657.9     13503412.83      2531036.56     13501790.24
      2533237.03     13498968.59      2533858.99     13496018.48
#Sta/Elev= 30
  -853.9  166.86  -438.5  166.87  -200.6  155.63  -191.6  155.22   -57.2  147.33
    69.7  140.14   242.4  126.73   625.7  132.89   765.9  144.97  1462.8  152.72
  2102.3  144.01  2930.5   129.5  3717.7  134.31  3814.8  141.99  3957.7  128.76
    4284  129.94  4892.5  129.06  4948.7  114.98  4950.2  112.98    5070  114.98
  5113.8     118    5214  139.12    5371  147.66  5785.5  146.39  5979.6  135.73
  6029.4  147.81  6447.8  159.21  7307.4  170.43    7477  171.22  7868.5  177.01
#Mann= 18 ,-1 , 0
  -853.9     .04       0  -200.6     .05       0  -191.6     .04       0
   -57.2     .05       0    69.7      .1       0   765.9     .12       0
  2102.3     .04       0  3717.7     .12       0    4284     .04       0
  4892.5      .1       0  4948.7     .05       0    5070      .1       0
  5113.8     .05       0    5214     .12       0    5371     .05       0
  6447.8     .04       0  7307.4     .05       0    7477     .04       0
Bank Sta=4948.7,5070
XS Rating Curve= 0 ,0
Exp/Cntr=0.3,0.1

Type RM Length L Ch R = 1 ,163644  ,3698,3698,3698
BEGIN DESCRIPTION:
Mapping XS faff94a7
END DESCRIPTION:
XS GIS Cut Line= 5
      2529241.24     13503951.02      2531127.22     13501964.88
      2533660.21     13499294.11       2534369.2      13498768.7
      2534310.69     13495860.76
#Sta/Elev= 30
 -1515.1  168.71  -146.5  153.42  -122.8  152.12   -22.4  146.61   146.3  137.35
   288.4  124.55   436.8  131.26   450.1  131.56   612.8  138.13   719.9  147.52
    1300  152.48    2096  145.43  2332.7  131.23  2665.2  125.46  3531.4  131.63
  3684.2  137.35  3860.5  130.33  4221.3  134.96    4396  128.68  4587.4  126.07
  4935.7  125.48  5024.7  115.74  5026.2  113.74    5146  115.74  5150.1  131.87
  5172.1  141.35  5188.5  139.15  5260.1   140.3  5348.1  144.18  8695.7  171.65
#Mann= 19 ,-1 , 0
 -1515.1     .04       0  -146.5     .05       0  -122.8     .04       0
   -22.4     .05       0   146.3      .1       0   436.8     .12       0
   450.1      .1       0   612.8     .12       0    2096     .04       0
  3531.4     .05       0  3684.2     .12       0    4396     .03       0
  4587.4     .04       0  4935.7      .1       0  5024.7     .05       0
    5146      .1       0  5188.5     .12       0  5260.1     .05       0
  5348.1     .04       0
Bank Sta=5024.7,5146
XS Rating Curve= 0 ,0
Exp/Cntr=0.3,0.1

Type RM Length L Ch R = 1 ,159946  ,2162,2162,2162
BEGIN DESCRIPTION:
Mapping XS c17d95bb
END DESCRIPTION:
XS GIS Cut Line= 5
      2529345.44     13503968.34      2531283.39     13502170.56
      2534067.64     13501503.09      2534466.94     13500374.62
      2534397.53     13495828.04
#Sta/Elev= 30
   977.2  168.78    1036  168.37  1176.7  167.71  1458.1  167.28  2059.8  159.43
  2328.2  146.07    2570  134.25    2706  125.45    2822  134.28  3116.4     145
  3568.7  146.69  3859.4  146.69  4342.1   147.2    4649  125.97  4671.2   132.2
  4722.6  119.14  4760.6  118.08    4918  121.27  4949.8  111.78  4951.3  109.78
  5071.2  111.78  5373.4  122.63  5780.3  138.18  6323.5  137.23  6667.2  144.41
  7466.3  139.55  7748.7  139.93  7928.2  141.03  8535.3  143.49 12227.9  170.13
#Mann= 20 ,-1 , 0
   977.2    .013       0    1036    .013       0  1176.7    .013       0
  1458.1     .04       0  2059.8     .05       0  2328.2      .1       0
    2570      .1       0    2822     .12       0  3568.7     .12       0
  3859.4     .12       0  4760.6     .05       0  4949.8     .05       0
  5071.2     .05       0  5373.4     .05       0  5780.3     .04       0
  6667.2     .04       0  7466.3     .12       0  7748.7     .05       0
  7928.2     .12       0  8535.3     .04       0
Bank Sta=4949.8,5071.2
XS Rating Curve= 0 ,0
Exp/Cntr=0.3,0.1

Type RM Length L Ch R = 1 ,157784  ,870,870,870
BEGIN DESCRIPTION:
COLETO CREEK 35
END DESCRIPTION:
XS GIS Cut Line= 4
      2534623.19     13503742.68      2533737.77     13502996.15
      2534536.39     13500391.98       2534484.3     13495860.68
#Sta/Elev= 30
  3610.4  171.43  3898.1  168.29  4160.7  153.12  4275.1  151.34  4328.3  145.05
  4445.2  133.06  4466.3  128.78  4500.1  113.22  4516.6  109.73  4518.1  107.73
  4670.9  109.73    4729  114.62  4973.3  113.14  5053.2  112.47  5080.7  123.31
  5303.2  129.48  5502.6  128.89  5649.3  129.79  5822.1  133.18  5976.8   137.4
  6234.4  136.48  6470.3  144.19  7025.5  139.08    7049  139.06  7351.6  140.24
  7557.9  140.58  7622.8  140.81  7755.1  141.27  8330.4  143.23   12024  168.91
#Mann= 19 ,-1 , 0
  3610.4     .04       0  4328.3     .12       0  4500.1     .05       0
  4516.6     .05       0  4670.9     .12       0  4973.3     .05       0
  5502.6     .12       0  5649.3     .05       0  5822.1     .12       0
  5976.8     .04       0  6234.4     .05       0  6470.3     .04       0
  7025.5     .05       0    7049     .12       0  7351.6     .05       0
  7557.9     .12       0  7622.8     .05       0  7755.1     .12       0
  8330.4     .04       0
Bank Sta=4516.6,4670.9
XS Rating Curve= 0 ,0
Exp/Cntr=0.3,0.1

Type RM Length L Ch R = 1 ,156914  ,877,877,877
BEGIN DESCRIPTION:
COLETO CREEK 44
END DESCRIPTION:
XS GIS Cut Line= 4
      2534883.62      13503482.3      2534539.68     13502543.55
      2535005.14      13500426.7      2534605.83     13495843.35
#Sta/Elev= 30
  4074.7  175.34  4359.4  174.84  4412.6  168.37  4669.9  150.56  4756.3  141.86
    4828  110.81  4903.5  108.25  4959.2  111.59  4962.9  108.08  4964.4  106.08
  5115.8  106.08  5117.3  108.08  5120.8   121.1  5267.5  118.05  5318.7  119.89
  5398.7  131.71  5687.3  132.21  5861.4  136.23  5953.5  134.74  6242.7  138.81
  6352.8  143.13  6581.2  142.56  6862.4  139.46  7527.8  138.81  7924.7  139.82
  8023.9  140.05  8420.8  142.03    8520   142.3 10897.4  161.62 11842.6  166.42
#Mann= 11 ,-1 , 0
  4074.7     .04       0  4669.9      .1       0  4962.9     .05       0
  5117.3      .1       0  6581.2     .05       0  6862.4     .12       0
  7527.8      .1       0  7924.7     .12       0  8023.9     .04       0
  8420.8     .05       0    8520     .04       0
Bank Sta=4962.9,5117.3
XS Rating Curve= 0 ,0
Exp/Cntr=0.3,0.1

Type RM Length L Ch R = 1 ,156037  ,943,943,943
BEGIN DESCRIPTION:
COLETO CREEK 36
END DESCRIPTION:
XS GIS Cut Line= 3
      2535074.58     13503447.53        2535335.     13502579.48
        2534710.     13495930.16
#Sta/Elev= 30
  3888.7  171.17  4116.1  169.48  4429.3  151.36  4654.3  146.45  4726.6  150.31
  4859.7  145.77  4879.8  141.55  4899.2  127.72  4956.1  113.66  5055.3  109.85
  5095.3  108.63  5096.8  106.63  5249.7  108.63  5251.5  114.73  5351.9  115.54
  5432.2  129.57  6048.3  137.22  6147.6  137.83  6246.9  138.69  6646.9  138.25
  6743.3  138.84  6964.4  139.27  7242.4  138.97  7326.6  138.91    7637  139.36
  7736.3  139.67  7835.6  139.78  8232.8   141.9  8277.3  142.13 11473.6  164.54
#Mann= 20 ,-1 , 0
  3888.7     .04       0  4654.3     .12       0  4899.2     .05       0
  4956.1      .1       0  5055.3     .12       0  5095.3     .05       0
  5249.7     .12       0  6048.3     .05       0  6147.6     .12       0
  6246.9     .05       0  6646.9      .1       0  6743.3     .05       0
  6964.4     .12       0  7242.4     .12       0  7326.6      .1       0
    7637     .04       0  7736.3     .12       0  7835.6     .04       0
  8232.8     .05       0  8277.3     .04       0
Bank Sta=5095.3,5249.7
XS Rating Curve= 0 ,0
Exp/Cntr=0.3,0.1

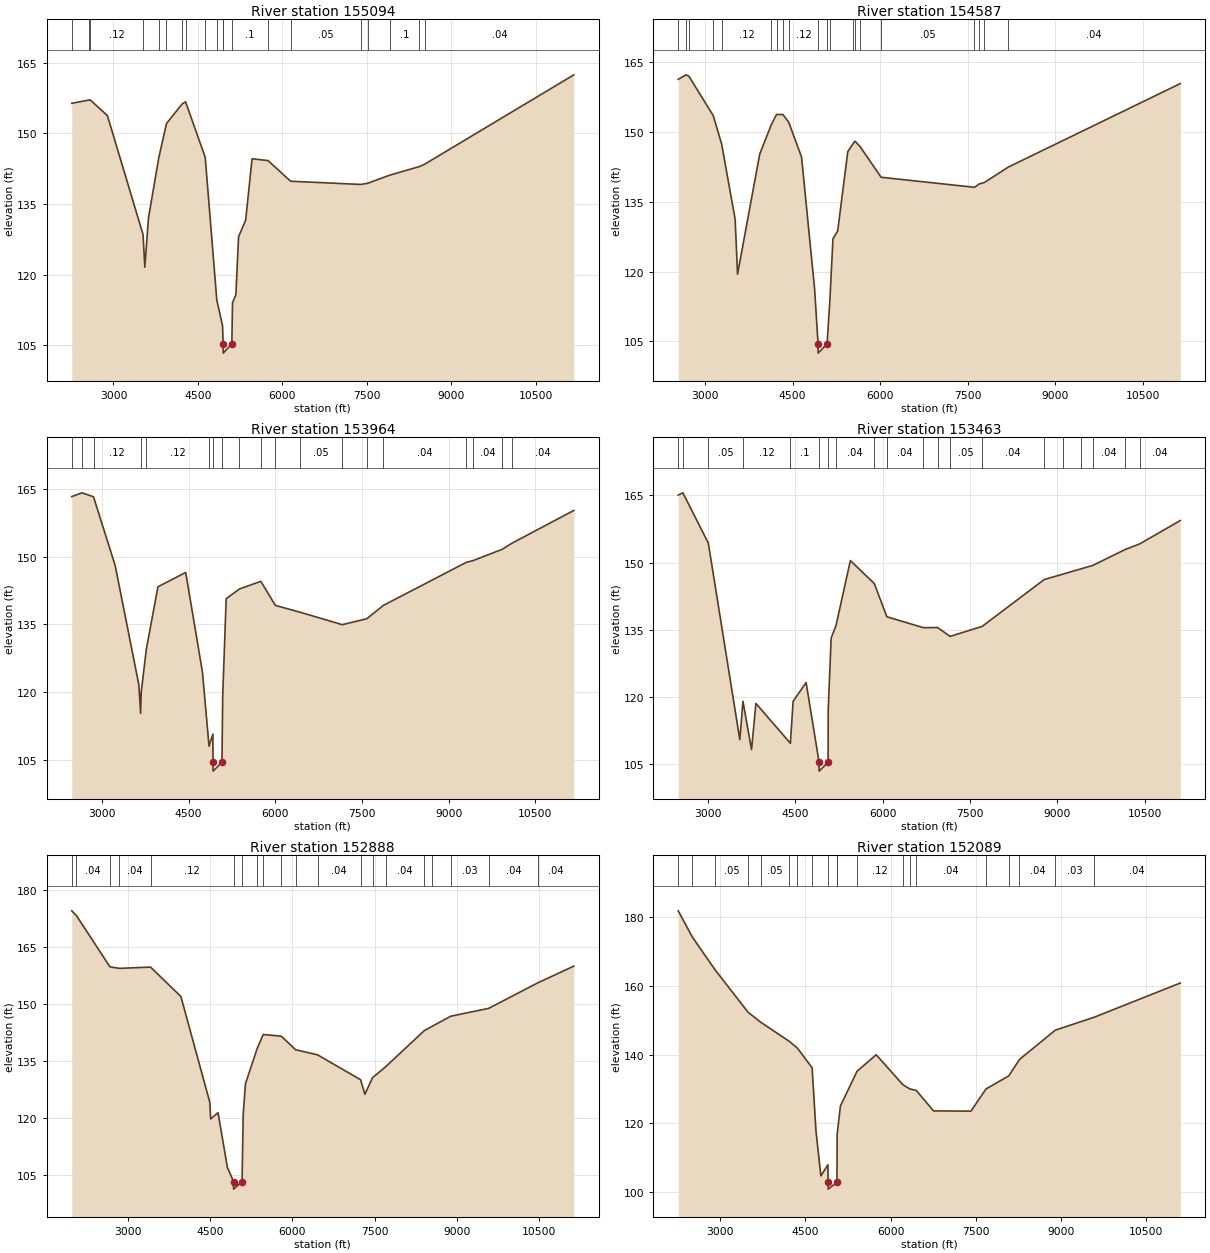
Type RM Length L Ch R = 1 ,155094  ,507,507,507
BEGIN DESCRIPTION:
COLETO CREEK 37
END DESCRIPTION:
XS GIS Cut Line= 3
      2536637.07     13504628.05      2535895.08     13501901.16
      2534848.88     13495895.44
#Sta/Elev= 30
  2258.7  156.36  2570.5  157.06  2583.7   157.1  2891.9  153.76  3525.4  128.51
  3557.3  121.59  3621.7  132.02  3806.1  144.87  3941.6  152.06    4218  156.19
  4281.1  156.68  4629.9  144.92  4835.8  114.67  4938.8  109.11  4948.6  105.37
  4950.1  103.37    5103  105.37  5115.4  114.05  5174.9  115.73  5222.9  128.07
  5348.6  131.56  5462.7   144.6  5746.8  144.21  6147.5  139.83  7392.6  139.15
    7518   139.4  7917.8  141.15  8434.4  142.93  8534.1  143.47 11180.9   162.4
#Mann= 20 ,-1 , 0
  2258.7     .05       0  2570.5    .013       0  2583.7     .12       0
  3525.4    .013       0  3806.1     .12       0  3941.6     .05       0
    4218    .013       0  4281.1     .05       0  4629.9     .12       0
  4835.8     .05       0  4938.8      .1       0  4948.6     .05       0
    5103      .1       0  5746.8     .04       0  6147.5     .05       0
  7392.6     .12       0    7518     .05       0  7917.8      .1       0
  8434.4     .05       0  8534.1     .04       0
Bank Sta=4948.6,5103
XS Rating Curve= 0 ,0
Exp/Cntr=0.3,0.1

Type RM Length L Ch R = 1 ,154587  ,623,623,623
BEGIN DESCRIPTION:
COLETO CREEK 38
END DESCRIPTION:
XS GIS Cut Line= 3
      2536775.98     13504315.63       2536241.2     13501328.87
       2534935.7     13495912.85
#Sta/Elev= 30
  2538.7  161.33  2674.4  162.29  2721.9  161.98  3138.7  153.53  3283.6  147.37
  3514.6   131.2  3555.2  119.44  3935.3  145.25  4132.2  151.52  4223.6  153.78
  4332.7  153.76  4433.3  152.09  4652.4  144.61  4875.9  116.31  4935.5  104.49
    4937  102.49    5090  104.49    5138  113.91  5190.8  127.06  5272.1  128.76
  5444.8  145.78  5540.7  147.58  5568.1  148.04  5653.8  146.91  6015.7  140.28
  7616.4  138.12  7701.5  138.86  7786.8  139.16  8195.2  142.46 11144.1  160.41
#Mann= 20 ,-1 , 0
  2538.7     .04       0  2674.4    .013       0  2721.9     .12       0
  3138.7    .013       0  3283.6     .12       0  4132.2     .03       0
  4223.6     .12       0  4332.7     .03       0  4433.3     .12       0
  4935.5     .05       0    5090     .12       0    5138     .12       0
  5540.7    .013       0  5568.1     .05       0  5653.8     .04       0
  6015.7     .05       0  7616.4     .12       0  7701.5     .05       0
  7786.8     .12       0  8195.2     .04       0
Bank Sta=4935.5,5090
XS Rating Curve= 0 ,0
Exp/Cntr=0.3,0.1

Type RM Length L Ch R = 1 ,153964  ,501,501,501
BEGIN DESCRIPTION:
COLETO CREEK 39
END DESCRIPTION:
XS GIS Cut Line= 3
      2536914.86      13504246.1      2536876.94     13501103.61
      2535022.85     13495879.07
#Sta/Elev= 30
  2480.1  163.24    2657  164.07  2856.1   163.2  3231.3     148  3641.3  121.64
  3671.2  115.36  3681.3  119.98  3769.8   129.5  3971.3  143.32  4451.3  146.48
  4741.4  124.45  4854.8  108.12  4921.4  110.79  4924.1   104.6  4925.6   102.6
  5078.6   104.6  5091.4  119.06  5151.4  140.68  5379.2  142.82  5751.1  144.52
  6002.1  139.21  6427.5  137.71    7160  134.95  7583.2  136.25  7871.9  139.21
  9308.5  148.73  9416.4  149.07  9922.7  151.57 10097.3  152.95 11166.6  160.18
#Mann= 19 ,-1 , 0
  2480.1     .04       0    2657    .013       0  2856.1     .12       0
  3671.2      .1       0  3769.8     .12       0  4854.8      .1       0
  4924.1     .05       0  5078.6      .1       0  5379.2     .04       0
  5751.1    .013       0  6002.1     .04       0  6427.5     .05       0
    7160     .12       0  7583.2     .05       0  7871.9     .04       0
  9308.5     .03       0  9416.4     .04       0  9922.7     .05       0
 10097.3     .04       0
Bank Sta=4924.1,5078.6
XS Rating Curve= 0 ,0
Exp/Cntr=0.3,0.1

Type RM Length L Ch R = 1 ,153463  ,575,575,575
BEGIN DESCRIPTION:
COLETO CREEK 40
END DESCRIPTION:
XS GIS Cut Line= 4
      2537053.75     13504124.61       2537329.4     13501929.13
      2537304.86     13501033.64      2535126.66     13495964.89
#Sta/Elev= 30
  2489.7  165.05  2569.3  165.55  3006.3  154.35  3547.6   110.5  3601.9  119.04
  3749.1  108.26  3824.5  118.57  4416.5  109.67  4463.1  119.03  4686.4  123.23
  4909.4  105.46  4910.9  103.46  5063.9  105.46  5066.7  117.18  5116.7  133.15
  5200.6  135.94  5446.8  150.43    5857  145.33  6074.3   137.9  6702.7  135.46
    6944   135.5  7160.6  133.52  7712.6  135.76  8776.7   146.2  9108.3  147.45
  9401.2  148.56  9610.8  149.35 10169.5  152.91 10416.6  154.15 11115.2  159.37
#Mann= 20 ,-1 , 0
  2489.7    .013       0  2569.3     .12       0  3006.3     .05       0
  3601.9     .12       0  4416.5      .1       0  4909.4     .05       0
  5063.9      .1       0  5200.6     .04       0    5857     .12       0
  6074.3     .04       0  6702.7    .013       0    6944     .12       0
  7160.6     .05       0  7712.6     .04       0  8776.7     .03       0
  9108.3     .04       0  9401.2     .03       0  9610.8     .04       0
 10169.5     .05       0 10416.6     .04       0
Bank Sta=4909.4,5063.9
XS Rating Curve= 0 ,0
Exp/Cntr=0.3,0.1

Type RM Length L Ch R = 1 ,152888  ,799,799,799
BEGIN DESCRIPTION:
COLETO CREEK 41
END DESCRIPTION:
XS GIS Cut Line= 4
      2539623.21     13503968.39      2537899.02      13501671.3
      2537774.11     13501395.06      2535230.83      13495964.9
#Sta/Elev= 30
  1969.1  174.58  2054.9  173.32  2666.5  159.82  2840.3  159.42    3408  159.75
  3962.2  152.01  4491.3  124.09  4505.9  119.74  4641.3  121.39  4812.1  106.95
    4924  103.24  4925.5  101.24  5079.7  103.24  5100.5  120.79  5141.7  128.99
  5355.6  138.28    5466  141.99  5796.9  141.54  6057.9  137.98  6458.9  136.63
  7244.2  130.08  7324.3  126.24  7462.9  130.61  7702.2  133.48  8406.9  142.99
  8555.2  144.16  8891.6  146.81  9585.5  148.88 10490.5  155.66 11140.7  160.01
#Mann= 20 ,-1 , 0
  1969.1     .05       0  2054.9     .04       0  2666.5     .12       0
  2840.3     .04       0    3408     .12       0    4924     .05       0
  5079.7      .1       0  5355.6     .05       0    5466     .12       0
  5796.9     .05       0  6057.9     .04       0  6458.9     .04       0
  7244.2    .013       0  7462.9     .12       0  7702.2     .04       0
  8406.9     .05       0  8555.2     .03       0  8891.6     .03       0
  9585.5     .04       0 10490.5     .04       0
Bank Sta=4924,5079.7
XS Rating Curve= 0 ,0
Exp/Cntr=0.3,0.1

Type RM Length L Ch R = 1 ,152089  ,627,627,627
BEGIN DESCRIPTION:
COLETO CREEK 42
END DESCRIPTION:
XS GIS Cut Line= 2
      2539831.51     13503742.65      2535387.09      13496103.8
#Sta/Elev= 30
  2260.3  181.85  2508.2  174.24  2908.6  164.68    3490  152.32  3715.6  149.38
  4209.2  143.92  4359.2  141.86  4616.9  136.15  4685.3  117.67  4771.4  104.66
  4895.4   107.9  4898.5  102.81    4900  100.81  5054.2  102.81  5057.4  116.78
  5059.5  117.03  5115.2  125.02  5407.4  135.13  5744.5  139.94  6213.9  131.24
  6335.1     130  6451.1  129.53  6754.8  123.59  7412.6  123.52  7678.1  129.99
  8078.9  133.79  8265.4  138.54  8896.9   147.1  9583.2  150.87   11098  160.83
#Mann= 20 ,-1 , 0
  2260.3     .12       0  2508.2     .03       0  2908.6     .05       0
    3490     .12       0  3715.6     .05       0  4209.2     .05       0
  4359.2     .12       0  4616.9     .12       0  4898.5     .05       0
  5054.2      .1       0  5059.5     .12       0  5407.4     .12       0
  6213.9     .04       0  6335.1    .013       0  6451.1     .04       0
  7678.1     .05       0  8078.9    .013       0  8265.4     .04       0
  8896.9     .03       0  9583.2     .04       0
Bank Sta=4898.5,5054.2
XS Rating Curve= 0 ,0
Exp/Cntr=0.3,0.1

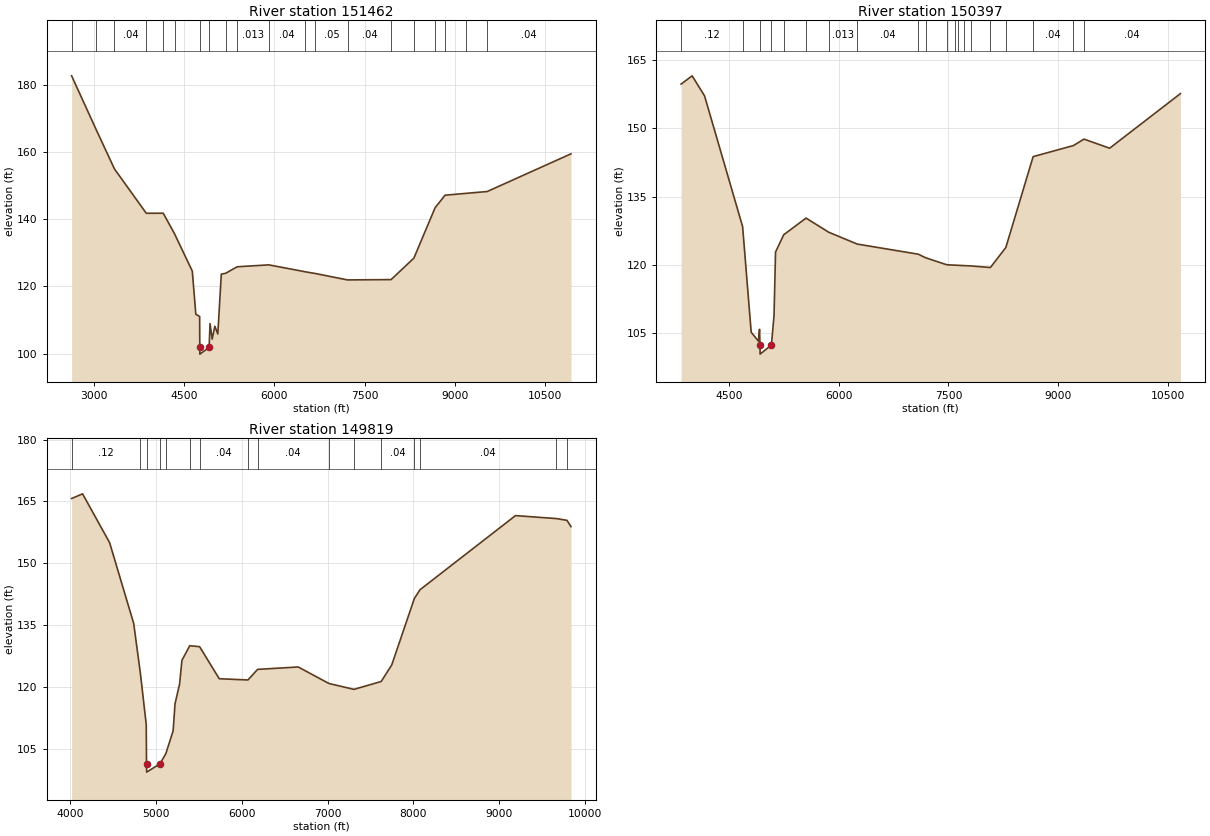
Type RM Length L Ch R = 1 ,151462  ,1065,1065,1065
BEGIN DESCRIPTION:
COLETO CREEK 43
END DESCRIPTION:
XS GIS Cut Line= 3
      2540230.82     13503221.83      2539241.25     13501503.09
      2535630.16     13496312.15
#Sta/Elev= 30
  2627.2  182.65  3031.1  166.82  3339.9  154.95  3869.4  141.77  4151.2  141.78
  4339.1  135.67  4634.4  124.56  4693.4  111.71  4756.6  111.07    4759  101.87
  4760.5   99.87  4914.7  101.87  4929.4  108.95  4965.2  104.35  5009.7  108.15
  5058.9  105.88  5117.1  123.67  5188.4  123.91  5381.2  125.85    5908  126.42
  6517.4  124.35  6678.1  123.86  7217.8  121.94  7941.8  122.04  8320.8  128.43
    8674  143.43  8839.5  147.14  9193.9   147.7  9540.8  148.24 10933.9  159.45
#Mann= 20 ,-1 , 0
  2627.2     .03       0  3031.1     .04       0  3339.9     .04       0
  3869.4      .1       0  4151.2     .12       0  4339.1     .12       0
    4759     .05       0  4914.7     .05       0  5188.4     .04       0
  5381.2    .013       0    5908     .04       0  6517.4     .04       0
  6678.1     .05       0  7217.8     .04       0  7941.8     .05       0
  8320.8     .05       0    8674    .013       0  8839.5     .04       0
  9193.9     .03       0  9540.8     .04       0
Bank Sta=4759,4914.7
XS Rating Curve= 0 ,0
Exp/Cntr=0.3,0.1

Type RM Length L Ch R = 1 ,150397  ,578,578,578
BEGIN DESCRIPTION:
COLETO CREEK 56
END DESCRIPTION:
XS GIS Cut Line= 3
      2540664.85     13501468.36      2539143.81      13500141.4
      2535970.87     13496522.64
#Sta/Elev= 30
  3842.4  159.76  3993.4  161.58  4163.3  157.17  4684.1  128.41  4801.3  105.18
    4901  103.22  4915.2  105.82  4921.8  102.37  4923.3  100.37  5077.6  102.37
  5113.6   108.8  5134.5  122.83  5246.6  126.63  5551.9  130.29  5862.2  127.18
    6251  124.58  7086.7  122.35  7186.9  121.57  7475.9  120.03    7583  119.94
  7636.5   119.9  7709.7  119.84  7802.8  119.77  8073.7  119.42  8284.9  123.82
  8658.5  143.81  9209.8  146.24  9354.3  147.66  9705.3  145.66 10673.7  157.67
#Mann= 20 ,-1 , 0
  3842.4     .12       0  4684.1      .1       0  4921.8     .05       0
  5077.6      .1       0  5246.6     .05       0  5551.9     .04       0
  5862.2    .013       0    6251     .04       0  7086.7     .05       0
  7186.9     .12       0  7475.9     .05       0    7583     .12       0
  7636.5     .05       0  7709.7     .12       0  7802.8     .05       0
  8073.7     .12       0  8284.9     .04       0  8658.5     .04       0
  9209.8    .013       0  9354.3     .04       0
Bank Sta=4921.8,5077.6
XS Rating Curve= 0 ,0
Exp/Cntr=0.3,0.1

Type RM Length L Ch R = 1 ,149819  ,1003,1003,1003
BEGIN DESCRIPTION:
COLETO CREEK 99
END DESCRIPTION:
XS GIS Cut Line= 3
      2540658.33     13501286.04      2539882.85      13499907.8
      2537945.66     13496131.97
#Sta/Elev= 30
  4014.3  165.72  4141.7  166.86  4457.3  155.01  4738.4  135.38  4817.4   123.1
  4884.8   110.8  4887.8  101.27  4889.3   99.27  5043.6  101.27  5113.1  103.74
  5198.4  109.31  5220.3  115.85  5273.6  120.66    5301  126.42  5392.1  129.97
  5507.1  129.74  5736.4  121.95  6071.2  121.65  6183.7  124.22  6657.2  124.81
  7015.7   120.8    7308  119.37  7625.5  121.28  7748.8  125.31  8012.3  141.44
  8078.4  143.57  9192.3  161.57  9669.3  160.85  9792.6  160.42  9839.5   158.9
#Mann= 16 ,-1 , 0
  4014.3     .12       0  4817.4      .1       0  4887.8     .05       0
  5043.6      .1       0  5113.1     .04       0  5392.1    .013       0
  5507.1     .04       0  6071.2    .013       0  6183.7     .04       0
  7015.7     .05       0    7308      .1       0  7625.5     .04       0
  8012.3     .05       0  8078.4     .04       0  9669.3    .013       0
  9792.6     .04       0
Bank Sta=4887.8,5043.6
XS Rating Curve= 0 ,0
Exp/Cntr=0.3,0.1