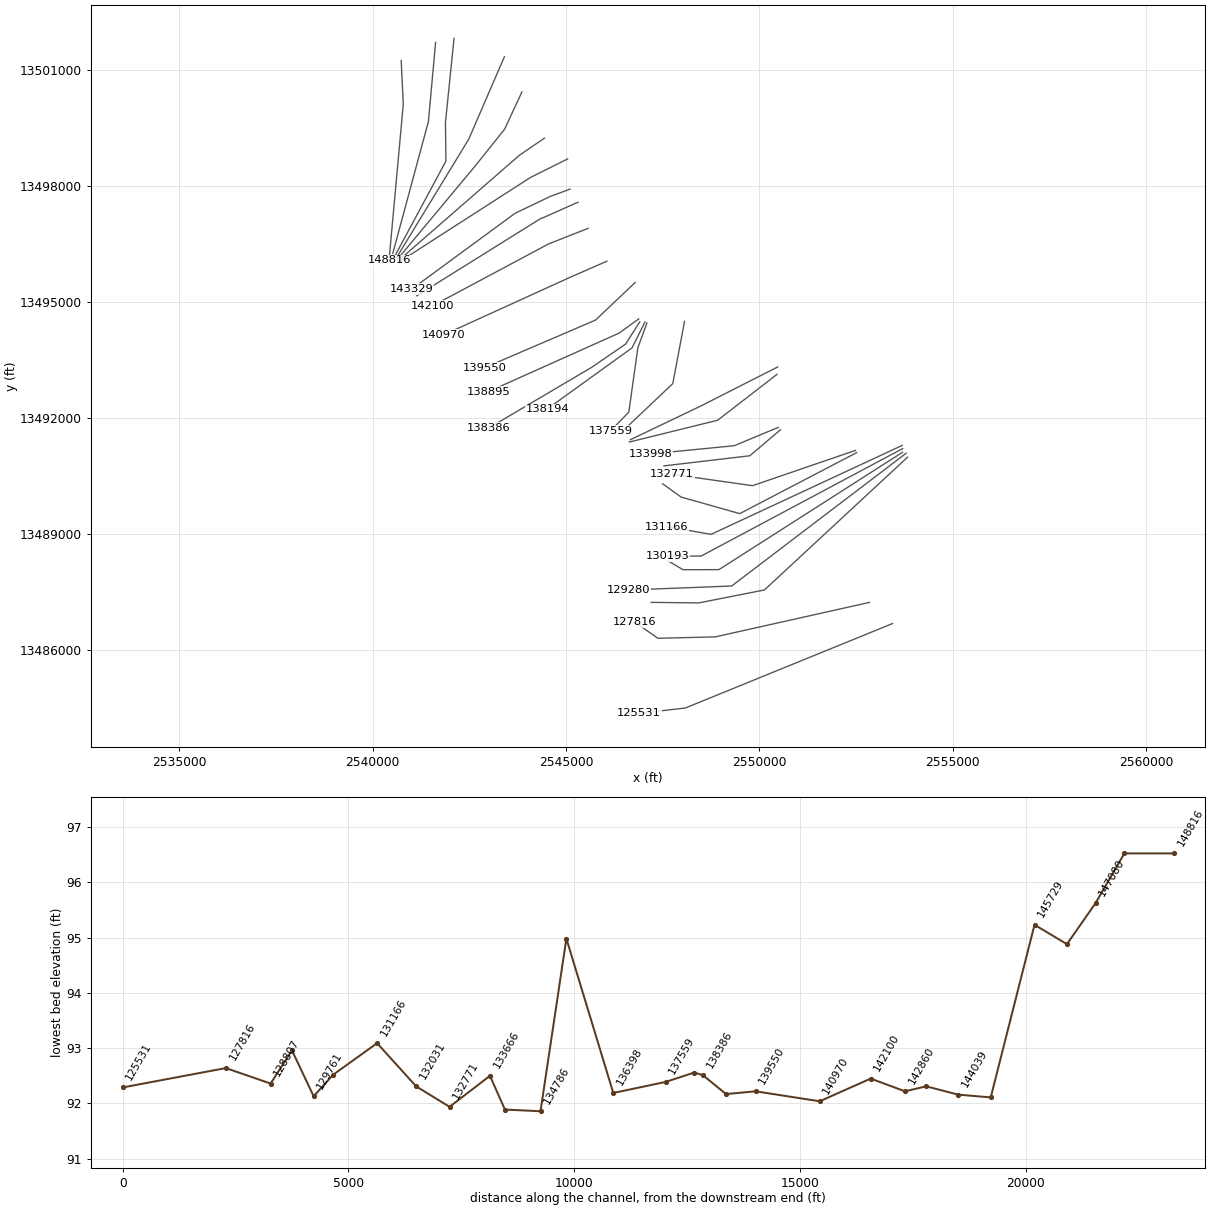
HEC-RAS study COLETO CREEK.prj: COLETO CREEK Base Level Engineering

--- COLETO CREEK.g01 (geometry) --- (continued)

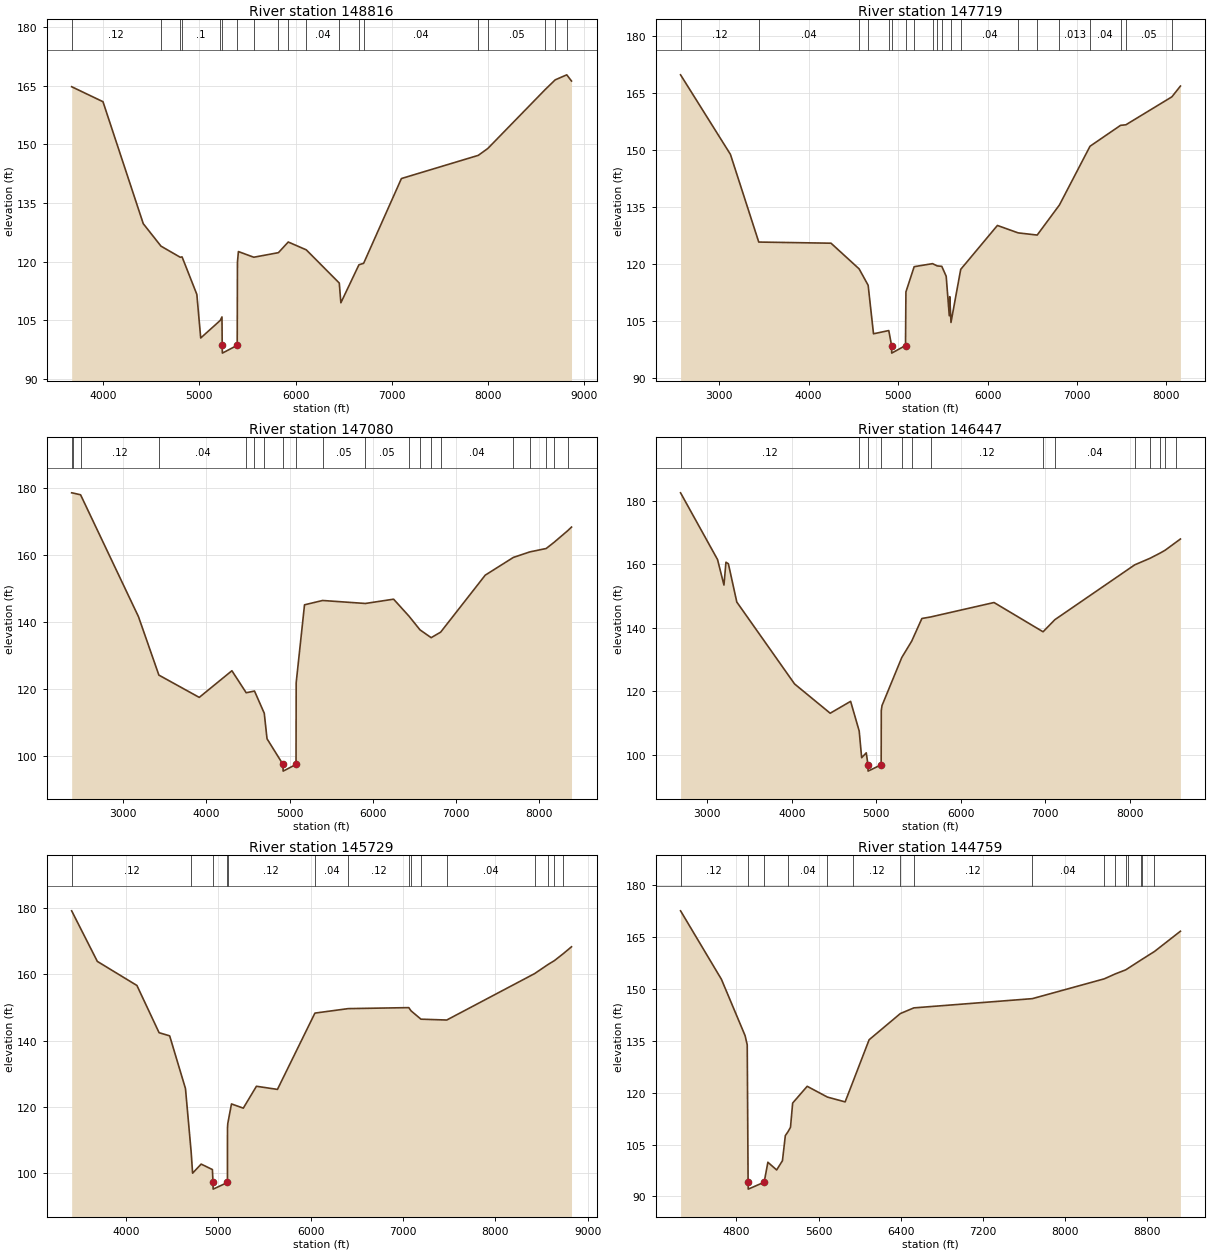
Type RM Length L Ch R = 1 ,148816  ,1097,1097,1097
BEGIN DESCRIPTION:
COLETO CREEK 55
END DESCRIPTION:
XS GIS Cut Line= 3
       2540734.3     13501253.52      2540788.56     13500125.05
      2540419.74      13496078.9
#Sta/Elev= 30
    3674   164.8  3999.4  160.96  4417.9   129.7    4602  123.94  4801.5   121.1
  4821.1  121.18  4974.5  111.57  5014.7   100.4  5217.6   104.9  5235.6   105.8
    5238   98.52  5239.5   96.52  5393.8   98.52  5396.3  119.81  5406.3  122.55
  5566.1   121.1    5822  122.27    5924     125  6111.5  122.99  6454.2  114.48
  6470.7  109.42  6658.6  119.17    6707  119.53  7099.8  141.27  7898.2  147.21
  7997.5  148.98    8593  164.07  8697.2  166.56  8817.3  167.85  8866.7  166.26
#Mann= 19 ,-1 , 0
    3674     .12       0    4602     .04       0  4801.5     .05       0
  4821.1      .1       0  5217.6     .12       0    5238     .05       0
  5393.8     .12       0  5566.1     .05       0    5822     .04       0
    5924     .03       0  6111.5     .04       0  6454.2      .1       0
  6658.6     .12       0    6707     .04       0  7898.2     .12       0
  7997.5     .05       0    8593     .12       0  8697.2    .013       0
  8817.3     .04       0
Bank Sta=5238,5393.8
XS Rating Curve= 0 ,0
Exp/Cntr=0.3,0.1

Type RM Length L Ch R = 1 ,147719  ,639,639,639
BEGIN DESCRIPTION:
COLETO CREEK 49
END DESCRIPTION:
XS GIS Cut Line= 3
      2541624.06     13501720.12       2541438.5     13499674.46
      2540517.28     13496262.19
#Sta/Elev= 30
  2568.4  169.76  3125.8  148.83  3442.6  125.75  4250.4  125.45  4564.8  118.69
  4665.6  114.37  4725.5  101.61  4896.2  102.46  4927.5   98.52    4929   96.52
  5083.3   98.52    5088  112.63  5180.1  119.27    5386  120.07  5437.4  119.47
  5488.9  119.36  5538.1  116.75  5572.8  106.35    5578  111.38  5591.8  104.59
  5700.5  118.56  6110.7  130.12  6342.1  128.17  6555.4  127.59  6804.3  135.51
    7146  150.96  7487.8  156.47  7547.1  156.61  8061.6  163.97  8156.9   166.8
#Mann= 20 ,-1 , 0
  2568.4     .12       0  3442.6     .04       0  4564.8     .05       0
  4665.6    .035       0  4896.2      .1       0  4927.5     .05       0
  5083.3      .1       0  5180.1     .04       0    5386      .1       0
  5437.4     .04       0  5488.9      .1       0  5591.8     .05       0
  5700.5     .04       0  6342.1     .12       0  6555.4     .04       0
  6804.3    .013       0    7146     .04       0  7487.8     .12       0
  7547.1     .05       0  8061.6     .12       0
Bank Sta=4927.5,5083.3
XS Rating Curve= 0 ,0
Exp/Cntr=0.3,0.1

Type RM Length L Ch R = 1 ,147080  ,633,633,633
BEGIN DESCRIPTION:
COLETO CREEK 50
END DESCRIPTION:
XS GIS Cut Line= 4
      2542101.49     13501828.62      2541878.77     13499647.77
      2541891.25     13498649.31      2540560.67     13496175.36
#Sta/Elev= 30
    2385  178.65  2401.1  178.59  2492.2  178.06  3187.4  141.68  3431.9  124.27
  3916.5  117.62  4308.6  125.57  4480.1     119  4579.5  119.52  4696.9  112.89
    4730  105.28  4921.9   97.62  4923.4   95.62  5078.1   97.62    5080  121.99
    5180  145.24  5397.1  146.53  5910.7  145.64  6249.4  146.92    6435  141.83
  6566.4  137.76  6700.3  135.44    6814  137.08    7349  154.08  7686.2  159.37
  7883.4  161.02  8080.7  162.04    8178  163.93  8338.9  167.35  8384.8  168.43
#Mann= 20 ,-1 , 0
    2385     .12       0  2401.1     .05       0  2492.2     .12       0
  3431.9     .04       0  4480.1     .12       0  4579.5     .05       0
  4696.9    .035       0  4921.9     .05       0  5078.1     .12       0
  5397.1     .05       0  5910.7     .05       0    6435     .04       0
  6566.4     .12       0  6700.3     .05       0    6814     .04       0
  7686.2    .013       0  7883.4     .04       0  8080.7     .05       0
    8178     .12       0  8338.9    .013       0
Bank Sta=4921.9,5078.1
XS Rating Curve= 0 ,0
Exp/Cntr=0.3,0.1

Type RM Length L Ch R = 1 ,146447  ,718,718,718
BEGIN DESCRIPTION:
COLETO CREEK 48
END DESCRIPTION:
XS GIS Cut Line= 3
      2543403.56     13501351.15      2542479.95     13499214.07
      2540614.94      13496153.7
#Sta/Elev= 30
  2685.3  182.46  3122.6  161.46  3198.5  153.44    3222  160.62  3250.9  160.13
  3350.4  148.09  4033.8  122.31  4455.1   113.1  4696.5  116.84  4797.9  107.51
  4827.2    99.1  4881.7  100.64  4901.6   96.88  4903.1   94.88  5057.8   96.88
  5059.2  113.95    5068  115.52  5301.6  130.63  5419.1  135.79  5539.3  142.91
  5645.8  143.41  6392.6  147.94  6972.6  138.73  7112.8  142.55  8056.3  159.79
  8236.9  161.85    8356  163.48  8417.5  164.41  8540.4  166.82  8597.3  167.93
#Mann= 14 ,-1 , 0
  2685.3     .12       0  4797.9      .1       0  4901.6     .05       0
  5057.8      .1       0  5301.6     .05       0  5419.1     .04       0
  5645.8     .12       0  6972.6     .05       0  7112.8     .04       0
  8056.3    .013       0  8236.9     .04       0    8356     .05       0
  8417.5     .12       0  8540.4    .013       0
Bank Sta=4901.6,5057.8
XS Rating Curve= 0 ,0
Exp/Cntr=0.3,0.1

Type RM Length L Ch R = 1 ,145729  ,970,970,970
BEGIN DESCRIPTION:
COLETO CREEK 47
END DESCRIPTION:
XS GIS Cut Line= 4
      2543857.13     13500441.88      2543408.88     13499475.84
      2542639.22     13498513.77      2540645.72     13496119.45
#Sta/Elev= 30
  3412.2  179.15  3690.2   163.9    4119  156.64    4359   142.4  4473.5  141.45
  4644.7  125.55  4706.2  106.43  4721.7  100.04  4814.6  102.78  4936.2  101.13
  4942.9   97.23  4944.4   95.23  5099.2   97.23  5099.5  113.61  5102.8     115
  5142.7  120.92  5270.8  119.65  5413.1  126.25  5640.6   125.3  6046.3  148.31
  6406.1  149.66  7063.1  149.96  7086.8     149  7194.4  146.48  7473.8  146.22
  8424.6  160.21  8573.2  163.01  8639.5  164.13  8733.8  166.19  8824.8  168.31
#Mann= 15 ,-1 , 0
  3412.2     .12       0  4706.2      .1       0  4942.9     .05       0
  5099.2      .1       0  5102.8     .12       0  6046.3     .04       0
  6406.1     .12       0  7063.1     .05       0  7086.8     .12       0
  7194.4     .05       0  7473.8     .04       0  8424.6    .013       0
  8573.2     .05       0  8639.5     .12       0  8733.8    .013       0
Bank Sta=4942.9,5099.2
XS Rating Curve= 0 ,0
Exp/Cntr=0.3,0.1

Type RM Length L Ch R = 1 ,144759  ,720,720,720
BEGIN DESCRIPTION:
COLETO CREEK 46
END DESCRIPTION:
XS GIS Cut Line= 3
      2544438.74     13499243.98      2543791.45     13498801.54
      2540715.35     13496119.48
#Sta/Elev= 30
    4257   172.6  4654.6   152.8  4884.8  136.52  4905.8  133.84  4914.3   94.11
  4915.8   92.11  5070.6   94.11  5106.8   99.88  5192.2   97.66  5248.6  100.33
  5276.7  107.59    5302  108.68    5327     110  5347.9     117  5489.4  121.85
  5686.6  118.73  5858.7  117.34  5931.6  122.92  6092.2  135.31  6396.1  142.89
  6527.7  144.53  7680.9   147.2  8380.8  152.93  8487.6  154.35  8590.5  155.54
    8615  156.01  8742.3  158.45  8745.5  158.51  8869.6  160.84  9122.2   166.7
#Mann= 16 ,-1 , 0
    4257     .12       0  4914.3     .03       0  5070.6     .12       0
    5302     .04       0  5686.6     .05       0  5931.6     .12       0
  6396.1     .04       0  6527.7     .12       0  7680.9     .04       0
  8380.8     .12       0  8487.6     .05       0  8590.5     .04       0
    8615     .05       0  8742.3     .04       0  8745.5     .05       0
  8869.6    .013       0
Bank Sta=4914.3,5070.6
XS Rating Curve= 0 ,0
Exp/Cntr=0.3,0.1

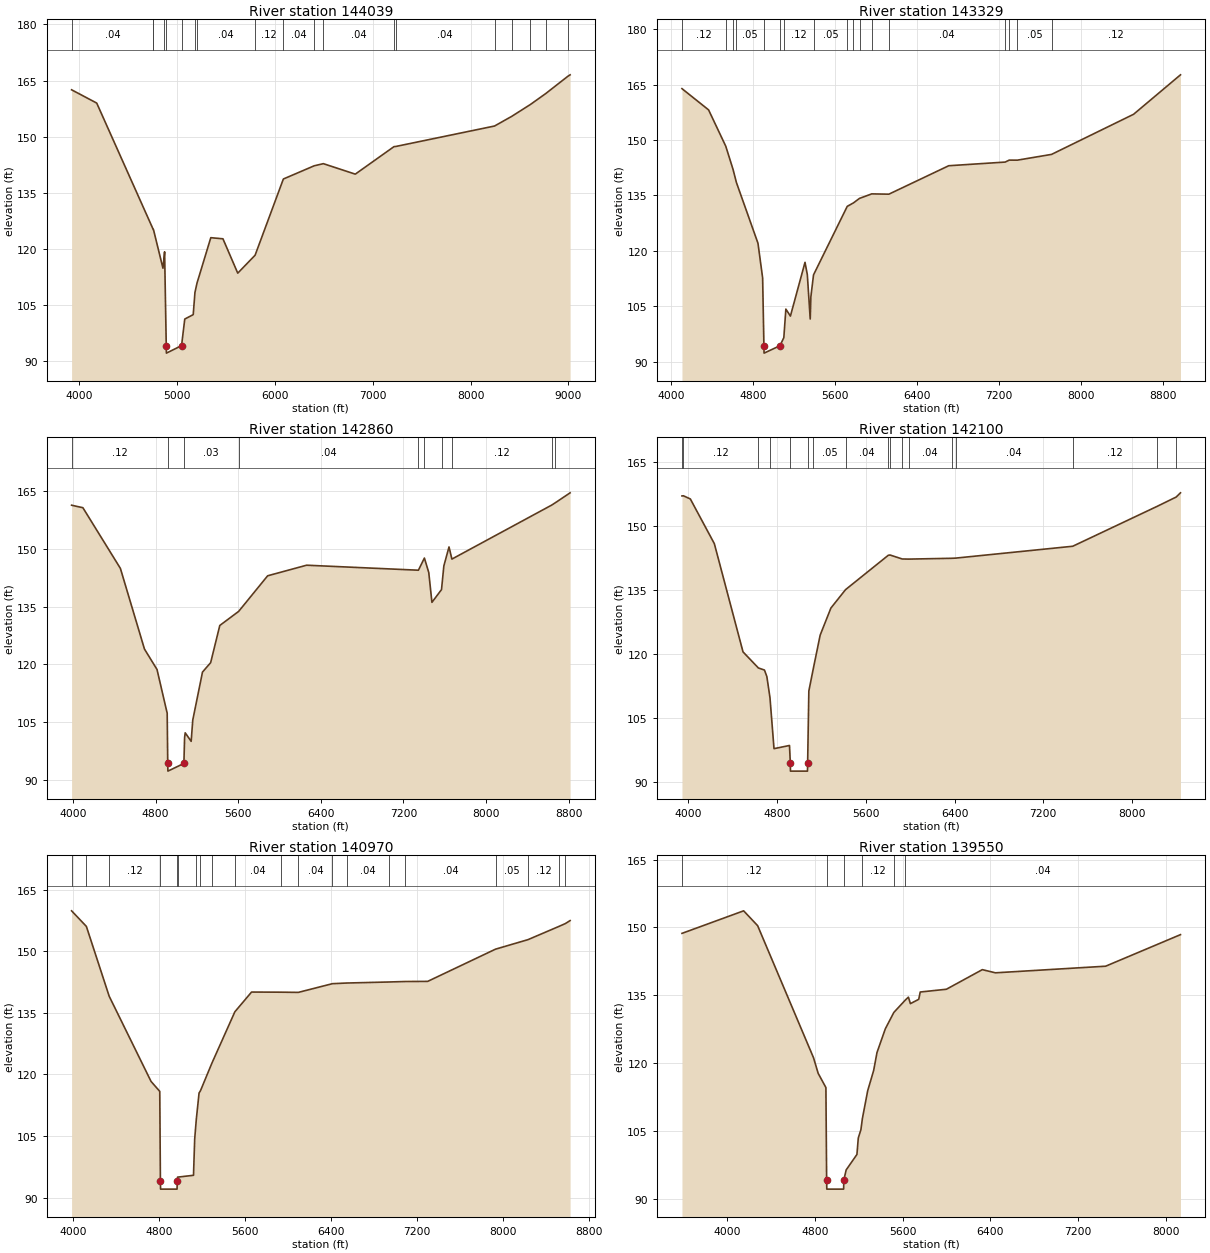
Type RM Length L Ch R = 1 ,144039  ,710,710,710
BEGIN DESCRIPTION:
COLETO CREEK 34
END DESCRIPTION:
XS GIS Cut Line= 3
      2545037.68     13498705.78        2544075.       13498225.
      2540697.76     13496049.76
#Sta/Elev= 30
  3924.3  162.53  4181.1  158.98    4759  125.17  4760.9  125.18  4857.8  114.85
  4869.3  117.77  4874.5  119.24  4891.4   94.16  4892.9   92.16  5047.7   94.16
  5080.6  101.27  5166.9  102.44  5184.6  108.37    5206  110.91  5346.6  123.01
  5470.7  122.71  5621.9  113.53  5799.2  118.33  6087.9  138.69  6403.1  142.22
  6496.3  142.79  6822.8  139.99  7217.5  147.33  7237.4  147.39  8245.6  152.85
  8422.2  155.45  8611.6   158.6  8766.8  161.49  8992.4   166.1  9017.5  166.53
#Mann= 19 ,-1 , 0
  3924.3     .04       0    4759     .05       0  4760.9     .12       0
  4869.3     .03       0  4891.4     .03       0  5047.7     .03       0
  5184.6     .05       0    5206     .04       0  5799.2     .12       0
  6087.9     .04       0  6403.1     .05       0  6496.3     .04       0
  7217.5     .05       0  7237.4     .04       0  8245.6     .12       0
  8422.2     .04       0  8611.6     .05       0  8766.8    .013       0
  8992.4     .05       0
Bank Sta=4891.4,5047.7
XS Rating Curve= 0 ,0
Exp/Cntr=0.3,0.1

Type RM Length L Ch R = 1 ,143329  ,469,469,469
BEGIN DESCRIPTION:
COLETO CREEK 54
END DESCRIPTION:
XS GIS Cut Line= 4
      2545098.45     13497924.53        2544586.     13497734.18
      2543679.84     13497299.71      2541011.51      13495338.9
#Sta/Elev= 30
  4108.6  163.91  4368.3  158.16  4535.8  148.33  4607.6  141.98  4639.6  138.51
  4850.2  122.04  4895.5  112.67    4908   94.31  4909.5   92.31  5064.3   94.31
  5102.1   96.49  5122.1  104.23  5166.5  102.34  5308.9  116.89  5331.5  113.54
  5359.7  101.54  5366.1  107.58    5392   113.5  5720.8  132.04  5780.7  132.97
  5840.4   134.2  5959.9  135.42  6126.9  135.34  6710.8  143.04  7261.3  144.03
  7300.8  144.56  7380.2  144.55  7713.8  146.11    8514  156.97  8971.5  167.65
#Mann= 17 ,-1 , 0
  4108.6     .12       0  4535.8     .05       0  4607.6     .12       0
  4639.6     .05       0    4908     .03       0  5064.3     .05       0
  5102.1     .12       0    5392     .05       0  5720.8     .04       0
  5780.7     .05       0  5840.4     .04       0  5959.9     .12       0
  6126.9     .04       0  7261.3     .05       0  7300.8     .04       0
  7380.2     .05       0  7713.8     .12       0
Bank Sta=4908,5064.3
XS Rating Curve= 0 ,0
Exp/Cntr=0.3,0.1

Type RM Length L Ch R = 1 ,142860  ,760,760,760
BEGIN DESCRIPTION:
COLETO CREEK 45
END DESCRIPTION:
XS GIS Cut Line= 4
       2545306.8       13497586.      2544427.21     13497194.62
      2544344.75     13497165.11      2541140.09     13495164.09
#Sta/Elev= 30
  3985.6  161.32  4095.1  160.67  4458.2  144.91  4691.3  123.95    4813  118.63
  4911.5  107.26  4916.9   94.22  4918.4   92.22  5073.3   94.22  5080.1  100.94
    5086  102.17  5143.8   99.96  5159.1  105.47  5253.5  117.96  5332.5  120.41
    5421  130.07  5603.8  133.73  5884.5  142.98  6261.7  145.73  7344.8  144.43
  7402.7  147.59    7445  143.83  7475.7  136.08  7568.4  139.39  7591.2  145.56
  7641.1  150.48    7669  147.32  8634.7  161.34  8670.8  161.96    8814  164.54
#Mann= 10 ,-1 , 0
  3985.6     .12       0  4916.9     .05       0  5073.3     .03       0
  5603.8     .04       0  7344.8     .05       0  7402.7     .12       0
  7568.4     .05       0    7669     .12       0  8634.7     .05       0
  8670.8     .12       0
Bank Sta=4916.9,5073.3
XS Rating Curve= 0 ,0
Exp/Cntr=0.3,0.1

Type RM Length L Ch R = 1 ,142100  ,1130,1130,1130
BEGIN DESCRIPTION:
COLETO CREEK 51
END DESCRIPTION:
XS GIS Cut Line= 3
       2545567.2     13496908.91      2544547.17     13496506.64
      2541549.03     13494904.19
#Sta/Elev= 30
  3941.1  157.14  3954.4  157.17  4016.6  156.43  4233.1  145.92  4491.7  120.48
  4630.4   116.7  4685.2  116.21  4706.7  114.68  4734.9  109.71  4771.2   97.73
  4910.9   98.48  4918.2   94.45  4919.7   92.45  5073.1   92.45  5074.6   94.45
  5085.4  111.28  5127.2  116.75  5187.5  124.42  5284.4  130.79  5416.4  135.11
  5801.9  143.19  5817.8  143.25  5927.6  142.32  5985.3  142.29  6372.1  142.48
  6408.1  142.52  7465.2  145.31  8226.5  154.69  8398.3  156.88  8437.1  157.87
#Mann= 17 ,-1 , 0
  3941.1     .05       0  3954.4     .12       0  4630.4     .05       0
  4734.9      .1       0  4918.2     .05       0  5074.6      .1       0
  5127.2     .05       0  5416.4     .04       0  5801.9     .05       0
  5817.8      .1       0  5927.6     .05       0  5985.3     .04       0
  6372.1      .1       0  6408.1     .04       0  7465.2     .12       0
  8226.5     .05       0  8398.3     .12       0
Bank Sta=4918.2,5074.6
XS Rating Curve= 0 ,0
Exp/Cntr=0.3,0.1

Type RM Length L Ch R = 1 ,140970  ,1420,1420,1420
BEGIN DESCRIPTION:
COLETO CREEK 52
END DESCRIPTION:
XS GIS Cut Line= 3
      2546053.34     13496058.22      2545066.45     13495625.76
      2541827.51     13494149.23
#Sta/Elev= 30
  3986.3  159.84  4123.9  156.04  4335.9  139.04  4725.4  118.28  4806.4  115.86
  4812.4   94.04  4813.9   92.04  4967.4   92.04  4968.9   94.04  4972.1   94.96
  5120.3   95.41  5131.3  104.23  5145.9  108.91  5171.9  115.45  5184.9     116
  5291.6  122.74    5505  135.24  5660.3  140.05  5931.7  140.02  6095.3  139.97
  6412.4  142.09  6543.8  142.25  6934.6   142.5  7089.6  142.62  7298.7  142.65
  7929.4   150.5  8231.7  152.82  8520.2  156.05  8580.2  156.75  8623.4  157.46
#Mann= 20 ,-1 , 0
  3986.3     .04       0  4123.9     .05       0  4335.9     .12       0
  4812.4     .03       0  4968.9     .12       0  4972.1     .03       0
  5145.9     .12       0  5184.9     .05       0  5291.6     .12       0
    5505     .04       0  5931.7     .03       0  6095.3     .04       0
  6412.4     .05       0  6543.8     .04       0  6934.6     .03       0
  7089.6     .04       0  7929.4     .05       0  8231.7     .12       0
  8520.2     .05       0  8580.2     .12       0
Bank Sta=4812.4,4968.9
XS Rating Curve= 0 ,0
Exp/Cntr=0.3,0.1

Type RM Length L Ch R = 1 ,139550  ,655,655,655
BEGIN DESCRIPTION:
Mapping XS b20f2a63
END DESCRIPTION:
XS GIS Cut Line= 3
      2546786.47     13495508.33      2545760.45     13494534.38
      2542885.41     13493299.99
#Sta/Elev= 30
  3588.4   148.7  4150.6  153.68  4278.1   150.4  4787.3  121.24  4829.8  117.79
  4900.3  114.65  4906.9   94.22  4908.4   92.22  5061.9   92.22  5063.4   94.22
    5085   96.46  5183.1   99.88  5195.5  103.53  5219.1  105.32  5232.8  107.81
  5281.1  113.95  5335.5  118.43  5365.9  122.39    5442  127.63  5519.4  131.24
  5625.1     134  5652.2  134.62  5670.3  133.18  5746.4  134.14  5759.9  135.75
  5998.3  136.36  6325.8  140.69  6445.5  139.99  7449.8  141.45  8131.9  148.42
#Mann= 6 ,-1 , 0
  3588.4     .12       0  4906.9     .03       0  5063.4     .12       0
  5232.8     .12       0  5519.4     .05       0  5625.1     .04       0
Bank Sta=4906.9,5063.4
XS Rating Curve= 0 ,0
Exp/Cntr=0.3,0.1

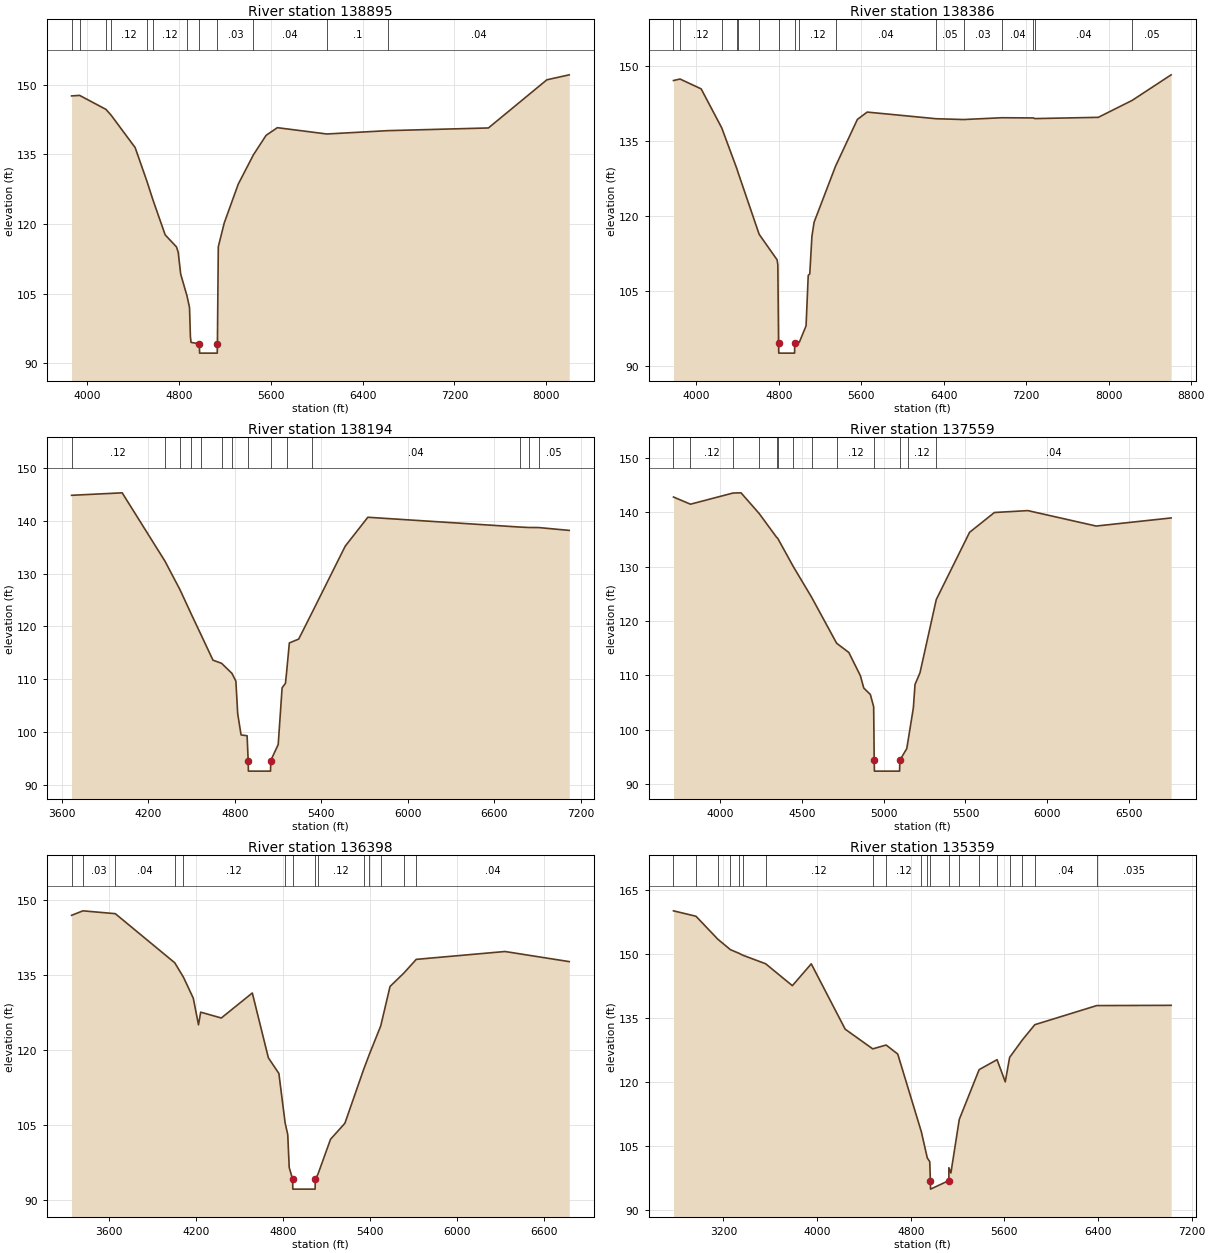
Type RM Length L Ch R = 1 ,138895  ,509,509,509
BEGIN DESCRIPTION:
COLETO CREEK 58
END DESCRIPTION:
XS GIS Cut Line= 3
      2546877.93     13494565.13      2546371.54     13494198.48
       2542989.5     13492681.66
#Sta/Elev= 30
  3867.1  147.56  3937.3  147.67  4166.7  144.66  4212.2  143.39  4420.8  136.43
  4523.3  129.18    4575  125.21  4682.2  117.63  4780.4  115.05  4795.4  113.89
  4817.3  109.17  4872.1  104.49    4894  101.98  4901.7   95.73  4907.2   94.48
  4980.1   94.17  4981.6   92.17  5135.2   92.17  5136.7   94.17  5144.5  115.08
  5196.3  120.21  5317.7  128.54  5450.5  134.89  5560.4  139.07  5658.6  140.72
  6088.9  139.36  6620.9  140.08  7495.6  140.66  8004.3  151.03  8198.9   152.1
#Mann= 12 ,-1 , 0
  3867.1     .05       0  3937.3     .12       0  4166.7     .05       0
  4212.2     .12       0  4523.3     .05       0    4575     .12       0
  4872.1     .03       0  4980.1     .03       0  5136.7     .03       0
  5450.5     .04       0  6088.9      .1       0  6620.9     .04       0
Bank Sta=4980.1,5136.7
XS Rating Curve= 0 ,0
Exp/Cntr=0.3,0.1

Type RM Length L Ch R = 1 ,138386  ,192,192,192
BEGIN DESCRIPTION:
COLETO CREEK 59
END DESCRIPTION:
XS GIS Cut Line= 4
      2546904.03     13494487.06      2546537.88     13493912.37
      2545663.73     13493313.63      2543006.46     13491743.99
#Sta/Elev= 30
  3778.5  147.02    3842  147.32  4047.1  145.35  4246.7  137.55  4392.6  129.43
  4406.2  128.56  4609.6  116.27  4783.6  111.17  4790.7  110.18  4798.1   94.51
  4799.6   92.51  4953.2   92.51  4954.7   94.51  4999.6    94.7  5064.6   97.97
  5085.6  108.05  5100.5  108.35  5121.4  115.87  5142.4  118.68  5350.3  129.88
  5562.3  139.24  5657.4  140.71    6326  139.38  6592.5  139.22  6963.5  139.58
  7269.7  139.54  7282.9  139.41  7898.9  139.66  8227.6  143.05  8605.7  148.16
#Mann= 16 ,-1 , 0
  3778.5     .05       0    3842     .12       0  4246.7     .05       0
  4392.6     .12       0  4406.2     .05       0  4609.6     .12       0
  4798.1     .05       0  4954.7     .12       0  4999.6     .12       0
  5350.3     .04       0    6326     .05       0  6592.5     .03       0
  6963.5     .04       0  7269.7     .05       0  7282.9     .04       0
  8227.6     .05       0
Bank Sta=4798.1,4954.7
XS Rating Curve= 0 ,0
Exp/Cntr=0.3,0.1

Type RM Length L Ch R = 1 ,138194  ,635,635,635
BEGIN DESCRIPTION:
Mapping XS 760b62a5
END DESCRIPTION:
XS GIS Cut Line= 3
      2547038.06     13494482.55      2546703.86     13493814.14
      2544508.84     13492230.78
#Sta/Elev= 30
  3666.7  144.83  4018.1   145.3  4315.3  132.34  4419.6  126.92  4499.1  122.23
  4565.6  118.39  4648.2  113.59    4708  112.99  4779.8  111.09  4807.2  109.61
  4819.9  103.42  4843.2   99.42    4885   99.27  4892.5   94.56    4894   92.56
  5047.6   92.56  5049.1   94.56  5100.9    97.6  5127.9  108.35  5151.2   109.2
  5159.7  111.45  5178.2  116.85  5243.2  117.59  5338.8  122.77  5565.9  135.19
    5723  140.67  6778.8  138.81  6839.1  138.73  6907.7  138.72  7120.5  138.18
#Mann= 14 ,-1 , 0
  3666.7     .12       0  4315.3     .04       0  4419.6     .12       0
  4499.1     .04       0  4565.6     .05       0    4708     .12       0
  4779.8      .1       0  4892.5     .03       0  5049.1      .1       0
  5159.7     .12       0  5338.8     .04       0  6778.8     .05       0
  6839.1     .03       0  6907.7     .05       0
Bank Sta=4892.5,5049.1
XS Rating Curve= 0 ,0
Exp/Cntr=0.3,0.1

Type RM Length L Ch R = 1 ,137559  ,1161,1161,1161
BEGIN DESCRIPTION:
Mapping XS 099f7379
END DESCRIPTION:
XS GIS Cut Line= 4
      2547090.14     13494460.85      2546855.77     13493818.48
      2546621.39     13492151.82      2546152.66     13491670.07
#Sta/Elev= 30
  3716.8  142.81  3820.6  141.49  4080.2  143.54  4129.3  143.58    4240  139.78
  4346.1  135.42  4353.3  135.22  4449.2  129.98  4560.1  124.39  4713.2  115.91
  4787.8  114.21  4858.5  109.92  4878.7  107.68  4919.1  106.48  4939.3  104.23
  4942.5   94.39    4944   92.39  5097.6   92.39  5099.1   94.39  5141.3   96.53
  5148.9   97.91  5181.7  104.04  5191.8  108.33  5222.1  110.48  5321.6  123.95
    5525  136.32  5676.5  139.96  5880.9  140.31  6298.1  137.47  6755.8  138.96
#Mann= 13 ,-1 , 0
  3716.8     .04       0  3820.6     .12       0  4080.2     .04       0
    4240     .05       0  4346.1     .12       0  4353.3     .04       0
  4449.2     .12       0  4560.1     .05       0  4713.2     .12       0
  4942.5     .03       0  5099.1     .12       0  5148.9     .12       0
  5321.6     .04       0
Bank Sta=4942.5,5099.1
XS Rating Curve= 0 ,0
Exp/Cntr=0.3,0.1

Type RM Length L Ch R = 1 ,136398  ,1039,1039,1039
BEGIN DESCRIPTION:
Mapping XS a977e2ed
END DESCRIPTION:
XS GIS Cut Line= 3
      2548062.37     13494499.93      2547758.54     13492889.66
      2546456.44     13491657.01
#Sta/Elev= 30
  3340.3  146.91  3418.9  147.81    3642  147.24  4051.9  137.43  4111.8  134.55
  4179.8  130.35  4215.7  125.03  4230.7  127.56  4372.9  126.39  4586.8  131.39
  4697.6  118.43    4770  115.31    4813  105.44  4831.1   103.1  4841.3   96.49
  4864.7   94.19  4866.2   92.19  5019.8   92.19  5021.3   94.19  5038.7   95.12
  5126.2  102.16  5225.3  105.36  5354.4  116.11  5394.2  119.16  5472.4  124.82
  5536.4  132.69  5630.7  135.34  5717.3  138.11  6328.9  139.68    6772  137.66
#Mann= 14 ,-1 , 0
  3340.3     .04       0  3418.9     .03       0    3642     .04       0
  4051.9     .05       0  4111.8     .12       0    4813     .03       0
  4864.7     .03       0  5021.3     .03       0  5038.7     .12       0
  5354.4     .05       0  5394.2     .12       0  5472.4      .1       0
  5630.7     .05       0  5717.3     .04       0
Bank Sta=4864.7,5021.3
XS Rating Curve= 0 ,0
Exp/Cntr=0.3,0.1

Type RM Length L Ch R = 1 ,135359  ,573,573,573
BEGIN DESCRIPTION:
Mapping XS 34d33a00
END DESCRIPTION:
XS GIS Cut Line= 3
      2550472.58     13493321.88      2548493.45     13492314.95
      2546661.83     13491438.21
#Sta/Elev= 30
  2773.1  160.12  2965.5  158.85  3150.8  153.51  3259.5  151.03  3330.2  150.21
  3368.3   149.7  3560.4  147.73  3788.7   142.6  3950.1  147.71  4240.2  132.41
  4475.4  127.81  4589.7  128.71    4689  126.59  4890.8  108.37  4941.1   102.3
  4962.2  101.41  4967.6   96.98  4969.1   94.98  5125.6   96.98  5125.7   99.99
  5142.9   98.76  5214.6  111.31  5384.2  122.95  5537.2  125.28  5607.3  120.09
  5644.7  125.82  5752.3  129.87  5859.8  133.47  6388.4  137.94  7024.3     138
#Mann= 20 ,-1 , 0
  2773.1     .05       0  2965.5     .12       0  3150.8     .05       0
  3259.5     .12       0  3330.2     .05       0  3368.3     .03       0
  3560.4     .12       0  4475.4     .05       0  4589.7     .12       0
  4890.8      .1       0  4941.1     .03       0  4967.6     .03       0
  5125.6     .03       0  5214.6     .05       0  5384.2     .12       0
  5537.2      .1       0  5644.7     .05       0  5752.3    .013       0
  5859.8     .04       0  6388.4    .035       0
Bank Sta=4967.6,5125.6
XS Rating Curve= 0 ,0
Exp/Cntr=0.3,0.1

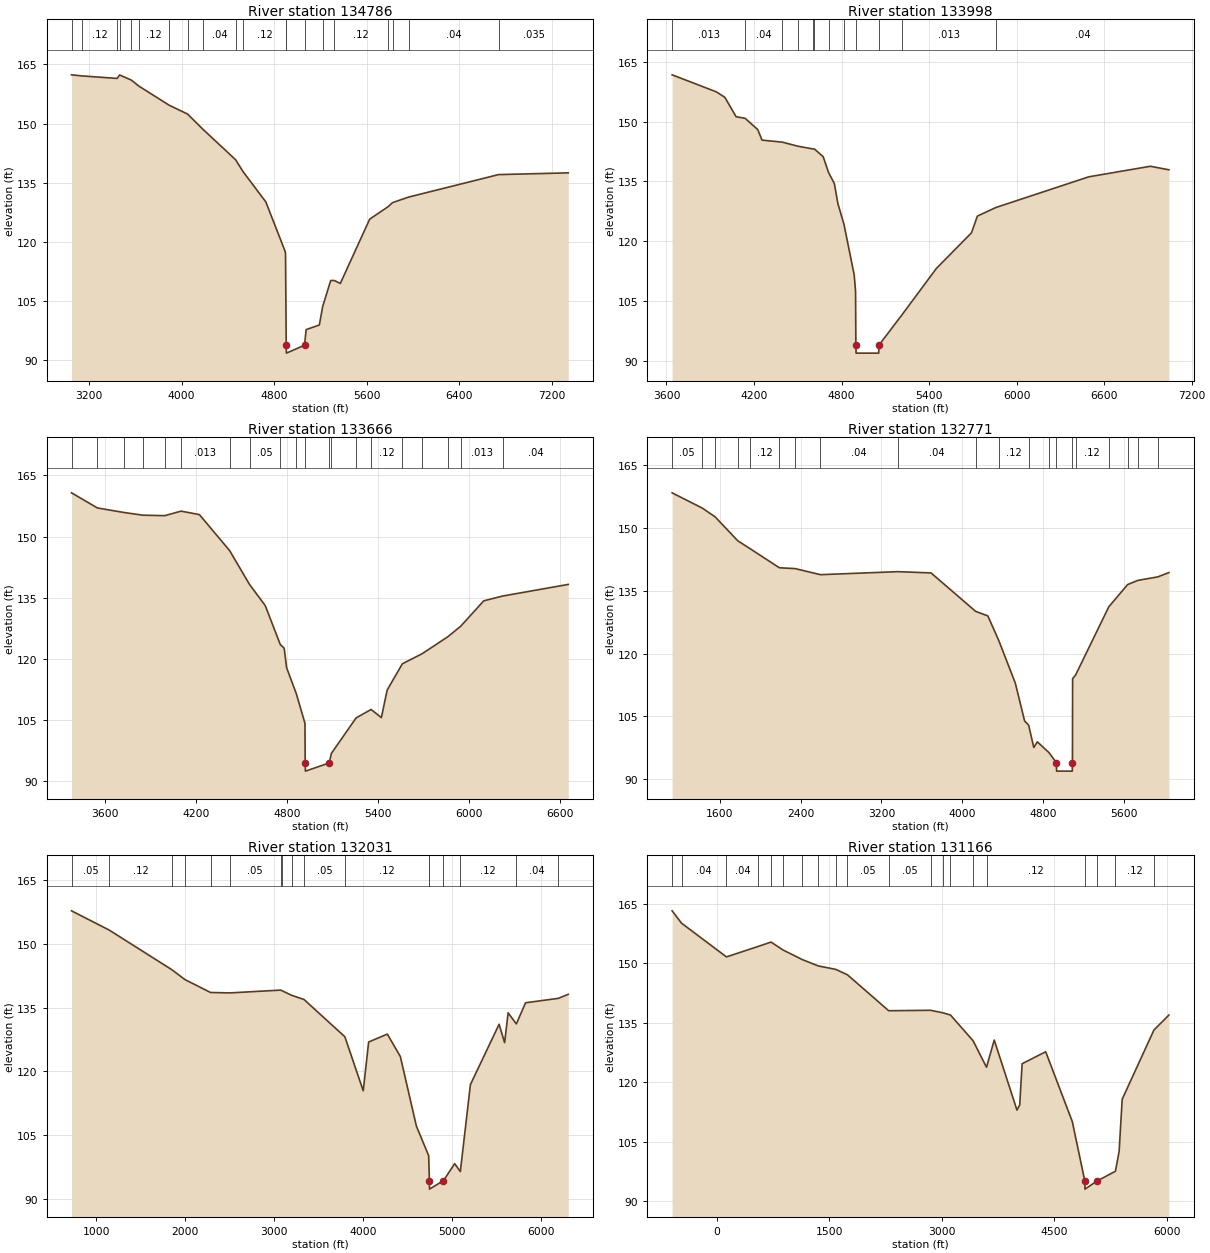
Type RM Length L Ch R = 1 ,134786  ,788,788,788
BEGIN DESCRIPTION:
Mapping XS 7afaa838
END DESCRIPTION:
XS GIS Cut Line= 3
      2550455.23      13493130.9      2548918.79     13491941.69
      2546635.79     13491377.45
#Sta/Elev= 30
  3048.6  162.38  3136.7  162.11  3443.1  161.47  3464.7  162.34  3564.8  161.06
  3631.8  159.51  3891.6   154.7  4051.5  152.45  4188.5  148.48  4467.5  140.86
  4532.3  137.83  4728.6  130.18  4892.5  117.87  4898.8  117.19  4903.2  100.36
  4904.9   93.86  4906.4   91.86  5062.9   93.86  5077.3   97.82  5191.1   98.98
  5220.3  103.71  5289.6  110.26  5320.8  110.26  5372.5  109.51  5626.3   125.8
    5783  128.91  5823.7  129.99  5962.3   131.4    6741   137.1  7343.2  137.54
#Mann= 20 ,-1 , 0
  3048.6     .05       0  3136.7     .12       0  3443.1     .05       0
  3464.7     .12       0  3564.8     .05       0  3631.8     .12       0
  3891.6     .05       0  4051.5     .12       0  4188.5     .04       0
  4467.5    .013       0  4532.3     .12       0  4903.2      .1       0
  4904.9     .03       0  5062.9      .1       0  5220.3      .1       0
  5320.8     .12       0    5783     .04       0  5823.7    .013       0
  5962.3     .04       0    6741    .035       0
Bank Sta=4904.9,5062.9
XS Rating Curve= 0 ,0
Exp/Cntr=0.3,0.1

Type RM Length L Ch R = 1 ,133998  ,332,332,332
BEGIN DESCRIPTION:
COLETO CREEK 63
END DESCRIPTION:
XS GIS Cut Line= 3
      2550487.73     13491757.65      2549349.87      13491282.8
      2547188.72     13491069.63
#Sta/Elev= 30
  3638.9  161.77  3942.1  157.49  4000.6  156.11  4077.5  151.24  4138.9  150.86
  4225.8  148.02    4255  145.38  4395.1  144.86  4500.4  143.85  4605.7  143.15
    4614  143.15  4674.1  141.22    4711  137.25  4750.9  134.45  4774.7  129.47
  4816.3  124.29  4886.8  111.54  4896.1  107.39  4898.2   93.89  4899.7   91.89
  5054.8   91.89  5056.3   93.89  5213.9  101.49  5449.5  113.13  5690.7  122.11
  5730.9   126.3  5859.6  128.48  6494.6  136.16  6916.6  138.81  7043.5  137.92
#Mann= 12 ,-1 , 0
  3638.9    .013       0  4138.9     .04       0  4395.1     .12       0
  4500.4     .05       0  4605.7     .12       0    4614     .05       0
    4711    .013       0  4816.3     .03       0  4898.2     .05       0
  5056.3     .03       0  5213.9    .013       0  5859.6     .04       0
Bank Sta=4898.2,5056.3
XS Rating Curve= 0 ,0
Exp/Cntr=0.3,0.1

Type RM Length L Ch R = 1 ,133666  ,895,895,895
BEGIN DESCRIPTION:
COLETO CREEK 62
END DESCRIPTION:
XS GIS Cut Line= 3
      2550543.83     13491694.41      2549751.02     13491022.32
      2547531.55     13490760.56
#Sta/Elev= 30
  3380.4  160.72  3551.4  157.01  3724.7  155.91  3850.6  155.24  3994.7  155.12
  4102.4  156.23  4223.4  155.38  4422.2  146.58  4553.6  138.28  4657.4  133.08
  4756.3  123.55  4782.2  122.63  4798.4  117.83  4861.6  111.54  4919.2  104.22
  4920.7    94.5  4922.2    92.5  5078.8    94.5  5093.6   96.86  5256.3  105.55
  5354.9  107.61  5422.7  105.62    5461  112.38  5561.3  118.82  5692.8  121.31
  5860.8  125.44  5946.9  128.06  6097.3  134.24  6222.3  135.42  6654.6  138.27
#Mann= 20 ,-1 , 0
  3380.4     .05       0  3551.4    .013       0  3724.7     .12       0
  3850.6     .12       0  3994.7     .12       0  4102.4    .013       0
  4422.2    .013       0  4553.6     .05       0  4756.3     .12       0
  4861.6     .03       0  4920.7     .03       0  5078.8     .03       0
  5093.6      .1       0  5256.3     .05       0  5354.9     .12       0
  5561.3     .05       0  5692.8     .12       0  5860.8     .05       0
  5946.9    .013       0  6222.3     .04       0
Bank Sta=4920.7,5078.8
XS Rating Curve= 0 ,0
Exp/Cntr=0.3,0.1

Type RM Length L Ch R = 1 ,132771  ,740,740,740
BEGIN DESCRIPTION:
COLETO CREEK 61
END DESCRIPTION:
XS GIS Cut Line= 3
      2552481.85     13491160.81      2549820.64     13490247.99
      2547742.27     13490542.89
#Sta/Elev= 30
  1130.3  158.38  1428.1  154.74  1554.9  152.66  1779.4  146.93  1899.2  145.08
  2190.4  140.49  2346.1  140.29  2597.1  138.84  3360.5  139.56  3690.8  139.26
  4131.8  130.08  4252.4     129  4360.5  123.13  4523.8  112.98    4616  103.93
  4655.9  102.93  4706.9   97.58  4741.7   98.94  4857.9   96.34  4930.9   93.94
  4932.4   91.94  5087.5   91.94    5089   93.94  5090.7     114  5120.8  114.91
  5448.7  131.17    5635  136.48  5734.7  137.47  5934.1  138.32  6042.9  139.34
#Mann= 20 ,-1 , 0
  1130.3     .05       0  1428.1     .05       0  1554.9     .12       0
  1779.4     .05       0  1899.2     .12       0  2190.4     .05       0
  2346.1    .013       0  2597.1     .04       0  3360.5     .04       0
  4131.8     .05       0  4360.5     .12       0  4655.9     .03       0
  4857.9      .1       0  4930.9     .05       0    5089      .1       0
  5120.8     .12       0  5448.7     .12       0    5635     .04       0
  5734.7     .05       0  5934.1    .013       0
Bank Sta=4930.9,5089
XS Rating Curve= 0 ,0
Exp/Cntr=0.3,0.1

Type RM Length L Ch R = 1 ,132031  ,865,865,865
BEGIN DESCRIPTION:
COLETO CREEK 67
END DESCRIPTION:
XS GIS Cut Line= 4
       2552516.9     13491104.61      2549490.62     13489524.76
      2547973.95     13489953.08      2547496.52     13490297.12
#Sta/Elev= 30
   722.7  157.81  1146.2  153.28  1850.5  143.94  1996.4  141.63  2284.2  138.59
  2500.1  138.49  3071.1  139.15  3087.7  138.99    3197  137.91  3333.8  136.94
  3792.4  128.17  3998.7  115.45  4059.3  126.93  4269.2   128.8  4415.6  123.51
  4595.9  107.12  4733.5  100.19  4741.5   94.31    4743   92.31  4899.6   94.31
  5025.6   98.31  5089.1   96.44  5202.3  116.92  5524.4  131.11  5586.2  126.78
  5625.4   133.8    5718   131.2  5821.5  136.17  6188.6  137.21    6301  138.16
#Mann= 17 ,-1 , 0
   722.7     .05       0  1146.2     .12       0  1850.5    .013       0
  1996.4     .05       0  2284.2     .04       0  2500.1     .05       0
  3071.1     .04       0  3087.7     .05       0    3197     .04       0
  3333.8     .05       0  3792.4     .12       0  4733.5      .1       0
  4741.5     .03       0  4899.6      .1       0  5089.1     .12       0
    5718     .04       0  6188.6    .013       0
Bank Sta=4741.5,4899.6
XS Rating Curve= 0 ,0
Exp/Cntr=0.3,0.1

Type RM Length L Ch R = 1 ,131166  ,973,973,973
BEGIN DESCRIPTION:
COLETO CREEK 68
END DESCRIPTION:
XS GIS Cut Line= 3
      2553691.94     13491290.66      2548749.51     13488988.11
      2547602.19     13489188.22
#Sta/Elev= 30
  -591.8  163.26  -465.8  160.14   131.9  151.64     557   154.3   725.9  155.38
   884.9  153.39    1143  150.96  1354.5  149.37  1587.4   148.5  1742.9  147.14
  2293.2  138.07  2851.8  138.18    3010  137.57    3116  136.99  3416.4  130.52
  3595.8  123.82  3698.8  130.68  4001.7  113.02  4038.2  114.29  4070.3  124.71
  4384.2  127.73  4738.3  110.14    4906   95.09  4907.5   93.09  5064.1   95.09
  5313.3    97.6  5362.6  102.63  5403.2  115.75  5826.6  133.22  6025.3  136.98
#Mann= 20 ,-1 , 0
  -591.8     .05       0  -465.8     .04       0   131.9     .04       0
     557     .05       0   725.9     .04       0   884.9    .013       0
    1143     .04       0  1354.5     .05       0  1587.4    .013       0
  1742.9     .05       0  2293.2     .05       0  2851.8     .04       0
    3010     .05       0    3116     .05       0  3416.4     .03       0
  3595.8     .12       0    4906     .05       0  5064.1      .1       0
  5313.3     .12       0  5826.6     .04       0
Bank Sta=4906,5064.1
XS Rating Curve= 0 ,0
Exp/Cntr=0.3,0.1

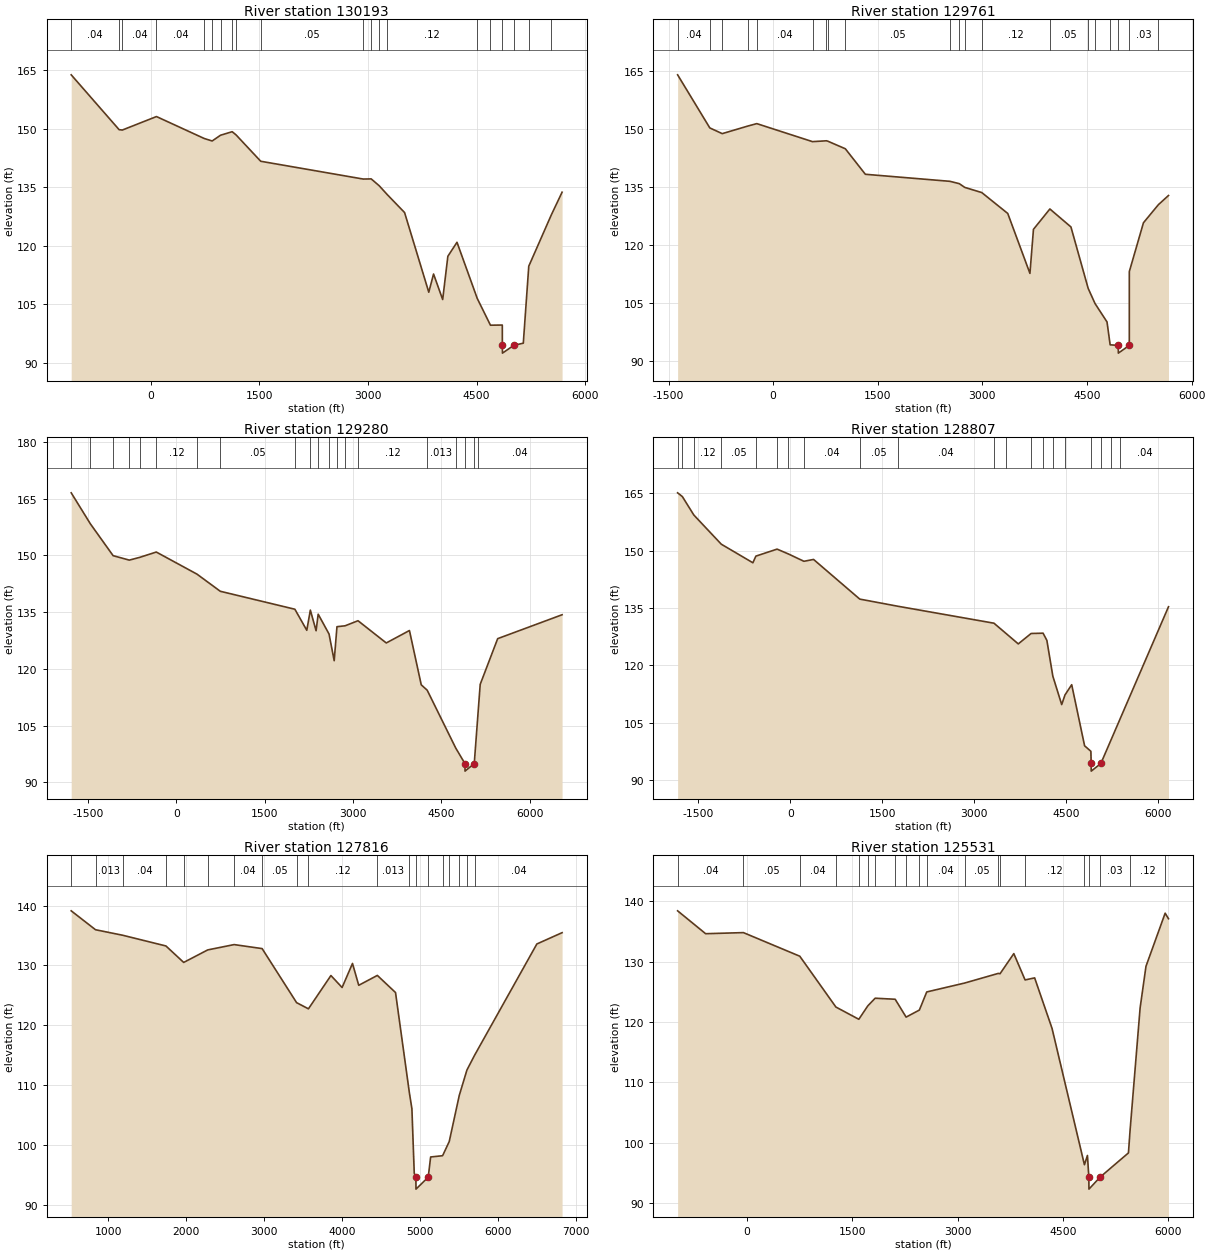
Type RM Length L Ch R = 1 ,130193  ,432,432,432
BEGIN DESCRIPTION:
COLETO CREEK 74
END DESCRIPTION:
XS GIS Cut Line= 3
      2553702.36     13491207.33      2548496.03     13488427.78
      2547619.46     13488415.66
#Sta/Elev= 30
 -1096.8  163.87  -435.2  149.81  -391.8  149.71    80.6  153.17   739.8  147.55
   849.6  146.91   965.1  148.38  1125.7  149.29    1179  148.48  1520.3  141.71
  2935.7  137.15  3045.5  137.19  3155.3  135.45  3265.1  133.21  3506.7  128.56
  3840.9  108.14  3906.8   112.8  4032.8  106.26  4104.3  117.35  4230.4  120.94
  4510.2  106.54  4692.5   99.68  4856.1   99.72  4856.9   94.52  4858.4   92.52
  5015.2   94.52  5146.1   95.07  5221.6   114.8    5533  127.96  5681.7  133.78
#Mann= 20 ,-1 , 0
 -1096.8     .04       0  -435.2     .05       0  -391.8     .04       0
    80.6     .04       0   739.8    .013       0   849.6     .05       0
   965.1    .013       0  1125.7     .05       0    1179     .12       0
  1520.3     .05       0  2935.7     .12       0  3045.5     .05       0
  3155.3     .05       0  3265.1     .12       0  4510.2      .1       0
  4692.5      .1       0  4856.9     .03       0  5015.2      .1       0
  5221.6     .12       0    5533     .04       0
Bank Sta=4856.9,5015.2
XS Rating Curve= 0 ,0
Exp/Cntr=0.3,0.1

Type RM Length L Ch R = 1 ,129761  ,481,481,481
BEGIN DESCRIPTION:
COLETO CREEK 33
END DESCRIPTION:
XS GIS Cut Line= 4
      2553702.38     13491113.59      2548952.31     13488074.78
      2548025.26     13488071.91      2547619.03     13488311.48
#Sta/Elev= 30
 -1369.7   164.1  -908.1  150.37  -729.9  148.89  -358.5  150.88  -234.5  151.48
   564.4  146.82   764.2  147.04   782.3  146.95  1034.7  144.98  1321.8  138.38
  2534.4  136.56  2669.3  135.95  2746.8  134.99  2990.9  133.65  3363.4  128.25
  3681.4  112.75  3731.8  124.14  3967.3  129.41  4269.2  124.76  4516.5  108.86
  4614.8  104.95  4786.5  100.19  4831.3   94.28  4947.4   94.13  4948.9   92.13
  5105.7   94.13  5106.5  113.24  5308.8  125.84    5523  130.52  5667.9  132.89
#Mann= 20 ,-1 , 0
 -1369.7     .04       0  -908.1     .05       0  -729.9     .04       0
  -358.5     .05       0  -234.5     .04       0   564.4    .013       0
   764.2     .04       0   782.3     .12       0  1034.7     .05       0
  2534.4     .03       0  2669.3     .05       0  2746.8     .12       0
  2990.9     .12       0  3967.3     .05       0  4516.5     .03       0
  4614.8      .1       0  4831.3     .03       0  4947.4     .03       0
  5105.7     .03       0    5523     .04       0
Bank Sta=4947.4,5105.7
XS Rating Curve= 0 ,0
Exp/Cntr=0.3,0.1

Type RM Length L Ch R = 1 ,129280  ,473,473,473
BEGIN DESCRIPTION:
COLETO CREEK 73
END DESCRIPTION:
XS GIS Cut Line= 3
      2553796.14      13491089.3      2549282.25     13487650.84
        2546626.      13487547.6
#Sta/Elev= 30
 -1782.6  166.57 -1456.4  158.35 -1071.2  149.95  -796.9  148.77  -615.3  149.52
  -338.4  150.91   352.7  145.06   748.1  140.53  2014.1  135.78  2216.4  130.21
  2276.8  135.55  2374.2  130.09  2409.7  134.47  2594.2  129.22  2681.5  122.17
  2728.6  131.16  2866.7   131.4  3085.8  132.74  3565.4  126.86    3959  130.15
  4159.2  115.79  4260.4  114.36  4744.5   99.07  4900.7   94.96  4902.2   92.96
    5059   94.96  5116.9  106.97    5160  115.91  5456.7     128    6550  134.32
#Mann= 20 ,-1 , 0
 -1782.6     .12       0 -1456.4     .05       0 -1071.2     .04       0
  -796.9     .05       0  -615.3     .04       0  -338.4     .12       0
   352.7     .04       0   748.1     .05       0  2014.1     .03       0
  2276.8     .05       0  2409.7     .03       0  2594.2     .05       0
  2728.6     .12       0  2866.7     .05       0  3085.8     .12       0
  4260.4    .013       0  4744.5     .03       0  4900.7     .05       0
    5059      .1       0  5116.9     .04       0
Bank Sta=4900.7,5059
XS Rating Curve= 0 ,0
Exp/Cntr=0.3,0.1

Type RM Length L Ch R = 1 ,128807  ,991,991,991
BEGIN DESCRIPTION:
COLETO CREEK 72
END DESCRIPTION:
XS GIS Cut Line= 4
      2553830.82      13490985.1      2550129.33     13487548.37
      2548431.47     13487213.32       2547201.9     13487227.06
#Sta/Elev= 30
 -1838.1  165.13 -1760.2  164.14 -1573.9  159.34 -1125.6   151.7  -609.8  146.84
  -560.7  148.58  -214.8  150.41     -35  149.18     223  147.23   380.6  147.71
  1134.8  137.34  1757.2  135.47  3324.8  131.04  3522.1  128.35  3721.4  125.63
  3930.9  128.35  4126.2  128.43  4188.3  126.54  4285.7  117.18  4430.2  109.76
  4483.8  112.28  4593.3  114.96    4804   98.98  4906.6   97.54  4910.8   94.36
  4912.3   92.36  5069.1   94.36  5235.7  100.54  5388.9  106.23  6173.1  135.34
#Mann= 20 ,-1 , 0
 -1838.1     .04       0 -1760.2     .12       0 -1573.9     .12       0
 -1125.6     .05       0  -560.7     .12       0  -214.8     .12       0
     -35     .04       0     223     .04       0  1134.8     .05       0
  1757.2     .04       0  3324.8     .04       0  3522.1     .04       0
  3930.9     .12       0  4126.2    .013       0  4285.7     .03       0
  4483.8     .05       0  4910.8     .03       0  5069.1     .03       0
  5235.7     .12       0  5388.9     .04       0
Bank Sta=4910.8,5069.1
XS Rating Curve= 0 ,0
Exp/Cntr=0.3,0.1

Type RM Length L Ch R = 1 ,127816  ,2285,2285,2285
BEGIN DESCRIPTION:
COLETO CREEK 71
END DESCRIPTION:
XS GIS Cut Line= 4
      2552844.11     13487226.09      2548856.24      13486333.2
      2547372.49      13486297.6      2546782.22     13486714.26
#Sta/Elev= 30
   526.4  139.13   838.4  135.97  1186.5  135.05  1740.7  133.26  1968.5  130.51
  2276.3   132.6  2615.1  133.49  2974.1  132.82    3416  123.79  3567.7  122.76
    3856  128.32  3999.4  126.32  4132.6  130.34  4212.6  126.69  4451.2  128.34
  4684.3  125.48    4862  108.73  4894.3  106.08  4924.3    95.3  4945.2   94.64
  4946.7   92.64  5103.6   94.64  5134.4   98.01  5287.9   98.22  5372.9  100.59
  5501.6   108.3  5599.9  112.54  5698.1  115.01  6496.1  133.59  6819.7  135.48
#Mann= 19 ,-1 , 0
   526.4     .04       0   838.4    .013       0  1186.5     .04       0
  1740.7     .05       0  1968.5     .04       0  2276.3     .05       0
  2615.1     .04       0  2974.1     .05       0    3416      .1       0
  3567.7     .12       0  4451.2    .013       0    4862     .03       0
  4945.2     .03       0  5103.6     .03       0  5287.9     .12       0
  5372.9     .05       0  5501.6     .12       0  5599.9     .05       0
  5698.1     .04       0
Bank Sta=4945.2,5103.6
XS Rating Curve= 0 ,0
Exp/Cntr=0.3,0.1

Type RM Length L Ch R = 1 ,125531  ,1524,1524,1524
BEGIN DESCRIPTION:
COLETO CREEK 70
END DESCRIPTION:
XS GIS Cut Line= 3
      2553443.35       13486679.      2548082.45      13484492.1
      2546888.18     13484353.37
#Sta/Elev= 30
  -990.5   138.4  -591.6  134.61   -53.3  134.79   749.7  130.88    1264  122.46
  1590.7  120.43  1718.2  122.65  1823.2  123.92  2108.4  123.75  2264.2  120.79
    2453  121.96    2558  124.96  3096.3  126.43  3576.4  128.03  3602.5  127.98
  3798.2  131.31  3958.8  126.95    4095  127.29  4342.9  118.92  4804.2   96.33
  4847.1   97.87  4866.9   94.29  4868.4   92.29  5028.5   94.29    5431   98.29
    5455  102.13  5597.3  122.31  5680.9  129.21    5954  138.01  6001.6  137.09
#Mann= 20 ,-1 , 0
  -990.5     .04       0   -53.3     .05       0   749.7     .04       0
    1264     .04       0  1590.7     .05       0  1718.2    .013       0
  1823.2     .05       0  2108.4     .04       0  2264.2     .05       0
    2453     .05       0    2558     .04       0  3096.3     .05       0
  3576.4     .12       0  3602.5     .05       0  3958.8     .12       0
  4804.2     .03       0  4866.9     .03       0  5028.5     .03       0
    5455     .12       0    5954     .05       0
Bank Sta=4866.9,5028.5
XS Rating Curve= 0 ,0
Exp/Cntr=0.3,0.1