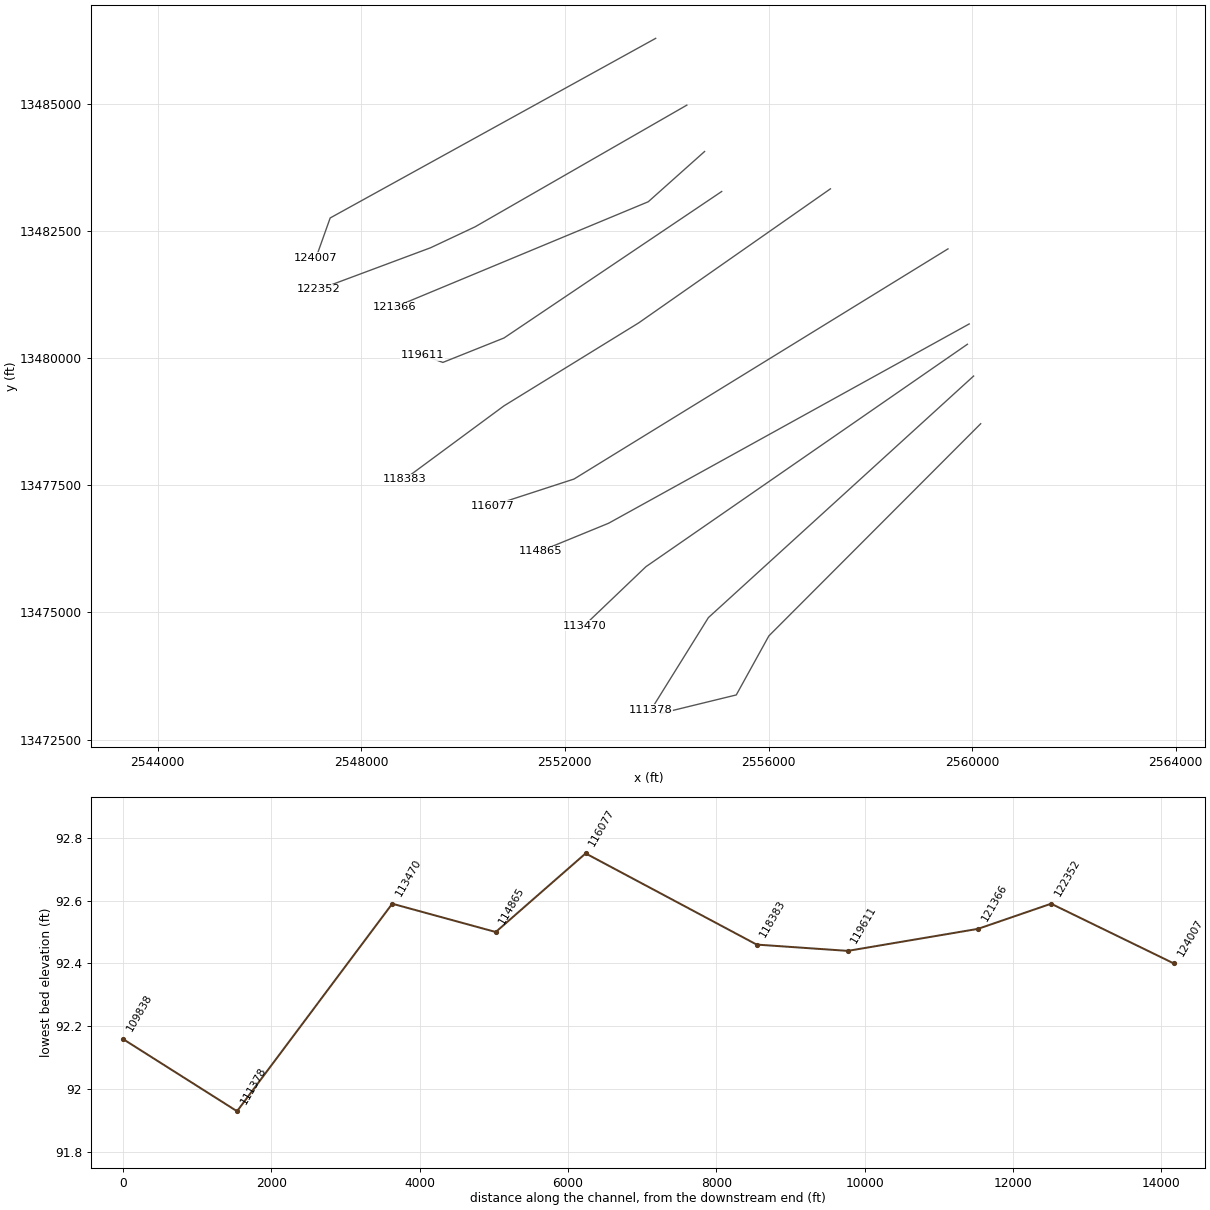
HEC-RAS study COLETO CREEK.prj: COLETO CREEK Base Level Engineering

--- COLETO CREEK.g01 (geometry) --- (continued)

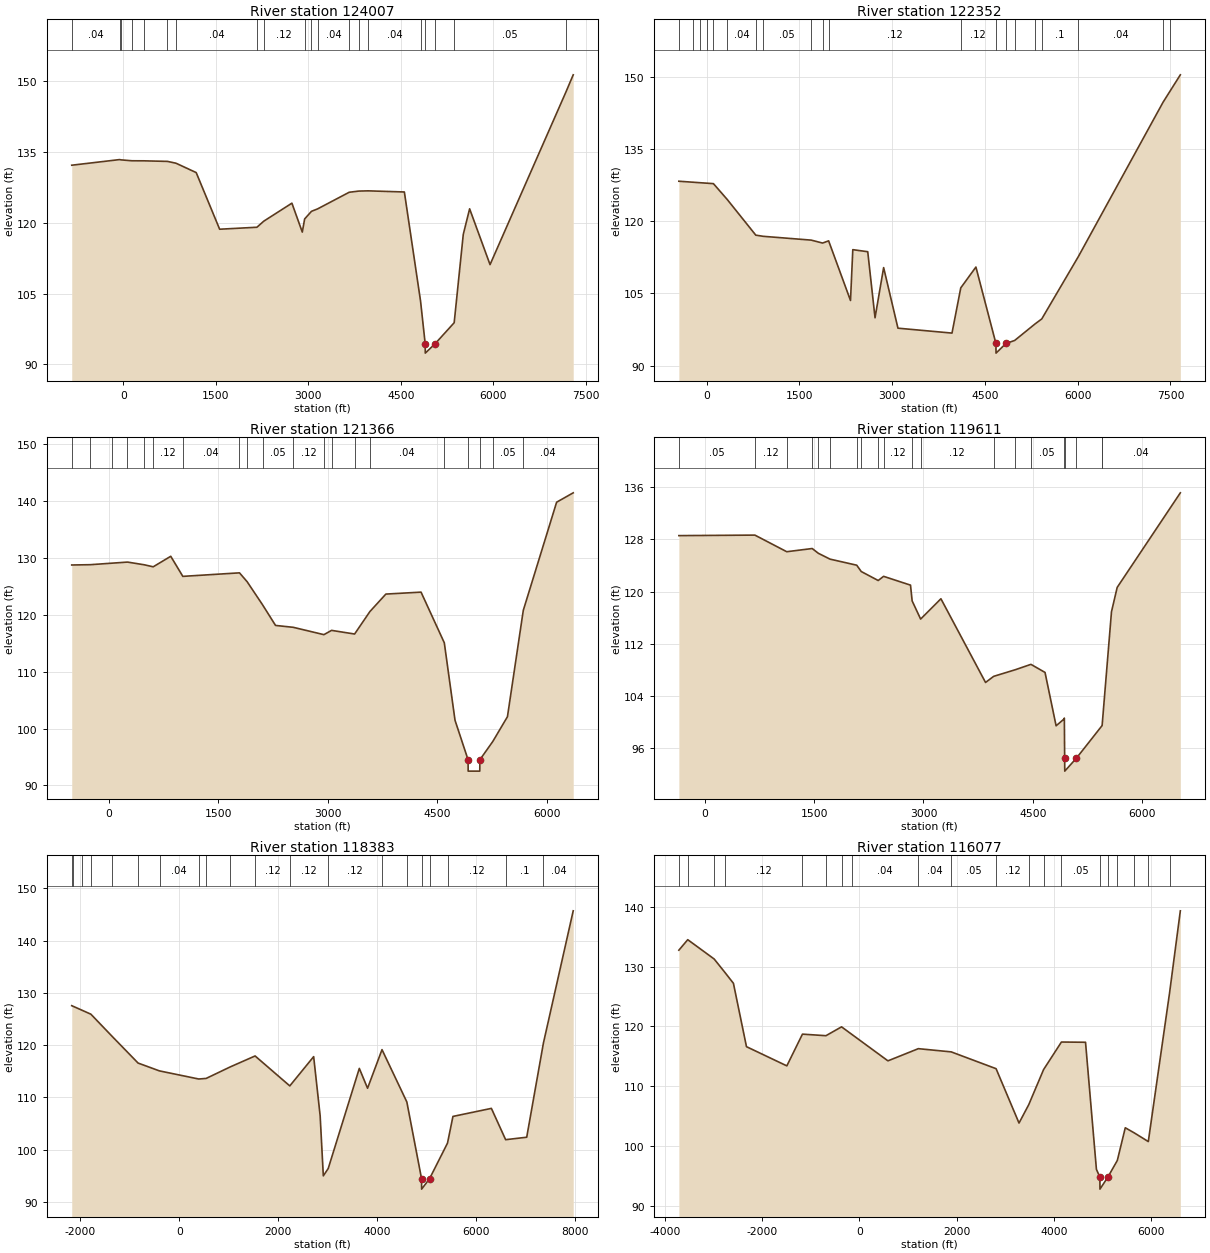
Type RM Length L Ch R = 1 ,124007  ,1655,1655,1655
BEGIN DESCRIPTION:
COLETO CREEK 69
END DESCRIPTION:
XS GIS Cut Line= 3
      2553784.09     13486287.64      2547389.85     13482755.94
      2547112.07     13481974.69
#Sta/Elev= 30
  -838.4  132.21   -63.7   133.4   -36.8  133.34   138.7  133.15   332.4  133.14
   714.3  133.02   853.2  132.63  1180.3  130.65  1560.6  118.65  2165.3  119.07
  2275.9  120.35  2732.7  124.17  2901.2  118.04  2939.4  120.83    3050  122.44
  3149.7  122.96  3661.9  126.48  3817.8  126.73  3968.1  126.78  4556.7  126.54
  4819.4  103.42  4894.5    94.4    4896    92.4  5056.1    94.4  5364.7   98.84
  5512.3  117.56  5615.4  122.97  5946.5  111.15  7175.4  147.66  7295.5  151.36
#Mann= 20 ,-1 , 0
  -838.4     .04       0   -63.7     .05       0   -36.8     .04       0
   138.7    .013       0   332.4     .04       0   714.3     .05       0
   853.2     .04       0  2165.3    .013       0  2275.9     .12       0
  2939.4     .04       0    3050    .013       0  3149.7     .04       0
  3661.9     .04       0  3817.8     .03       0  3968.1     .04       0
  4819.4     .05       0  4894.5     .03       0  5056.1     .05       0
  5364.7     .05       0  7175.4     .04       0
Bank Sta=4894.5,5056.1
XS Rating Curve= 0 ,0
Exp/Cntr=0.3,0.1

Type RM Length L Ch R = 1 ,122352  ,986,986,986
BEGIN DESCRIPTION:
COLETO CREEK 76
END DESCRIPTION:
XS GIS Cut Line= 4
       2554395.7     13484974.36      2550237.07     13482582.32
      2549363.21     13482170.73       2547164.6     13481349.85
#Sta/Elev= 30
  -450.8  128.29  -226.6  128.09  -107.7  127.98    -3.4  127.89   108.2  127.79
   331.4   124.5   793.6  117.09     914  116.85  1689.7  116.06  1873.5  115.45
  1971.3  115.91  2325.1  103.52  2362.4  114.08  2603.9  113.65  2721.8   99.93
  2860.9  110.35  3092.6   97.77  3966.5   96.75  4108.3  106.14  4353.3  110.47
  4677.1   94.59  4678.6   92.59  4838.8   94.59  4980.1   95.22  5314.3    98.7
  5418.2   99.69  6010.9  112.66  7379.7  144.69  7485.5  146.85  7659.5  150.39
#Mann= 20 ,-1 , 0
  -450.8     .05       0  -226.6     .04       0  -107.7     .04       0
    -3.4    .013       0   108.2    .013       0   331.4     .04       0
   793.6     .05       0     914     .05       0  1689.7     .04       0
  1873.5     .04       0  1971.3     .12       0  4108.3     .12       0
  4677.1     .03       0  4838.8     .12       0  4980.1     .03       0
  5314.3     .05       0  5418.2      .1       0  6010.9     .04       0
  7379.7    .013       0  7485.5     .04       0
Bank Sta=4677.1,4838.8
XS Rating Curve= 0 ,0
Exp/Cntr=0.3,0.1

Type RM Length L Ch R = 1 ,121366  ,1755,1755,1755
BEGIN DESCRIPTION:
COLETO CREEK 75
END DESCRIPTION:
XS GIS Cut Line= 3
      2554744.43     13484062.81       2553637.7      13483074.7
      2548658.64     13481003.06
#Sta/Elev= 30
    -511  128.73  -260.6  128.78    41.5  129.05   253.5  129.24   486.4  128.76
     606  128.41   846.7  130.26  1012.4  126.73  1789.1  127.35  1894.4  125.79
  2104.9  121.75  2283.6  118.11  2525.9  117.78  2946.8  116.49  3052.1  117.24
  3367.8   116.6  3578.3  120.56  3796.7  123.62    4279  123.96  4597.8  115.06
  4744.8  101.44  4923.6   94.51  4925.1   92.51  5084.3   92.51  5085.8   94.51
  5262.2   97.71  5463.7  102.07  5680.9  120.76  6137.9  139.76  6365.5  141.41
#Mann= 20 ,-1 , 0
    -511     .04       0  -260.6     .05       0    41.5     .05       0
   253.5     .04       0   486.4     .04       0     606     .12       0
  1012.4     .04       0  1789.1    .013       0  1894.4     .12       0
  2104.9     .05       0  2525.9     .12       0  2946.8     .05       0
  3052.1     .12       0  3367.8     .05       0  3578.3     .04       0
  4597.8     .05       0  4923.6     .03       0  5085.8     .03       0
  5262.2     .05       0  5680.9     .04       0
Bank Sta=4923.6,5085.8
XS Rating Curve= 0 ,0
Exp/Cntr=0.3,0.1

Type RM Length L Ch R = 1 ,119611  ,1228,1228,1228
BEGIN DESCRIPTION:
COLETO CREEK 77
END DESCRIPTION:
XS GIS Cut Line= 4
      2555080.81     13483276.77      2550804.07     13480396.34
      2549603.35     13479916.05      2549203.12     13480062.81
#Sta/Elev= 30
  -353.6  128.59   688.7  128.67  1125.7  126.12  1474.6  126.61  1558.7  125.88
  1719.8  124.98    2085  124.05    2147  123.08  2379.6   121.7  2453.4  122.34
  2822.6  120.99  2844.9  118.57  2961.3  115.78  3239.5   118.9  3851.3  106.05
    3963  106.99  4260.8  108.01  4473.5  108.83  4666.9  107.59  4818.8    99.4
  4921.6  100.38  4931.9  100.58    4936   94.44  4937.5   92.44  5098.2   94.44
  5443.7   99.35  5449.8   99.44  5578.1   116.9  5656.2  120.64  6522.2  135.16
#Mann= 20 ,-1 , 0
  -353.6     .05       0   688.7     .12       0  1125.7     .04       0
  1474.6     .12       0  1558.7    .013       0  1719.8     .12       0
    2085     .05       0    2147     .12       0  2379.6    .013       0
  2453.4     .12       0  2844.9    .013       0  2961.3     .12       0
    3963     .04       0  4260.8    .013       0  4473.5     .05       0
  4921.6     .03       0    4936     .03       0  5098.2     .03       0
  5443.7     .05       0  5449.8     .04       0
Bank Sta=4936,5098.2
XS Rating Curve= 0 ,0
Exp/Cntr=0.3,0.1

Type RM Length L Ch R = 1 ,118383  ,2306,2306,2306
BEGIN DESCRIPTION:
COLETO CREEK 81
END DESCRIPTION:
XS GIS Cut Line= 4
       2557216.2     13483328.83      2553450.56     13480693.79
      2550804.07     13479062.21      2548849.07     13477617.71
#Sta/Elev= 30
 -2171.7  127.56 -2142.7  127.44 -1954.8  126.65 -1784.3  125.93 -1356.3   121.7
  -830.7  116.58  -397.7  115.08   395.9  113.53   544.8  113.64  1033.1  115.85
  1534.5  117.94  2235.6  112.21    2718  117.81  2849.3  106.48  2913.2      95
  3012.1    96.4  3640.9  115.56  3807.4  111.76  4099.4  119.15  4601.4  109.14
  4898.5   94.46    4900   92.46  5060.7   94.46  5423.1  101.26  5533.3  106.37
  6310.2  107.91  6598.3  101.92  7024.2  102.39  7362.1  120.42  7964.1  145.71
#Mann= 20 ,-1 , 0
 -2171.7     .04       0 -2142.7    .013       0 -1954.8     .03       0
 -1784.3     .04       0 -1356.3    .013       0  -830.7     .12       0
  -397.7     .04       0   395.9     .05       0   544.8     .12       0
  1033.1     .12       0  1534.5     .12       0  2235.6     .12       0
  3012.1     .12       0  4099.4     .12       0  4601.4     .12       0
  4898.5     .03       0  5060.7     .12       0  5423.1     .12       0
  6598.3      .1       0  7362.1     .04       0
Bank Sta=4898.5,5060.7
XS Rating Curve= 0 ,0
Exp/Cntr=0.3,0.1

Type RM Length L Ch R = 1 ,116077  ,1212,1212,1212
BEGIN DESCRIPTION:
COLETO CREEK 80
END DESCRIPTION:
XS GIS Cut Line= 3
       2559525.3     13482148.32      2552179.51     13477623.21
      2550578.59     13477101.48
#Sta/Elev= 30
 -3709.6  132.74 -3526.9   134.5 -2984.3  131.27 -2770.5   129.1 -2587.7   127.2
 -2319.2  116.59 -1489.4  113.38 -1168.3  118.69  -685.3  118.43  -364.1  119.91
    -153  118.65   589.5  114.22  1215.2  116.26  1890.7  115.72  2812.9  112.91
  3284.7  103.81  3485.1  106.89  3790.7  112.77  4156.7  117.37  4652.3  117.33
  4876.4   96.06  4947.5   94.75    4949   92.75    5111   94.75  5306.2   97.55
  5469.8  103.02  5659.2  102.14  5943.2  100.71  6380.1  125.58  6601.9  139.33
#Mann= 20 ,-1 , 0
 -3709.6     .04       0 -3526.9     .12       0 -2984.3    .013       0
 -2770.5     .12       0 -1168.3     .12       0  -685.3     .03       0
  -364.1     .05       0    -153     .04       0  1215.2     .04       0
  1890.7     .05       0  2812.9     .12       0  3485.1    .013       0
  3790.7     .04       0  4156.7     .05       0  4947.5     .03       0
    5111     .03       0  5306.2     .12       0  5659.2     .03       0
  5943.2     .12       0  6380.1     .04       0
Bank Sta=4947.5,5111
XS Rating Curve= 0 ,0
Exp/Cntr=0.3,0.1

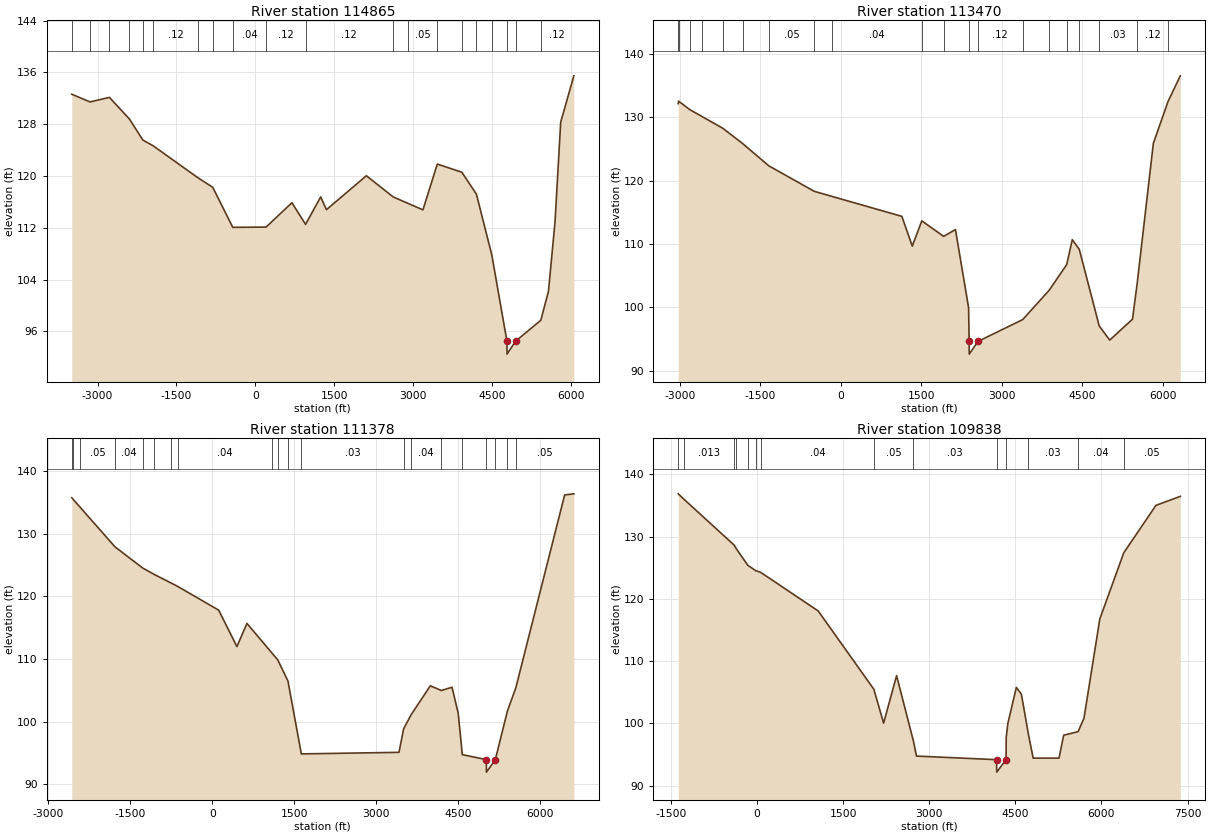
Type RM Length L Ch R = 1 ,114865  ,1395,1395,1395
BEGIN DESCRIPTION:
COLETO CREEK 84
END DESCRIPTION:
XS GIS Cut Line= 3
      2559941.93      13480672.6      2552858.62     13476754.17
      2551524.49     13476207.18
#Sta/Elev= 30
 -3488.8  132.64 -3141.8  131.45 -2773.5  132.15 -2394.3  128.82 -2138.1  125.56
 -1944.9  124.69 -1096.1  119.76  -810.6  118.26  -430.8  112.08   201.8  112.12
   692.8  115.88   952.1  112.54  1238.9  116.77  1349.1  114.81  2107.5  120.05
  2616.3  116.78  2903.3  115.76  3181.7  114.78  3454.6  121.85  3919.5   120.6
  4196.8  117.22  4489.2  107.84  4777.2    94.5  4778.7    92.5  4941.2    94.5
  5420.8   97.73  5566.3  102.22  5690.8  112.96  5798.4  128.33    6048  135.48
#Mann= 20 ,-1 , 0
 -3488.8     .05       0 -3141.8     .05       0 -2773.5    .013       0
 -2394.3     .05       0 -2138.1     .04       0 -1944.9     .12       0
 -1096.1     .12       0  -810.6     .12       0  -430.8     .04       0
   201.8     .12       0   952.1     .12       0  2616.3     .04       0
  2903.3     .05       0  3454.6     .05       0  3919.5     .04       0
  4196.8     .05       0  4489.2      .1       0  4777.2     .03       0
  4941.2      .1       0  5420.8     .12       0
Bank Sta=4777.2,4941.2
XS Rating Curve= 0 ,0
Exp/Cntr=0.3,0.1

Type RM Length L Ch R = 1 ,113470  ,2092,2092,2092
BEGIN DESCRIPTION:
COLETO CREEK 82
END DESCRIPTION:
XS GIS Cut Line= 3
      2559907.17     13480273.27      2553592.39     13475900.33
      2552379.35     13474740.62
#Sta/Elev= 30
 -3029.7  132.17 -3022.7  132.57 -2814.5  131.23 -2590.7  130.16 -2198.2  128.28
 -1827.8  125.86 -1339.8  122.34  -494.3  118.32  -166.1  117.52    1139  114.36
  1332.9  109.66  1511.2  113.65  1918.4   111.2  2138.3  112.28  2382.9   99.92
  2393.5   94.59    2395   92.59  2557.5   94.59  3391.4   98.05  3884.2  102.67
  4212.5  106.75    4316  110.68    4446  109.16  4818.1   97.04    5014   94.81
  5438.3   98.11  5523.9  103.65  5827.3  125.91    6101  132.52  6329.6  136.57
#Mann= 20 ,-1 , 0
 -3029.7     .05       0 -3022.7     .12       0 -2814.5     .05       0
 -2590.7     .05       0 -2198.2     .12       0 -1827.8     .04       0
 -1339.8     .05       0  -494.3     .04       0  -166.1     .04       0
  1511.2     .04       0  1918.4     .12       0  2393.5     .03       0
  2557.5     .12       0  3391.4     .05       0  3884.2     .12       0
  4212.5     .05       0    4446     .04       0  4818.1     .03       0
  5523.9     .12       0    6101     .04       0
Bank Sta=2393.5,2557.5
XS Rating Curve= 0 ,0
Exp/Cntr=0.3,0.1

Type RM Length L Ch R = 1 ,111378  ,1540,1540,1540
BEGIN DESCRIPTION:
COLETO CREEK 83
END DESCRIPTION:
XS GIS Cut Line= 3
      2560028.76     13479648.32      2554819.79     13474899.74
      2553691.91     13473085.77
#Sta/Elev= 30
 -2571.4  135.74 -2541.7  135.44 -2414.3  134.18 -1782.7  127.91 -1276.3  124.53
 -1059.5  123.48  -758.3  122.14    -636  121.59   116.2  117.79   449.3  111.97
   633.1  115.67  1086.5  110.99  1197.1  109.85  1383.1  106.48    1628   94.84
  3414.7   95.09  3499.3   98.84  3639.2  101.13  3988.4  105.72    4188  104.96
  4384.9  105.48  4498.1  101.32  4572.8   94.72    5013   93.93  5014.5   91.93
  5177.2   93.93  5397.8  101.68  5550.3  105.34  6444.9  136.18  6613.2  136.36
#Mann= 20 ,-1 , 0
 -2571.4     .05       0 -2541.7    .013       0 -2414.3     .05       0
 -1782.7     .04       0 -1276.3     .05       0 -1059.5     .04       0
  -758.3     .05       0    -636     .04       0  1086.5    .013       0
  1197.1     .04       0  1383.1     .05       0    1628     .03       0
  3499.3     .05       0  3639.2     .04       0    4188     .05       0
  4572.8     .03       0    5013     .03       0  5177.2     .03       0
  5397.8     .12       0  5550.3     .05       0
Bank Sta=5013,5177.2
XS Rating Curve= 0 ,0
Exp/Cntr=0.3,0.1

Type RM Length L Ch R = 1 ,109838  ,2033,2033,2033
BEGIN DESCRIPTION:
COLETO CREEK 79
END DESCRIPTION:
XS GIS Cut Line= 4
      2560167.64     13478710.81      2556007.16     13474539.53
      2555366.78     13473378.84       2553882.9     13473016.35
#Sta/Elev= 30
   -1371  136.86 -1266.5  135.95  -397.3  128.63  -357.2  128.01  -159.3  125.39
   -23.9  124.53    66.5  124.24  1067.4  118.04  2036.1  105.47  2205.9  100.03
  2432.1  107.66  2724.9   97.16  2778.6   94.74  4174.3   94.16  4175.8   92.16
  4338.6   94.16  4341.3    97.7  4369.6   99.96  4518.1  105.77  4605.6  104.69
  4728.9   98.19  4811.2   94.41    5261   94.41  5342.4   98.09    5593   98.66
  5695.4  100.79  5972.1  116.78  6388.9  127.39  6949.4  135.01  7373.6  136.45
#Mann= 14 ,-1 , 0
   -1371     .04       0 -1266.5    .013       0  -397.3     .04       0
  -357.2    .013       0  -159.3     .04       0   -23.9     .05       0
    66.5     .04       0  2036.1     .05       0  2724.9     .03       0
  4174.3     .03       0  4338.6     .03       0  4728.9     .03       0
    5593     .04       0  6388.9     .05       0
Bank Sta=4174.3,4338.6
XS Rating Curve= 0 ,0
Exp/Cntr=0.3,0.1