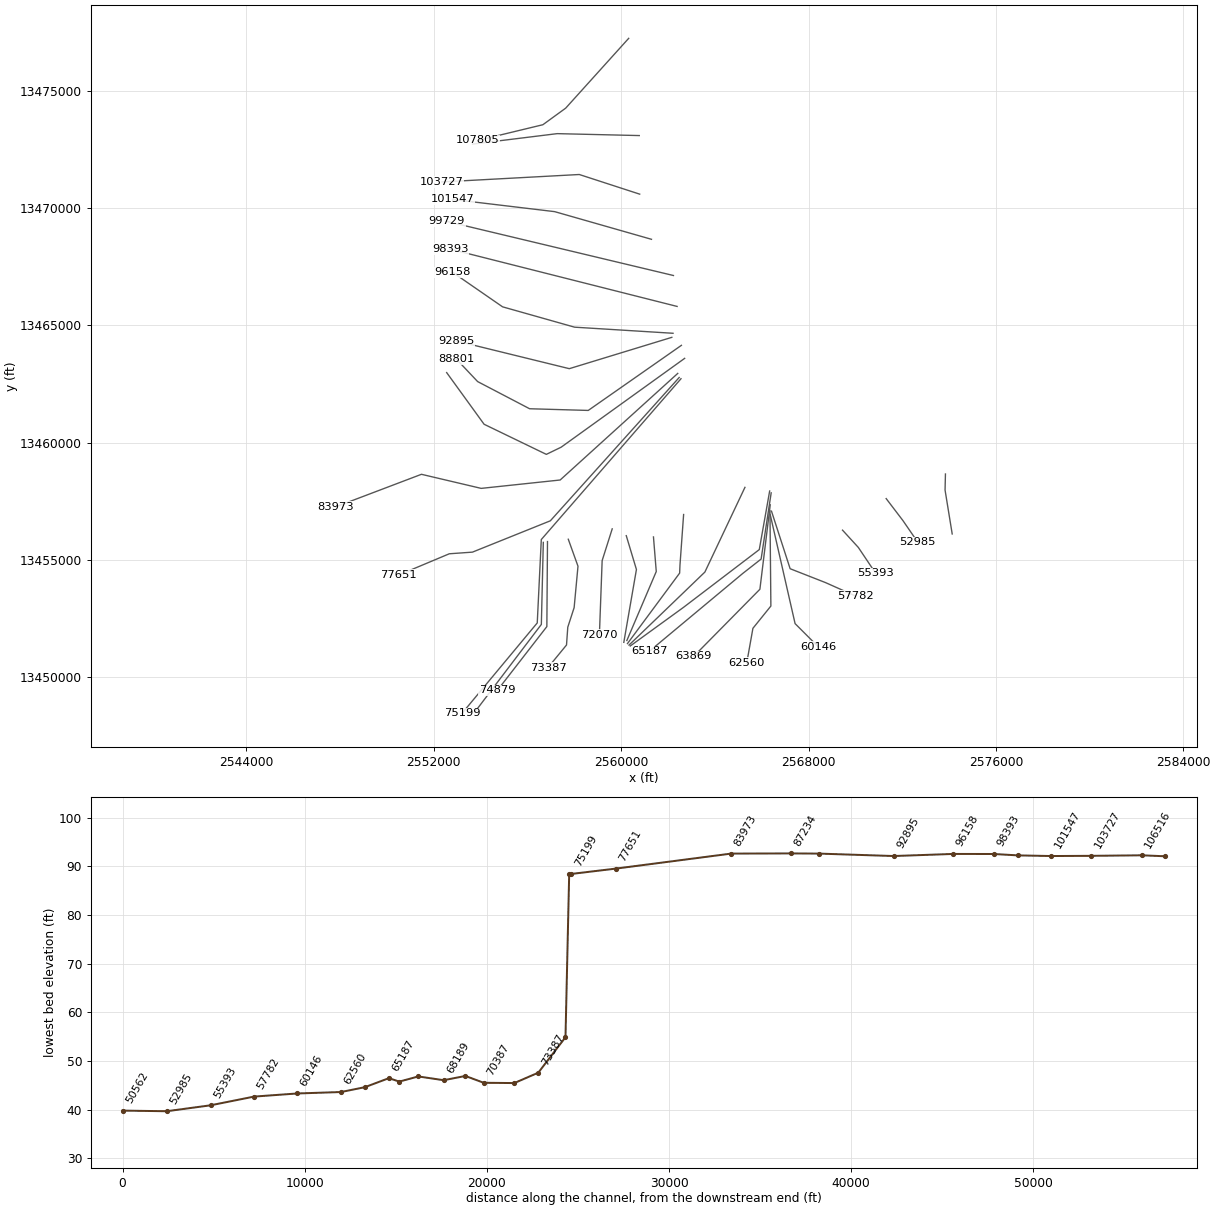
HEC-RAS study COLETO CREEK.prj: COLETO CREEK Base Level Engineering

--- COLETO CREEK.g01 (geometry) --- (continued)

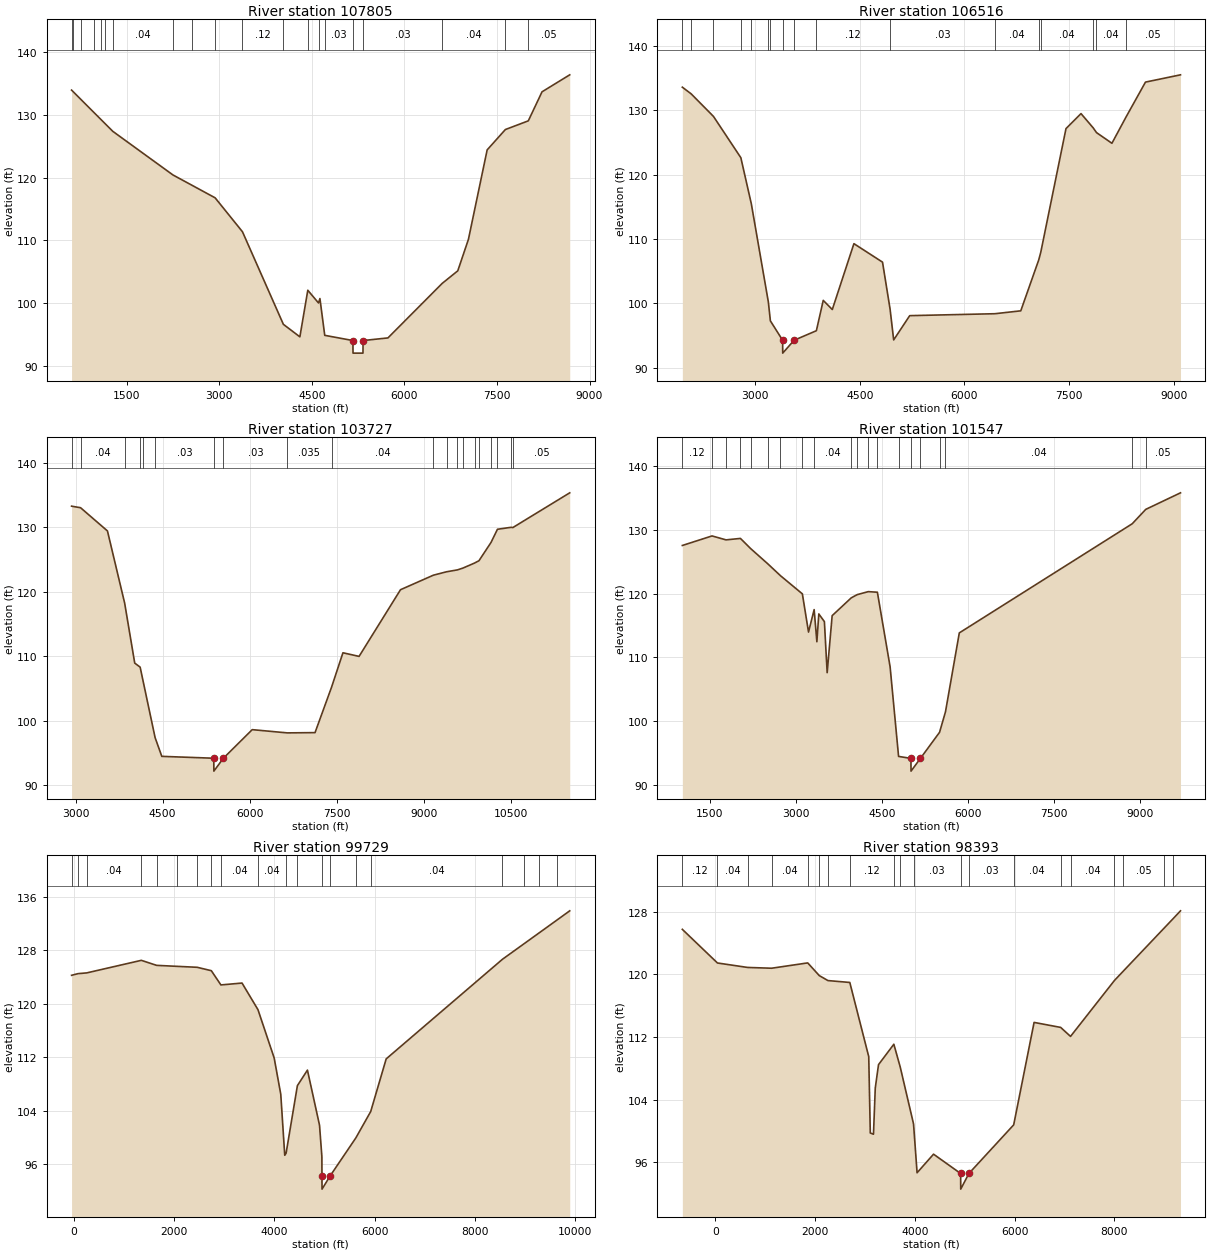
Type RM Length L Ch R = 1 ,107805  ,1289,1289,1289
BEGIN DESCRIPTION:
COLETO CREEK 78
END DESCRIPTION:
XS GIS Cut Line= 4
      2560323.87     13477252.46      2557634.79      13474272.7
      2556660.88     13473565.61      2553882.89     13472894.82
#Sta/Elev= 30
   603.6  133.91   621.3  133.74   763.6  132.34   966.2  130.35  1078.3  129.25
  1151.7  128.53  1272.3  127.35  2246.4  120.42  2552.7  118.79  2930.4  116.78
    3374  111.38  4036.9   96.66  4304.4   94.67  4432.8  102.08  4606.2  100.06
  4629.4  100.76  4707.3   94.91  5164.2   94.08  5165.7   92.08  5327.2   92.08
  5328.7   94.08  5731.9    94.5  6612.3  103.18    6864  105.17  7036.7  110.18
  7340.1   124.4  7635.5  127.64    8007  129.02  8229.8  133.64  8678.7  136.34
#Mann= 20 ,-1 , 0
   603.6     .04       0   621.3    .013       0   763.6     .04       0
   966.2     .05       0  1078.3     .04       0  1151.7     .05       0
  1272.3     .04       0  2246.4     .05       0  2552.7     .04       0
  2930.4     .05       0    3374     .12       0  4036.9     .03       0
  4432.8     .12       0  4606.2      .1       0  4707.3     .03       0
  5164.2     .03       0  5328.7     .03       0  6612.3     .04       0
  7635.5     .05       0    8007     .05       0
Bank Sta=5164.2,5328.7
XS Rating Curve= 0 ,0
Exp/Cntr=0.3,0.1

Type RM Length L Ch R = 1 ,106516  ,2789,2789,2789
BEGIN DESCRIPTION:
COLETO CREEK 90
END DESCRIPTION:
XS GIS Cut Line= 3
      2560775.28     13473103.16        2557273.     13473185.36
      2553658.63     13472738.75
#Sta/Elev= 30
  1954.1  133.58  2080.1  132.55  2400.7  129.04  2793.2  122.63  2943.5  115.47
  3187.8  100.22  3216.9   97.29  3392.4   94.28  3393.9   92.28  3557.1   94.28
  3876.5   95.76  3974.9  100.47    4105   99.05  4415.1  109.28  4825.2  106.41
  4933.8   99.11  4985.2   94.33  5215.3    98.1  6437.6    98.4  6808.2   98.85
  7066.6  106.78    7095  107.94  7456.8  127.15  7672.1  129.48  7846.3  127.27
  7894.2  126.53  8115.5  124.87  8318.5  128.96  8596.9  134.37  9099.2   135.5
#Mann= 17 ,-1 , 0
  1954.1     .04       0  2080.1     .03       0  2400.7     .04       0
  2793.2     .05       0  2943.5     .12       0  3187.8      .1       0
  3216.9     .03       0  3392.4     .03       0  3557.1     .03       0
  3876.5     .12       0  4933.8     .03       0  6437.6     .04       0
  7066.6     .05       0    7095     .04       0  7846.3     .05       0
  7894.2     .04       0  8318.5     .05       0
Bank Sta=3392.4,3557.1
XS Rating Curve= 0 ,0
Exp/Cntr=0.3,0.1

Type RM Length L Ch R = 1 ,103727  ,2180,2180,2180
BEGIN DESCRIPTION:
COLETO CREEK 91
END DESCRIPTION:
XS GIS Cut Line= 3
      2560792.62     13470603.16      2558214.82     13471441.26
      2552355.12     13471123.99
#Sta/Elev= 30
  2931.7  133.25  3086.8  133.01  3549.6  129.41  3846.3   118.2  4019.3  108.92
  4112.7  108.29  4163.4  106.13  4370.3   97.36  4485.5   94.46  5380.7   94.17
  5382.2   92.17    5546   94.17  6042.7    98.6  6646.3    98.1  7124.3   98.14
  7408.6  105.18    7605  110.52  7882.8  109.96  8596.5   120.3  9162.4  122.55
  9389.6  123.08  9575.6  123.37  9673.9  123.66  9870.5  124.43  9947.2  124.79
 10155.3  127.63 10265.8  129.67 10498.8  129.97 10531.9  129.94 11510.6  135.32
#Mann= 20 ,-1 , 0
  2931.7     .05       0  3086.8     .04       0  3846.3     .05       0
  4112.7     .12       0  4163.4     .05       0  4370.3     .03       0
  5380.7     .03       0    5546     .03       0  6646.3    .035       0
  7408.6     .04       0  9162.4    .013       0  9389.6     .05       0
  9575.6     .04       0  9673.9     .05       0  9870.5     .04       0
  9947.2     .05       0 10155.3     .04       0 10265.8     .05       0
 10498.8     .04       0 10531.9     .05       0
Bank Sta=5380.7,5546
XS Rating Curve= 0 ,0
Exp/Cntr=0.3,0.1

Type RM Length L Ch R = 1 ,101547  ,1818,1818,1818
BEGIN DESCRIPTION:
COLETO CREEK 89
END DESCRIPTION:
XS GIS Cut Line= 3
      2561296.12     13468676.07      2557164.15     13469856.63
      2552808.26     13470377.26
#Sta/Elev= 30
  1020.4  127.57  1537.7  129.07  1782.5  128.45  2032.7  128.68  2213.9  127.06
  2518.6  124.62  2729.1  122.84  3112.8  119.97    3220  113.97  3318.1   117.5
  3365.6  112.45  3399.4  116.82  3496.8  115.61    3545  107.59    3632  116.55
  3965.7  119.35  4068.7  119.85  4260.9  120.32  4420.3  120.23  4642.2  108.52
    4790   94.44  5005.3   94.13  5006.8   92.13  5170.7   94.13  5504.4   98.23
  5607.7  101.45  5848.6  113.84  8862.9  130.98  9098.6  133.24  9704.6  135.84
#Mann= 20 ,-1 , 0
  1020.4     .12       0  1537.7     .12       0  1782.5     .12       0
  2032.7     .05       0  2213.9     .05       0  2518.6     .12       0
  2729.1     .04       0  3112.8     .05       0  3318.1     .04       0
  3965.7    .013       0  4068.7     .04       0  4260.9     .05       0
  4420.3     .12       0    4790     .03       0  5005.3     .03       0
  5170.7     .03       0  5504.4     .12       0  5607.7     .04       0
  8862.9    .013       0  9098.6     .05       0
Bank Sta=5005.3,5170.7
XS Rating Curve= 0 ,0
Exp/Cntr=0.3,0.1

Type RM Length L Ch R = 1 ,99729   ,1336,1336,1336
BEGIN DESCRIPTION:
COLETO CREEK 88
END DESCRIPTION:
XS GIS Cut Line= 2
      2562233.59     13467130.94      2552563.44     13469439.97
#Sta/Elev= 30
   -46.4  124.26    82.8  124.51   255.9  124.62  1345.5   126.5  1650.7  125.75
  2058.7   125.6  2460.1  125.46  2742.7  124.95    2934  122.82  3355.7   123.1
  3673.5  119.12  3997.3  111.88  4128.8  106.45  4207.8   97.33  4235.2   97.64
  4460.6  107.75  4660.9  110.07  4901.8  101.84    4949   97.14  4950.5   94.26
    4952   92.26  5115.9   94.26  5626.4   99.92  5923.4  103.87  6232.3  111.75
  8552.9  126.66  8975.7  128.94  9290.8  130.64  9648.1  132.57  9895.6  133.91
#Mann= 20 ,-1 , 0
   -46.4     .12       0    82.8    .013       0   255.9     .04       0
  1345.5     .12       0  1650.7     .12       0  2058.7     .04       0
  2460.1     .05       0  2742.7     .04       0    2934     .04       0
  3673.5     .04       0  4235.2    .013       0  4460.6     .12       0
  4950.5     .05       0  5115.9      .1       0  5626.4     .05       0
  5923.4     .04       0  8552.9     .05       0  8975.7     .04       0
  9290.8     .05       0  9648.1     .05       0
Bank Sta=4950.5,5115.9
XS Rating Curve= 0 ,0
Exp/Cntr=0.3,0.1

Type RM Length L Ch R = 1 ,98393   ,2235,2235,2235
BEGIN DESCRIPTION:
COLETO CREEK 92
END DESCRIPTION:
XS GIS Cut Line= 2
      2562389.87     13465811.49      2552702.37      13468259.4
#Sta/Elev= 30
    -664  125.77    40.2  121.47   644.2   120.9  1126.1   120.8    1851  121.48
  2082.2  119.86  2255.9  119.22  2694.8  118.98  3074.8  109.49  3105.8   99.73
  3169.8   99.57  3205.7  105.48  3270.8  108.47  3578.4  111.08  3706.9  108.15
  3973.4  100.88  4044.4   94.64  4374.4   97.02  4918.2   94.55  4919.7   92.55
  5083.9   94.55  5982.2  100.77  6391.2  113.87  6924.7  113.23  7122.1  112.08
    8004  119.24  8176.2   120.4  8989.3  125.86  9168.3  127.06    9328  128.14
#Mann= 20 ,-1 , 0
    -664     .12       0    40.2     .04       0   644.2    .013       0
  1126.1     .04       0    1851     .12       0  2082.2     .04       0
  2255.9     .05       0  2694.8     .12       0  3578.4     .05       0
  3706.9     .12       0  3973.4     .03       0  4918.2     .03       0
  5083.9     .03       0  5982.2     .04       0  6924.7    .013       0
  7122.1     .04       0    8004     .05       0  8176.2     .05       0
  8989.3    .013       0  9168.3     .04       0
Bank Sta=4918.2,5083.9
XS Rating Curve= 0 ,0
Exp/Cntr=0.3,0.1

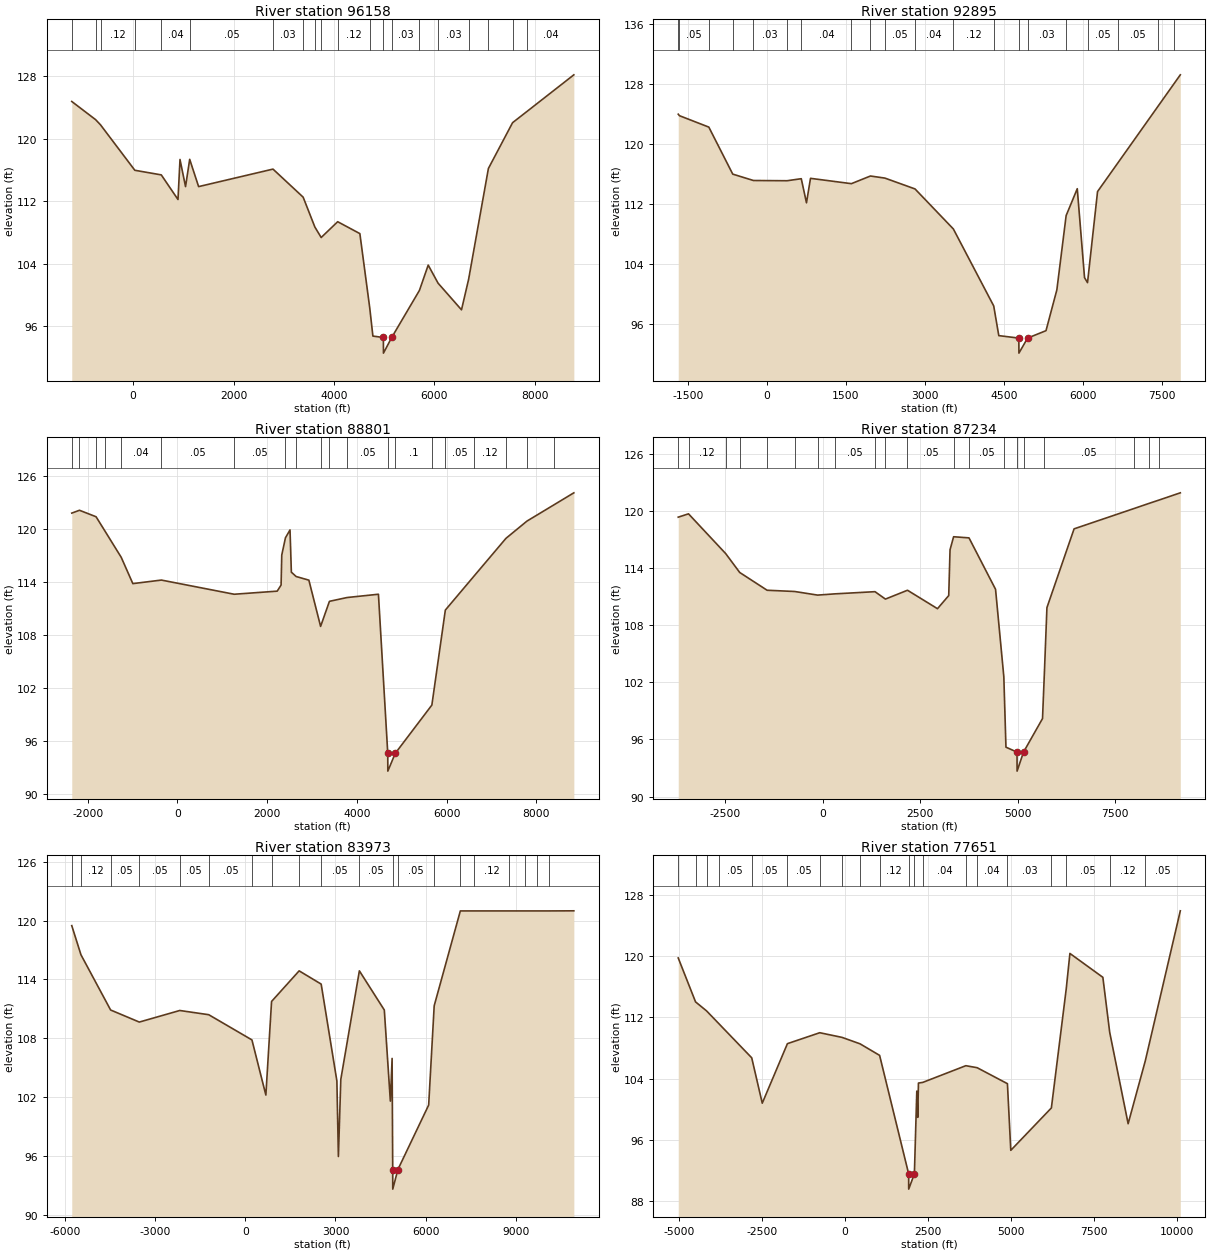
Type RM Length L Ch R = 1 ,96158   ,3263,3263,3263
BEGIN DESCRIPTION:
COLETO CREEK 87
END DESCRIPTION:
XS GIS Cut Line= 4
      2562216.24     13464665.66      2558014.85     13464926.07
      2554941.93     13465794.13      2552806.54     13467269.81
#Sta/Elev= 30
 -1221.7  124.75  -747.6  122.43  -648.9  121.76    34.3  115.95   560.8  115.36
   893.6  112.21   933.7  117.33  1043.9  113.86  1126.7  117.35  1304.4  113.86
  2785.5   116.1  3386.1  112.51  3619.3  108.69  3745.2  107.35  4073.7  109.37
  4515.4  107.85  4711.1    98.4  4774.9   94.74  4983.8   94.56  4985.3   92.56
  5149.5   94.56  5701.4  100.58  5876.5  103.82  6072.7  101.51  6539.4    98.1
  6681.3  102.01  7075.2  116.18  7556.8  122.04  7852.5  123.52  8776.6  128.16
#Mann= 20 ,-1 , 0
 -1221.7     .05       0  -747.6     .12       0  -648.9     .12       0
    34.3     .05       0   560.8     .04       0  1126.7     .05       0
  2785.5     .03       0  3386.1     .12       0  3619.3     .12       0
  3745.2    .013       0  4073.7     .12       0  4711.1     .03       0
  4983.8     .03       0  5149.5     .03       0  5701.4     .05       0
  6072.7     .03       0  6681.3     .05       0  7075.2     .04       0
  7556.8     .05       0  7852.5     .04       0
Bank Sta=4983.8,5149.5
XS Rating Curve= 0 ,0
Exp/Cntr=0.3,0.1

Type RM Length L Ch R = 1 ,92895   ,4094,4094,4094
BEGIN DESCRIPTION:
COLETO CREEK 86
END DESCRIPTION:
XS GIS Cut Line= 3
      2562164.13     13464492.04      2557789.15     13463155.24
      2552980.09     13464335.81
#Sta/Elev= 30
 -1681.4  123.94 -1658.3  123.74 -1100.9  122.22    -647  115.96  -253.9  115.11
   384.4  115.08     653  115.35     752  112.14   828.1   115.4  1603.9  114.69
  1965.7  115.71  2240.9  115.43  2811.2  113.99  3538.8  108.66  4304.7   98.41
  4400.9   94.46  4781.3   94.13  4782.8   92.13  4947.2   94.13  5296.7   95.12
  5502.6  100.55  5678.8  110.44    5890  114.02  6027.8  102.18  6084.5  101.51
  6274.9  113.64  6664.1  117.49  7417.8  124.95  7716.9  127.91  7845.1  129.18
#Mann= 20 ,-1 , 0
 -1681.4     .04       0 -1658.3     .05       0 -1100.9     .12       0
    -647     .05       0  -253.9     .03       0   384.4     .05       0
     653     .04       0  1603.9     .05       0  1965.7     .12       0
  2240.9     .05       0  2811.2     .04       0  3538.8     .12       0
  4304.7     .03       0  4781.3     .03       0  4947.2     .03       0
  5678.8     .12       0  6084.5     .05       0  6664.1     .05       0
  7417.8     .04       0  7716.9    .013       0
Bank Sta=4781.3,4947.2
XS Rating Curve= 0 ,0
Exp/Cntr=0.3,0.1

Type RM Length L Ch R = 1 ,88801   ,1567,1567,1567
BEGIN DESCRIPTION:
COLETO CREEK 85
END DESCRIPTION:
XS GIS Cut Line= 5
      2562573.19     13464150.88      2558597.48     13461373.09
      2556095.49      13461444.8      2553876.78      13462604.6
      2552963.65     13463570.97
#Sta/Elev= 30
   -2353  121.76 -2181.4  122.08 -1811.9  121.35   -1613  119.73 -1251.2  116.77
  -992.3   113.8  -356.1   114.2  1265.2   112.6  2224.3  112.95  2310.6  113.64
  2325.5  117.02  2407.6  118.97  2509.5  119.86  2539.5  115.09  2646.7   114.6
  2929.6  114.19  3191.1  108.97  3387.9   111.8  3781.5  112.23  4479.4   112.6
  4687.3   94.63  4688.8   92.63  4853.4   94.63    5670  100.09  5969.9  110.81
  6619.4  114.71  7320.5  118.91  7789.1  120.86  8391.6   122.7  8833.1  124.05
#Mann= 20 ,-1 , 0
   -2353     .04       0 -2181.4     .04       0 -1811.9     .05       0
   -1613     .12       0 -1251.2     .04       0  -356.1     .05       0
  1265.2     .05       0  2407.6    .013       0  2646.7     .04       0
  3191.1     .04       0  3387.9    .013       0  3781.5     .05       0
  4687.3     .03       0  4853.4      .1       0    5670     .12       0
  5969.9     .05       0  6619.4     .12       0  7320.5     .12       0
  7789.1     .12       0  8391.6     .05       0
Bank Sta=4687.3,4853.4
XS Rating Curve= 0 ,0
Exp/Cntr=0.3,0.1

Type RM Length L Ch R = 1 ,87234   ,3261,3261,3261
BEGIN DESCRIPTION:
COLETO CREEK 96
END DESCRIPTION:
XS GIS Cut Line= 5
      2562712.06     13463595.31      2557441.93     13459804.55
      2556809.29     13459498.09      2554153.04     13460782.82
      2552555.84     13462987.65
#Sta/Elev= 30
 -3700.5  119.39 -3437.2  119.74 -2482.9  115.55 -2124.6  113.57 -1422.7   111.7
  -718.4  111.57  -128.6  111.19   316.4  111.32  1341.9  111.55  1609.6  110.77
    2175   111.7  2944.2  109.76  3232.2  111.14  3265.9  115.96  3357.2  117.33
  3751.9  117.21  4432.2   111.8  4644.3   102.6  4698.8   95.19  4982.6   94.67
  4984.1   92.67  5148.8   94.67    5636    98.2    5686  103.22    5749  109.87
  6444.9  118.16  7967.9  120.28  8367.2  120.84    8630   121.2  9167.5  121.95
#Mann= 20 ,-1 , 0
 -3700.5     .04       0 -3437.2     .12       0 -2482.9     .04       0
 -2124.6     .04       0 -1422.7     .05       0  -718.4     .05       0
  -128.6     .03       0   316.4     .05       0  1341.9     .05       0
  1609.6     .03       0    2175     .05       0  3357.2     .04       0
  3751.9     .05       0  4644.3     .03       0  4982.6     .03       0
  5148.8     .03       0    5686     .05       0  7967.9     .12       0
  8367.2     .05       0    8630     .05       0
Bank Sta=4982.6,5148.8
XS Rating Curve= 0 ,0
Exp/Cntr=0.3,0.1

Type RM Length L Ch R = 1 ,83973   ,6322,6322,6322
BEGIN DESCRIPTION:
COLETO CREEK 97
END DESCRIPTION:
XS GIS Cut Line= 5
      2562416.93     13462952.96      2557399.57     13458404.34
      2554028.98     13458046.57      2551479.43      13458647.4
       2547815.5     13457256.66
#Sta/Elev= 30
 -5769.7  119.49   -5464  116.52 -4477.2  110.89 -3523.1  109.66 -2177.4  110.84
 -1213.9  110.41   223.1  107.84   686.5  102.22   876.1  111.76  1793.2  114.88
  2526.2  113.53  3048.6  103.66  3098.9   95.96  3179.3  103.82  3797.1  114.88
  4626.2  110.89  4827.7   101.6  4885.4  105.95  4905.7   94.63  4907.2   92.63
  5078.5   94.63  6101.7   101.2  6285.4  111.32    7155  120.99  7601.2  120.99
  8777.8  120.99  9319.9  120.99    9699  120.99   10101  120.99 10930.5     121
#Mann= 20 ,-1 , 0
 -5769.7     .05       0   -5464     .12       0 -4477.2     .05       0
 -3523.1     .05       0 -2177.4     .05       0 -1213.9     .05       0
   223.1     .12       0   876.1     .04       0  1793.2     .04       0
  2526.2     .05       0  3797.1     .05       0  4905.7     .03       0
  5078.5     .05       0  6285.4     .12       0    7155     .05       0
  7601.2     .12       0  8777.8     .05       0  9319.9     .04       0
    9699     .04       0   10101     .04       0
Bank Sta=4905.7,5078.5
XS Rating Curve= 0 ,0
Exp/Cntr=0.3,0.1

Type RM Length L Ch R = 1 ,77651   ,2452,2452,2452
BEGIN DESCRIPTION:
COLETO CREEK 98
END DESCRIPTION:
XS GIS Cut Line= 5
      2562478.18     13462778.65      2556979.62      13456662.5
      2553654.97     13455325.69       2552668.8      13455255.8
       2550511.6     13454350.46
#Sta/Elev= 30
 -5025.2  119.76 -4503.2  114.02 -4170.3  112.84 -3806.6   111.2 -2809.9  106.71
 -2492.2  100.78 -1733.6  108.56  -758.4  109.99   -86.4  109.38   455.1  108.54
  1045.6  107.03  1921.1   91.55  1922.6   89.55  2094.1   91.55  2166.9  102.36
  2195.3   98.93  2216.2  103.41  2348.3   103.5    3645  105.68  3985.3  105.42
  4898.8  103.33  5000.3   94.62  6223.9  100.16    6671  115.69  6782.6  120.35
    7776  117.23  7982.3  110.04  8537.8    98.1  9054.3   106.3 10110.7  125.92
#Mann= 20 ,-1 , 0
 -5025.2     .05       0 -4503.2     .04       0 -4170.3     .04       0
 -3806.6     .05       0 -2809.9     .05       0 -1733.6     .05       0
  -758.4     .05       0   -86.4     .04       0   455.1     .05       0
  1045.6     .12       0  1921.1     .03       0  2094.1     .12       0
  2348.3     .04       0    3645     .04       0  3985.3     .04       0
  4898.8     .03       0  6223.9     .12       0    6671     .05       0
  7982.3     .12       0  9054.3     .05       0
Bank Sta=1921.1,2094.1
XS Rating Curve= 0 ,0
Exp/Cntr=0.3,0.1

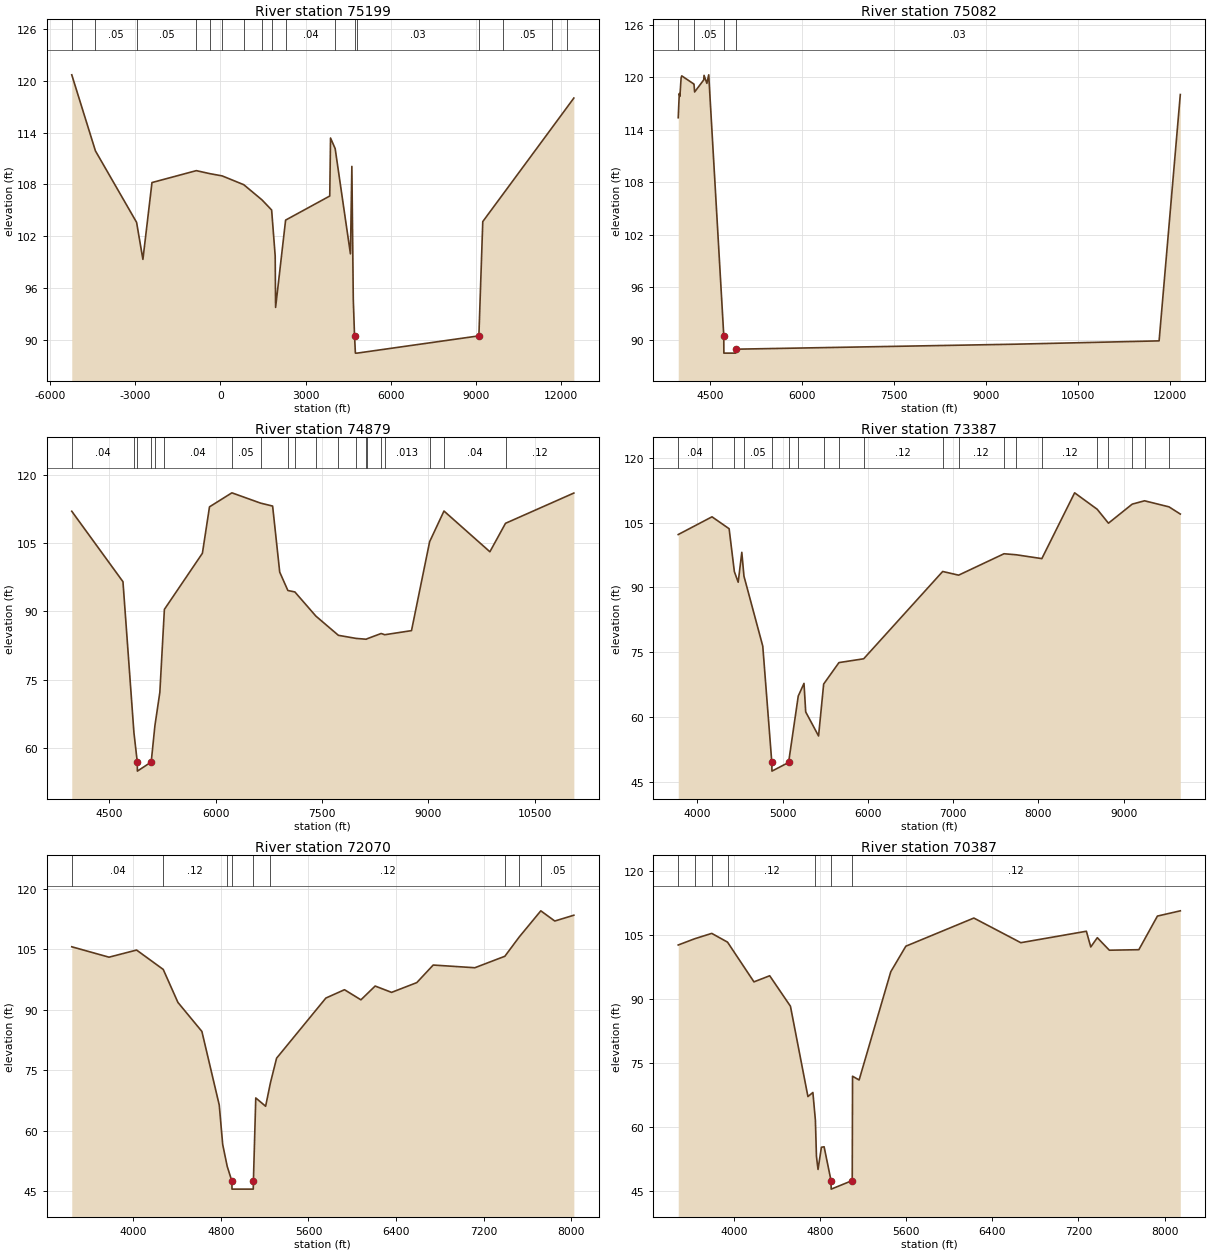
Type RM Length L Ch R = 1 ,75199   ,117,117,117
BEGIN DESCRIPTION:
COLETO CREEK 95
END DESCRIPTION:
XS GIS Cut Line= 4
      2562556.28     13462726.54      2556594.36     13455863.85
      2556421.46     13452304.71      2553210.09     13448444.77
#Sta/Elev= 30
 -5231.6  120.69 -4398.7  111.88 -2949.6   103.6   -2727   99.31   -2408  108.21
  -846.9  109.59  -367.2  109.24    64.6  108.98   824.2  107.96  1465.7   106.2
  1804.6  105.03  1929.7    99.7    1944   93.75  2296.4  103.86  3850.7  106.65
    3878  113.37  4041.2  112.14  4578.8   99.95  4628.9  110.08  4678.9   94.68
  4723.1   90.45  4733.4   89.77  4753.2   88.45  4813.6   88.45  9100.7   90.45
  9237.6  103.69  9962.2  106.92   11681  114.59 12189.4  116.86 12443.6     118
#Mann= 17 ,-1 , 0
 -5231.6     .05       0 -4398.7     .05       0 -2949.6     .05       0
  -846.9     .05       0  -367.2     .04       0    64.6     .05       0
   824.2     .12       0  1465.7     .05       0  1804.6     .12       0
  2296.4     .04       0  4041.2     .05       0  4733.4     .03       0
  4813.6     .03       0  9100.7     .03       0  9962.2     .05       0
   11681    .013       0 12189.4    .013       0
Bank Sta=4723.1,9100.7
XS Rating Curve= 0 ,0
Exp/Cntr=0.3,0.1

Type RM Length L Ch R = 1 ,75082   ,203,203,203
BEGIN DESCRIPTION:
COLETO CREEK 93
END DESCRIPTION:
XS GIS Cut Line= 3
      2556680.01     13455742.04      2556596.49     13452241.19
      2553763.52     13448509.95
#Sta/Elev= 19
  3982.7  115.35  3999.7  118.11  4009.7  117.79  4029.7  119.91  4039.8  120.13
  4237.6   119.2  4239.8  119.19  4249.8  118.29  4398.6  119.67  4403.6  120.19
  4449.9  119.28  4479.9  120.25  4725.2   90.45  4726.7   88.45  4919.9   88.45
  4921.4    88.9  9474.8   89.47 11823.6   89.85 12169.4     118
#Mann= 4 ,-1 , 0
  3982.7    .013       0  4237.6     .05       0  4725.2     .05       0
  4921.4     .03       0
Bank Sta=4725.2,4921.4
XS Rating Curve= 0 ,0
Exp/Cntr=0.3,0.1

Type RM Length L Ch R = 1 ,74879   ,1492,1492,1492
BEGIN DESCRIPTION:
COLETO CREEK 94
END DESCRIPTION:
XS GIS Cut Line= 3
      2556858.45     13455776.74      2556831.27     13452148.45
      2554716.21     13449422.57
#Sta/Elev= 30
  3973.4  111.99  4695.2   96.51  4849.8   63.34  4897.1   56.89  4898.6   54.89
  5093.3   56.89  5145.7   64.89  5215.2    72.2  5279.3   90.43  5815.2  102.76
  5915.2  112.96  6230.9  116.04  6635.1  113.78  6805.2  113.13  6905.2   98.62
  7020.1   94.58  7118.8   94.26  7414.7   88.96  7732.6   84.73  7983.1   84.05
  8125.5   83.87  8137.8   83.98  8335.6   85.13  8386.2   84.86  8763.2   85.76
  9018.8   105.3  9221.1  112.04  9868.4  103.09 10088.5  109.34   11052  115.99
#Mann= 20 ,-1 , 0
  3973.4     .04       0  4849.8      .1       0  4897.1     .05       0
  5093.3      .1       0  5145.7     .03       0  5279.3     .04       0
  6230.9     .05       0  6635.1     .04       0  7020.1     .05       0
  7118.8     .03       0  7414.7    .013       0  7732.6     .03       0
  7983.1    .013       0  8125.5     .04       0  8137.8    .013       0
  8335.6     .04       0  8386.2    .013       0  9018.8     .05       0
  9221.1     .04       0 10088.5     .12       0
Bank Sta=4897.1,5093.3
XS Rating Curve= 0 ,0
Exp/Cntr=0.3,0.1

Type RM Length L Ch R = 1 ,73387   ,1317,1317,1317
BEGIN DESCRIPTION:
COLETO CREEK 32
END DESCRIPTION:
XS GIS Cut Line= 6
       2557746.1     13455876.56      2558159.94     13454724.85
      2557995.65     13452957.77      2557724.38     13452122.27
      2557670.13     13451362.72      2556878.05     13450397.03
#Sta/Elev= 30
  3776.2  102.23  4172.2  106.32  4372.9  103.57  4434.3   93.67  4479.2   91.22
  4521.7   98.12  4546.8   92.63  4767.5   76.46  4873.5    49.6    4875    47.6
  5070.3    49.6  5183.6   64.94  5250.9   67.86    5271   61.27  5421.7   55.72
  5481.6   67.71  5660.8   72.66  5950.8   73.54  6877.2    93.7  7064.2   92.85
  7596.3   97.79  7738.5   97.56  8039.9   96.67  8424.4  111.86  8689.2  108.06
    8821  104.85  9099.5  109.25  9244.3  110.02  9530.8  108.62  9663.6  106.96
#Mann= 20 ,-1 , 0
  3776.2     .04       0  4172.2     .03       0  4434.3     .04       0
  4546.8     .05       0  4873.5     .05       0  5070.3     .05       0
  5183.6      .1       0  5481.6     .12       0  5660.8     .04       0
  5950.8     .12       0  6877.2     .05       0  7064.2     .12       0
  7596.3     .05       0  7738.5     .12       0  8039.9     .12       0
  8689.2     .05       0    8821     .05       0  9099.5     .12       0
  9244.3     .05       0  9530.8     .04       0
Bank Sta=4873.5,5070.3
XS Rating Curve= 0 ,0
Exp/Cntr=0.3,0.1

Type RM Length L Ch R = 1 ,72070   ,1683,1683,1683
BEGIN DESCRIPTION:
COLETO CREEK 31
END DESCRIPTION:
XS GIS Cut Line= 3
      2559620.76     13456319.34      2559191.06     13454965.14
      2559073.87     13451801.05
#Sta/Elev= 30
  3437.4  105.58  3777.7     103  4029.5  104.77  4273.1   99.96  4407.2   91.78
  4626.2   84.58  4784.8   66.32  4816.3   56.53  4857.4   51.12  4899.9   47.46
  4901.4   45.46  5095.4   45.46  5096.9   47.46  5118.5   68.08  5208.5   66.02
  5252.6   71.86  5308.6   77.94  5758.9   92.86    5929   94.93  6079.1   92.42
  6209.2   95.84  6359.3   94.27  6589.5   96.69  6739.6  101.05  7119.8  100.38
  7394.3  103.23    7525     108  7722.6   114.5  7850.3  111.97  8024.4  113.41
#Mann= 9 ,-1 , 0
  3437.4     .04       0  4273.1     .12       0  4857.4      .1       0
  4899.9     .05       0  5096.9      .1       0  5252.6     .12       0
  7394.3     .05       0    7525     .03       0  7722.6     .05       0
Bank Sta=4899.9,5096.9
XS Rating Curve= 0 ,0
Exp/Cntr=0.3,0.1

Type RM Length L Ch R = 1 ,70387   ,1003,1003,1003
BEGIN DESCRIPTION:
COLETO CREEK 30
END DESCRIPTION:
XS GIS Cut Line= 3
      2560220.05     13456028.48      2560654.07     13454585.37
      2560115.54     13451475.52
#Sta/Elev= 30
  3482.7  102.67  3634.1  104.12  3793.8  105.39  3940.5  103.34    4186   94.04
  4332.2   95.47  4524.8   88.34  4687.2   67.19  4733.3   68.14  4756.6   61.66
  4766.4   53.19  4781.2   50.13  4812.5   55.33  4837.6   55.43  4901.7   47.52
  4903.2   45.52  5098.7   47.52  5101.7   71.95  5162.6   71.07  5456.9   96.42
  5596.7  102.39  6228.2  108.98  6664.6  103.21  7273.5  105.89  7314.1  102.21
    7375  104.38  7486.7  101.45  7760.7  101.57  7933.2  109.44  8145.8  110.67
#Mann= 7 ,-1 , 0
  3482.7     .05       0  3634.1     .12       0  3793.8     .05       0
  3940.5     .12       0  4756.6      .1       0  4901.7     .05       0
  5098.7     .12       0
Bank Sta=4901.7,5098.7
XS Rating Curve= 0 ,0
Exp/Cntr=0.3,0.1

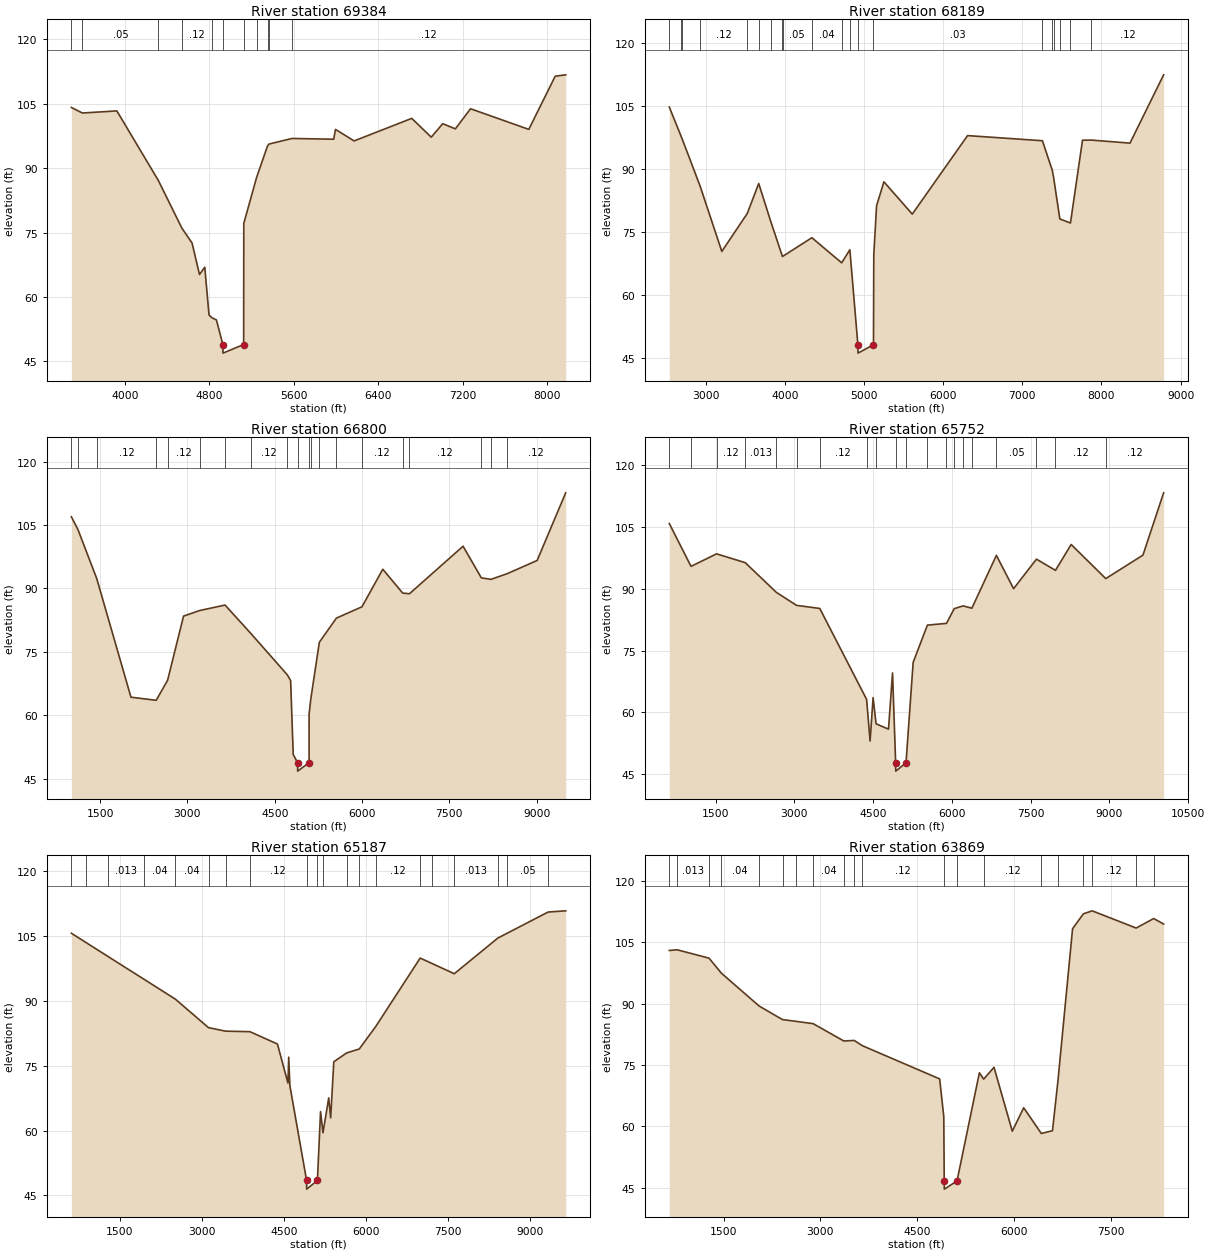
Type RM Length L Ch R = 1 ,69384   ,1195,1195,1195
BEGIN DESCRIPTION:
COLETO CREEK 29
END DESCRIPTION:
XS GIS Cut Line= 3
      2561381.06      13455974.3      2561500.43     13454498.57
      2560245.74     13451553.66
#Sta/Elev= 30
  3493.1  104.12  3597.4  102.83  3923.8  103.32  4316.3   87.14  4539.9   76.02
  4636.1   72.56  4706.4   65.22  4756.5   66.93  4796.6   55.81  4822.4   55.19
  4866.9   54.64  4927.6   48.92  4929.1   46.92  5124.6   48.92    5126   77.12
  5247.3   87.83  5350.6   95.14    5365    95.6    5582    96.9  5977.6   96.73
  5994.6   99.01  6170.8   96.33  6716.7  101.58  6901.5    97.2  7010.2  100.34
  7129.7   99.14  7273.7  103.82  7825.4   99.02  8075.4   111.4  8174.7  111.72
#Mann= 11 ,-1 , 0
  3493.1     .04       0  3597.4     .05       0  4316.3     .04       0
  4539.9     .12       0  4822.4     .03       0  4927.6     .03       0
  5124.6     .03       0  5247.3     .05       0  5350.6     .12       0
    5365     .05       0    5582     .12       0
Bank Sta=4927.6,5124.6
XS Rating Curve= 0 ,0
Exp/Cntr=0.3,0.1

Type RM Length L Ch R = 1 ,68189   ,1389,1389,1389
BEGIN DESCRIPTION:
COLETO CREEK 28
END DESCRIPTION:
XS GIS Cut Line= 4
      2562667.62     13456931.26      2562511.38      13454756.8
      2562497.93     13454430.76      2560271.78     13451423.45
#Sta/Elev= 30
  2537.4   104.8  2680.1   98.13  2700.8   97.16  2927.9   85.87  3201.1   70.33
  3522.4   79.38  3667.7   86.55  3819.6   77.49  3966.8   69.15  3969.7   69.14
  4339.3   73.61  4715.9   67.61  4819.6   70.73    4921   48.05  4922.5   46.05
  5118.1   48.05  5121.9   69.54  5157.3   81.24    5250   86.96  5608.2   79.24
  6307.6   97.99  7253.8   96.76  7379.1   89.64  7394.9   87.99  7473.6   78.09
  7607.9   77.12  7760.1   96.89  7872.5   96.92  8360.5   96.19  8785.4   112.5
#Mann= 20 ,-1 , 0
  2537.4     .05       0  2680.1     .12       0  2700.8     .05       0
  2927.9     .12       0  3522.4     .05       0  3667.7     .12       0
  3819.6     .05       0  3966.8     .04       0  3969.7     .05       0
  4339.3     .04       0  4715.9     .12       0  4819.6     .03       0
    4921     .03       0  5118.1     .03       0  7253.8     .03       0
  7379.1     .05       0  7394.9     .03       0  7473.6     .05       0
  7607.9     .03       0  7872.5     .12       0
Bank Sta=4921,5118.1
XS Rating Curve= 0 ,0
Exp/Cntr=0.3,0.1

Type RM Length L Ch R = 1 ,66800   ,1048,1048,1048
BEGIN DESCRIPTION:
COLETO CREEK 27
END DESCRIPTION:
XS GIS Cut Line= 3
      2565284.82     13458090.16        2563575.       13454475.
      2560337.77     13451359.21
#Sta/Elev= 30
  1006.6  106.94  1119.6  103.93  1443.3    92.3    2030    64.3  2463.8   63.56
  2659.5    68.3  2933.7   83.47  3212.8   84.79  3646.9   86.08  4096.8   79.26
    4717   69.57  4773.4   68.22  4817.7   50.75    4893   48.82  4894.5   46.82
  5090.2   48.82  5090.5    60.3  5119.9   63.87  5266.4   77.27  5559.4   82.99
  5998.8   85.67  6356.5   94.54  6698.2   88.92  6813.8   88.74  7735.7   99.99
  8049.6   92.51    8216   92.16  8489.1   93.47  9008.6   96.62  9498.8  112.61
#Mann= 20 ,-1 , 0
  1006.6    .013       0  1119.6    .013       0  1443.3     .12       0
  2463.8     .05       0  2659.5     .12       0  3212.8    .013       0
  3646.9     .12       0  4096.8     .12       0    4717     .03       0
    4893     .03       0  5090.2     .03       0  5119.9    .013       0
  5266.4     .12       0  5559.4     .12       0  5998.8     .12       0
  6698.2     .05       0  6813.8     .12       0  8049.6     .03       0
    8216     .03       0  8489.1     .12       0
Bank Sta=4893,5090.2
XS Rating Curve= 0 ,0
Exp/Cntr=0.3,0.1

Type RM Length L Ch R = 1 ,65752   ,565,565,565
BEGIN DESCRIPTION:
Mapping XS 7be97e34
END DESCRIPTION:
XS GIS Cut Line= 4
      2566339.51     13457933.93      2565896.79     13455433.89
      2562667.63     13452972.95      2560389.96     13451320.02
#Sta/Elev= 30
   618.2  105.89  1031.8   95.49  1518.9   98.53    2064   96.39  2655.4   89.19
  3040.8   86.02  3483.5   85.27  4375.2   63.19  4441.8   53.07  4499.1   63.61
  4555.2   57.25  4792.2   55.96  4869.3    69.6  4928.5   47.76    4930   45.76
  5125.8   47.76  5262.1   72.18  5533.1   81.22  5896.1   81.64  6043.9   85.22
  6213.1   85.89  6380.1   85.33  6846.9   98.16  7174.5   90.07  7610.5   97.24
  7972.1   94.52  8270.6   100.8  8930.1   92.52  9637.9   98.22 10031.4  113.35
#Mann= 20 ,-1 , 0
   618.2     .04       0  1031.8     .12       0  1518.9     .12       0
    2064    .013       0  2655.4     .04       0  3040.8    .013       0
  3483.5     .12       0  4375.2     .05       0  4555.2     .12       0
  4928.5     .05       0  5125.8     .03       0  5533.1     .12       0
  5896.1     .12       0  6043.9    .013       0  6213.1     .12       0
  6380.1    .013       0  6846.9     .05       0  7610.5     .12       0
  7972.1     .12       0  8930.1     .12       0
Bank Sta=4928.5,5125.8
XS Rating Curve= 0 ,0
Exp/Cntr=0.3,0.1

Type RM Length L Ch R = 1 ,65187   ,1318,1318,1318
BEGIN DESCRIPTION:
COLETO CREEK 26
END DESCRIPTION:
XS GIS Cut Line= 4
       2566404.6     13457855.73      2565974.92     13455030.24
      2565193.67     13454418.26      2561210.88     13451099.28
#Sta/Elev= 30
   611.6  105.52     882  103.36  1273.9  100.22  1939.6    94.9  2513.2   90.31
    3118   83.74    3430   82.93  3874.8   82.81  4377.9   79.96  4569.7   70.96
  4584.1   76.93  4604.9   70.36  4910.8   48.47  4912.3   46.47  5108.6   48.47
  5165.9   64.36  5210.3   59.47  5315.6   67.53  5350.8   62.92    5408   75.86
  5642.2    77.9    5874   78.82    6175   84.01  6986.9    99.8  7199.1   98.57
  7609.7   96.18  8406.8  104.42  8566.2  105.46  9325.2  110.42  9646.4   110.7
#Mann= 20 ,-1 , 0
   611.6     .04       0     882    .013       0  1273.9    .013       0
  1939.6     .04       0  2513.2     .04       0    3118    .075       0
    3430     .04       0  3874.8     .12       0  4910.8     .05       0
  5108.6      .1       0  5210.3     .03       0  5642.2     .12       0
    5874     .03       0    6175     .12       0  6986.9     .05       0
  7199.1    .013       0  7609.7    .013       0  8406.8    .013       0
  8566.2     .05       0  9325.2     .12       0
Bank Sta=4910.8,5108.6
XS Rating Curve= 0 ,0
Exp/Cntr=0.3,0.1

Type RM Length L Ch R = 1 ,63869   ,1309,1309,1309
BEGIN DESCRIPTION:
COLETO CREEK 25
END DESCRIPTION:
XS GIS Cut Line= 3
      2566364.25     13457345.39      2565922.83     13453741.18
      2563098.68     13450877.98
#Sta/Elev= 30
   660.6     103     782  103.17  1275.9  101.12  1467.5   97.44  2051.3   89.41
  2413.1   86.09  2614.9   85.68  2887.6    85.1  3361.9   80.86  3524.1   80.99
  3647.8   79.72  4846.2   71.58  4909.8   62.38    4917   46.62  4918.5   44.62
  5114.8   46.62  5461.3   73.08  5527.5   71.53  5687.6   74.42  5970.5   58.79
  6147.2   64.52  6420.2   58.23  6592.7   58.91  6676.7   70.99  6903.9  108.32
  7071.3  111.97  7207.4   112.7  7887.9  108.49  8160.1  110.81  8313.4  109.47
#Mann= 20 ,-1 , 0
   660.6    .013       0     782    .013       0  1275.9    .013       0
  1467.5     .04       0  2051.3     .04       0  2413.1     .05       0
  2614.9    .075       0  2887.6     .04       0  3361.9     .12       0
  3524.1    .013       0  3647.8     .12       0    4917     .03       0
  5114.8     .12       0  5527.5     .12       0  6420.2      .1       0
  6676.7     .12       0  7071.3    .013       0  7207.4     .12       0
  7887.9    .013       0  8160.1     .12       0
Bank Sta=4917,5114.8
XS Rating Curve= 0 ,0
Exp/Cntr=0.3,0.1

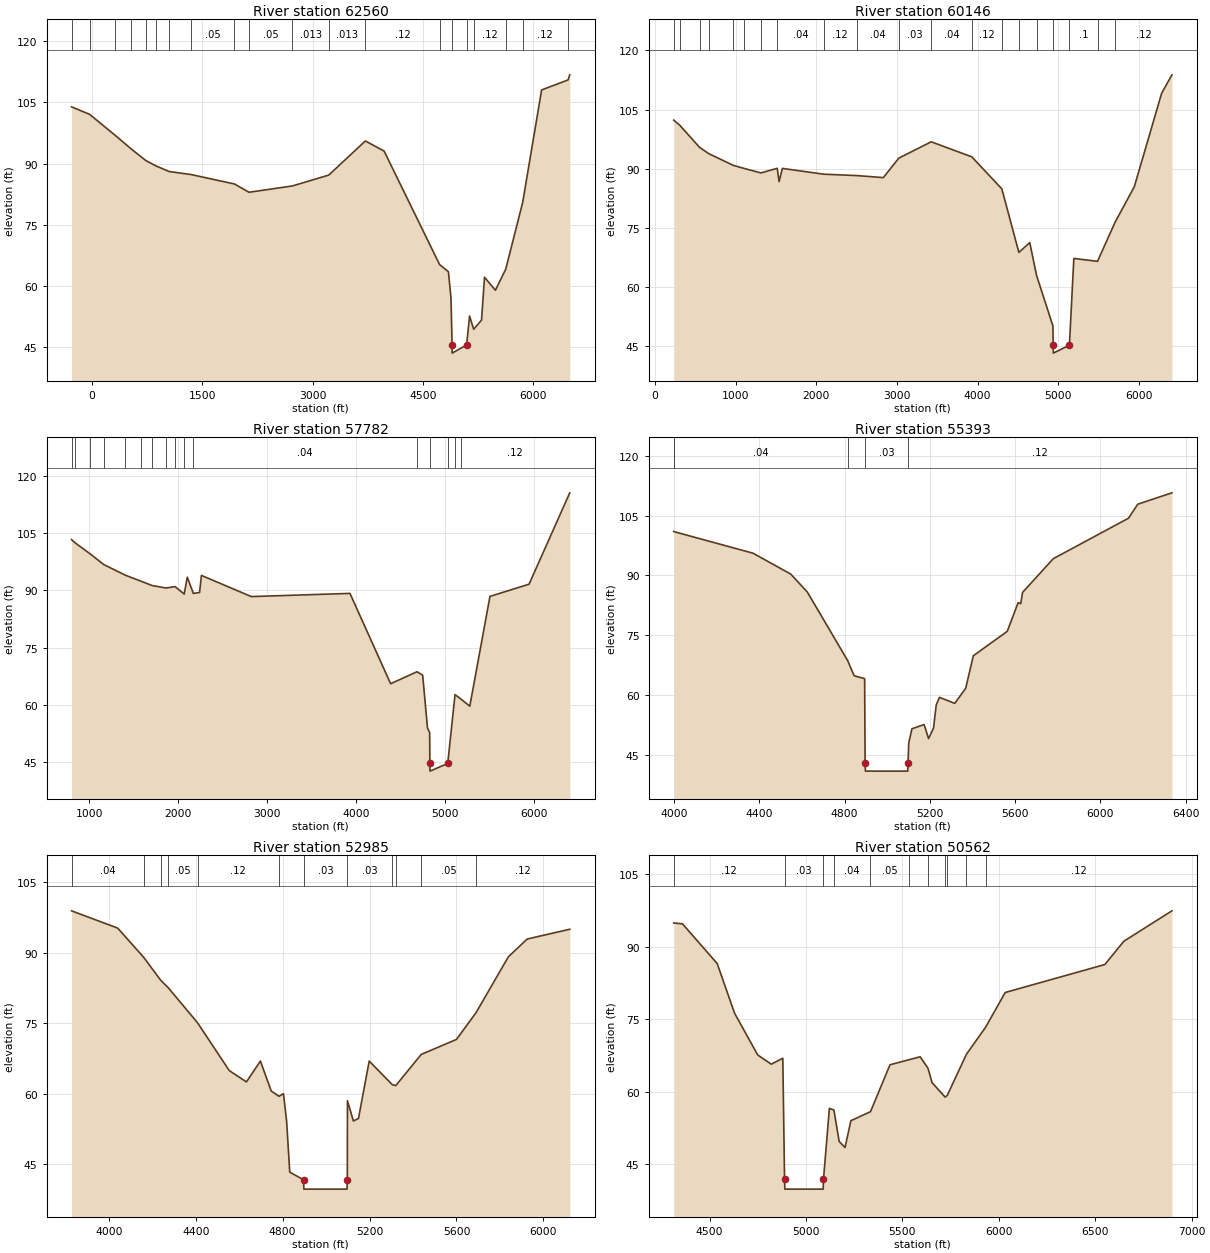
Type RM Length L Ch R = 1 ,62560   ,2414,2414,2414
BEGIN DESCRIPTION:
COLETO CREEK 24
END DESCRIPTION:
XS GIS Cut Line= 4
      2566352.52     13457087.49      2566391.58     13453025.03
        2565625.       13452075.      2565362.93     13450603.14
#Sta/Elev= 30
  -278.8  103.91   -34.2  102.09   316.5   96.91     533    93.6   733.2   90.75
   867.5   89.46  1050.8   88.07  1346.3   87.34    1938   85.03  2135.2      83
  2726.8   84.55  3219.9    87.2  3718.8   95.56  3973.8   93.08  4727.9   65.32
  4848.6   63.54  4883.8   57.12  4898.4   45.62  4899.9   43.62  5096.3   45.62
  5136.6   52.71  5192.4   49.47  5299.1    51.7  5339.8    62.2  5488.3   59.01
  5628.7   64.18  5859.1   80.51  6116.9  108.05  6476.3   110.5  6499.6  111.75
#Mann= 20 ,-1 , 0
  -278.8    .013       0   -34.2     .04       0   316.5     .04       0
     533     .04       0   733.2    .013       0   867.5     .04       0
  1050.8     .05       0  1346.3     .05       0    1938     .05       0
  2135.2     .05       0  2726.8    .013       0  3219.9    .013       0
  3718.8     .12       0  4727.9     .05       0  4898.4     .05       0
  5096.3     .05       0  5192.4     .12       0  5628.7     .05       0
  5859.1     .12       0  6476.3     .12       0
Bank Sta=4898.4,5096.3
XS Rating Curve= 0 ,0
Exp/Cntr=0.3,0.1

Type RM Length L Ch R = 1 ,60146   ,2364,2364,2364
BEGIN DESCRIPTION:
COLETO CREEK 23
END DESCRIPTION:
XS GIS Cut Line= 3
      2566365.55     13456918.25        2567425.       13452275.
        2568425.       13451275.
#Sta/Elev= 30
   233.3  102.36   309.8  101.01   553.4   95.46   667.3   93.86   972.2   90.89
  1110.2   90.09  1315.1   88.98  1516.1   90.15  1539.3   86.78  1580.3   90.12
  2090.7   88.66  2504.3    88.3  2831.7   87.79  3023.9   92.73    3426   96.86
  3928.7   93.05    4301   84.94  4512.5   68.83  4647.1   71.33  4732.8   62.93
  4934.3   50.22  4937.7   45.32  4939.2   43.32    5139   45.32  5193.9   67.31
  5487.5   66.58  5707.6   76.58  5943.4   85.46  6282.8  109.17  6410.1  113.83
#Mann= 20 ,-1 , 0
   233.3    .013       0   309.8     .04       0   553.4     .05       0
   667.3     .04       0   972.2     .04       0  1110.2    .013       0
  1315.1     .05       0  1516.1     .04       0  2090.7     .12       0
  2504.3     .04       0  3023.9     .03       0    3426     .04       0
  3928.7     .12       0    4301     .04       0  4512.5     .05       0
  4732.8     .03       0  4937.7     .05       0    5139      .1       0
  5487.5     .05       0  5707.6     .12       0
Bank Sta=4937.7,5139
XS Rating Curve= 0 ,0
Exp/Cntr=0.3,0.1

Type RM Length L Ch R = 1 ,57782   ,2389,2389,2389
BEGIN DESCRIPTION:
COLETO CREEK 22
END DESCRIPTION:
XS GIS Cut Line= 4
      2566417.62     13457074.53      2567213.55     13454617.79
        2568725.       13454025.      2570001.78     13453455.33
#Sta/Elev= 30
   802.7  103.27   836.7  102.53  1011.9   99.53  1165.5   96.73  1407.5   93.95
  1587.7   92.35  1709.6   91.24  1864.2   90.61  1966.9   90.97  2069.7   89.02
  2104.3   93.45  2172.4   89.18  2242.8   89.43  2263.3    93.9  2823.9   88.36
  3934.5   89.19  4391.8   65.55    4689   68.69  4752.4   67.78  4806.6   53.95
  4831.1   52.75  4832.9   44.68  4834.4   42.68  5034.2   44.68  5116.2   62.69
  5181.5   61.56  5282.5   59.68  5509.4   88.41  5949.3    91.6  6406.8  115.51
#Mann= 16 ,-1 , 0
   802.7     .04       0   836.7     .05       0  1011.9     .04       0
  1165.5     .05       0  1407.5     .04       0  1587.7     .05       0
  1709.6     .12       0  1864.2    .013       0  1966.9    .075       0
  2069.7     .05       0  2172.4     .04       0    4689     .03       0
  4832.9     .05       0  5034.2      .1       0  5116.2      .1       0
  5181.5     .12       0
Bank Sta=4832.9,5034.2
XS Rating Curve= 0 ,0
Exp/Cntr=0.3,0.1

Type RM Length L Ch R = 1 ,55393   ,2408,2408,2408
BEGIN DESCRIPTION:
COLETO CREEK 21
END DESCRIPTION:
XS GIS Cut Line= 3
      2569448.91     13456264.49        2570125.       13455525.
      2570868.69     13454415.81
#Sta/Elev= 30
  3998.8  101.03  3999.5  100.98  4370.8   95.56  4547.8   90.32  4625.5   85.82
  4814.5   68.65  4845.1   64.82  4894.4   64.09  4896.6   42.89  4898.1   40.89
  5096.6   40.89  5098.1   42.89  5101.3   47.91  5116.3   51.51  5173.4   52.58
  5194.4   49.06  5217.5   51.66  5230.4   57.51  5245.4    59.4  5317.4   57.89
  5368.4   61.66  5404.5   69.84  5563.5   75.96  5614.5   83.14  5626.8    82.9
  5635.5   85.73  5779.6   94.19  6132.5  104.34  6175.8  107.85  6336.2  110.71
#Mann= 5 ,-1 , 0
  3998.8    .013       0  3999.5     .04       0  4814.5     .03       0
  4896.6     .03       0  5098.1     .12       0
Bank Sta=4896.6,5098.1
XS Rating Curve= 0 ,0
Exp/Cntr=0.3,0.1

Type RM Length L Ch R = 1 ,52985   ,2423,2423,2423
BEGIN DESCRIPTION:
COLETO CREEK 20
END DESCRIPTION:
XS GIS Cut Line= 3
      2571312.31     13457610.33        2572025.       13456675.
      2572658.12     13455754.29
#Sta/Elev= 30
  3828.2   98.95  4040.6   95.27  4160.1   89.05  4238.4   84.17  4273.6   82.55
    4408   75.11  4554.1   64.92  4633.1   62.51  4697.5   66.95  4747.4   60.56
  4783.3   59.44  4803.6   60.01  4818.1   54.18  4832.6   43.28    4896   41.67
  4897.5   39.67  5096.1   39.67  5097.6   41.67  5098.2    58.5  5125.5   54.18
  5148.9   54.71  5198.3   66.95  5304.1   61.94  5320.4   61.71  5437.8   68.36
  5600.1   71.56  5690.6   77.29  5838.9   89.16  5925.5   92.94  6121.5   95.03
#Mann= 12 ,-1 , 0
  3828.2     .04       0  4160.1     .05       0  4238.4     .04       0
  4273.6     .05       0    4408     .12       0  4783.3     .03       0
    4896     .03       0  5097.6     .03       0  5304.1     .05       0
  5320.4    .013       0  5437.8     .05       0  5690.6     .12       0
Bank Sta=4896,5097.6
XS Rating Curve= 0 ,0
Exp/Cntr=0.3,0.1

Type RM Length L Ch R = 1 ,50562   ,2076,2076,2076
BEGIN DESCRIPTION:
COLETO CREEK 19
END DESCRIPTION:
XS GIS Cut Line= 3
      2573841.27     13458660.33        2573825.       13457975.
      2574129.65     13456101.84
#Sta/Elev= 30
  4314.4   94.89  4359.7   94.71  4539.8   86.48  4629.8   76.21  4749.9   67.56
  4819.9   65.66  4879.9   66.89    4889    41.8  4890.5    39.8  5089.3    39.8
  5090.8    41.8  5121.5   56.51  5144.9   56.17  5172.2   49.66  5202.6   48.42
  5232.9   53.96  5334.6   55.83  5435.6   65.53  5533.6   66.58  5592.2   67.19
    5633    64.8  5653.7   61.85  5721.5   58.85  5732.5   59.19    5832    67.7
  5931.5   73.31  6033.3    80.5    6550   86.29  6648.5   91.11  6897.7    97.4
#Mann= 11 ,-1 , 0
  4314.4     .12       0    4889     .03       0  5090.8     .12       0
  5144.9     .04       0  5334.6     .05       0  5533.6     .03       0
    5633     .05       0  5721.5    .013       0  5732.5     .05       0
    5832      .1       0  5931.5     .12       0
Bank Sta=4889,5090.8
XS Rating Curve= 0 ,0
Exp/Cntr=0.3,0.1