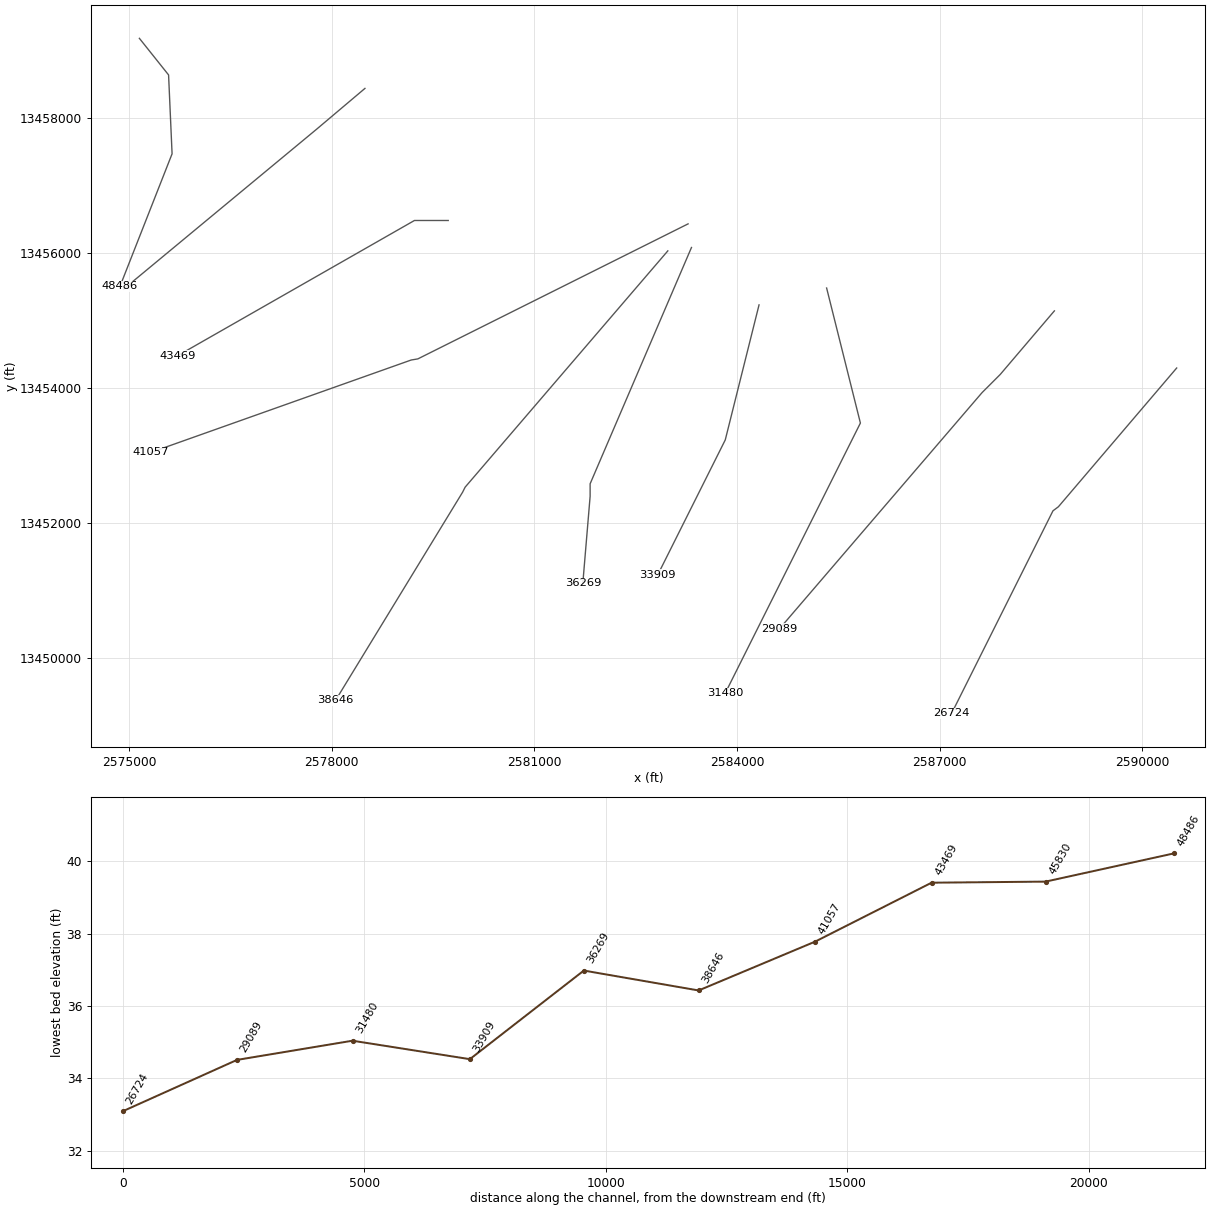
HEC-RAS study COLETO CREEK.prj: COLETO CREEK Base Level Engineering

--- COLETO CREEK.g01 (geometry) --- (continued)

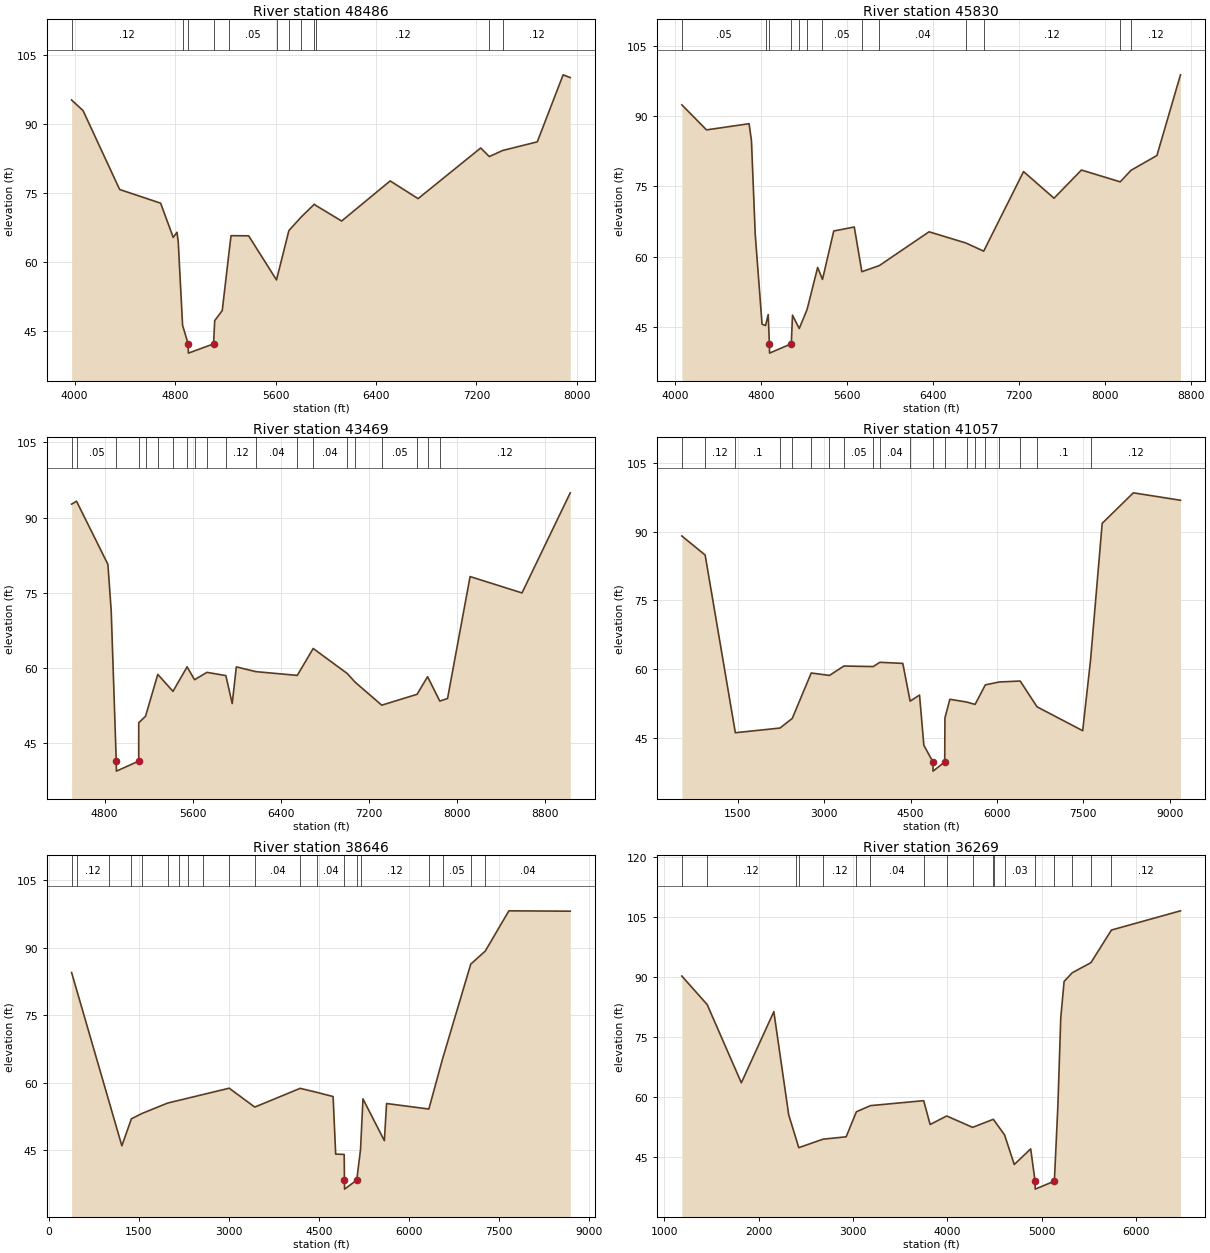
Type RM Length L Ch R = 1 ,48486   ,2656,2656,2656
BEGIN DESCRIPTION:
COLETO CREEK 18
END DESCRIPTION:
XS GIS Cut Line= 4
       2575154.3     13459172.78      2575586.38     13458630.74
      2575638.14      13457462.4      2574867.82     13455500.91
#Sta/Elev= 30
  3976.5   95.14  4067.7   92.84  4359.2   75.72  4685.4   72.75  4785.5   65.33
  4815.6   66.44  4825.6   64.36  4860.2   46.24  4904.8   42.22  4906.3   40.22
  5106.7   42.22  5115.9   47.28  5175.9   49.45  5233.5   62.92    5246    65.7
  5386.1   65.67  5607.9    56.1  5706.5   66.81  5805.1   69.77  5909.3   72.53
    5921   72.26  6126.4   68.88  6512.9   77.58  6735.2   73.74  7233.8   84.73
  7302.1   82.87  7409.2   84.19  7684.3   86.06  7889.8   100.6  7946.5     100
#Mann= 12 ,-1 , 0
  3976.5     .12       0  4860.2     .03       0  4904.8     .03       0
  5106.7     .03       0  5233.5     .05       0  5607.9    .013       0
  5706.5      .1       0  5805.1     .12       0  5909.3     .05       0
    5921     .12       0  7302.1     .05       0  7409.2     .12       0
Bank Sta=4904.8,5106.7
XS Rating Curve= 0 ,0
Exp/Cntr=0.3,0.1

Type RM Length L Ch R = 1 ,45830   ,2361,2361,2361
BEGIN DESCRIPTION:
COLETO CREEK 17
END DESCRIPTION:
XS GIS Cut Line= 3
      2578492.44     13458431.09        2577775.       13457825.
       2574921.8     13455459.25
#Sta/Elev= 30
  4060.8   92.38  4290.7   87.04  4687.3   88.36  4709.4   84.73  4744.5   64.76
  4808.2   45.61  4840.3   45.32  4865.4   47.66  4876.5   41.44    4878   39.44
  5080.6   41.44  5091.8   47.54  5154.5   44.68  5227.5   48.74  5326.2   57.71
  5371.2   55.15    5476   65.48  5667.4   66.33  5737.8    56.8  5900.8   58.11
    6364   65.31  6708.7   62.91    6873   61.18  7244.5   78.15  7528.4   72.47
  7783.7   78.48  8144.9   75.96  8246.1   78.43  8486.9   81.58  8706.4   98.78
#Mann= 13 ,-1 , 0
  4060.8     .05       0  4840.3      .1       0  4876.5     .05       0
  5080.6      .1       0  5154.5     .03       0  5227.5      .1       0
  5371.2     .05       0  5737.8      .1       0  5900.8     .04       0
  6708.7    .013       0    6873     .12       0  8144.9     .05       0
  8246.1     .12       0
Bank Sta=4876.5,5080.6
XS Rating Curve= 0 ,0
Exp/Cntr=0.3,0.1

Type RM Length L Ch R = 1 ,43469   ,2412,2412,2412
BEGIN DESCRIPTION:
COLETO CREEK 16
END DESCRIPTION:
XS GIS Cut Line= 3
      2579724.96       13456475.        2579225.       13456475.
      2575724.99     13454474.99
#Sta/Elev= 30
  4499.8   92.68  4544.5   93.27  4829.8   80.66  4859.8   71.36  4905.6   41.41
  4907.1   39.41  5109.7   41.41  5109.9   49.06  5171.6   50.35    5283   58.71
  5421.1   55.33  5549.3   60.21  5617.3   57.65  5729.8   59.12  5901.6   58.47
  5959.3   52.89  5996.7   60.21  6174.4   59.26  6550.4   58.51  6695.2   63.88
  7004.1    58.9  7075.1   57.18  7317.8   52.57  7639.2   54.74  7734.4   58.25
  7845.8   53.39  7915.9    53.9    8121   78.23  8592.5   74.97  9030.9   94.94
#Mann= 20 ,-1 , 0
  4499.8     .04       0  4544.5     .05       0  4905.6     .03       0
  5109.7     .03       0  5171.6      .1       0    5283     .05       0
  5421.1     .12       0  5549.3     .03       0  5617.3     .04       0
  5729.8     .05       0  5901.6     .12       0  6174.4     .04       0
  6550.4     .05       0  6695.2     .04       0  7004.1     .05       0
  7075.1     .04       0  7317.8     .05       0  7639.2     .12       0
  7734.4    .013       0  7845.8     .12       0
Bank Sta=4905.6,5109.7
XS Rating Curve= 0 ,0
Exp/Cntr=0.3,0.1

Type RM Length L Ch R = 1 ,41057   ,2411,2411,2411
BEGIN DESCRIPTION:
COLETO CREEK 15
END DESCRIPTION:
XS GIS Cut Line= 4
        2583275.       13456425.        2579275.       13454425.
      2579177.46     13454408.74      2575323.53     13453039.98
#Sta/Elev= 30
   527.7   89.04   932.6   84.88  1457.1   46.15  2233.1   47.17  2445.6   49.27
    2775   59.17  3091.9   58.64  3342.9   60.69  3851.1   60.57  3967.2    61.5
  4365.4   61.26  4493.2   53.03    4656   54.36  4731.5   43.41  4889.4   39.78
  4890.9   37.78  5093.6   39.78  5097.4   49.38  5182.8   53.44  5477.9   52.83
    5621   52.32  5798.9   56.58  6041.1   57.21  6404.3   57.42  6696.9    51.8
  7489.8   46.59  7626.4   61.96  7828.6   91.79  8369.8   98.44  9188.5   96.82
#Mann= 20 ,-1 , 0
   527.7     .05       0   932.6     .12       0  1457.1      .1       0
  2233.1     .12       0  2445.6     .12       0    2775     .03       0
  3091.9     .04       0  3342.9     .05       0  3851.1     .05       0
  3967.2     .04       0  4493.2     .03       0  4889.4     .05       0
  5093.6      .1       0  5477.9     .12       0    5621     .12       0
  5798.9      .1       0  6041.1     .05       0  6404.3     .12       0
  6696.9      .1       0  7626.4     .12       0
Bank Sta=4889.4,5093.6
XS Rating Curve= 0 ,0
Exp/Cntr=0.3,0.1

Type RM Length L Ch R = 1 ,38646   ,2377,2377,2377
BEGIN DESCRIPTION:
COLETO CREEK 14
END DESCRIPTION:
XS GIS Cut Line= 4
      2582974.98     13456024.98        2579975.       13452525.
       2579938.2     13452451.41      2578057.94     13449368.13
#Sta/Elev= 30
   383.9   84.49   467.3   80.66  1012.6   55.61  1220.8   46.04  1379.7   52.03
  1554.1    53.2  1981.9   55.52  2177.7   56.15  2315.8   56.59  2575.9   57.43
  3008.4   58.82  3433.7   54.63  4190.2   58.79  4464.1   57.91  4738.5   56.97
  4781.3    44.2  4922.9   44.13  4927.9   38.43  4929.4   36.43  5132.1   38.43
  5195.4   45.24  5235.7   56.45    5592   47.18  5628.8   55.42  6333.1    54.2
  6560.6    65.3  7030.7   86.35  7272.4   89.24  7665.7   98.17  8687.3   98.09
#Mann= 20 ,-1 , 0
   383.9     .05       0   467.3     .12       0  1012.6      .1       0
  1379.7     .03       0  1554.1     .12       0  1981.9     .05       0
  2177.7     .04       0  2315.8     .05       0  2575.9     .04       0
  3008.4     .05       0  3433.7     .04       0  4190.2     .05       0
  4464.1     .04       0  4927.9     .03       0  5132.1     .03       0
  5195.4     .12       0  6333.1    .013       0  6560.6     .05       0
  7030.7     .05       0  7272.4     .04       0
Bank Sta=4927.9,5132.1
XS Rating Curve= 0 ,0
Exp/Cntr=0.3,0.1

Type RM Length L Ch R = 1 ,36269   ,2360,2360,2360
BEGIN DESCRIPTION:
COLETO CREEK 13
END DESCRIPTION:
XS GIS Cut Line= 4
      2583324.98     13456074.96        2581825.       13452575.
        2581825.     13452388.94      2581716.79     13451099.97
#Sta/Elev= 30
  1184.6   90.31    1453   83.19  1815.6   63.59  2160.1    81.4  2317.9   55.57
  2390.3   50.01  2424.4   47.36  2681.8   49.48  2927.1   50.08  3035.2   56.34
  3184.6   57.88  3748.9   59.12  3817.4   53.16  3993.2   55.29  4267.8   52.44
  4487.8   54.46  4499.1   54.08  4606.5   50.56  4709.6   43.14  4883.6   47.06
  4930.1   38.98  4931.6   36.98  5134.8   38.98  5172.4   58.05  5202.5   79.85
    5238   88.95    5324   91.14  5522.5   93.66  5739.9  101.83    6472  106.64
#Mann= 18 ,-1 , 0
  1184.6     .05       0    1453     .12       0  2390.3     .05       0
  2424.4      .1       0  2681.8     .12       0  3035.2     .05       0
  3184.6     .04       0  3748.9     .05       0  3993.2     .12       0
  4267.8      .1       0  4487.8     .03       0  4499.1      .1       0
  4606.5     .03       0  4930.1     .03       0  5134.8     .03       0
    5324     .12       0  5522.5     .03       0  5739.9     .12       0
Bank Sta=4930.1,5134.8
XS Rating Curve= 0 ,0
Exp/Cntr=0.3,0.1

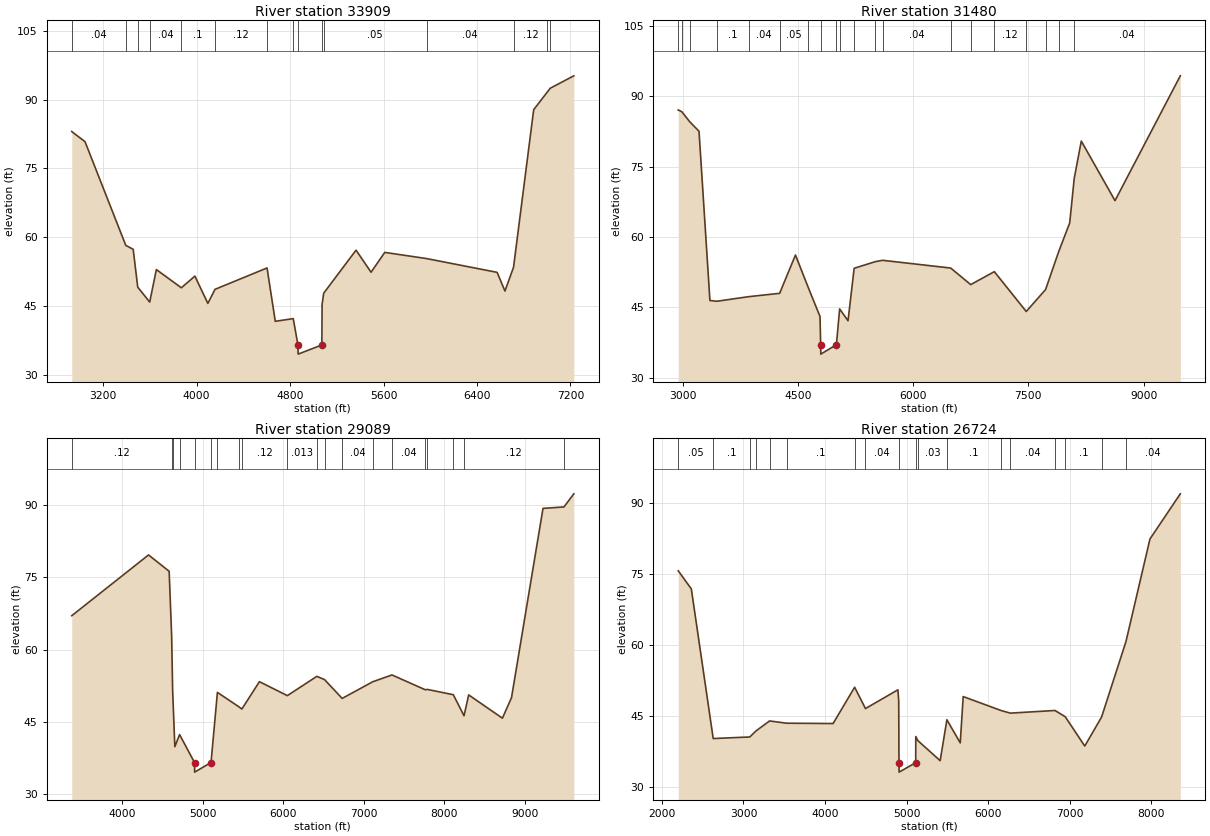
Type RM Length L Ch R = 1 ,33909   ,2429,2429,2429
BEGIN DESCRIPTION:
COLETO CREEK 12
END DESCRIPTION:
XS GIS Cut Line= 3
      2584325.01     13455225.02        2583825.       13453225.
      2582825.02     13451225.04
#Sta/Elev= 30
  2931.3   83.03  3044.7   80.83  3393.7   58.23    3457   57.37  3496.1   49.12
  3598.4   45.88  3655.4   52.96  3869.1   48.99  3985.3   51.53  4096.1   45.59
  4157.6   48.65  4602.9   53.31  4673.3   41.68    4827   42.27  4867.3   36.53
  4868.9   34.53    5072   36.53  5073.9   45.36  5087.9   47.81  5364.6   57.19
  5493.2   52.38  5610.6    56.7  5969.5   55.35  6572.1   52.35  6639.2   48.28
  6712.7   53.46  6885.2    87.8  7001.7   91.64  7026.6   92.47  7228.9   95.18
#Mann= 15 ,-1 , 0
  2931.3     .04       0  3393.7     .05       0  3496.1      .1       0
  3598.4     .04       0  3869.1      .1       0  4157.6     .12       0
  4602.9      .1       0    4827     .05       0  4867.3     .03       0
    5072     .05       0  5087.9     .05       0  5969.5     .04       0
  6712.7     .12       0  7001.7     .05       0  7026.6     .12       0
Bank Sta=4867.3,5072
XS Rating Curve= 0 ,0
Exp/Cntr=0.3,0.1

Type RM Length L Ch R = 1 ,31480   ,2391,2391,2391
BEGIN DESCRIPTION:
COLETO CREEK 11
END DESCRIPTION:
XS GIS Cut Line= 3
      2585325.01     13455474.96        2585825.       13453475.
      2583825.02     13449475.04
#Sta/Elev= 30
  2943.5   87.09  2990.1   86.72  3093.7   84.57    3214   82.55  3355.8   46.48
  3446.2   46.31  3860.2   47.29  4263.2      48    4469   56.17  4636.5    49.2
  4788.5   43.05    4797   37.04  4798.5   35.04  5001.7   37.04  5044.1   44.68
  5153.2   42.16  5232.8   53.34  5507.5   54.75  5603.3   55.04  6489.1   53.39
  6749.5   49.86    7057   52.62    7472   44.13  7723.7    48.8  7894.5   56.89
  8037.7   63.01  8096.6   72.48  8188.6   80.46  8627.4   67.76  9477.1   94.37
#Mann= 20 ,-1 , 0
  2943.5     .04       0  2990.1     .05       0  3093.7     .03       0
  3446.2      .1       0  3860.2     .04       0  4263.2     .05       0
  4636.5     .03       0    4797     .05       0  5001.7     .03       0
  5044.1     .05       0  5232.8     .04       0  5507.5    .013       0
  5603.3     .04       0  6489.1    .013       0  6749.5     .04       0
    7057     .12       0    7472     .12       0  7723.7     .12       0
  7894.5     .05       0  8096.6     .04       0
Bank Sta=4797,5001.7
XS Rating Curve= 0 ,0
Exp/Cntr=0.3,0.1

Type RM Length L Ch R = 1 ,29089   ,2365,2365,2365
BEGIN DESCRIPTION:
COLETO CREEK 10
END DESCRIPTION:
XS GIS Cut Line= 4
      2588695.97     13455136.36      2587893.75     13454193.75
        2587625.       13453925.      2584625.01     13450425.01
#Sta/Elev= 30
  3377.8   67.04  4329.9   79.68  4585.8   76.28  4616.7   62.86  4629.2   51.36
  4656.2   39.81    4715   42.32  4900.4   36.51  4901.9   34.51  5105.2   36.51
  5184.4   51.09  5452.3   48.08  5487.4   47.63  5705.2   53.32  6051.8   50.42
    6418   54.43  6513.4   53.75  6731.9   49.84  7110.7    53.3  7349.4   54.72
  7762.9   51.64  7788.4   51.71  8110.3   50.61  8243.3   46.23    8301   50.57
  8719.1   45.73  8832.2   49.99  9222.9   89.36  9482.6   89.66  9605.4   92.39
#Mann= 20 ,-1 , 0
  3377.8     .12       0  4616.7     .05       0  4629.2     .12       0
    4715      .1       0  4900.4     .05       0  5105.2      .1       0
  5184.4     .03       0  5452.3     .05       0  5487.4     .12       0
  6051.8    .013       0    6418     .05       0  6513.4     .05       0
  6731.9     .04       0  7110.7     .05       0  7349.4     .04       0
  7762.9     .05       0  7788.4     .04       0  8110.3     .04       0
  8243.3     .12       0  9482.6     .05       0
Bank Sta=4900.4,5105.2
XS Rating Curve= 0 ,0
Exp/Cntr=0.3,0.1

Type RM Length L Ch R = 1 ,26724   ,2362,2362,2362
BEGIN DESCRIPTION:
COLETO CREEK 9
END DESCRIPTION:
XS GIS Cut Line= 4
      2590505.86       13454290.      2588755.68     13452235.51
        2588675.       13452175.      2587174.98     13449174.96
#Sta/Elev= 30
  2200.1   75.64  2360.5   71.82  2628.8   40.19    3077   40.52  3154.2   41.81
  3319.8   43.91  3527.1   43.43  4098.3   43.36  4362.4   51.03  4495.1   46.52
  4892.7   50.49  4902.6   48.15  4905.7   35.09  4907.2   33.09  5110.8   35.09
  5111.7   40.61  5137.7   39.74  5410.7   35.51    5493   44.16  5656.7   39.27
    5693   49.06    6159    46.1  6270.9   45.56  6818.2   46.12    6944   44.79
  7182.8    38.6  7389.1   44.73  7687.6   60.67  7982.2   82.37    8354   91.91
#Mann= 18 ,-1 , 0
  2200.1     .05       0  2628.8      .1       0    3077     .05       0
  3154.2      .1       0  3319.8     .12       0  3527.1      .1       0
  4362.4     .12       0  4495.1     .04       0  4905.7     .04       0
  5110.8     .04       0  5137.7     .03       0    5493      .1       0
    6159    .013       0  6270.9     .04       0  6818.2     .05       0
    6944      .1       0  7389.1     .05       0  7687.6     .04       0
Bank Sta=4905.7,5110.8
XS Rating Curve= 0 ,0
Exp/Cntr=0.3,0.1