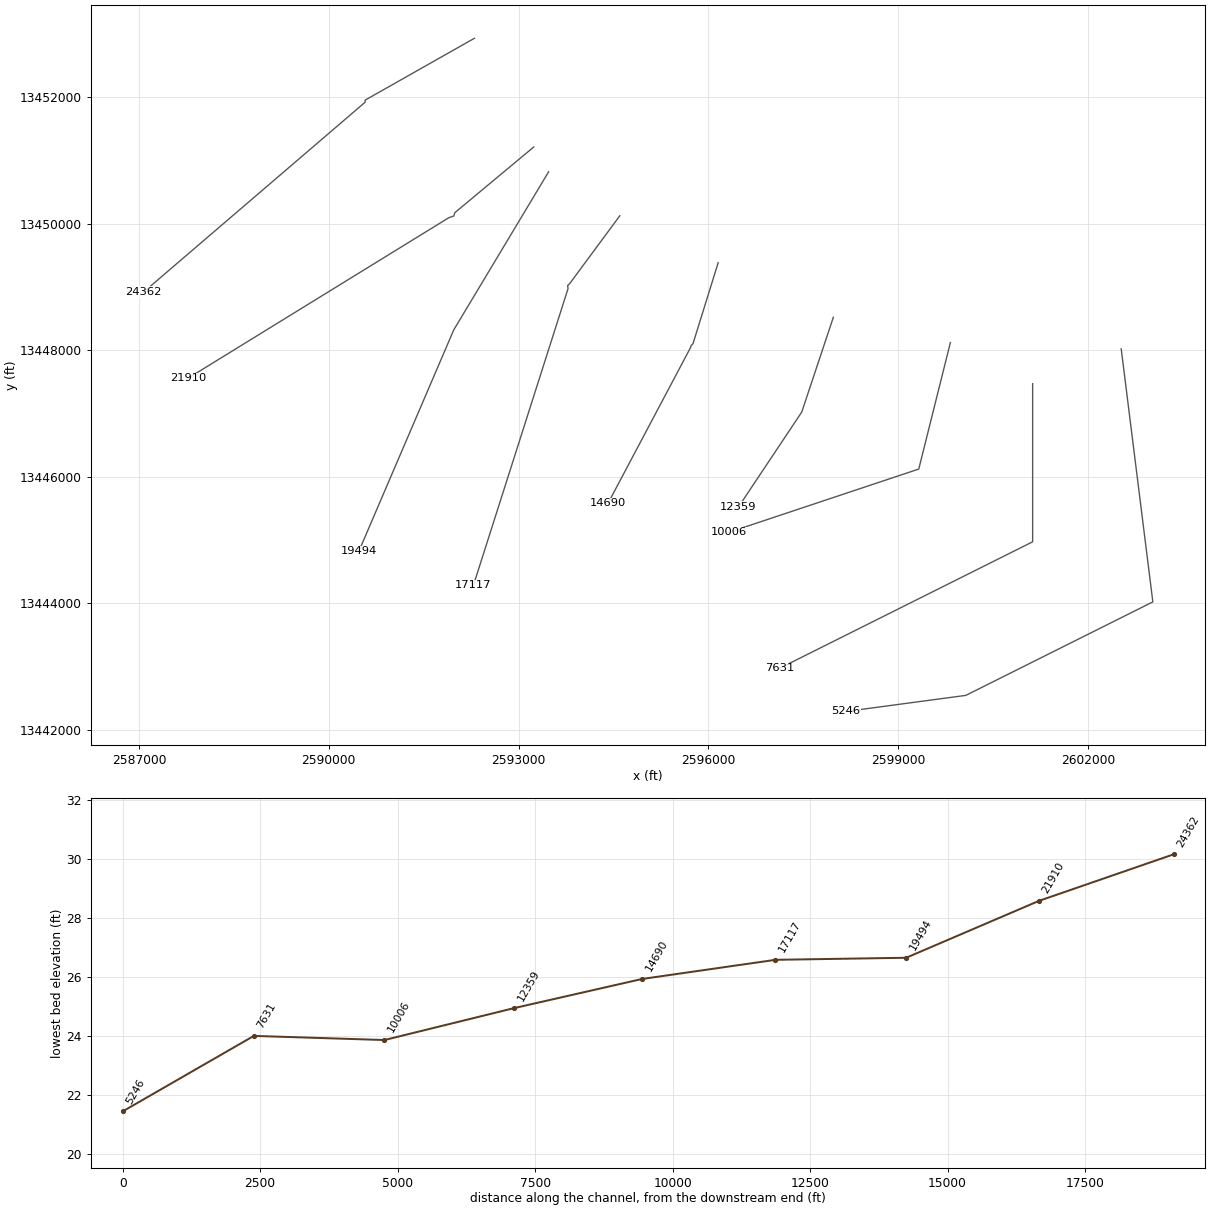
HEC-RAS study COLETO CREEK.prj: COLETO CREEK Base Level Engineering

--- COLETO CREEK.g01 (geometry) --- (continued)

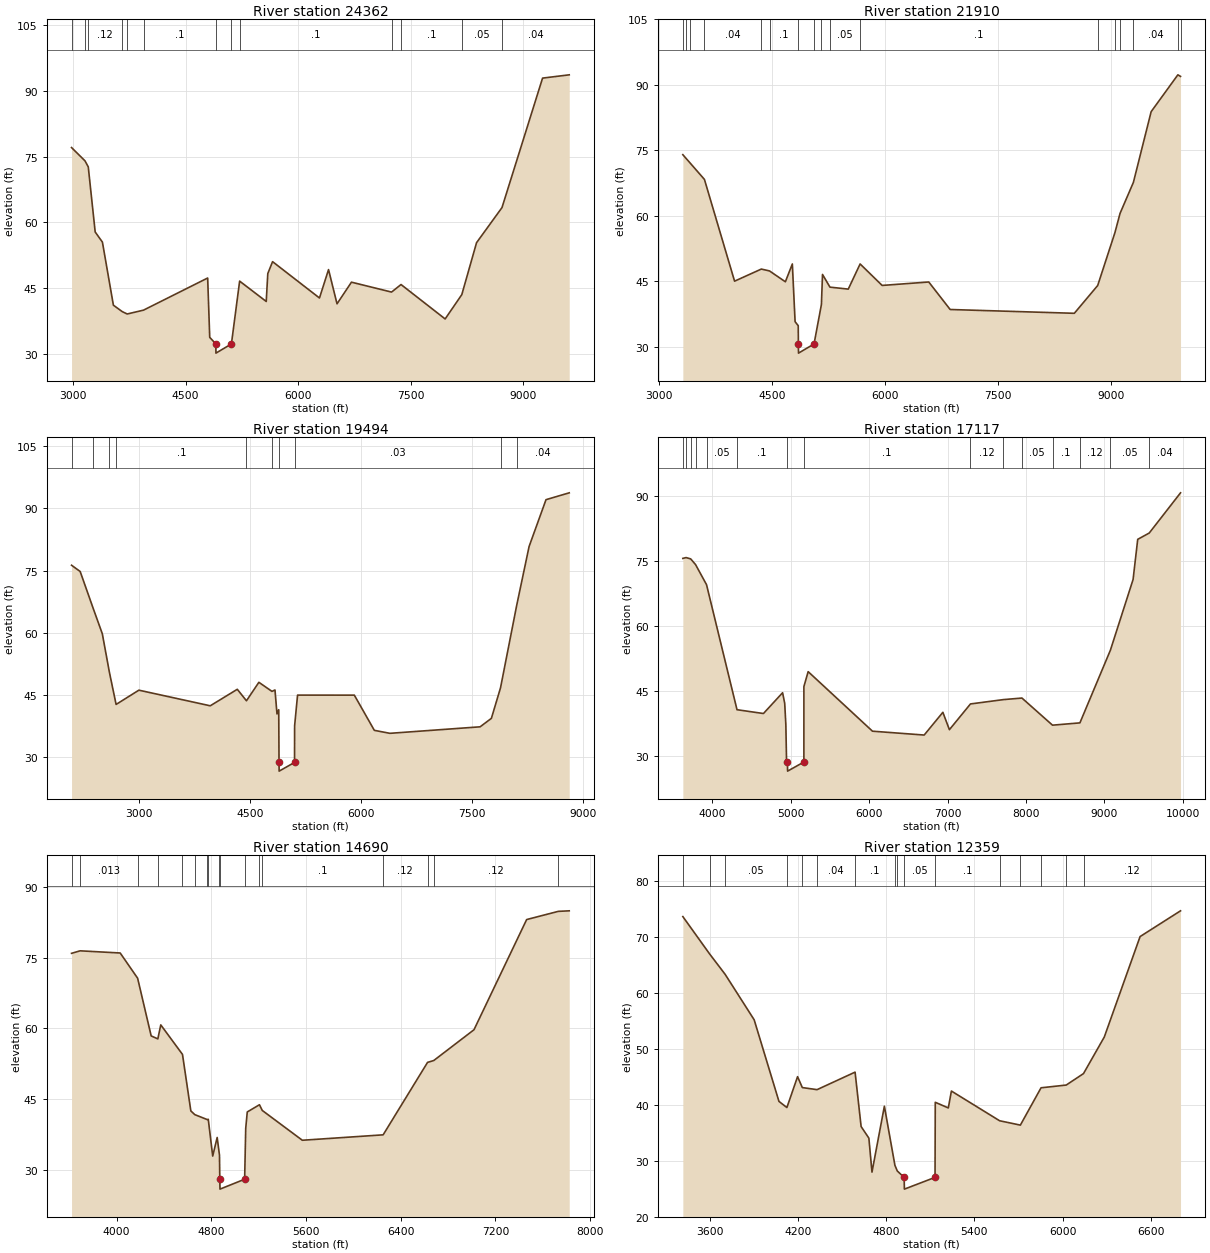
Type RM Length L Ch R = 1 ,24362   ,2452,2452,2452
BEGIN DESCRIPTION:
COLETO CREEK 8
END DESCRIPTION:
XS GIS Cut Line= 5
      2592302.72     13452935.82        2590575.     13451957.81
        2590575.       13451925.      2590555.48     13451908.27
        2587075.       13448925.
#Sta/Elev= 30
  2981.9   77.05  3160.6   74.03  3204.6   72.64  3296.7   57.79    3393   55.48
  3539.2   41.09    3657   39.62    3723   39.08  3940.7   39.96  4794.7   47.29
  4822.1   33.75  4903.3   32.25  4904.9   30.15    5111   32.25  5220.4   46.58
  5574.6   41.94  5595.5   48.31  5659.1   51.02  6283.6   42.73  6404.4   49.21
  6517.4    41.4  6709.5   46.34  7243.4   44.08  7369.8    45.8  7957.4   37.95
  8179.1    43.5  8375.6   55.35  8714.4   63.36  9254.7    92.9  9609.8   93.65
#Mann= 13 ,-1 , 0
  2981.9     .03       0  3160.6     .05       0  3204.6     .12       0
    3657      .1       0    3723     .12       0  3940.7      .1       0
  4903.3     .03       0    5111      .1       0  5220.4      .1       0
  7243.4    .013       0  7369.8      .1       0  8179.1     .05       0
  8714.4     .04       0
Bank Sta=4903.3,5111
XS Rating Curve= 0 ,0
Exp/Cntr=0.3,0.1

Type RM Length L Ch R = 1 ,21910   ,2416,2416,2416
BEGIN DESCRIPTION:
COLETO CREEK 7
END DESCRIPTION:
XS GIS Cut Line= 5
      2593240.22     13451217.07      2591992.94     13450178.83
        2591975.       13450125.      2591898.35     13450099.45
      2587772.95     13447559.12
#Sta/Elev= 30
  3320.9   74.01    3366   73.12  3411.1   72.23  3607.4   68.35  4007.4   45.05
  4362.6   47.82  4471.2   47.39  4681.8   44.91  4774.2   48.99  4810.7   35.77
  4852.3   34.85  4854.5   30.67    4856   28.57  5062.2   30.67    5160   39.71
  5174.5   46.59  5273.4   43.68  5516.4   43.23  5673.7   48.99    5966   44.07
  6584.7   44.86  6868.7   38.56  8516.7   37.69  8826.6   44.05  9055.1   56.14
  9123.5   60.57  9300.7   67.68  9536.1   83.86  9890.9    92.3  9926.1   91.94
#Mann= 17 ,-1 , 0
  3320.9     .05       0    3366     .04       0  3411.1     .05       0
  3607.4     .04       0  4362.6     .05       0  4471.2      .1       0
  4854.5     .03       0  5062.2      .1       0    5160      .1       0
  5273.4     .05       0  5673.7      .1       0  8826.6     .05       0
  9055.1      .1       0  9123.5     .05       0  9300.7     .04       0
  9890.9    .013       0  9926.1     .04       0
Bank Sta=4854.5,5062.2
XS Rating Curve= 0 ,0
Exp/Cntr=0.3,0.1

Type RM Length L Ch R = 1 ,19494   ,2377,2377,2377
BEGIN DESCRIPTION:
COLETO CREEK 6
END DESCRIPTION:
XS GIS Cut Line= 3
      2593474.98     13450824.97        2591975.       13448325.
      2590475.01     13444825.03
#Sta/Elev= 30
    2085   76.31  2201.6    74.8  2377.1   65.92  2500.9   59.76  2596.5   50.48
  2686.9   42.73  2994.6   46.17  3958.6    42.4  4324.1   46.38  4447.8   43.61
  4615.6   48.07  4792.5   45.88  4833.3   46.22  4860.5   40.44  4883.8   41.45
  4887.9   28.74  4889.4   26.64  5097.5   28.74  5098.4   37.55  5138.3   44.98
  5905.3   44.97  6175.4   36.48  6385.8   35.76  7604.3   37.33  7756.6   39.37
  7880.1   46.74  8097.8   66.56  8266.2   80.84  8494.6   92.13  8808.3   93.78
#Mann= 10 ,-1 , 0
    2085     .04       0  2377.1     .05       0  2596.5     .04       0
  2686.9      .1       0  4447.8     .05       0  4792.5     .03       0
  4887.9     .03       0  5097.5     .03       0  7880.1     .05       0
  8097.8     .04       0
Bank Sta=4887.9,5097.5
XS Rating Curve= 0 ,0
Exp/Cntr=0.3,0.1

Type RM Length L Ch R = 1 ,17117   ,2427,2427,2427
BEGIN DESCRIPTION:
COLETO CREEK 5
END DESCRIPTION:
XS GIS Cut Line= 5
      2594599.91     13450129.23      2593810.19     13449060.19
        2593775.       13449025.      2593781.68     13448978.27
      2592285.43     13444284.98
#Sta/Elev= 30
  3621.8   75.68  3662.8   75.87  3721.6   75.57  3784.1   74.25  3924.1   69.62
  4313.1   40.75  4650.5   39.87  4894.9   44.67  4921.9   42.22  4936.5   37.29
  4944.8    29.4    4957   28.67  4958.6   26.57  5166.6   28.67  5166.8   46.09
  5221.2   49.54  6042.1   35.79    6702    34.9  6940.6   40.15    7024   36.14
  7292.7   42.08  7713.1   43.08    7950   43.44  8339.8   37.18  8689.7   37.71
  9078.8   54.49  9368.3   70.81  9427.5   80.08  9574.6   81.54  9973.9   90.82
#Mann= 15 ,-1 , 0
  3621.8     .05       0  3662.8     .04       0  3721.6     .05       0
  3784.1     .04       0  3924.1     .05       0  4313.1      .1       0
    4957     .05       0  5166.6      .1       0  7292.7     .12       0
  7713.1      .1       0    7950     .05       0  8339.8      .1       0
  8689.7     .12       0  9078.8     .05       0  9574.6     .04       0
Bank Sta=4957,5166.6
XS Rating Curve= 0 ,0
Exp/Cntr=0.3,0.1

Type RM Length L Ch R = 1 ,14690   ,2331,2331,2331
BEGIN DESCRIPTION:
COLETO CREEK 4
END DESCRIPTION:
XS GIS Cut Line= 5
      2596154.77      13449387.5      2595756.14     13448106.14
        2595725.       13448075.      2595717.43     13448044.72
      2594412.24     13445580.74
#Sta/Elev= 30
  3618.8   75.91    3691   76.44  4029.9   75.98  4177.2   70.63  4291.7    58.4
  4347.9   57.77  4372.8   60.74  4556.3   54.48  4626.8    42.5  4660.5   41.71
  4764.7   40.67  4774.1   40.72  4811.6   32.93  4849.4   36.87  4868.9   33.11
  4871.5   28.02  4873.1   25.92  5081.5   28.02  5090.6   38.81  5103.6   42.28
  5206.7   43.81  5230.4    42.6  5568.9   36.28  6251.8   37.43  6627.1   52.79
  6679.4   53.18  7019.5   59.71  7464.5   83.07  7732.5   84.81  7824.3   84.92
#Mann= 17 ,-1 , 0
  3618.8     .04       0    3691    .013       0  4177.2     .04       0
  4347.9      .1       0  4556.3     .05       0  4660.5      .1       0
  4764.7     .05       0  4774.1      .1       0  4868.9     .05       0
  4871.5     .05       0  5081.5     .05       0  5206.7     .05       0
  5230.4      .1       0  6251.8     .12       0  6627.1     .05       0
  6679.4     .12       0  7732.5     .05       0
Bank Sta=4871.5,5081.5
XS Rating Curve= 0 ,0
Exp/Cntr=0.3,0.1

Type RM Length L Ch R = 1 ,12359   ,2353,2353,2353
BEGIN DESCRIPTION:
COLETO CREEK 3
END DESCRIPTION:
XS GIS Cut Line= 3
        2597975.     13448524.99        2597475.       13447025.
        2596475.     13445525.01
#Sta/Elev= 30
  3418.6   73.64  3601.3   66.94  3706.2   63.32  3903.5    55.2  4072.1   40.61
    4126   39.51  4198.6   45.03  4230.9   43.08  4331.3   42.71  4589.7   45.84
  4630.8   36.11  4683.5   34.04  4704.6   27.97  4788.9   39.75  4860.6   29.18
  4876.7   28.17  4923.3   27.03  4924.9   24.93  5133.3   27.03  5134.9   40.45
  5223.6   39.44  5244.6   42.46  5572.4   37.15  5713.5   36.37  5854.1   43.04
  6025.3   43.53  6142.8   45.58  6284.2   52.12  6527.6   70.07  6802.5   74.67
#Mann= 16 ,-1 , 0
  3418.6     .05       0  3601.3    .013       0  3706.2     .05       0
    4126    .013       0  4230.9     .05       0  4331.3     .04       0
  4589.7      .1       0  4860.6     .03       0  4876.7      .1       0
  4923.3     .05       0  5133.3      .1       0  5572.4    .013       0
  5713.5      .1       0  5854.1     .12       0  6025.3    .013       0
  6142.8     .12       0
Bank Sta=4923.3,5133.3
XS Rating Curve= 0 ,0
Exp/Cntr=0.3,0.1

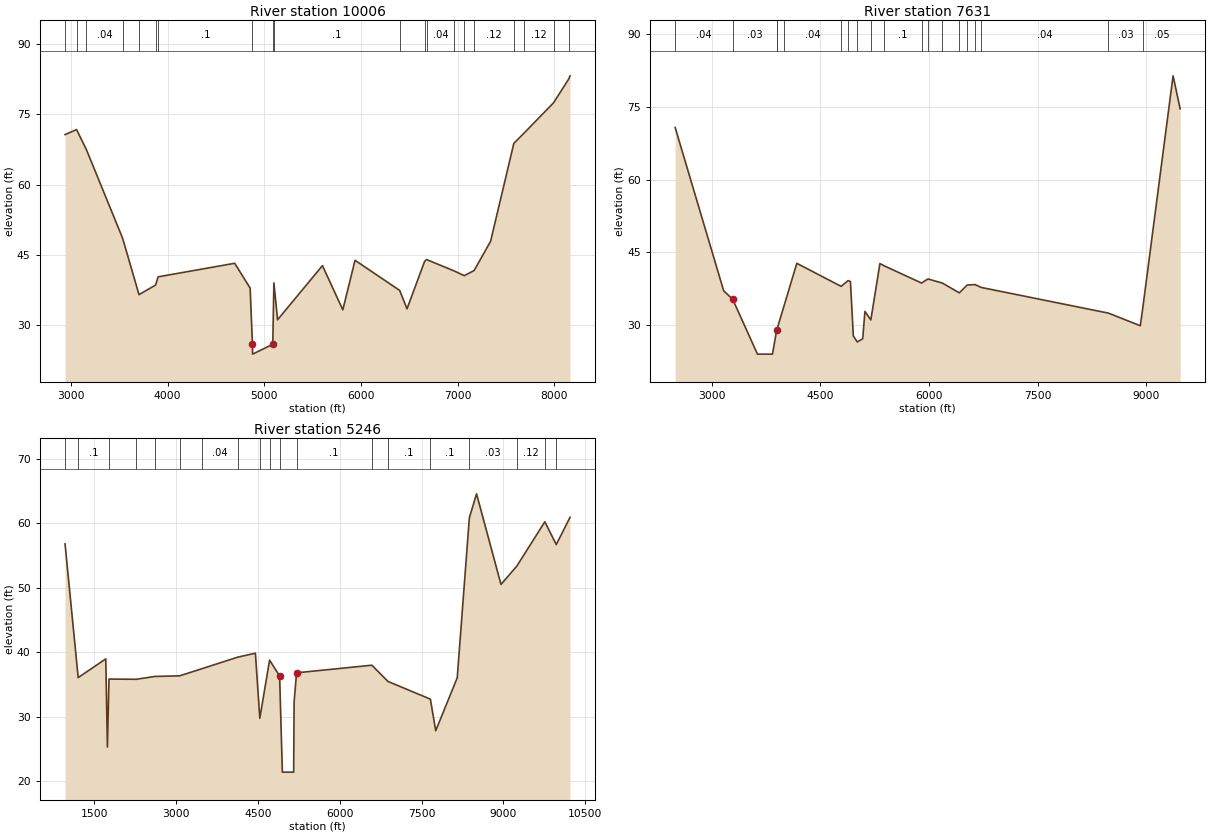
Type RM Length L Ch R = 1 ,10006   ,2375,2375,2375
BEGIN DESCRIPTION:
COLETO CREEK 2
END DESCRIPTION:
XS GIS Cut Line= 3
        2599825.     13448125.02        2599325.       13446125.
      2596325.05     13445125.02
#Sta/Elev= 30
  2938.7   70.66    3058   71.73  3160.4   67.42  3534.3   48.56  3703.7   36.54
  3875.2   38.57  3901.6   40.33  4693.6   43.22  4853.4   37.93  4877.2   25.95
  4878.8   23.85  5087.3   25.95    5099   39.04  5137.3   31.18  5601.1   42.72
  5811.9    33.3  5938.4   43.86  6399.7   37.44    6476   33.51  6657.2   43.59
  6677.5   44.02  6965.1   41.58  7067.8   40.58  7170.4   41.68  7340.4    47.9
    7581   68.79  7683.7   70.91  7991.6   77.44  8150.9   82.58  8162.5   83.19
#Mann= 20 ,-1 , 0
  2938.7     .05       0    3058    .013       0  3160.4     .04       0
  3534.3    .013       0  3703.7      .1       0  3875.2     .05       0
  3901.6      .1       0  4877.2     .03       0  5087.3     .03       0
    5099      .1       0  6399.7     .04       0  6657.2    .013       0
  6677.5     .04       0  6965.1      .1       0  7067.8      .1       0
  7170.4     .12       0    7581     .05       0  7683.7     .12       0
  7991.6     .05       0  8150.9     .12       0
Bank Sta=4877.2,5087.3
XS Rating Curve= 0 ,0
Exp/Cntr=0.3,0.1

Type RM Length L Ch R = 1 ,7631    ,2385,2385,2385
BEGIN DESCRIPTION:
COLETO CREEK 1
END DESCRIPTION:
XS GIS Cut Line= 3
        2601125.     13447474.95        2601125.       13444975.
      2597124.99     13442974.99
#Sta/Elev= 30
  2495.7   70.75  3165.7   37.06  3290.8   35.29  3632.1   23.99  3839.2   23.99
  3897.2   28.89  3995.9   33.79  4175.7   42.72  4787.1   37.97  4883.6   39.16
  4915.7   38.97  4955.7   27.74  5010.2    26.5  5085.1   27.16  5115.8    32.8
  5197.3   31.04  5322.7   42.67  5383.2    42.2  5897.9   38.65  5985.6    39.5
  6185.7   38.64  6419.1   36.63  6527.5   38.25  6635.9   38.33  6723.8   37.74
    8477   32.45  8917.2   29.85  8949.1    33.2    9370    81.4  9467.8    74.6
#Mann= 19 ,-1 , 0
  2495.7     .04       0  3290.8     .03       0  3897.2      .1       0
  3897.2      .1       0  3995.9     .04       0  4787.1     .05       0
  4883.6     .03       0  5010.2      .1       0  5197.3     .05       0
  5383.2      .1       0  5897.9     .04       0  5985.6     .12       0
  6185.7     .04       0  6419.1    .013       0  6527.5     .05       0
  6635.9      .1       0  6723.8     .04       0    8477     .03       0
  8949.1     .05       0
Bank Sta=3290.8,3897.2
XS Rating Curve= 0 ,0
Exp/Cntr=0.3,0.1

Type RM Length L Ch R = 1 ,5246    ,0,0,0
BEGIN DESCRIPTION:
COLETO CREEK 0
END DESCRIPTION:
XS GIS Cut Line= 4
        2602525.       13448025.        2603025.       13444025.
      2600068.73     13442546.87      2598171.34     13442292.54
#Sta/Elev= 30
   968.9    56.8  1209.7   36.08  1714.7   38.98  1744.9   25.33  1774.1   35.85
  2274.7   35.82  2613.2   36.26  3067.2   36.35  3484.3   37.48  4137.6   39.26
  4455.8   39.86  4536.6   29.78  4715.6   38.78  4899.3   36.34  4949.6   21.43
  5156.7   21.43  5164.9    32.3  5209.7   36.82  6589.6      38    6885   35.48
  7661.1   32.74  7758.8   27.85  8152.9   36.05  8374.7   60.84  8506.6   64.56
  8954.4   50.52  9242.9   53.34  9757.6   60.23  9966.9   56.69 10219.6   60.93
#Mann= 19 ,-1 , 0
   968.9     .04       0  1209.7      .1       0  1774.1     .04       0
  2274.7     .12       0  2613.2     .04       0  3067.2     .04       0
  3484.3     .04       0  4137.6     .05       0  4536.6     .03       0
  4715.6     .05       0  4899.3     .03       0  5209.7      .1       0
  6589.6     .03       0    6885      .1       0  7661.1      .1       0
  8374.7     .03       0  9242.9     .12       0  9757.6     .05       0
  9966.9     .05       0
Bank Sta=4899.3,5209.7
XS Rating Curve= 0 ,0
Exp/Cntr=0.3,0.1

Chan Stop Cuts=-1
Use User Specified Reach Order=0
Composite Channel Slope=5