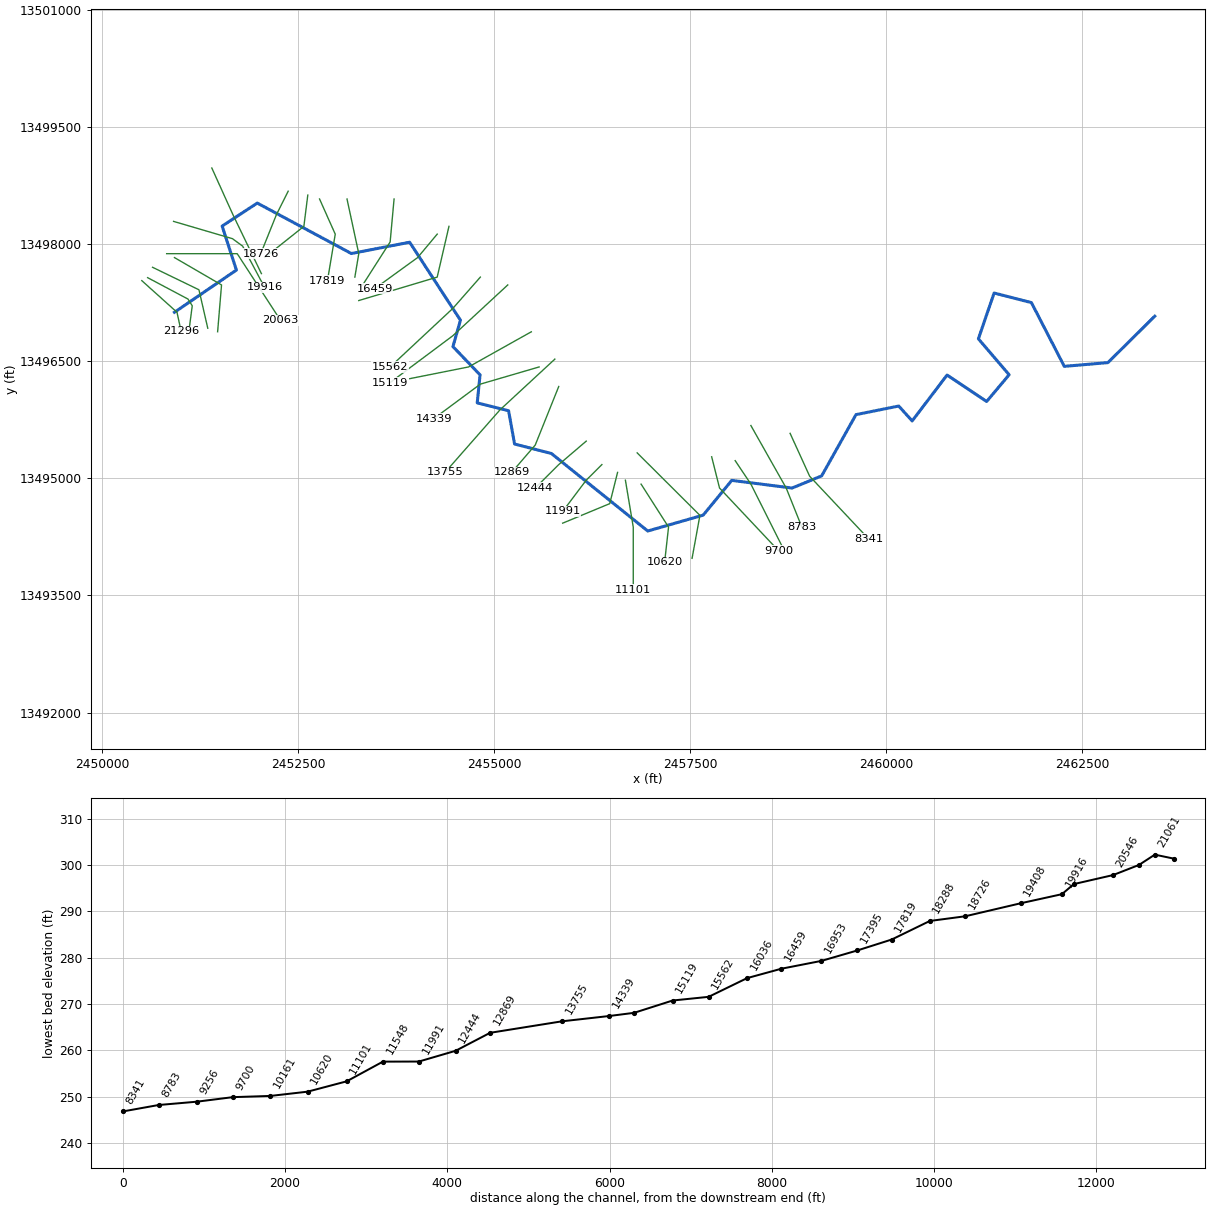
--- COW CREEK.prj (project) ---

Proj Title=COW CREEK Base Level Engineering
Current Plan=p01
Default Exp/Contr=0.3,0.1
English Units
Geom File=g01
Flow File=f01
Plan File=p01
Y Axis Title=Elevation
X Axis Title(PF)=Main Channel Distance
X Axis Title(XS)=Station
BEGIN DESCRIPTION:
COW CREEK
END DESCRIPTION:
DSS Export Rating Curves= 0
DSS Export Rating Curve Sorted= 0
DSS Export Volume Flow Curves= 0
DXF OffsetX= 0
DXF OffsetY= 0
DXF ScaleX= 1
DXF ScaleY= 10

--- COW CREEK.p01 (plan) ---

Plan Title=Multiple Run
Short Identifier=Multiple
Geom File=g01
Flow File=f01
Subcritical Flow
K Sum by GR= 0
Std Step Tol= 0.01
Critical Tol= 0.01
Num of Std Step Trials= 20
Max Error Tol= 0.3
Flow Tol Ratio= 0.001
Split Flow NTrial= 30
Split Flow Tol= 0.02
Split Flow Ratio= 0.02
Log Output Level= 0
Friction Slope Method= 1
Unsteady Friction Slope Method= 2
Unsteady Bridges Friction Slope Method= 1
Parabolic Critical Depth
Global Vel Dist=  1 , 1 , 1
Global Log Level= 0
CheckData=True
Encroach Param= -1, 0, 0, 0
BEGIN DESCRIPTION:
Multiple Run
END DESCRIPTION:

--- COW CREEK.f01 (steady flow) ---

Flow Title=Multiple
Number of Profiles=7
Profile Names=10-year,25-year,50-year,1pct_min,100-year,1pct_plu,500-year
River Rch & RM= COW CREEK,Reach-1,21296
     618    1000    1345     876    1749    3489    2925
River Rch & RM= COW CREEK,Reach-1,18288
     947    1566    2139    1412    2818    5622    4842
River Rch & RM= COW CREEK,Reach-1,14339
    1004    1662    2271    1499    2992    5969    5144
River Rch & RM= COW CREEK,Reach-1,11101
    1650    2801    3892    2609    5206   10387    9229
River Rch & RM= COW CREEK,Reach-1,8341
    1650    2798    3884    2601    5189   10354    9180
River Rch & RM= COW CREEK,Reach-1,7012
    1747    2970    4129    2769    5524   11022    9801
River Rch & RM= COW CREEK,Reach-1,6066
    1777    3013    4180    2796    5580   11133    9852
Boundary for River Rch & Prof#=COW CREEK,Reach-1,1
Up Type=0
Dn Type=3
Dn Slope=0.005
Boundary for River Rch & Prof#=COW CREEK,Reach-1,2
Up Type=0
Dn Type=3
Dn Slope=0.005
Boundary for River Rch & Prof#=COW CREEK,Reach-1,3
Up Type=0
Dn Type=3
Dn Slope=0.005
Boundary for River Rch & Prof#=COW CREEK,Reach-1,4
Up Type=0
Dn Type=3
Dn Slope=0.005
Boundary for River Rch & Prof#=COW CREEK,Reach-1,5
Up Type=0
Dn Type=3
Dn Slope=0.005
Boundary for River Rch & Prof#=COW CREEK,Reach-1,6
Up Type=0
Dn Type=3
Dn Slope=0.005
Boundary for River Rch & Prof#=COW CREEK,Reach-1,7
Up Type=0
Dn Type=3
Dn Slope=0.005

--- COW CREEK.g01 (geometry) ---

Geom Title=Existing Conditions
Program Version=4.10

River Reach=COW CREEK       ,Reach-1
Reach XY= 30
        2450925.       13497125.      2451714.52      13497665.2
      2451532.58     13498228.32      2451980.93     13498522.77
      2453180.67     13497876.98      2453923.78     13498021.56
      2454571.56     13497023.43      2454476.05     13496685.43
      2454821.55     13496323.75      2454785.42     13495965.19
      2455185.18     13495864.68      2455261.64      13495438.4
      2455731.34     13495316.98      2456959.82     13494324.57
       2457666.7     13494528.07      2458030.93     13494972.76
       2458800.3      13494874.7       2459177.7     13495030.36
      2459615.19     13495814.49      2460159.97     13495924.67
      2460331.66     13495733.95      2460776.58     13496321.33
      2461281.21      13495982.8      2461567.92       13496325.
      2461175.97     13496785.29      2461376.46     13497371.46
      2461852.01     13497248.52      2462271.33     13496432.69
      2462827.45     13496480.46        2463425.       13497075.

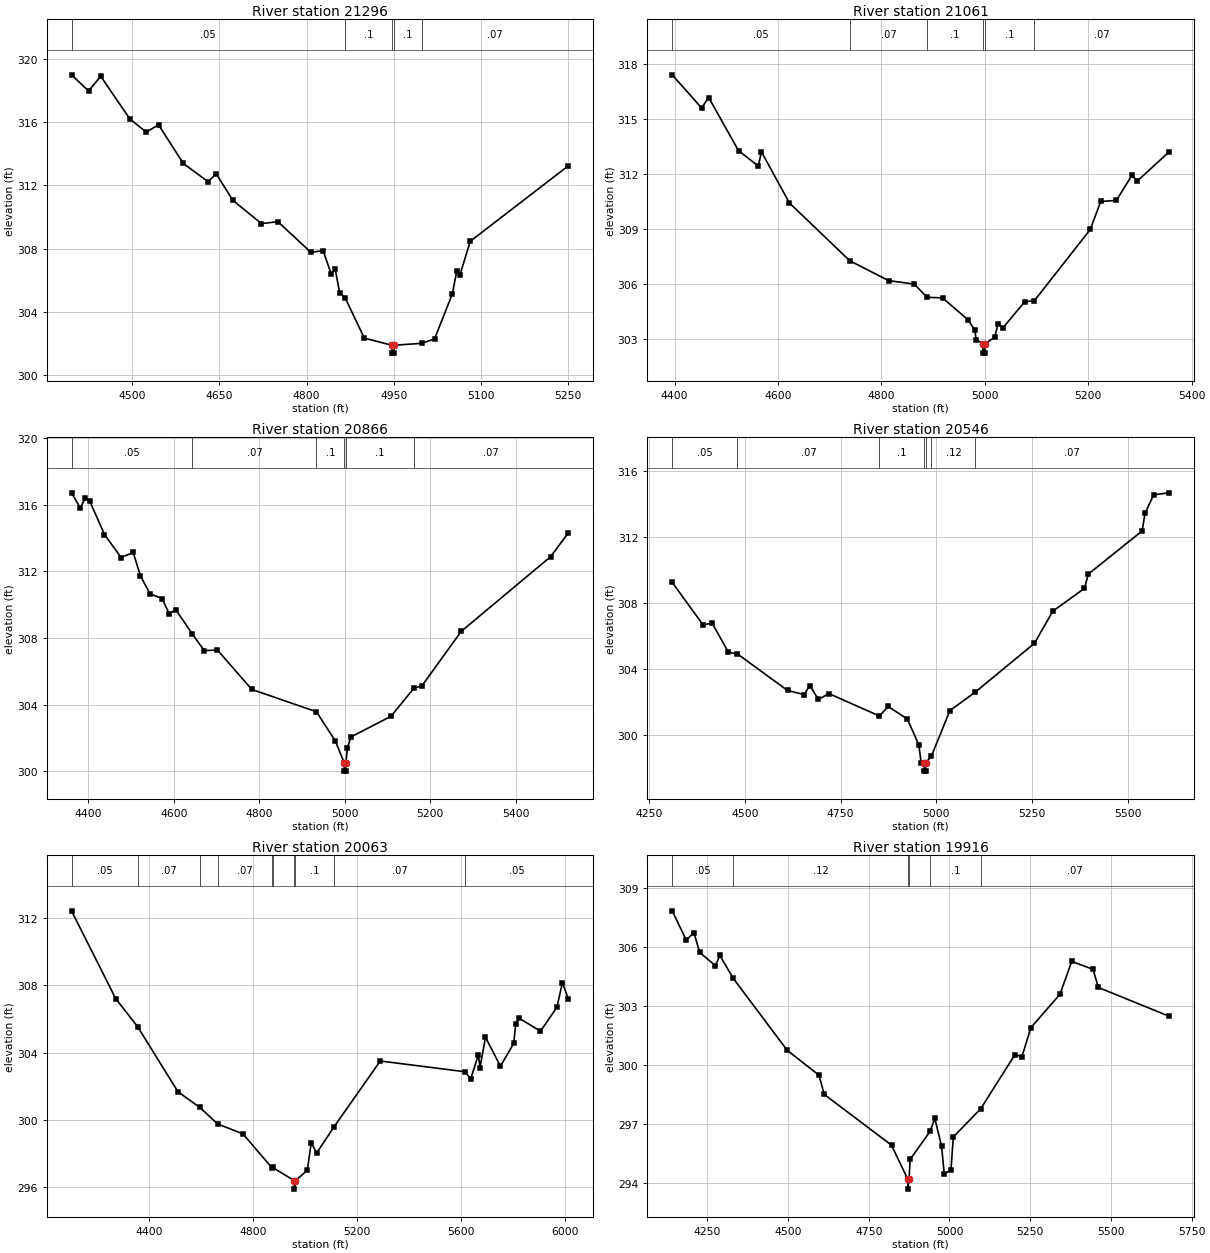
Type RM Length L Ch R = 1 ,21296   ,235,235,235
BEGIN DESCRIPTION:
COW CREEK 37.0
END DESCRIPTION:
XS GIS Cut Line= 3
      2450508.45     13497529.89      2450957.05     13497124.85
      2451009.91     13496879.99
#Sta/Elev= 30
  4395.6     319    4425  317.98  4445.9  318.91  4495.9  316.21  4524.3  315.37
  4545.3  315.84  4587.9  313.39  4630.5  312.24  4644.7  312.73  4673.1  311.06
  4722.4  309.58  4750.8   309.7  4807.6  307.76  4828.5  307.87  4842.7  306.37
  4849.4   306.7  4856.9  305.21  4866.3  304.89  4899.5  302.33  4946.8  301.88
  4947.1  301.38  4950.6  301.38  4950.8  301.88  4998.2     302  5020.3  302.28
    5051  305.14  5058.7  306.61  5063.9  306.32  5081.7  308.46  5250.5  313.24
#Mann= 5 ,-1 , 0
  4395.6     .05       0  4866.3      .1       0  4946.8     .05       0
  4950.8      .1       0  4998.2     .07       0
Bank Sta=4946.8,4950.8
XS Rating Curve= 0 ,0
Exp/Cntr=0.3,0.1

Type RM Length L Ch R = 1 ,21061   ,195,195,195
BEGIN DESCRIPTION:
Mapping XS 349de952
END DESCRIPTION:
XS GIS Cut Line= 4
      2450582.64     13497568.15      2451097.61     13497293.79
      2451151.58     13497208.34       2451115.6     13496933.95
#Sta/Elev= 30
  4395.2   317.4    4452   315.6  4465.9  316.16  4523.5  313.27  4561.8  312.43
  4567.8  313.21    4622  310.42  4738.9  307.27    4814  306.19  4863.6     306
  4888.5  305.28  4918.2  305.25  4967.8  304.05  4980.9  303.49  4983.2  302.98
  4996.5  302.74  4996.7  302.24  5000.2  302.24  5000.5  302.74  5019.6  303.12
  5025.6  303.85  5034.9  303.61  5077.3  305.04  5096.1   305.1  5204.2  308.98
  5224.3   310.5  5254.6  310.56  5284.8  311.93  5294.9  311.61  5356.5   313.2
#Mann= 6 ,-1 , 0
  4395.2     .05       0  4738.9     .07       0  4888.5      .1       0
  4996.5     .05       0  5000.5      .1       0  5096.1     .07       0
Bank Sta=4996.5,5000.5
XS Rating Curve= 0 ,0
Exp/Cntr=0.3,0.1

Type RM Length L Ch R = 1 ,20866   ,320,320,320
BEGIN DESCRIPTION:
Mapping XS ba6096f3
END DESCRIPTION:
XS GIS Cut Line= 3
      2450645.58     13497700.84      2451237.04     13497412.98
      2451349.47     13496920.53
#Sta/Elev= 30
  4360.7  316.71  4381.1  315.81  4393.4  316.42  4403.6   316.2  4437.9  314.21
  4476.8  312.83    4505  313.14  4521.9  311.74  4544.5  310.65  4572.6  310.37
  4589.6  309.45  4604.7  309.71  4643.7  308.23  4671.5  307.25  4702.3  307.28
  4782.7  304.92  4934.1  303.58  4978.4  301.82    4999  300.52  4999.2  300.02
  5002.7  300.02    5003  300.52  5006.5  301.42  5014.6  302.07  5108.7  303.31
  5162.6  305.01  5180.5  305.12  5272.8   308.4  5482.1  312.88  5523.6  314.31
#Mann= 6 ,-1 , 0
  4360.7     .05       0  4643.7     .07       0  4934.1      .1       0
    4999     .05       0    5003      .1       0  5162.6     .07       0
Bank Sta=4999,5003
XS Rating Curve= 0 ,0
Exp/Cntr=0.3,0.1

Type RM Length L Ch R = 1 ,20546   ,483,483,483
BEGIN DESCRIPTION:
COW CREEK 36.0
END DESCRIPTION:
XS GIS Cut Line= 3
      2450924.96     13497825.02        2451525.       13497475.
        2451475.     13496875.05
#Sta/Elev= 30
  4310.4  309.27  4391.5  306.68  4414.2  306.82  4457.2  305.03  4480.3  304.94
  4611.4  302.72  4654.9  302.47  4669.3  303.02  4692.1  302.18  4719.4  302.53
  4851.4  301.17    4874  301.75    4924  300.99  4954.2  299.42    4960  298.34
  4967.9  298.33  4968.2  297.83  4971.7  297.83  4971.9  298.33  4986.6  298.72
  5035.2   301.5    5102  302.63  5255.9  305.58  5303.6  307.52  5386.4  308.91
  5396.4  309.77  5536.9  312.39  5544.4  313.45    5567  314.58  5607.1   314.7
#Mann= 7 ,-1 , 0
  4310.4     .05       0  4480.3     .07       0  4851.4      .1       0
  4967.9     .05       0  4971.9      .1       0  4986.6     .12       0
    5102     .07       0
Bank Sta=4967.9,4971.9
XS Rating Curve= 0 ,0
Exp/Cntr=0.3,0.1

Type RM Length L Ch R = 1 ,20063   ,147,147,147
BEGIN DESCRIPTION:
COW CREEK 35.0
END DESCRIPTION:
XS GIS Cut Line= 3
      2450825.04       13497875.        2451725.       13497875.
      2452275.01     13497024.99
#Sta/Elev= 30
    4100  312.42    4270  307.21  4354.8  305.53    4510  301.67  4594.2  300.74
  4662.5  299.76    4760  299.17  4870.9  297.17  4873.8  297.18    4958  296.39
  4958.2  295.89    4962  296.39  5007.5  297.01  5022.7  298.63  5043.8  298.04
  5109.6  299.57  5288.5   303.5  5615.7  302.86  5636.1  302.42  5666.4  303.87
  5672.4  303.11  5693.5  304.91  5750.9  303.19  5802.3  304.55  5809.9  305.71
  5823.4  306.04  5905.2  305.27  5968.5  306.69  5989.6  308.16  6012.4  307.18
#Mann= 10 ,-1 , 0
    4100     .05       0  4354.8     .07       0  4594.2     .12       0
  4662.5     .07       0  4870.9     .12       0  4873.8      .1       0
    4958     .05       0    4962      .1       0  5109.6     .07       0
  5615.7     .05       0
Bank Sta=4958,4962
XS Rating Curve= 0 ,0
Exp/Cntr=0.3,0.1

Type RM Length L Ch R = 1 ,19916   ,508,508,508
BEGIN DESCRIPTION:
Mapping XS 8e6bc846
END DESCRIPTION:
XS GIS Cut Line= 4
      2450913.49     13498288.44      2451664.36     13498067.09
      2451794.56      13497971.6      2452072.35     13497446.42
#Sta/Elev= 30
  4141.5  307.84  4184.8  306.36  4208.8  306.73  4226.5  305.73  4275.4  305.05
    4289  305.58  4330.1  304.42  4497.5  300.76  4596.2  299.49  4612.2  298.52
  4820.7  295.94  4870.9  294.21  4871.1  293.71  4874.9  294.21  4878.4  295.22
  4939.9  296.64  4954.7   297.3  4975.5   295.9    4984  294.47  5004.8   294.7
  5011.9  296.36  5096.8  297.79  5202.5  300.53  5224.5  300.44  5252.2  301.91
  5342.1   303.6  5378.6  305.27  5444.6  304.87    5461  303.95  5679.9  302.49
#Mann= 6 ,-1 , 0
  4141.5     .05       0  4330.1     .12       0  4870.9     .05       0
  4874.9     .12       0  4939.9      .1       0  5096.8     .07       0
Bank Sta=4870.9,4874.9
XS Rating Curve= 0 ,0
Exp/Cntr=0.3,0.1

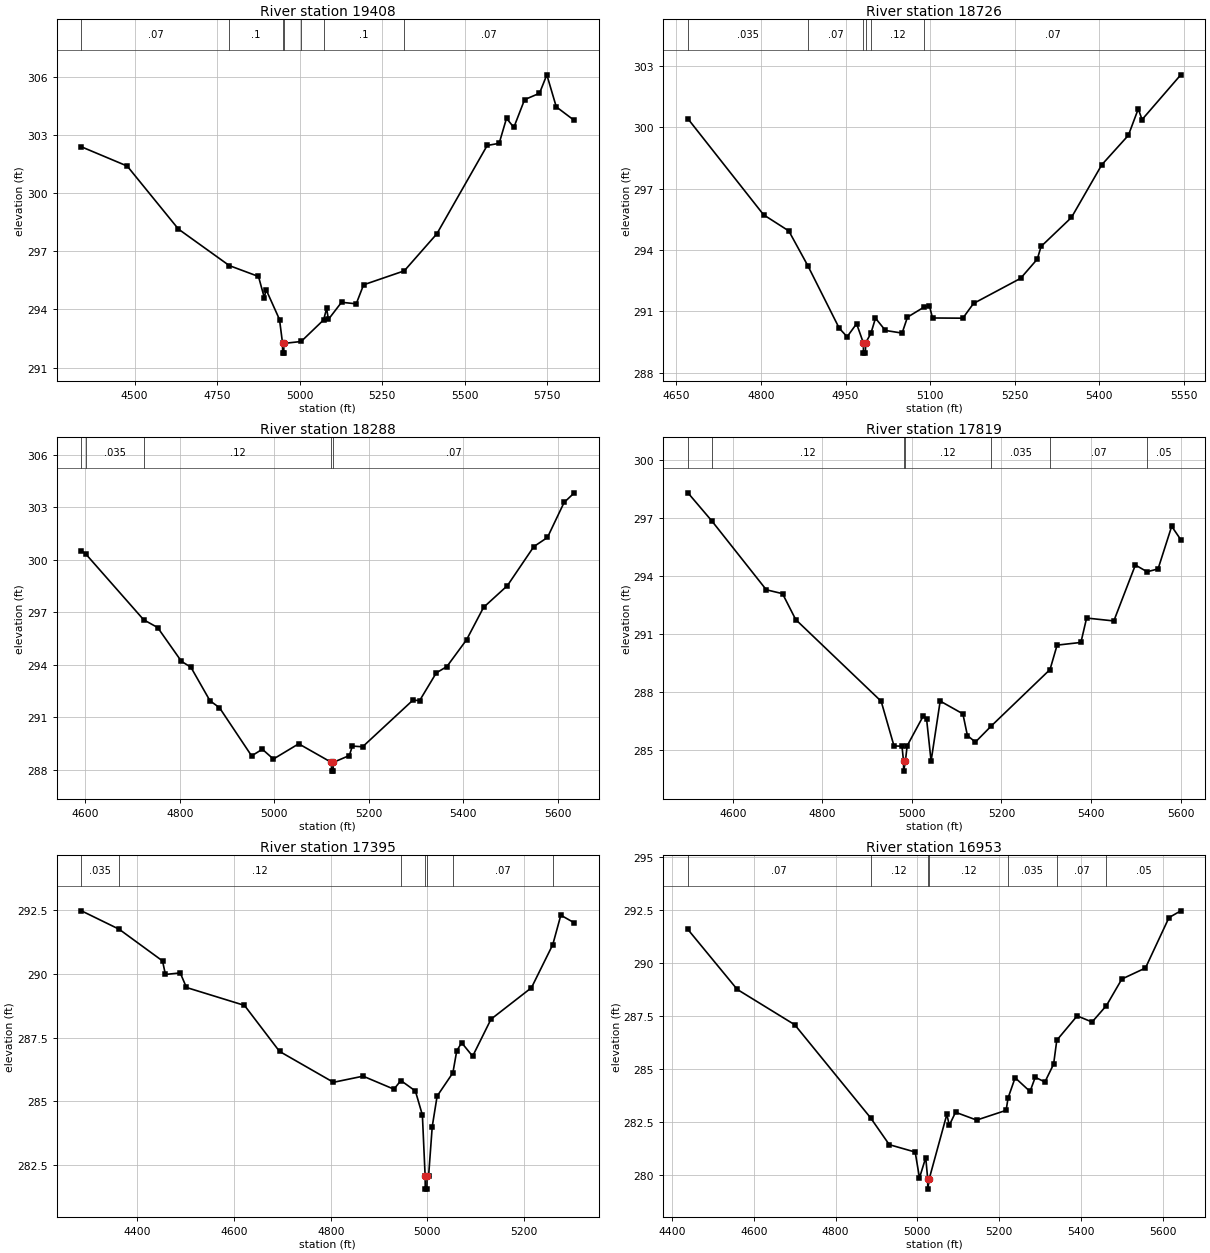
Type RM Length L Ch R = 1 ,19408   ,682,682,682
BEGIN DESCRIPTION:
COW CREEK 34.0
END DESCRIPTION:
XS GIS Cut Line= 3
      2451401.06     13498971.77       2451672.7     13498369.17
      2452033.28     13497620.03
#Sta/Elev= 30
    4339  302.38  4477.5  301.39  4632.8  298.14  4786.8  296.26  4875.1   295.7
  4892.7  294.61  4898.2  295.02  4938.8  293.48    4948  292.25  4948.2  291.75
  4951.7  291.75    4952  292.25  5004.3  292.35  5072.2  293.46  5081.4  294.05
  5086.9  293.49  5126.6  294.37  5171.1  294.29  5193.3  295.27  5316.6  295.99
  5415.3   297.9  5567.6  302.45  5603.9  302.56  5626.1  303.85  5648.3  303.38
  5680.8  304.81    5726  305.14  5748.2  306.09  5776.8  304.44  5831.4  303.74
#Mann= 7 ,-1 , 0
    4339     .07       0  4786.8      .1       0    4948     .05       0
    4952      .1       0  5004.3     .12       0  5072.2      .1       0
  5316.6     .07       0
Bank Sta=4948,4952
XS Rating Curve= 0 ,0
Exp/Cntr=0.3,0.1

Type RM Length L Ch R = 1 ,18726   ,438,438,438
BEGIN DESCRIPTION:
COW CREEK 33.0
END DESCRIPTION:
XS GIS Cut Line= 3
        2452375.     13498675.01        2452225.       13498375.
      2452025.01     13497875.03
#Sta/Elev= 30
  4670.5  300.42  4804.7  295.72  4849.4  294.93  4883.1  293.23  4938.8  290.17
  4952.8  289.75  4969.6  290.39  4981.6  289.45  4981.8  288.95  4985.3  288.95
  4985.6  289.45    4995  289.92  5003.1  290.66  5020.7  290.06  5050.3  289.93
  5059.8  290.71  5089.7  291.21  5098.8  291.26  5104.2  290.67    5158  290.66
  5176.9  291.38  5260.4  292.61    5290  293.55  5296.7  294.17  5350.6  295.59
  5404.4  298.17  5451.5  299.61    5469   300.9  5475.8  300.38  5544.4  302.57
#Mann= 6 ,-1 , 0
  4670.5    .035       0  4883.1     .07       0  4981.6     .05       0
  4985.6     .07       0    4995     .12       0  5089.7     .07       0
Bank Sta=4981.6,4985.6
XS Rating Curve= 0 ,0
Exp/Cntr=0.3,0.1

Type RM Length L Ch R = 1 ,18288   ,469,469,469
BEGIN DESCRIPTION:
COW CREEK 32.0
END DESCRIPTION:
XS GIS Cut Line= 3
      2452625.01     13498625.04        2452575.       13498225.
      2452074.98     13497824.98
#Sta/Elev= 30
  4591.7  300.52  4601.8   300.3  4723.5  296.57    4753  296.13  4803.4   294.2
  4823.5  293.86  4863.8  291.95    4884  291.55    4952   288.8  4974.7  289.18
  4998.1  288.62  5051.7  289.49  5120.9  288.43  5121.2  287.93  5124.7  287.93
  5124.9  288.43  5158.9  288.82  5165.3  289.36    5187  289.32  5293.4  291.98
  5307.8  291.96    5343  293.54  5365.4   293.9  5407.1  295.43  5443.1  297.28
  5493.5  298.52  5549.5  300.75  5578.3  301.27  5613.6  303.27  5635.2  303.82
#Mann= 5 ,-1 , 0
  4591.7     .05       0  4601.8    .035       0  4723.5     .12       0
  5120.9     .05       0  5124.9     .07       0
Bank Sta=5120.9,5124.9
XS Rating Curve= 0 ,0
Exp/Cntr=0.3,0.1

Type RM Length L Ch R = 1 ,17819   ,424,424,424
BEGIN DESCRIPTION:
COW CREEK 31.0
END DESCRIPTION:
XS GIS Cut Line= 3
        2452775.     13498575.01        2452975.       13498125.
        2452875.     13497525.02
#Sta/Elev= 30
  4499.9  298.31  4553.6  296.85    4675   293.3  4711.2   293.1  4740.7  291.76
  4931.5  287.54  4960.2  285.23    4978  285.22  4981.5  284.43  4981.7  283.93
  4985.5  284.43  4989.6  285.24  5025.3  286.77  5032.9  286.63    5043  284.45
  5063.3  287.55    5114  286.89  5124.1  285.77  5141.9  285.43  5177.3  286.26
  5308.6  289.18  5324.4  290.44  5377.6  290.58  5390.3  291.84  5451.1  291.69
  5499.2  294.58  5525.5  294.23  5549.9  294.38  5580.3  296.58  5600.6  295.89
#Mann= 7 ,-1 , 0
  4499.9     .07       0  4553.6     .12       0  4981.5     .05       0
  4985.5     .12       0  5177.3    .035       0  5308.6     .07       0
  5525.5     .05       0
Bank Sta=4981.5,4985.5
XS Rating Curve= 0 ,0
Exp/Cntr=0.3,0.1

Type RM Length L Ch R = 1 ,17395   ,442,442,442
BEGIN DESCRIPTION:
COW CREEK 30.0
END DESCRIPTION:
XS GIS Cut Line= 3
      2453125.01     13498574.95        2453275.       13497875.
        2453225.     13497574.98
#Sta/Elev= 30
    4284  292.46    4362  291.74  4451.8   290.5  4457.8  289.97  4488.5  290.03
  4501.3  289.46  4621.4  288.76  4693.9  286.96  4805.5  285.75  4866.9  285.99
  4930.8  285.48    4945  285.82  4975.1  285.41  4989.6  284.47  4995.3  282.07
  4995.5  281.57    4999  281.57  4999.3  282.07  5002.4  282.07    5010  284.02
  5020.1  285.21  5052.7  286.12  5060.7  286.98  5070.8   287.3  5093.6  286.77
  5131.6  288.22  5215.3  289.45  5259.5  291.14  5276.1  292.29    5304  291.99
#Mann= 7 ,-1 , 0
    4284    .035       0    4362     .12       0    4945    .035       0
  4995.3    .035       0  4999.3    .035       0  5052.7     .07       0
  5259.5     .05       0
Bank Sta=4995.3,4999.3
XS Rating Curve= 0 ,0
Exp/Cntr=0.3,0.1

Type RM Length L Ch R = 1 ,16953   ,494,494,494
BEGIN DESCRIPTION:
COW CREEK 29.0
END DESCRIPTION:
XS GIS Cut Line= 3
        2453725.     13498575.02        2453675.       13498025.
      2453325.01     13497475.01
#Sta/Elev= 30
  4439.2  291.58  4559.7  288.75  4700.3  287.08  4885.4  282.69  4931.2  281.42
  4994.5  281.07    5005  279.85  5020.3  280.81    5025  279.82  5025.3  279.32
    5029  279.82  5071.9  282.85  5077.8  282.33  5093.1  282.95  5144.7  282.58
  5216.7  283.04  5221.4  283.62  5238.7  284.58  5275.1  283.93  5287.8   284.6
  5311.5  284.38  5332.7  285.22  5340.5  286.35  5390.3   287.5  5426.7  287.21
  5461.9  287.99  5499.5  289.24  5557.1  289.76  5614.6  292.14  5643.4  292.46
#Mann= 7 ,-1 , 0
  4439.2     .07       0  4885.4     .12       0    5025     .05       0
    5029     .12       0  5221.4    .035       0  5340.5     .07       0
  5461.9     .05       0
Bank Sta=5025,5029
XS Rating Curve= 0 ,0
Exp/Cntr=0.3,0.1

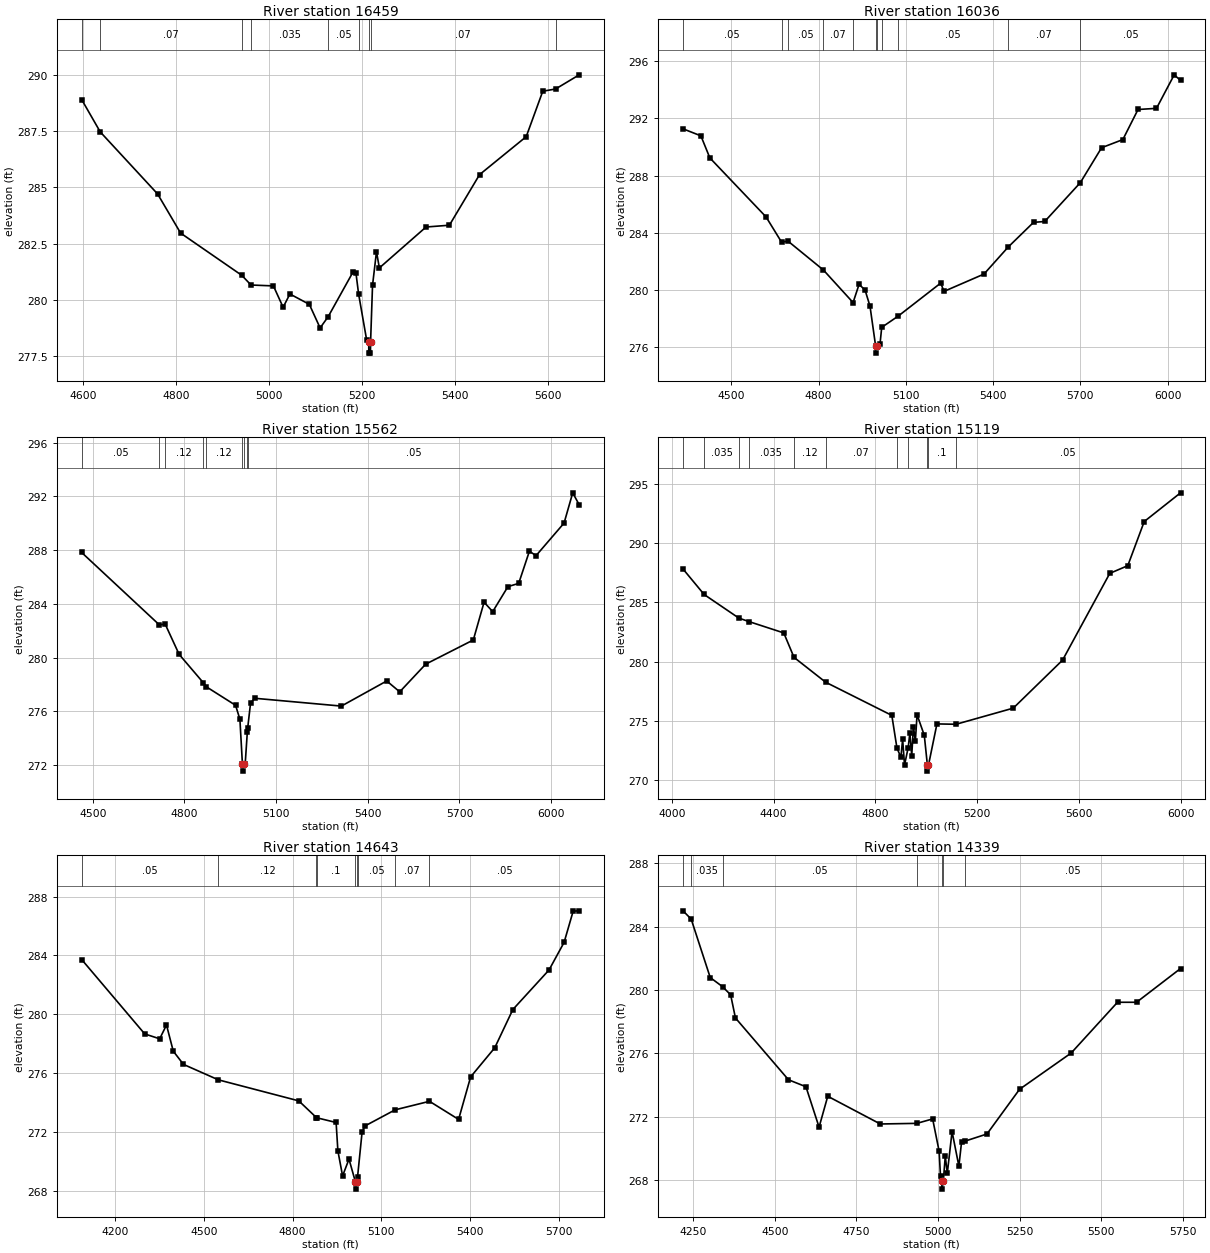
Type RM Length L Ch R = 1 ,16459   ,423,423,423
BEGIN DESCRIPTION:
COW CREEK 28.0
END DESCRIPTION:
XS GIS Cut Line= 3
      2454275.03     13498125.04        2454025.       13497825.
      2453475.03     13497425.02
#Sta/Elev= 30
  4596.8  288.91  4636.8  287.47  4760.2  284.71  4809.7  282.97  4941.4  281.09
  4961.2  280.66  5009.4  280.62  5030.3  279.67  5044.9  280.26  5086.7   279.8
  5109.9  278.75  5127.2  279.25    5181  281.25  5187.1  281.18  5192.8  280.25
  5209.9  278.23  5214.5  278.13  5214.7  277.63  5218.2  277.63  5218.5  278.13
  5222.7  280.65  5231.2  282.14  5237.4  281.42  5337.8  283.24  5388.1  283.32
    5453  285.57  5553.4  287.26    5589  289.28  5616.6  289.38  5667.4  290.01
#Mann= 9 ,-1 , 0
  4596.8     .05       0  4636.8     .07       0  4941.4     .12       0
  4961.2    .035       0  5127.2     .05       0  5192.8     .07       0
  5214.5    .035       0  5218.5     .07       0  5616.6     .05       0
Bank Sta=5214.5,5218.5
XS Rating Curve= 0 ,0
Exp/Cntr=0.3,0.1

Type RM Length L Ch R = 1 ,16036   ,474,474,474
BEGIN DESCRIPTION:
COW CREEK 27.0
END DESCRIPTION:
XS GIS Cut Line= 3
      2454424.99     13498224.95        2454275.       13497575.
      2453274.97     13497274.99
#Sta/Elev= 30
  4333.5  291.26    4395  290.77  4425.8  289.23  4619.1  285.11  4672.4  283.35
  4694.6  283.42  4816.5   281.4  4918.4  279.13    4939   280.4  4959.5  280.01
  4976.6  278.88  4995.9   276.1  4996.2   275.6    5000   276.1    5011  276.23
  5016.9   277.4  5073.9  278.19  5219.8  280.49  5231.1  279.91  5368.6  281.12
    5452  283.01  5539.1  284.73  5577.4  284.79  5699.9   287.5  5773.1  289.94
  5846.2  290.51  5898.4  292.61  5961.9  292.69  6022.8  295.03  6044.6  294.64
#Mann= 11 ,-1 , 0
  4333.5     .05       0  4672.4     .07       0  4694.6     .05       0
  4816.5     .07       0  4918.4    .035       0  4995.9    .035       0
    5000    .035       0  5016.9      .1       0  5073.9     .05       0
    5452     .07       0  5699.9     .05       0
Bank Sta=4995.9,5000
XS Rating Curve= 0 ,0
Exp/Cntr=0.3,0.1

Type RM Length L Ch R = 1 ,15562   ,443,443,443
BEGIN DESCRIPTION:
COW CREEK 26.0
END DESCRIPTION:
XS GIS Cut Line= 3
      2454825.03     13497575.03        2454475.       13497175.
      2453675.03     13496425.03
#Sta/Elev= 30
  4463.7  287.83  4717.6  282.45    4737   282.5  4782.6  280.25  4862.1  278.13
  4871.4  277.84  4967.3  276.46  4981.5  275.42  4989.8  272.06  4990.1  271.56
    4994  272.06  4998.7  272.06  5005.7  274.44  5006.9  274.75  5016.5  276.65
  5030.7  276.98  5313.5   276.4    5462  278.27  5504.5  277.46  5589.5  279.52
  5745.3  281.32  5780.5  284.13  5808.8  283.43  5858.6  285.29  5893.8  285.53
  5928.9  287.93  5950.4  287.59  6042.3  290.02  6070.6  292.27  6091.8  291.38
#Mann= 9 ,-1 , 0
  4463.7     .05       0  4717.6    .035       0    4737     .12       0
  4862.1     .07       0  4871.4     .12       0  4989.8     .05       0
    4994     .12       0  5005.7     .07       0  5006.9     .05       0
Bank Sta=4989.8,4994
XS Rating Curve= 0 ,0
Exp/Cntr=0.3,0.1

Type RM Length L Ch R = 1 ,15119   ,476,476,476
BEGIN DESCRIPTION:
COW CREEK 25.0
END DESCRIPTION:
XS GIS Cut Line= 3
      2455174.99     13497474.99        2454475.       13496825.
      2453675.03     13496225.02
#Sta/Elev= 30
  4044.2  287.81  4127.2  285.66  4263.7  283.67  4302.9  283.38  4440.2  282.42
  4480.4  280.36  4604.4  278.27  4864.8  275.47    4885  272.71  4900.5  271.94
  4907.3  273.46  4914.7  271.28    4929  272.75  4935.7  273.97    4943  272.08
  4949.8  274.53  4957.2  273.29    4964  275.52  4992.4  273.79  5004.6  271.27
  5004.9  270.77  5008.8  271.27  5042.1  274.75  5117.1  274.72  5342.1  276.08
  5535.9  280.13  5721.3  287.44  5792.1  288.09  5856.7  291.81  5999.4  294.23
#Mann= 11 ,-1 , 0
  4044.2     .05       0  4127.2    .035       0  4263.7     .05       0
  4302.9    .035       0  4480.4     .12       0  4604.4     .07       0
    4885     .05       0    4929      .1       0  5004.6     .05       0
  5008.8      .1       0  5117.1     .05       0
Bank Sta=5004.6,5008.8
XS Rating Curve= 0 ,0
Exp/Cntr=0.3,0.1

Type RM Length L Ch R = 1 ,14643   ,304,304,304
BEGIN DESCRIPTION:
COW CREEK 24.0
END DESCRIPTION:
XS GIS Cut Line= 3
      2455475.04     13496875.02        2454675.       13496425.
      2453924.98       13496275.
#Sta/Elev= 30
  4086.3  283.72  4299.6  278.66  4350.2  278.33  4373.2  279.27  4396.1  277.49
  4430.6  276.59  4548.6  275.54  4820.7  274.11  4880.5  272.97  4881.7  272.96
  4946.9  272.64  4952.9  270.71  4968.8  269.01  4990.5  270.15  5012.1  268.61
  5012.5  268.11  5016.7  268.61  5019.4  268.93  5034.8     272    5045  272.41
  5146.4   273.5  5262.7  274.08  5361.2  272.85  5401.9  275.74  5483.5  277.72
  5544.7  280.32  5667.1  283.01  5718.1  284.89  5748.7  287.01  5769.1  287.03
#Mann= 9 ,-1 , 0
  4086.3     .05       0  4548.6     .12       0  4880.5     .05       0
  4881.7      .1       0  5012.1     .05       0  5016.7      .1       0
  5019.4     .05       0  5146.4     .07       0  5262.7     .05       0
Bank Sta=5012.1,5016.7
XS Rating Curve= 0 ,0
Exp/Cntr=0.3,0.1

Type RM Length L Ch R = 1 ,14339   ,584,584,584
BEGIN DESCRIPTION:
COW CREEK 23.0
END DESCRIPTION:
XS GIS Cut Line= 3
      2455574.98     13496424.99       2454825.2     13496204.95
      2454229.44     13495761.47
#Sta/Elev= 30
  4218.6  284.99  4243.6  284.47    4302  280.78    4340   280.2  4364.5  279.69
  4379.2  278.23  4541.7  274.33  4595.2  273.89  4635.4  271.34    4662  273.29
    4823  271.54    4935  271.58  4983.3  271.86  5003.2  269.82  5007.4  268.23
  5011.2  267.93  5011.6  267.43    5016  267.93    5022  269.51  5028.2  268.43
  5042.8  271.06  5063.7  268.88    5072  270.42  5081.2  270.45  5149.8  270.91
  5249.6  273.73  5407.8  276.02  5549.6  279.22    5608  279.22  5742.7  281.35
#Mann= 7 ,-1 , 0
  4218.6     .05       0  4243.6    .035       0    4340     .05       0
    4935      .1       0  5011.2     .05       0    5016      .1       0
  5081.2     .05       0
Bank Sta=5011.2,5016
XS Rating Curve= 0 ,0
Exp/Cntr=0.3,0.1

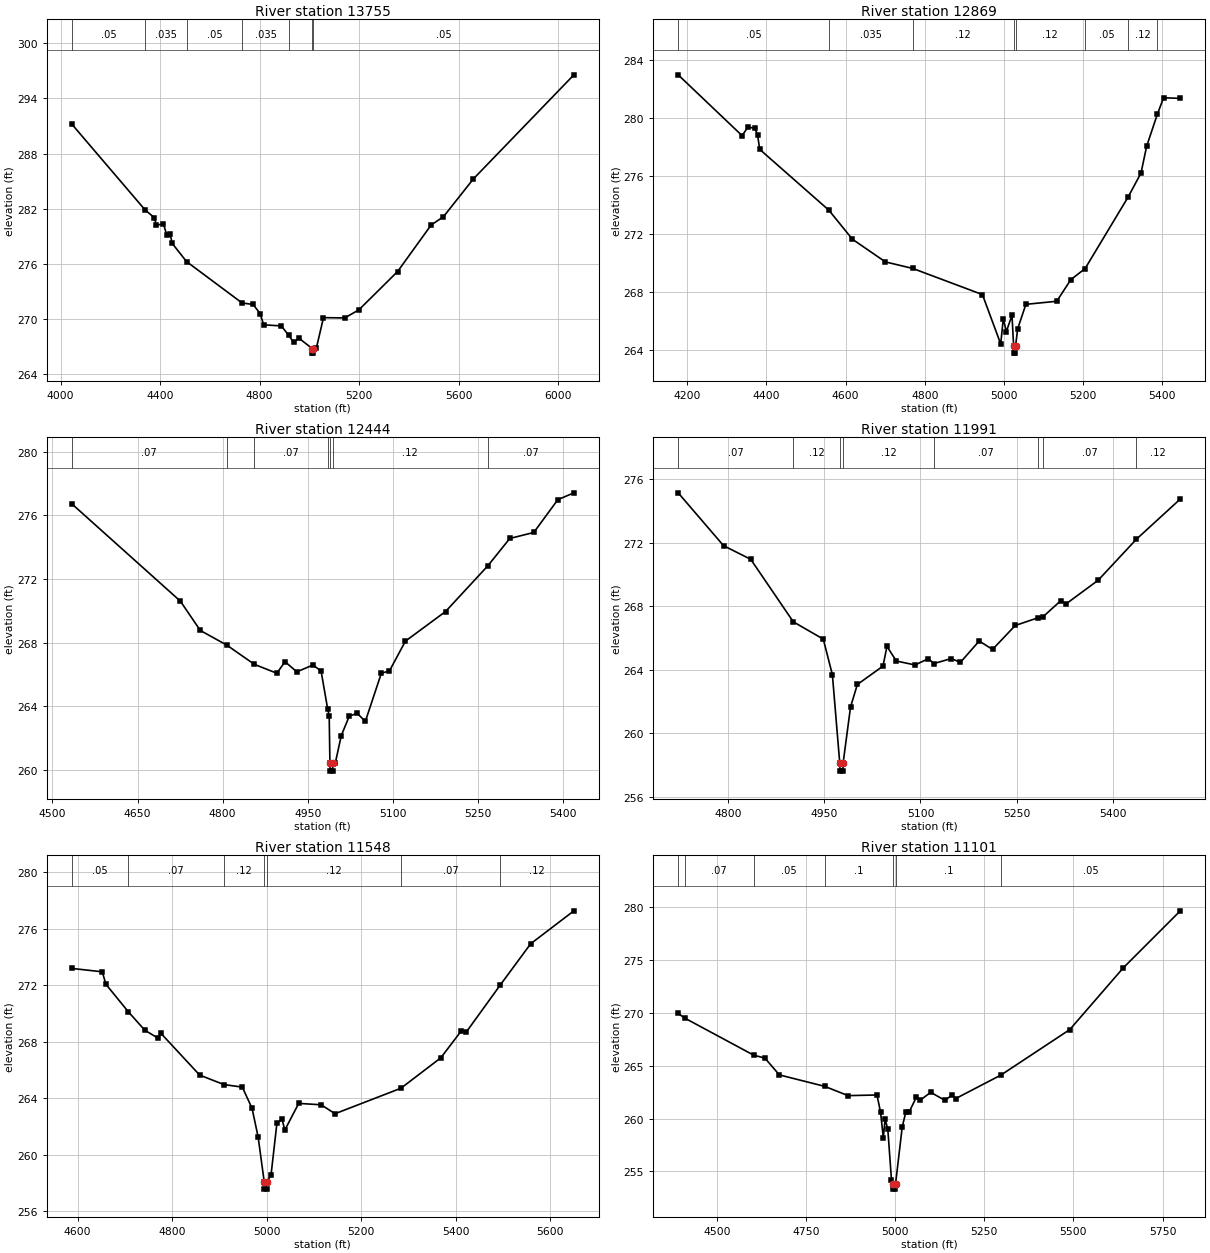
Type RM Length L Ch R = 1 ,13755   ,886,886,886
BEGIN DESCRIPTION:
COW CREEK 22.0
END DESCRIPTION:
XS GIS Cut Line= 3
        2455775.       13496525.        2455075.       13495875.
      2454374.98     13495074.97
#Sta/Elev= 30
  4044.9   291.2    4339  281.88  4377.4     281  4384.8  280.18  4413.1  280.37
    4427  279.11  4440.9  279.19  4448.3  278.23  4506.3  276.24  4729.9  271.73
  4773.7  271.58    4802  270.58  4816.2  269.36    4887  269.24  4917.5   268.2
  4936.4  267.45  4957.9   267.9  5011.5  266.78  5011.9  266.28    5016  266.28
  5016.3  266.78  5028.2  266.85  5056.6  270.14    5142  270.11    5199  270.99
  5354.6  275.16  5489.4  280.22  5538.8  281.12  5659.3  285.24  6063.2  296.56
#Mann= 7 ,-1 , 0
  4044.9     .05       0    4339    .035       0  4506.3     .05       0
  4729.9    .035       0  4917.5     .05       0  5011.5     .05       0
  5016.3     .05       0
Bank Sta=5011.5,5016.3
XS Rating Curve= 0 ,0
Exp/Cntr=0.3,0.1

Type RM Length L Ch R = 1 ,12869   ,425,425,425
BEGIN DESCRIPTION:
COW CREEK 21.0
END DESCRIPTION:
XS GIS Cut Line= 3
      2455825.02     13496175.04        2455525.       13495425.
        2455225.       13495075.
#Sta/Elev= 30
  4177.1  282.96  4338.7  278.77  4353.5  279.37    4371  279.27  4377.7  278.82
  4383.1  277.83  4557.9  273.64  4617.4  271.64  4700.8  270.08  4769.8  269.63
  4945.9  267.83  4992.1  264.43  4998.6  266.18  5006.3  265.28  5020.6  266.41
  5024.7   264.3  5025.1   263.8  5029.3   263.8  5029.7   264.3  5034.9  265.47
  5055.7  267.16  5133.6  267.37  5169.3  268.86  5205.3  269.62  5314.1  274.55
  5346.6   276.2  5360.8  278.04  5387.7  280.23  5403.6  281.38  5445.9  281.34
#Mann= 8 ,-1 , 0
  4177.1     .05       0  4557.9    .035       0  4769.8     .12       0
  5024.7     .05       0  5029.7     .12       0  5205.3     .05       0
  5314.1     .12       0  5387.7     .05       0
Bank Sta=5024.7,5029.7
XS Rating Curve= 0 ,0
Exp/Cntr=0.3,0.1

Type RM Length L Ch R = 1 ,12444   ,453,453,453
BEGIN DESCRIPTION:
COW CREEK 20.0
END DESCRIPTION:
XS GIS Cut Line= 3
      2456174.98     13495474.98        2455825.       13495175.
      2455525.01     13494875.01
#Sta/Elev= 30
    4534  276.72  4725.5   270.6  4760.6  268.76  4807.3  267.84  4855.9  266.63
  4895.6  266.07  4909.9   266.8  4930.7  266.16  4959.3  266.59  4973.5  266.21
    4985  263.85  4987.8   263.4  4989.1  260.42  4989.5  259.92  4993.8  259.92
  4994.2  260.42  4998.5  260.42  5009.1  262.15  5023.2  263.38  5037.4  263.55
  5051.5  263.04  5079.8  266.08  5093.9  266.21  5122.2  268.09  5192.9  269.95
  5267.4  272.82  5306.1  274.54  5348.5  274.92  5390.9  276.98  5419.2  277.41
#Mann= 7 ,-1 , 0
    4534     .07       0  4807.3     .05       0  4855.9     .07       0
    4985     .12       0  4989.1     .05       0  4994.2     .12       0
  5267.4     .07       0
Bank Sta=4989.1,4994.2
XS Rating Curve= 0 ,0
Exp/Cntr=0.3,0.1

Type RM Length L Ch R = 1 ,11991   ,443,443,443
BEGIN DESCRIPTION:
COW CREEK 19.0
END DESCRIPTION:
XS GIS Cut Line= 3
      2456374.98     13495174.98        2456175.       13494975.
      2455875.01     13494575.01
#Sta/Elev= 30
  4722.3  275.14    4793  271.81  4835.4  270.95  4901.8  267.01  4948.5  265.92
  4962.7  263.68  4974.2   258.1  4974.6   257.6    4979   257.6  4979.4   258.1
    4991  261.64  5001.6  263.06  5041.6  264.22  5047.8  265.46  5062.4  264.54
  5091.6  264.29  5112.4  264.69  5120.8  264.38  5147.8  264.69  5162.4  264.46
  5191.6   265.8  5212.4  265.27  5247.8  266.78  5283.6  267.27  5291.4  267.34
  5318.7  268.34    5327  268.14    5377  269.63  5436.5  272.21  5505.1  274.75
#Mann= 8 ,-1 , 0
  4722.3     .07       0  4901.8     .12       0  4974.2     .05       0
  4979.4     .12       0  5120.8     .07       0  5283.6     .12       0
  5291.4     .07       0  5436.5     .12       0
Bank Sta=4974.2,4979.4
XS Rating Curve= 0 ,0
Exp/Cntr=0.3,0.1

Type RM Length L Ch R = 1 ,11548   ,447,447,447
BEGIN DESCRIPTION:
COW CREEK 18.0
END DESCRIPTION:
XS GIS Cut Line= 3
      2456575.01     13495075.03        2456475.       13494675.
      2455875.04     13494425.02
#Sta/Elev= 30
  4587.7  273.18  4652.2  272.94  4659.9  272.06  4707.7   270.1  4742.3  268.81
  4770.7  268.24  4775.8  268.61  4858.3  265.64  4909.6  264.97  4948.5  264.79
  4969.1  263.29    4982  261.26  4994.9  258.08  4995.3  257.58  4999.7  257.58
  5000.1  258.08  5009.3  258.59  5021.7  262.24  5032.5  262.51  5038.5  261.76
  5067.8  263.64  5115.4  263.54  5144.7  262.91    5284  264.71  5368.4  266.86
  5411.7  268.76  5422.5  268.69  5494.5  272.02  5558.5  274.92    5650  277.25
#Mann= 7 ,-1 , 0
  4587.7     .05       0  4707.7     .07       0  4909.6     .12       0
  4994.9     .05       0  5000.1     .12       0    5284     .07       0
  5494.5     .12       0
Bank Sta=4994.9,5000.1
XS Rating Curve= 0 ,0
Exp/Cntr=0.3,0.1

Type RM Length L Ch R = 1 ,11101   ,481,481,481
BEGIN DESCRIPTION:
COW CREEK 17.0
END DESCRIPTION:
XS GIS Cut Line= 3
        2456675.     13494974.98        2456775.       13494375.
        2456775.     13493574.96
#Sta/Elev= 30
  4391.5  269.96  4410.3  269.51  4603.2  266.01  4634.8  265.73  4675.3  264.14
  4802.1  263.06    4868  262.18  4949.1  262.24  4959.2  260.59  4966.8  258.19
  4971.9  259.95  4979.5  258.99  4989.6  254.24  4993.3  253.83  4993.8  253.33
  5000.7  253.33  5001.2  253.83  5019.8   259.2  5029.8  260.61  5039.8  260.67
  5059.8  262.05  5069.8  261.74  5099.8  262.49  5139.8  261.73  5159.8  262.25
  5169.8   261.9  5296.9  264.13  5489.8  268.43  5639.8  274.27  5799.8  279.67
#Mann= 7 ,-1 , 0
  4391.5     .05       0  4410.3     .07       0  4603.2     .05       0
  4802.1      .1       0  4993.3     .05       0  5001.2      .1       0
  5296.9     .05       0
Bank Sta=4993.3,5001.2
XS Rating Curve= 0 ,0
Exp/Cntr=0.3,0.1

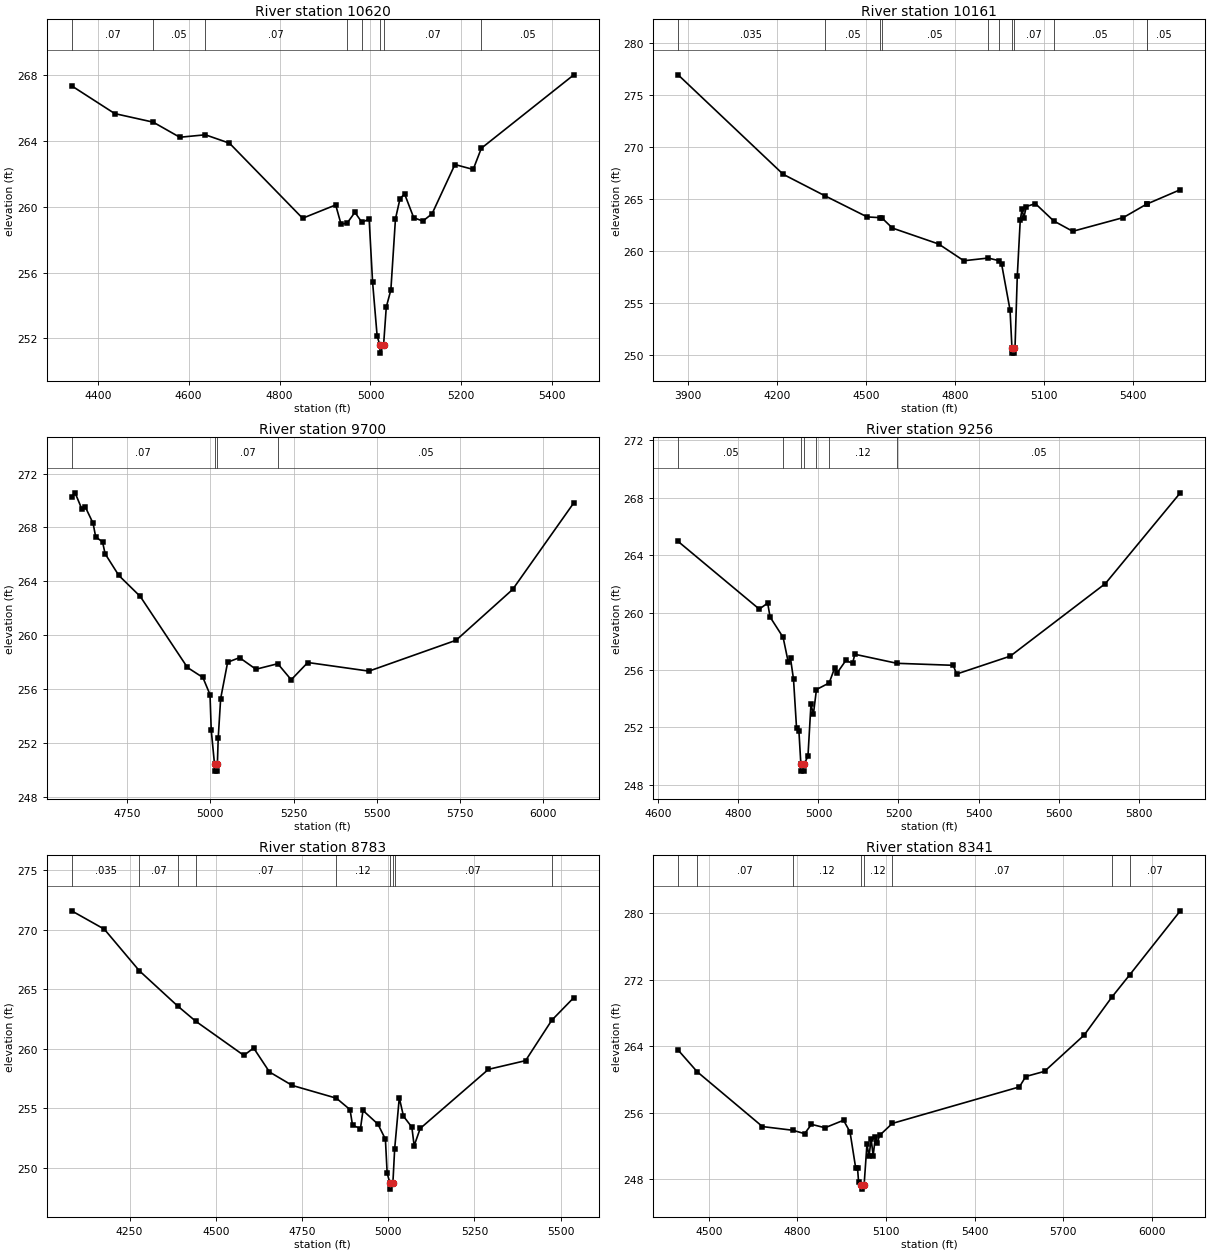
Type RM Length L Ch R = 1 ,10620   ,459,459,459
BEGIN DESCRIPTION:
COW CREEK 16.0
END DESCRIPTION:
XS GIS Cut Line= 3
      2456875.01     13494924.98        2457225.       13494375.
        2457175.     13493924.97
#Sta/Elev= 30
  4342.7  267.37  4437.5  265.68    4522  265.16  4580.6  264.24  4636.8  264.39
  4689.8  263.88  4850.7  259.31  4923.5  260.12  4935.3  258.95  4948.6  259.01
  4965.8  259.67  4981.2  259.06  4997.1  259.26  5004.7  255.42  5014.7  252.14
  5020.6   251.6  5021.1   251.1  5028.9   251.6  5034.8   253.9  5044.9  254.95
    5055  259.27    5065   260.5  5075.1  260.79  5095.2  259.34  5115.3  259.14
  5135.5  259.58  5185.8  262.58    5226  262.28  5243.9  263.57  5447.4  268.04
#Mann= 8 ,-1 , 0
  4342.7     .07       0    4522     .05       0  4636.8     .07       0
  4948.6      .1       0  4981.2     .07       0  5020.6     .05       0
  5028.9     .07       0  5243.9     .05       0
Bank Sta=5020.6,5028.9
XS Rating Curve= 0 ,0
Exp/Cntr=0.3,0.1

Type RM Length L Ch R = 1 ,10161   ,461,461,461
BEGIN DESCRIPTION:
COW CREEK 15.0
END DESCRIPTION:
XS GIS Cut Line= 3
      2456824.97     13495325.03        2457625.       13494525.
      2457525.01     13493975.03
#Sta/Elev= 30
    3868  276.93  4221.6  267.37    4361  265.32  4504.4  263.27  4548.9   263.2
  4554.8  263.15  4589.3   262.2  4744.9  260.67  4829.7  259.06  4911.8  259.32
    4949  259.06    4957  258.73  4985.3  254.32  4991.7  250.68  4992.2  250.18
  4999.5  250.18    5000  250.68    5002  250.68  5009.6  257.55  5019.7     263
  5026.1  264.07  5031.2  263.14  5040.1  264.27  5070.6  264.55  5132.1  262.89
  5196.3  261.89  5366.6  263.21  5444.8   264.5  5446.7  264.52  5558.4  265.89
#Mann= 11 ,-1 , 0
    3868    .035       0    4361     .05       0  4548.9    .035       0
  4554.8     .05       0  4911.8      .1       0    4949     .07       0
  4991.7     .05       0    5000     .07       0  5132.1     .05       0
  5444.8     .07       0  5446.7     .05       0
Bank Sta=4991.7,5000
XS Rating Curve= 0 ,0
Exp/Cntr=0.3,0.1

Type RM Length L Ch R = 1 ,9700    ,444,444,444
BEGIN DESCRIPTION:
COW CREEK 14.0
END DESCRIPTION:
XS GIS Cut Line= 3
        2457775.       13495275.        2457875.       13494875.
      2458625.01     13494074.99
#Sta/Elev= 30
    4583  270.29  4593.3  270.57  4613.9  269.35  4624.2  269.51  4647.4  268.31
  4655.2   267.3  4675.8  266.93  4683.5  266.05  4724.7  264.44  4789.2  262.88
  4930.9  257.61  4977.3  256.87  4998.7   255.6  5002.4  252.96  5012.3  250.42
  5012.8  249.92  5020.3  249.92  5020.8  250.42  5023.4  252.39  5030.7   255.3
  5051.7     258  5087.4  258.34  5136.7  257.48  5202.3  257.89  5242.7   256.7
  5292.5  257.98  5476.2  257.34    5738  259.63    5908   263.4  6091.9  269.83
#Mann= 4 ,-1 , 0
    4583     .07       0  5012.3     .05       0  5020.8     .07       0
  5202.3     .05       0
Bank Sta=5012.3,5020.8
XS Rating Curve= 0 ,0
Exp/Cntr=0.3,0.1

Type RM Length L Ch R = 1 ,9256    ,473,473,473
BEGIN DESCRIPTION:
COW CREEK 13.0
END DESCRIPTION:
XS GIS Cut Line= 3
      2458075.02     13495224.98        2458275.       13494925.
      2458675.02     13494124.96
#Sta/Elev= 30
  4649.3  264.96  4852.1  260.24  4873.1  260.66  4879.1  259.69  4911.7  258.27
  4924.2  256.58  4930.2   256.8  4937.7  255.34  4945.2  251.97  4951.2  251.73
    4956  249.44  4956.5  248.94    4964  248.94  4964.5  249.44  4973.8  249.99
  4981.3   253.6  4987.3   252.9    4995  254.63  5026.8  255.09  5040.6  256.14
  5046.2  255.77  5068.5  256.66  5085.3  256.46  5090.9  257.09  5196.1  256.46
  5336.9  256.32  5345.2  255.71  5479.4  256.96    5717  262.02  5904.3  268.35
#Mann= 7 ,-1 , 0
  4649.3     .05       0  4911.7     .12       0    4956     .05       0
  4964.5     .12       0    4995     .05       0  5026.8     .12       0
  5196.1     .05       0
Bank Sta=4956,4964.5
XS Rating Curve= 0 ,0
Exp/Cntr=0.3,0.1

Type RM Length L Ch R = 1 ,8783    ,442,442,442
BEGIN DESCRIPTION:
COW CREEK 12.0
END DESCRIPTION:
XS GIS Cut Line= 3
      2458274.99     13495675.01        2458725.       13494875.
        2458925.     13494375.01
#Sta/Elev= 30
    4082  271.57  4176.7  270.03  4278.3  266.54  4389.6  263.58  4441.7  262.31
  4581.4  259.44  4609.8  260.06  4655.7  258.05  4721.7  256.92  4849.8  255.85
  4889.3  254.89  4896.6  253.58  4919.6   253.3  4926.9  254.82  4970.3  253.67
  4991.9  252.41    4997  249.56    5005  248.72  5005.5  248.22  5013.6  248.72
  5018.8  251.61  5032.2  255.89  5044.3  254.34  5068.6  253.42  5075.3  251.86
  5092.8  253.31  5290.7  258.27  5398.4     259  5474.4  262.39  5538.4  264.29
#Mann= 9 ,-1 , 0
    4082    .035       0  4278.3     .07       0  4389.6    .035       0
  4441.7     .07       0  4849.8     .12       0    5005     .05       0
  5013.6     .12       0  5018.8     .07       0  5474.4     .12       0
Bank Sta=5005,5013.6
XS Rating Curve= 0 ,0
Exp/Cntr=0.3,0.1

Type RM Length L Ch R = 1 ,8341    ,450,450,450
BEGIN DESCRIPTION:
COW CREEK 11.0
END DESCRIPTION:
XS GIS Cut Line= 3
      2458774.98     13495575.04        2459025.       13495025.
      2459775.01     13494224.98
#Sta/Elev= 30
  4395.8  263.55  4460.4  260.94  4681.4  254.35  4783.6  253.91  4824.2   253.5
  4847.3  254.62  4893.4  254.21  4956.1  255.11    4978   253.7  4997.2  249.37
  5003.4  249.37  5007.1  247.66  5016.8  247.33  5017.3  246.83  5025.7  247.33
  5035.4  252.24  5042.3  250.77  5049.6  252.86  5056.4  250.84  5063.7  253.06
  5070.6  252.39  5077.9  253.28  5121.2  254.73  5551.7  259.12  5573.2  260.37
  5636.7  260.99    5771  265.35  5864.9  269.92  5924.9  272.58  6096.6  280.29
#Mann= 8 ,-1 , 0
  4395.8    .035       0  4460.4     .07       0  4783.6     .12       0
  5016.8     .05       0  5025.7     .12       0  5121.2     .07       0
  5864.9     .05       0  5924.9     .07       0
Bank Sta=5016.8,5025.7
XS Rating Curve= 0 ,0
Exp/Cntr=0.3,0.1