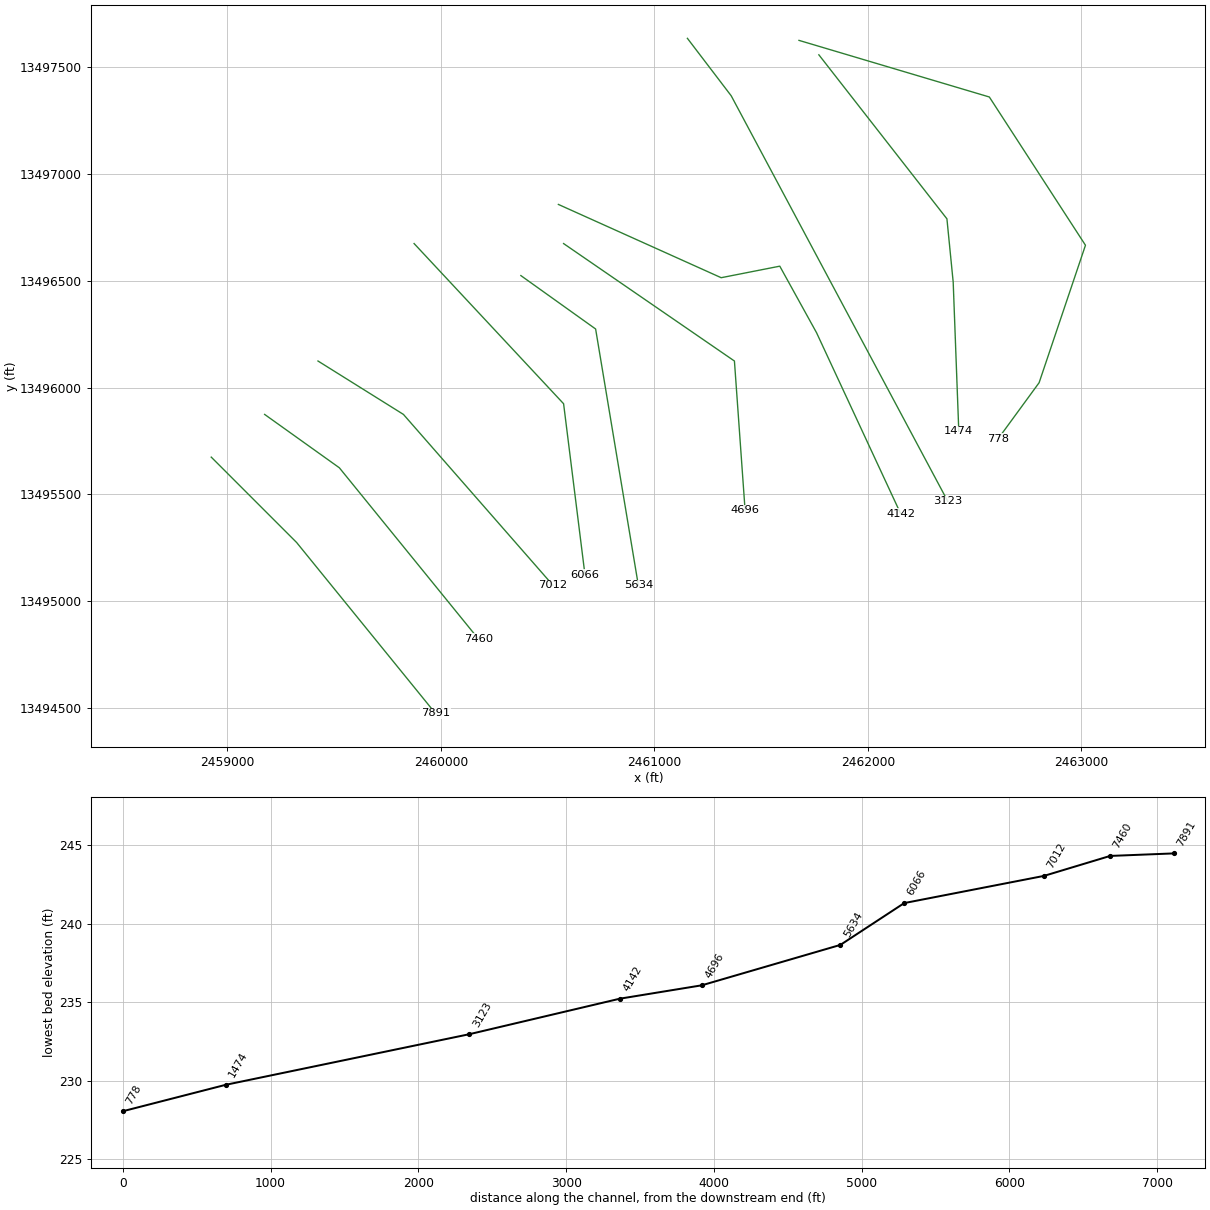
HEC-RAS study COW CREEK.prj: COW CREEK Base Level Engineering

--- COW CREEK.g01 (geometry) --- (continued)

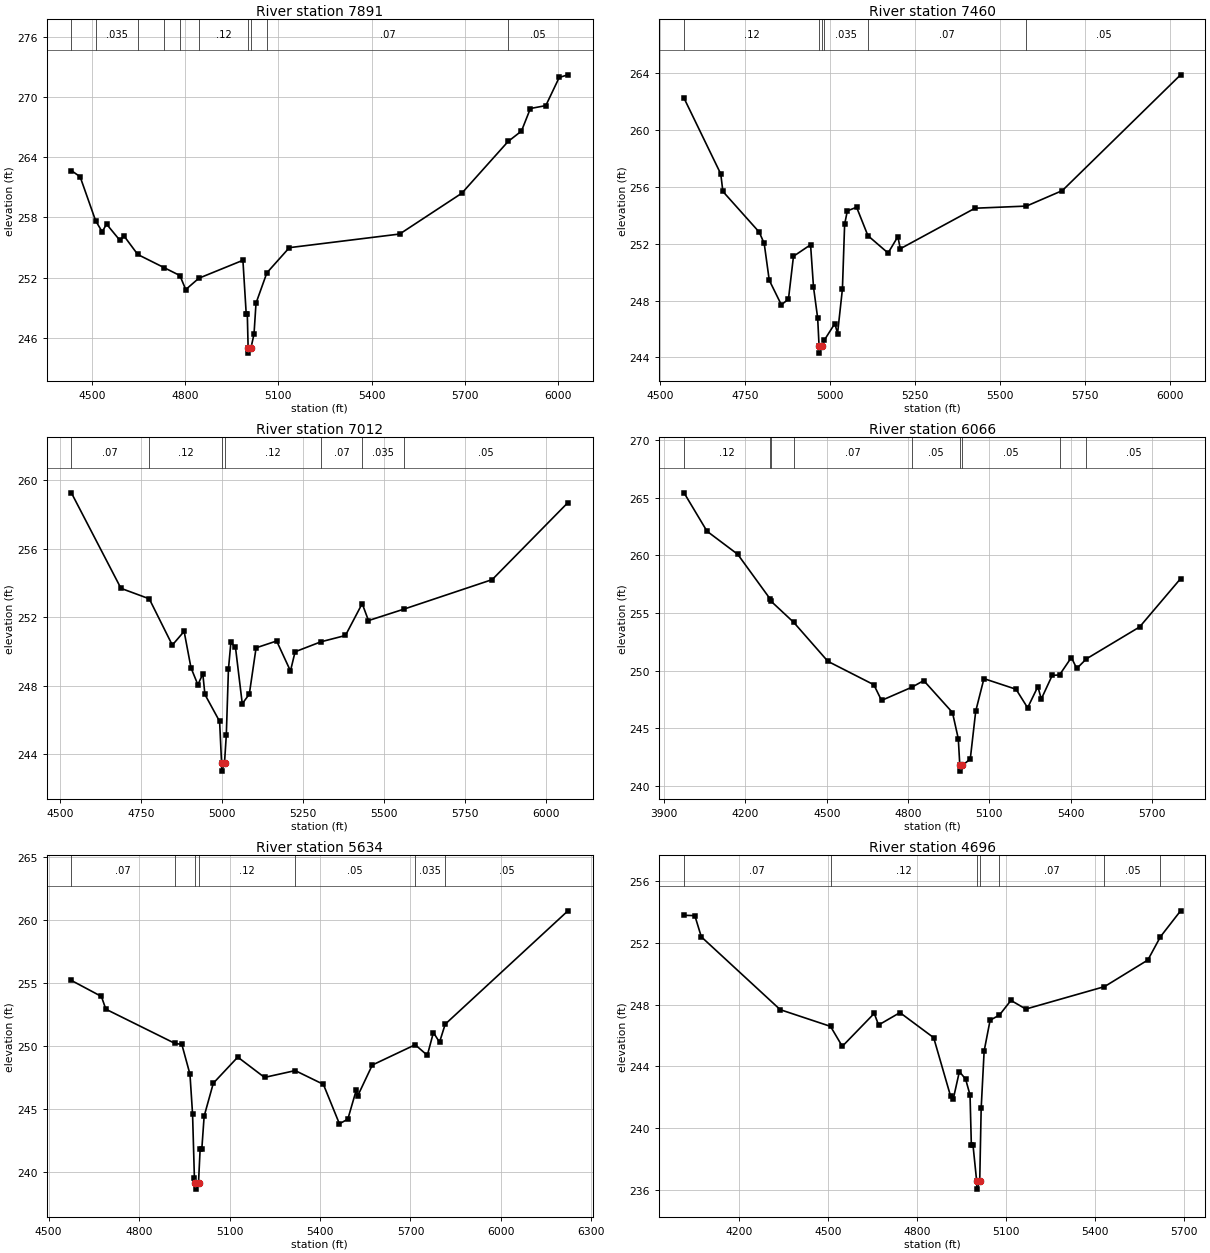
Type RM Length L Ch R = 1 ,7891    ,431,431,431
BEGIN DESCRIPTION:
COW CREEK 10.0
END DESCRIPTION:
XS GIS Cut Line= 3
      2458925.03     13495674.97        2459325.       13495275.
      2459974.99     13494475.01
#Sta/Elev= 30
  4434.6  262.67  4462.8  262.05  4512.4  257.68  4533.6  256.56  4547.7  257.33
  4590.1  255.73  4604.3  256.13    4648   254.3  4733.8  252.97  4783.5   252.2
  4802.3   250.8  4844.4  251.93  4986.1  253.72  4996.7  248.38  5000.2  248.38
  5002.9  244.96  5003.4  244.46  5011.9  244.96  5021.8  246.37  5028.2  249.44
  5063.1  252.47  5135.3  254.98  5490.1  256.34  5689.8  260.41  5838.6  265.57
  5881.6  266.61  5910.3  268.86  5959.9  269.15    6003  271.96    6031  272.22
#Mann= 10 ,-1 , 0
  4434.6     .12       0  4512.4    .035       0    4648     .07       0
  4733.8     .12       0  4783.5     .07       0  4844.4     .12       0
  5002.9     .05       0  5011.9     .12       0  5063.1     .07       0
  5838.6     .05       0
Bank Sta=5002.9,5011.9
XS Rating Curve= 0 ,0
Exp/Cntr=0.3,0.1

Type RM Length L Ch R = 1 ,7460    ,448,448,448
BEGIN DESCRIPTION:
COW CREEK 9.0
END DESCRIPTION:
XS GIS Cut Line= 3
      2459175.01     13495874.99        2459525.       13495625.
      2460175.02     13494824.98
#Sta/Elev= 30
    4570  262.23  4678.1   256.9  4684.3  255.67  4791.2  252.81  4805.9  252.01
  4820.7  249.43  4856.3   247.7  4877.2  248.09    4892  251.11  4942.3  251.92
  4950.9  248.95  4963.2  246.76  4967.3   244.8  4967.8   244.3  4976.4   244.8
  4982.7  245.21  5013.7  246.38  5021.7  245.68    5036  248.81  5042.5  253.36
  5050.4   254.3  5077.7  254.56    5111  252.56  5170.3  251.34  5199.1  252.49
  5206.3  251.64    5426  254.49  5577.5  254.64    5683  255.73  6030.9  263.87
#Mann= 6 ,-1 , 0
    4570     .12       0  4967.3    .035       0  4976.4     .12       0
  4982.7    .035       0    5111     .07       0  5577.5     .05       0
Bank Sta=4967.3,4976.4
XS Rating Curve= 0 ,0
Exp/Cntr=0.3,0.1

Type RM Length L Ch R = 1 ,7012    ,946,946,946
BEGIN DESCRIPTION:
COW CREEK 8.0
END DESCRIPTION:
XS GIS Cut Line= 3
      2459424.96     13496125.02        2459825.       13495875.
      2460525.03     13495074.97
#Sta/Elev= 30
  4534.1  259.26  4687.4  253.69  4774.8  253.08  4846.1  250.38  4882.6  251.18
  4903.8  249.06  4925.1  248.07  4940.4   248.7  4946.9   247.5  4992.3  245.93
  4998.3  243.53  4998.8  243.03  5007.5  243.53    5013  245.14  5019.6  248.98
  5027.2  250.54  5041.4  250.24  5062.3  246.96  5084.1  247.52    5105  250.22
  5168.6  250.62  5211.3  248.87  5225.6  249.99  5305.1  250.57  5381.2  250.94
    5433   252.8  5452.4  251.81  5560.8  252.47  5834.9   254.2  6068.9  258.69
#Mann= 7 ,-1 , 0
  4534.1     .07       0  4774.8     .12       0  4998.3     .05       0
  5007.5     .12       0  5305.1     .07       0    5433    .035       0
  5560.8     .05       0
Bank Sta=4998.3,5007.5
XS Rating Curve= 0 ,0
Exp/Cntr=0.3,0.1

Type RM Length L Ch R = 1 ,6066    ,432,432,432
BEGIN DESCRIPTION:
COW CREEK 7.0
END DESCRIPTION:
XS GIS Cut Line= 3
      2459874.97     13496675.03        2460575.       13495925.
        2460675.     13495124.98
#Sta/Elev= 30
  3973.4  265.43  4058.2   262.1  4171.5   260.1  4291.1  256.23  4294.1  256.04
  4378.5  254.19  4504.2  250.82  4673.8  248.79  4702.1  247.43  4814.4  248.58
  4857.9  249.15  4963.9  246.38  4985.4  244.11    4991   241.8  4991.5   241.3
  5000.9   241.8  5029.6  242.35  5049.7   246.5    5080  249.32  5198.4   248.4
  5241.2  246.79    5279  248.63  5291.6  247.55  5331.9   249.6  5358.9  249.64
  5402.5  251.15  5422.6   250.2  5457.9  251.03  5654.4   253.8  5805.6  257.99
#Mann= 9 ,-1 , 0
  3973.4     .12       0  4291.1     .07       0  4294.1     .12       0
  4378.5     .07       0  4814.4     .05       0    4991     .05       0
  5000.9     .05       0  5358.9    .035       0  5457.9     .05       0
Bank Sta=4991,5000.9
XS Rating Curve= 0 ,0
Exp/Cntr=0.3,0.1

Type RM Length L Ch R = 1 ,5634    ,938,938,938
BEGIN DESCRIPTION:
COW CREEK 6.0
END DESCRIPTION:
XS GIS Cut Line= 3
      2460374.97     13496525.02        2460725.       13496275.
        2460925.     13495075.01
#Sta/Elev= 30
  4575.5  255.19  4675.1  253.92  4689.8  252.91  4919.5  250.19  4941.8  250.12
  4968.8  247.75  4977.4   244.6  4983.5  239.54  4987.1  239.14  4987.6  238.64
  4997.1  239.14  5002.6  241.86  5008.2  241.86  5015.8  244.42  5046.2  247.04
  5127.3  249.11    5216   247.5  5317.8  248.04  5411.2  246.95  5464.4  243.82
  5492.3  244.19  5520.2  246.49  5525.2  246.04  5573.4  248.48  5715.7  250.09
  5755.9  249.25  5776.1  251.06  5796.4  250.29  5815.2  251.72  6222.2  260.71
#Mann= 7 ,-1 , 0
  4575.5     .07       0  4919.5     .12       0  4987.1     .05       0
  4997.1     .12       0  5317.8     .05       0  5715.7    .035       0
  5815.2     .05       0
Bank Sta=4987.1,4997.1
XS Rating Curve= 0 ,0
Exp/Cntr=0.3,0.1

Type RM Length L Ch R = 1 ,4696    ,554,554,554
BEGIN DESCRIPTION:
COW CREEK 5.0
END DESCRIPTION:
XS GIS Cut Line= 3
      2460574.98     13496675.01        2461375.       13496125.
        2461425.     13495425.03
#Sta/Elev= 30
  4014.8  253.77  4051.2  253.75    4073  252.38  4338.9  247.67  4508.3  246.59
  4547.9   245.3  4655.5  247.43  4670.1  246.68  4742.1  247.48  4855.7  245.86
  4912.8  242.07  4921.4  241.87  4942.3  243.67  4963.3  243.18  4978.2  242.15
  4982.6  238.91  4988.2  238.91  5000.6  236.57  5001.1  236.07  5010.8  236.57
  5015.7   241.3  5025.7     245  5045.8  246.99  5077.1  247.32    5116  248.27
  5166.1  247.71  5431.1  249.16  5577.1  250.88  5619.7  252.39  5687.4  254.06
#Mann= 7 ,-1 , 0
  4014.8     .07       0  4508.3     .12       0  5000.6     .05       0
  5010.8     .12       0  5077.1     .07       0  5431.1     .05       0
  5619.7    .035       0
Bank Sta=5000.6,5010.8
XS Rating Curve= 0 ,0
Exp/Cntr=0.3,0.1

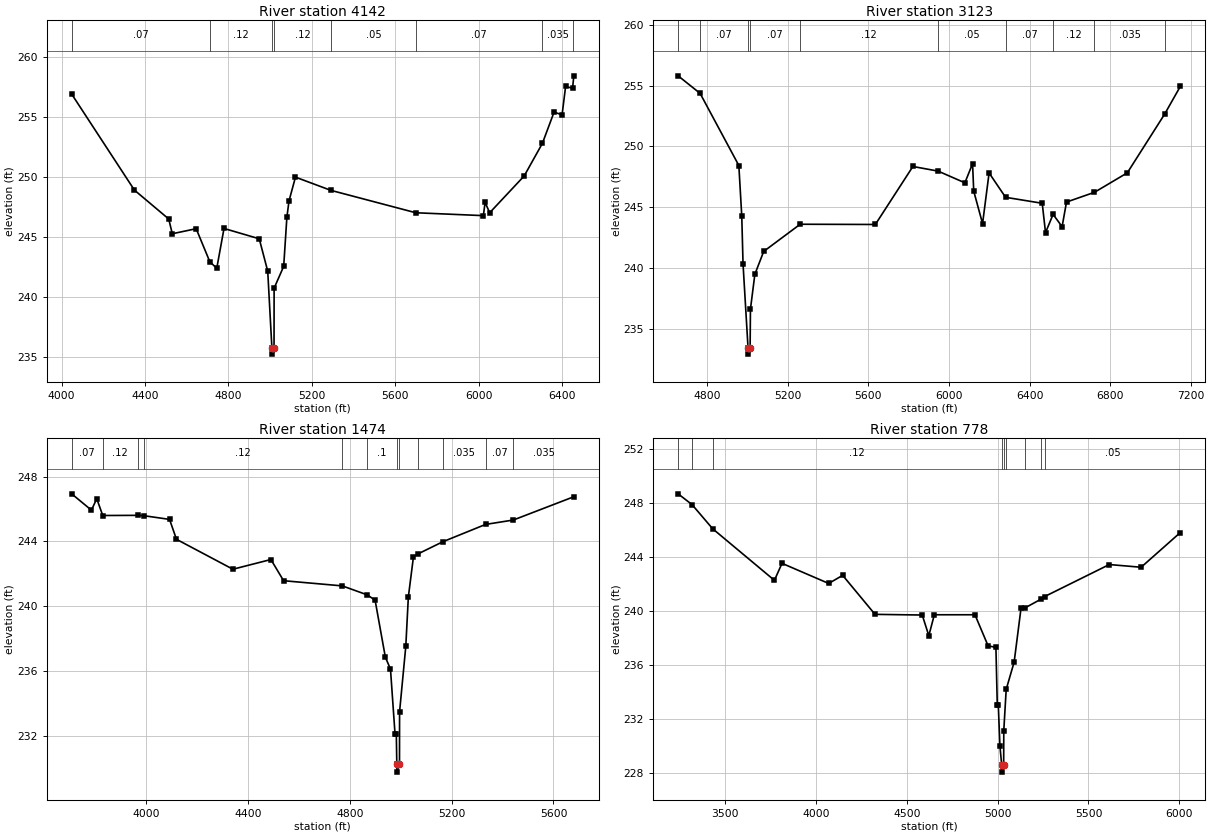
Type RM Length L Ch R = 1 ,4142    ,1019,1019,1019
BEGIN DESCRIPTION:
Mapping XS b57f901b
END DESCRIPTION:
XS GIS Cut Line= 5
      2460550.66     13496858.27      2461312.91     13496515.17
      2461587.36     13496569.16      2461759.56     13496257.47
       2462153.9     13495409.15
#Sta/Elev= 30
  4048.4  256.91  4349.2   248.9  4513.7  246.49  4530.8  245.26  4645.3  245.68
  4710.8  242.92    4744  242.38  4778.7   245.7  4947.6  244.84  4988.3  242.14
  5008.3  235.72  5008.8  235.22  5018.5  235.72  5018.9  240.72  5064.8  242.54
  5080.1  246.64  5090.3     248  5121.2  249.98  5290.8  248.88  5698.2  247.01
    6022  246.77  6030.1  247.88  6052.2  247.01  6217.6  250.08  6304.9   252.8
  6360.9  255.41  6399.2  255.17  6416.1  257.54  6449.4   257.4  6455.6  258.43
#Mann= 8 ,-1 , 0
  4048.4     .07       0  4710.8     .12       0  5008.3     .05       0
  5018.5     .12       0  5290.8     .05       0  5698.2     .07       0
  6304.9    .035       0  6449.4     .05       0
Bank Sta=5008.3,5018.5
XS Rating Curve= 0 ,0
Exp/Cntr=0.3,0.1

Type RM Length L Ch R = 1 ,3123    ,1649,1649,1649
BEGIN DESCRIPTION:
Mapping XS 1a22db36
END DESCRIPTION:
XS GIS Cut Line= 3
       2461154.8     13497636.06      2461359.91     13497366.93
      2462373.89     13495468.42
#Sta/Elev= 30
  4656.3   255.8  4765.3  254.36  4957.5  248.44    4972  244.27  4978.3  240.36
  5003.1  233.46  5003.6  232.96  5013.4  233.46    5015  236.65  5036.9  239.51
  5080.8  241.39  5261.8  243.62  5634.5   243.6  5820.7  248.36  5945.8  247.98
  6078.5  247.02  6116.7  248.59  6122.4  246.34  6166.3  243.67  6198.6  247.83
  6280.4  245.83  6462.2  245.34  6478.5  242.93    6516  244.43  6560.7  243.42
  6582.6  245.44  6721.2  246.24  6884.2  247.84  7069.8  252.67    7147  254.93
#Mann= 10 ,-1 , 0
  4656.3     .05       0  4765.3     .07       0  5003.1     .05       0
  5013.4     .07       0  5261.8     .12       0  5945.8     .05       0
  6280.4     .07       0    6516     .12       0  6721.2    .035       0
  7069.8     .07       0
Bank Sta=5003.1,5013.4
XS Rating Curve= 0 ,0
Exp/Cntr=0.3,0.1

Type RM Length L Ch R = 1 ,1474    ,696,696,696
BEGIN DESCRIPTION:
Mapping XS b40551c2
END DESCRIPTION:
XS GIS Cut Line= 4
      2461770.39     13497558.86      2462370.04     13496790.83
      2462399.41     13496494.46      2462425.65     13495795.78
#Sta/Elev= 30
  3708.5  246.94  3786.2  245.93    3807  246.64  3830.6   245.6  3968.8  245.61
  3991.4  245.59  4092.8  245.36  4119.9  244.13  4341.5  242.28  4490.7  242.88
  4540.5  241.57    4771  241.25  4869.8  240.69  4899.8  240.36    4940  236.84
  4960.1  236.11  4977.9  232.11    4983  232.11  4984.9  230.24  4985.4  229.74
  4995.5  230.24  4995.8  233.47  5020.2  237.51  5030.2  240.56  5050.2  243.04
  5067.2  243.22  5165.8  243.98  5333.5  245.05  5442.1  245.32  5679.9  246.76
#Mann= 12 ,-1 , 0
  3708.5     .07       0  3830.6     .12       0  3968.8     .07       0
  3991.4     .12       0    4771     .07       0  4869.8      .1       0
  4984.9     .05       0  4995.5      .1       0  5067.2     .12       0
  5165.8    .035       0  5333.5     .07       0  5442.1    .035       0
Bank Sta=4984.9,4995.5
XS Rating Curve= 0 ,0
Exp/Cntr=0.3,0.1

Type RM Length L Ch R = 1 ,778     ,0,0,0
BEGIN DESCRIPTION:
COW CREEK 1.0
END DESCRIPTION:
XS GIS Cut Line= 5
      2461677.32     13497626.49       2462568.7     13497361.35
      2463018.81     13496667.18      2462801.72     13496023.38
      2462609.59     13495760.53
#Sta/Elev= 30
  3242.7  248.68  3319.4  247.88  3432.9  246.09  3772.4  242.27  3814.1  243.53
  4070.9  242.04  4147.9  242.64  4325.7  239.75  4585.5   239.7  4621.7  238.17
    4652  239.72  4875.5  239.72    4948  237.41  4990.7  237.31  4998.3  233.04
  5003.8  233.04  5012.9  229.98  5022.8  228.56  5023.3  228.06  5033.4  228.56
    5034  231.13  5047.3  234.19  5091.1  236.22  5128.9  240.21  5152.3  240.24
    5238  240.87    5259  241.07  5614.4  243.44  5789.5  243.24    6005  245.81
#Mann= 9 ,-1 , 0
  3242.7     .05       0  3319.4     .07       0  3432.9     .12       0
  5022.8     .05       0  5033.4     .12       0  5047.3      .1       0
  5152.3     .05       0    5238      .1       0    5259     .05       0
Bank Sta=5022.8,5033.4
XS Rating Curve= 0 ,0
Exp/Cntr=0.3,0.1

Chan Stop Cuts=-1
Use User Specified Reach Order=0
Composite Channel Slope=5