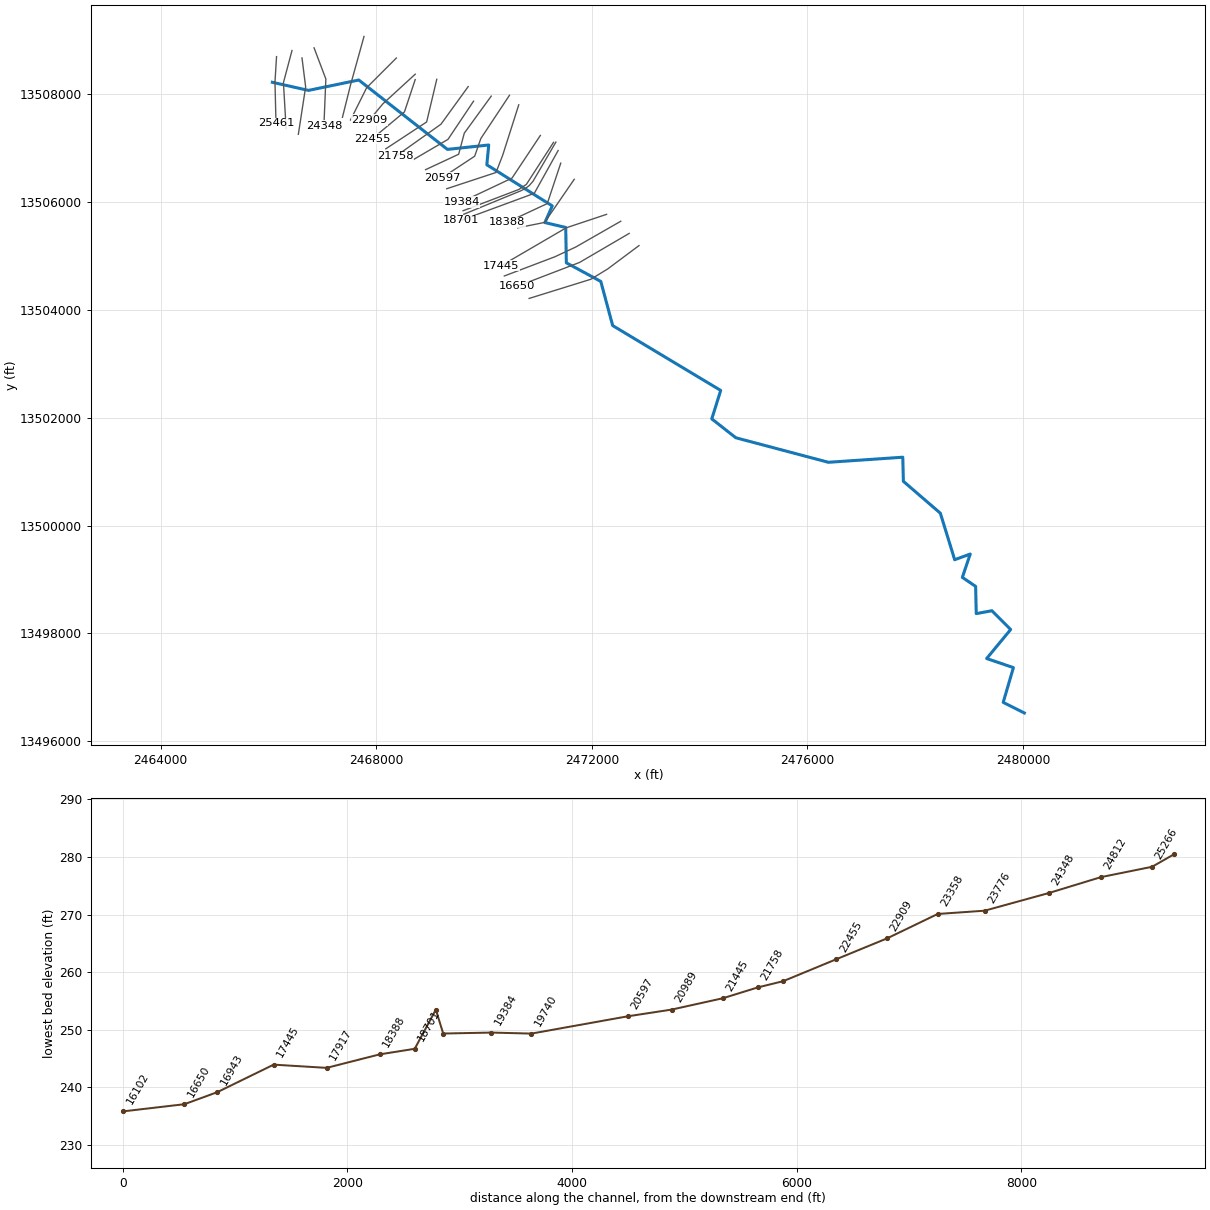
--- DRY CREEK GOLIAD.prj (project) ---

Proj Title=DRY CREEK GOLIAD Base Level Engineering
Current Plan=p01
Default Exp/Contr=0.3,0.1
English Units
Geom File=g01
Flow File=f01
Plan File=p01
Y Axis Title=Elevation
X Axis Title(PF)=Main Channel Distance
X Axis Title(XS)=Station
BEGIN DESCRIPTION:
DRY CREEK GOLIAD
END DESCRIPTION:
DSS Export Rating Curves= 0
DSS Export Rating Curve Sorted= 0
DSS Export Volume Flow Curves= 0
DXF OffsetX= 0
DXF OffsetY= 0
DXF ScaleX= 1
DXF ScaleY= 10

--- DRY CREEK GOLIAD.p01 (plan) ---

Plan Title=Multiple Run
Program Version=4.10
Short Identifier=Multiple
Geom File=g01
Flow File=f01
Subcritical Flow
K Sum by GR= 0
Std Step Tol= 0.01
Critical Tol= 0.01
Num of Std Step Trials= 20
Max Error Tol= 0.3
Flow Tol Ratio= 0.001
Split Flow NTrial= 30
Split Flow Tol= 0.02
Split Flow Ratio= 0.02
Log Output Level= 0
Friction Slope Method= 1
Unsteady Friction Slope Method= 2
Unsteady Bridges Friction Slope Method= 1
Parabolic Critical Depth
Global Vel Dist= 1 , 1 , 1
Global Log Level= 0
CheckData=True
Encroach Param=-1 ,0,0, 0
BEGIN DESCRIPTION:
Multiple Run
END DESCRIPTION:
Computation Interval=1HOUR
Output Interval=1HOUR
Run HTab= 0
Run UNet= 0
Run PostProcess= 0
Run WQNet= 0
UNET Theta= 1
UNET Theta Warmup= 1
UNET ZTol= 0.02
UNET ZSATol= 0.05
UNET MxIter= 20
UNET MaxInSteps= 0
UNET DtIC= 0
UNET DtMin= 0
UNET MaxCRTS= 20
UNET WFStab= 2
UNET SFStab= 1
UNET WFX= 1
UNET SFX= 1
UNET DSS MLevel= 4
UNET DZMax Abort= 100
UNET Convert EG Bridges= 0
UNET Use Existing IB Tables=-1
UNET Froude Reduction=False
UNET Froude Limit= 1
UNET Froude Power= 10
UNET Time Slicing=0,0, 5
UNET Junction Losses=0
Instantaneous Interval=1HOUR
Write IC File= 0
Write IC File at Sim End=0
Echo Input=False
Echo Parameters=False
Echo Output=False
Write Detailed= 0
WQ AD Non Conservative
WQ ULTIMATE=-1
WQ Max Comp Step=1HOUR
WQ Output Interval=15MIN
WQ Output Selected Increments= 0
WQ Output face flow=0
WQ Output face velocity=0
WQ Output face area=0
WQ Output face dispersion=0
WQ Output cell volume=0
WQ Output cell surface area=0
WQ Output cell continuity=0
WQ Output cumulative cell continuity=0
WQ Output face conc=0
WQ Output face dconc_dx=0
WQ Output face courant=0
WQ Output face peclet=0
WQ Output face adv mass=0
WQ Output face disp mass=0
WQ Output cell mass=0
WQ Output cell source sink temp=0
WQ Output cell source sink nsm=0
WQ Output MaxMinRange=-1
WQ Daily Max Min Mean=-1
WQ Daily Range=0
WQ Daily Time=0
WQ Create Restart=0
WQ Fixed Restart=0
WQ System Summary=0
WQ Use Fixed Temperature=0
Sorting and Armoring Iterations= 10
XS Update Threshold= 0.02
Hydraulics Update Threshold= 0.02
Energy Slope Method= 1
Volume Change Method= 0
XS Weighting Method= 0
Number of US Weighted Cross Sections= 1
Number of DS Weighted Cross Sections= 1
Upstream XS Weight=0.25
Main XS Weight=0.5
Downstream XS Weight=0.25
Number of DS XS's Weighted with US Boundary= 1
Upstream Boundary Weight= 1
Weight of XSs Associated with US Boundary= 0
Number of US XS's Weighted with DS Boundary= 1
Downstream Boundary Weight= 0.5
Weight of XSs Associated with DS Boundary= 0.5
Sediment Output Level= 4
Mass or Volume Output= 0
Output Increment Type= 1
Profile and TS Output Increment= 10
XS Output Flag= 0
XS Output Increment= 10
Disregard all LS=0
Disregard all Conn=0
Disregard all Breaches=0
Disregard all Pumps=0

--- DRY CREEK GOLIAD.f01 (steady flow) ---

Flow Title=Multiple
Number of Profiles=7
Profile Names=10-year,25-year,50-year,1pct_min,100-year,1pct_plu,500-year
River Rch & RM= DRY CREEK GOLIAD,Reach-1,25461
     487     774    1029     664    1324    2642    2165
River Rch & RM= DRY CREEK GOLIAD,Reach-1,21445
     677    1095    1473     960    1915    3820    3199
River Rch & RM= DRY CREEK GOLIAD,Reach-1,19384
     852    1395    1891    1240    2474    4936    4192
River Rch & RM= DRY CREEK GOLIAD,Reach-1,16650
    1266    2113    2902    1923    3838    7657    6650
River Rch & RM= DRY CREEK GOLIAD,Reach-1,10934
    1442    2419    3333    2216    4421    8821    7706
River Rch & RM= DRY CREEK GOLIAD,Reach-1,7871
    1477    2479    3418    2273    4535    9049    7913
River Rch & RM= DRY CREEK GOLIAD,Reach-1,6702
    1719    2891    3991    2656    5299   10572    9253
Boundary for River Rch & Prof#=DRY CREEK GOLIAD,Reach-1,1
Up Type=0
Dn Type=3
Dn Slope=0.005
Boundary for River Rch & Prof#=DRY CREEK GOLIAD,Reach-1,2
Up Type=0
Dn Type=3
Dn Slope=0.005
Boundary for River Rch & Prof#=DRY CREEK GOLIAD,Reach-1,3
Up Type=0
Dn Type=3
Dn Slope=0.005
Boundary for River Rch & Prof#=DRY CREEK GOLIAD,Reach-1,4
Up Type=0
Dn Type=3
Dn Slope=0.005
Boundary for River Rch & Prof#=DRY CREEK GOLIAD,Reach-1,5
Up Type=0
Dn Type=3
Dn Slope=0.005
Boundary for River Rch & Prof#=DRY CREEK GOLIAD,Reach-1,6
Up Type=0
Dn Type=3
Dn Slope=0.005
Boundary for River Rch & Prof#=DRY CREEK GOLIAD,Reach-1,7
Up Type=0
Dn Type=3
Dn Slope=0.005

--- DRY CREEK GOLIAD.g01 (geometry) ---

Geom Title=Existing Conditions
Program Version=4.10

River Reach=DRY CREEK GOLIAD,Reach-1
Reach XY= 30
        2466075.       13508225.      2466745.18     13508074.57
      2467678.24     13508267.16      2469322.71     13506980.07
      2470088.76     13507061.53      2470053.85      13506694.6
      2471267.66     13505931.33      2471130.39     13505622.56
       2471517.2     13505531.84      2471528.54     13504876.46
      2472167.52     13504531.06      2472388.36     13503711.66
      2474392.22     13502508.74      2474226.61     13501981.02
      2474672.45     13501630.73      2476390.21     13501175.51
      2477769.91     13501269.56      2477780.83      13500822.7
      2478466.86     13500231.06      2478732.83     13499368.14
      2479021.48     13499473.78      2478874.83     13499040.22
      2479121.47     13498873.55      2479132.68     13498368.47
      2479423.27     13498421.69      2479771.39      13498073.5
      2479325.96     13497535.27      2479821.94     13497366.72
      2479632.76     13496721.58        2480025.       13496525.

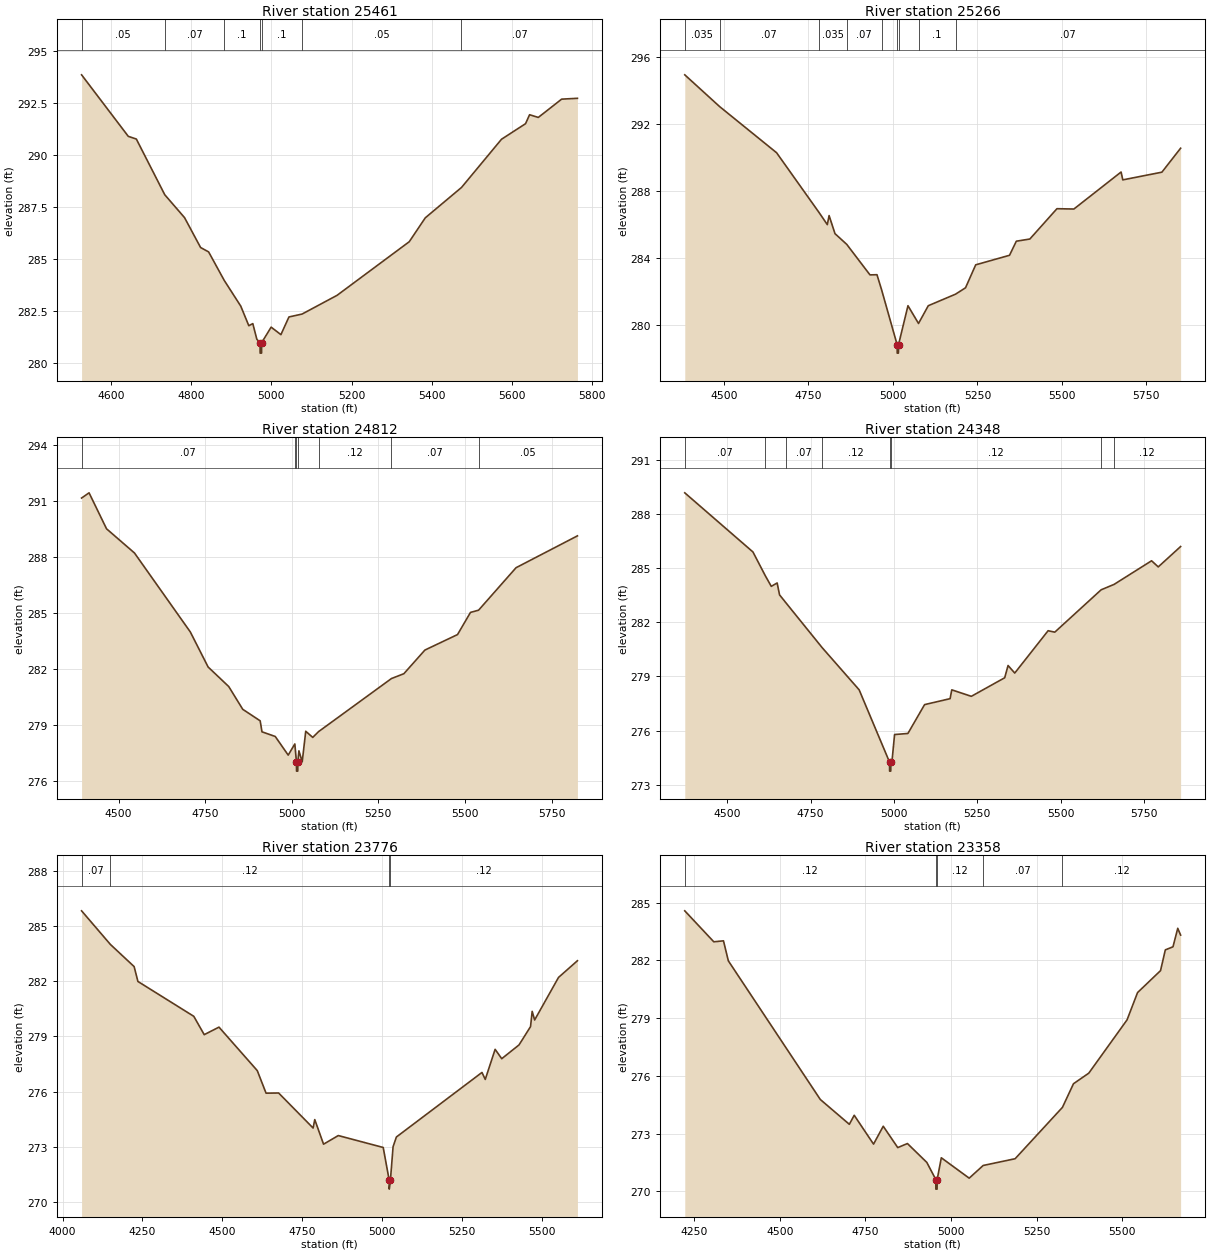
Type RM Length L Ch R = 1 ,25461   ,195,195,195
BEGIN DESCRIPTION:
DRY CREEK (GOLIAD) 53.0
END DESCRIPTION:
XS GIS Cut Line= 3
      2466152.49     13508701.31      2466123.51     13508228.69
      2466142.51     13507465.63
#Sta/Elev= 30
  4526.5  293.85    4643  290.89  4663.1  290.76    4734  288.08  4783.3  286.98
  4823.4  285.54  4843.4  285.33  4882.3  283.96  4923.6  282.72  4943.6  281.78
  4953.6  281.88  4963.6  281.13  4971.6  280.96  4971.9  280.46  4975.4  280.46
  4975.6  280.96  4999.3  281.71  5023.7  281.35  5043.7   282.2  5076.5  282.34
  5163.7  283.24  5343.8  285.82  5383.8  286.97  5474.1  288.43  5573.9  290.75
  5633.9   291.5  5643.9  291.93  5665.7   291.8  5723.9  292.68  5763.3  292.72
#Mann= 7 ,-1 , 0
  4526.5     .05       0    4734     .07       0  4882.3      .1       0
  4971.6     .05       0  4975.6      .1       0  5076.5     .05       0
  5474.1     .07       0
Bank Sta=4971.6,4975.6
XS Rating Curve= 0 ,0
Exp/Cntr=0.3,0.1

Type RM Length L Ch R = 1 ,25266   ,454,454,454
BEGIN DESCRIPTION:
Mapping XS 5ffceca3
END DESCRIPTION:
XS GIS Cut Line= 3
      2466439.37     13508814.57      2466280.53     13508218.24
      2466329.98      13507369.7
#Sta/Elev= 30
  4384.1  294.91  4487.5  293.01  4655.8  290.26  4780.8  286.71  4805.9  285.97
  4811.1  286.51  4828.6  285.43  4863.4  284.79  4932.1  282.97  4952.8  282.98
  4966.2   282.1  5012.5   278.8  5012.7   278.3  5016.2   278.3  5016.5   278.8
  5044.5  281.13  5075.7  280.07  5104.6  281.13  5185.4  281.82  5214.8   282.2
  5244.9  283.57    5345  284.14  5365.1  284.98  5405.1  285.11  5485.3  286.92
  5535.4   286.9  5675.1  289.11  5680.1  288.64  5795.8   289.1  5851.2  290.53
#Mann= 9 ,-1 , 0
  4384.1    .035       0  4487.5     .07       0  4780.8    .035       0
  4863.4     .07       0  4966.2     .12       0  5012.5     .05       0
  5016.5     .12       0  5075.7      .1       0  5185.4     .07       0
Bank Sta=5012.5,5016.5
XS Rating Curve= 0 ,0
Exp/Cntr=0.3,0.1

Type RM Length L Ch R = 1 ,24812   ,464,464,464
BEGIN DESCRIPTION:
Mapping XS 4632a7c0
END DESCRIPTION:
XS GIS Cut Line= 3
      2466624.79     13508676.46      2466692.49     13508140.04
      2466557.08     13507259.87
#Sta/Elev= 30
  4393.4  291.17    4415  291.45  4465.4  289.52  4546.1  288.22  4707.3  283.98
  4758.6   282.1  4818.2  281.05  4858.5  279.83  4908.9  279.21  4914.1  278.62
  4952.4  278.37  4989.8  277.37  5008.9  277.97  5013.6  277.01  5013.9  276.51
  5017.4  276.51  5017.6  277.01  5020.7   277.6  5030.2  277.01  5040.4  278.65
  5060.6  278.32  5077.4  278.63  5287.8  281.48  5323.6  281.74  5384.4  283.01
  5478.5  283.84  5515.9  285.03  5539.3  285.15  5647.4  287.43  5824.6  289.14
#Mann= 7 ,-1 , 0
  4393.4     .07       0  5008.9      .1       0  5013.6     .05       0
  5017.6      .1       0  5077.4     .12       0  5287.8     .07       0
  5539.3     .05       0
Bank Sta=5013.6,5017.6
XS Rating Curve= 0 ,0
Exp/Cntr=0.3,0.1

Type RM Length L Ch R = 1 ,24348   ,572,572,572
BEGIN DESCRIPTION:
Mapping XS c48ec0b2
END DESCRIPTION:
XS GIS Cut Line= 3
      2466848.73     13508864.04      2467067.49     13508285.87
      2467031.11     13507418.01
#Sta/Elev= 30
  4372.9  289.19  4577.3  285.91  4614.1   284.6  4632.3     284  4649.9  284.19
  4657.1  283.53  4676.6  283.08  4784.9   280.6  4895.8  278.26  4986.9  274.25
  4987.1  273.75  4990.6  273.75  4990.9  274.25    4994  274.25    5002  275.78
    5042  275.84    5092  277.44  5168.5  277.77  5173.5  278.26  5232.2   277.9
  5332.2  278.93  5342.3  279.61  5362.3  279.19  5462.4  281.54  5482.4  281.46
  5621.4  283.81  5660.2  284.11  5772.6  285.42  5792.6  285.08  5859.7  286.21
#Mann= 8 ,-1 , 0
  4372.9     .07       0  4614.1     .12       0  4676.6     .07       0
  4784.9     .12       0  4986.9     .05       0  4990.9     .12       0
  5621.4     .07       0  5660.2     .12       0
Bank Sta=4986.9,4990.9
XS Rating Curve= 0 ,0
Exp/Cntr=0.3,0.1

Type RM Length L Ch R = 1 ,23776   ,418,418,418
BEGIN DESCRIPTION:
DRY CREEK (GOLIAD) 50.0
END DESCRIPTION:
XS GIS Cut Line= 3
        2467775.       13509075.        2467525.       13508175.
      2467375.01     13507575.04
#Sta/Elev= 30
  4059.7  285.85  4149.8  284.02  4224.2  282.81  4236.1     282    4411   280.1
  4443.7   279.1  4489.9  279.51  4609.8  277.14  4637.3  275.91  4676.7  275.92
  4784.6  274.01  4789.8  274.47  4817.3  273.13  4863.5   273.6  5004.1  272.95
  5022.7  271.18    5023  270.68  5026.7  271.18    5035  272.99  5045.3  273.52
  5313.3  277.04  5323.6  276.66  5354.5   278.3  5375.2  277.79  5429.3  278.54
  5465.4  279.54  5470.5  280.37  5478.2   279.9    5553  282.22  5612.2  283.13
#Mann= 4 ,-1 , 0
  4059.7     .07       0  4149.8     .12       0  5022.7     .05       0
  5026.7     .12       0
Bank Sta=5022.7,5026.7
XS Rating Curve= 0 ,0
Exp/Cntr=0.3,0.1

Type RM Length L Ch R = 1 ,23358   ,449,449,449
BEGIN DESCRIPTION:
DRY CREEK (GOLIAD) 49.0
END DESCRIPTION:
XS GIS Cut Line= 3
      2468374.98     13508674.98        2467825.       13508125.
      2467525.01     13507525.01
#Sta/Elev= 30
  4222.2  284.58    4307  282.97  4335.3  283.02  4349.5  281.98  4618.2  274.77
    4703  273.48  4717.2  273.95  4773.7  272.45    4802  273.38  4844.4  272.27
  4872.7  272.48  4929.3   271.5  4955.6  270.61  4955.8  270.11  4959.3  270.11
  4959.6  270.61  4971.7  271.74  5053.1  270.68    5094  271.34  5187.3  271.69
  5325.5  274.36  5357.8  275.59  5402.5  276.14  5514.3  278.91    5545  280.33
  5612.1  281.47  5626.1  282.55  5648.5  282.71  5662.4  283.67  5670.8  283.32
#Mann= 5 ,-1 , 0
  4222.2     .12       0  4955.6     .05       0  4959.6     .12       0
    5094     .07       0  5325.5     .12       0
Bank Sta=4955.6,4959.6
XS Rating Curve= 0 ,0
Exp/Cntr=0.3,0.1

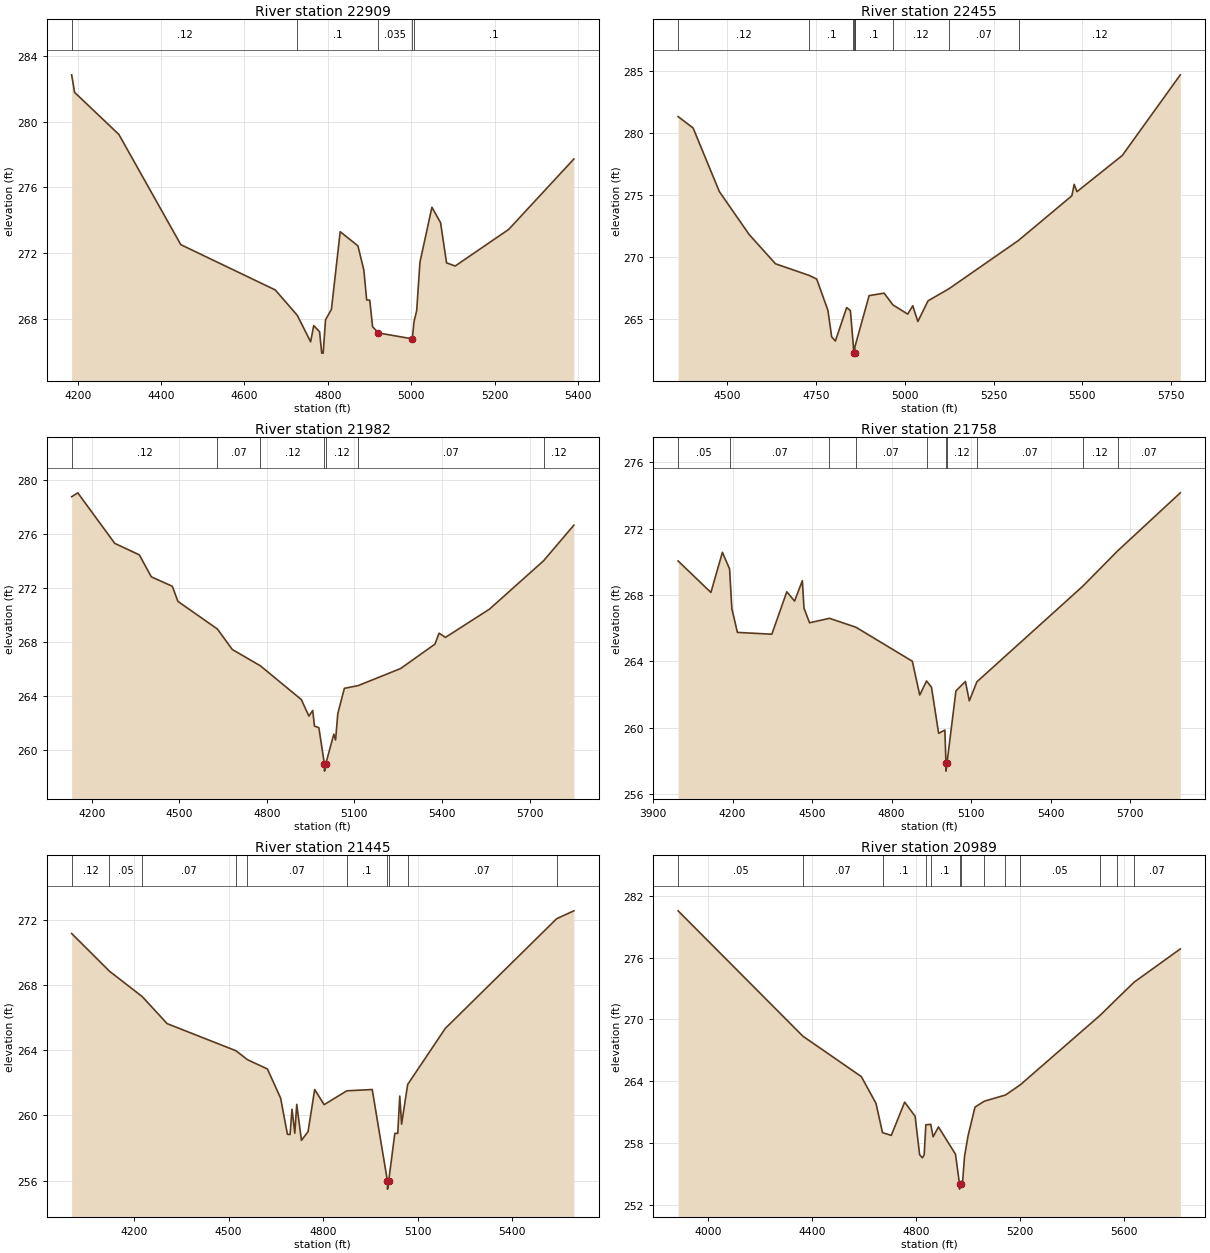
Type RM Length L Ch R = 1 ,22909   ,454,454,454
BEGIN DESCRIPTION:
DRY CREEK (GOLIAD) 48.0
END DESCRIPTION:
XS GIS Cut Line= 3
      2468725.01       13508375.        2468125.       13507825.
      2467874.97     13507524.97
#Sta/Elev= 30
  4185.5  282.85  4192.6  281.78  4298.7  279.22  4447.3   272.5  4673.9  269.74
  4726.8  268.19  4758.7  266.58  4766.1  267.57  4780.2  267.19  4785.3  265.89
  4788.8  265.89  4794.4  267.92  4808.6  268.56  4829.6  273.29  4872.1  272.43
  4886.3  270.96  4893.1  269.13  4900.5  269.12  4907.3   267.5  4921.4  267.12
  5002.7  266.76  5006.6   267.8  5013.1  268.48  5020.9  271.43  5049.6  274.78
  5070.4  273.84  5084.7  271.39  5105.5   271.2  5233.8  273.43    5390  277.72
#Mann= 5 ,-1 , 0
  4185.5     .12       0  4726.8      .1       0  4921.4    .035       0
  5002.7    .035       0  5006.6      .1       0
Bank Sta=4921.4,5002.7
XS Rating Curve= 0 ,0
Exp/Cntr=0.3,0.1

Type RM Length L Ch R = 1 ,22455   ,473,473,473
BEGIN DESCRIPTION:
DRY CREEK (GOLIAD) 47.0
END DESCRIPTION:
XS GIS Cut Line= 3
      2468725.01     13508275.03        2468525.       13507675.
      2467925.01     13507175.01
#Sta/Elev= 30
  4362.2  281.34  4404.4  280.42  4478.2  275.29  4562.5  271.81  4636.3  269.46
  4731.3  268.52  4752.2  268.23  4783.9   265.7  4794.4  263.56  4804.9  263.23
  4836.6  265.93  4847.1  265.68  4855.7  262.75  4855.9  262.25  4859.4  262.25
  4859.7  262.75  4899.8  266.89    4942  267.09    4967  266.14  5008.4   265.4
  5022.7  266.07    5037   264.8  5065.6  266.47  5124.8  267.45  5320.5  271.35
  5470.5  274.95    5477  275.87  5484.8  275.28  5612.3   278.2  5775.7  284.71
#Mann= 9 ,-1 , 0
  4362.2     .12       0  4731.3      .1       0  4855.7     .07       0
  4855.9     .05       0  4859.4     .07       0  4859.7      .1       0
    4967     .12       0  5124.8     .07       0  5320.5     .12       0
Bank Sta=4855.9,4859.4
XS Rating Curve= 0 ,0
Exp/Cntr=0.3,0.1

Type RM Length L Ch R = 1 ,21982   ,224,224,224
BEGIN DESCRIPTION:
Mapping XS a0e8301c
END DESCRIPTION:
XS GIS Cut Line= 3
      2469124.79     13508280.69      2468937.28       13507489.
      2468179.18     13506990.52
#Sta/Elev= 30
    4131  278.79    4152  279.08  4278.8  275.33  4362.9  274.48    4404  272.85
    4476  272.15  4495.1  271.03  4630.5  268.98  4681.5  267.46  4777.8  266.25
  4917.9  263.75  4944.1  262.52  4957.1  262.94  4963.1  261.78  4978.2  261.66
  4997.3  258.94  4997.5  258.44  5001.3  258.94  5029.4  261.18  5035.4  260.75
  5043.1  262.71  5065.6  264.58  5112.6  264.78  5258.5  266.05  5375.9  267.86
  5390.1  268.67    5412  268.36  5562.6  270.45  5748.2  274.04  5851.9  276.68
#Mann= 7 ,-1 , 0
    4131     .12       0  4630.5     .07       0  4777.8     .12       0
  4997.3     .05       0  5001.3     .12       0  5112.6     .07       0
  5748.2     .12       0
Bank Sta=4997.3,5001.3
XS Rating Curve= 0 ,0
Exp/Cntr=0.3,0.1

Type RM Length L Ch R = 1 ,21758   ,313,313,313
BEGIN DESCRIPTION:
Mapping XS 6a158f10
END DESCRIPTION:
XS GIS Cut Line= 3
       2469708.1     13508145.23      2469202.91     13507447.33
       2468360.7     13506849.47
#Sta/Elev= 30
  3994.5  270.05  4118.2  268.15  4161.6  270.57  4188.6  269.57  4197.2  267.18
  4218.1  265.74    4348  265.63  4404.5  268.19  4433.8  267.63  4463.2  268.86
  4469.4   267.2  4490.3  266.32  4565.5  266.59  4665.4  266.05    4878     264
    4906  261.96  4931.7  262.81  4950.3  262.43  4977.3  259.65  5000.7  259.85
  5004.9  257.87  5005.1  257.37  5008.9  257.87  5042.5  262.21  5078.2  262.78
    5093  261.61  5121.6  262.76  5520.6  268.52  5652.1  270.65  5888.9  274.16
#Mann= 10 ,-1 , 0
  3994.5     .05       0  4188.6     .07       0  4565.5     .12       0
  4665.4     .07       0  4931.7     .12       0  5004.9     .05       0
  5008.9     .12       0  5121.6     .07       0  5520.6     .12       0
  5652.1     .07       0
Bank Sta=5004.9,5008.9
XS Rating Curve= 0 ,0
Exp/Cntr=0.3,0.1

Type RM Length L Ch R = 1 ,21445   ,456,456,456
BEGIN DESCRIPTION:
Mapping XS c42bc60a
END DESCRIPTION:
XS GIS Cut Line= 3
       2469807.1     13507874.45      2469333.12     13507166.08
      2468692.52      13506791.1
#Sta/Elev= 30
  4001.7  271.16  4121.6  268.85  4225.8  267.29    4305  265.63  4523.2  263.97
  4559.9  263.42  4623.3  262.85  4665.3  261.06  4686.9  258.84  4695.3  258.83
  4701.4  260.38  4710.3  258.91  4716.4  260.68  4731.4  258.47  4752.4  259.01
  4773.4  261.59  4803.4  260.66  4875.4  261.51  4956.1  261.59  5004.4  255.98
  5004.7  255.48  5008.4  255.98  5027.9   258.9  5037.2   258.9  5043.6  261.19
  5049.4  259.47  5068.7   261.9  5188.2  265.34  5541.9  272.07  5596.3  272.55
#Mann= 10 ,-1 , 0
  4001.7     .12       0  4121.6     .05       0  4225.8     .07       0
  4523.2      .1       0  4559.9     .07       0  4875.4      .1       0
  5004.4     .05       0  5008.4      .1       0  5068.7     .07       0
  5541.9     .12       0
Bank Sta=5004.4,5008.4
XS Rating Curve= 0 ,0
Exp/Cntr=0.3,0.1

Type RM Length L Ch R = 1 ,20989   ,392,392,392
BEGIN DESCRIPTION:
Mapping XS 365cab45
END DESCRIPTION:
XS GIS Cut Line= 4
      2470135.22     13507968.19       2469635.2     13507280.67
      2469531.03     13506890.04      2468918.23     13506604.41
#Sta/Elev= 30
  3884.5  280.54  4363.9  268.37  4588.8  264.44  4645.2  261.84  4670.2     259
  4703.9  258.73  4755.4  261.96  4795.5  260.59  4812.9  256.86  4823.3  256.55
  4830.4  256.83  4836.8  259.76  4855.8   259.8  4864.7  258.59  4885.4  259.55
  4950.8   256.9  4966.2  254.01  4966.4  253.51  4970.2  254.01  4978.5  254.36
  4985.7  256.73  4999.2   258.7  5025.8  261.48  5061.5  262.05    5143  262.65
  5200.3  263.65  5507.1   270.4  5571.3  271.99  5637.5  273.61    5815  276.84
#Mann= 13 ,-1 , 0
  3884.5     .05       0  4363.9     .07       0  4670.2      .1       0
  4836.8     .07       0  4855.8      .1       0  4966.2     .05       0
  4970.2      .1       0  5061.5     .12       0    5143      .1       0
  5200.3     .05       0  5507.1     .07       0  5571.3     .05       0
  5637.5     .07       0
Bank Sta=4966.2,4970.2
XS Rating Curve= 0 ,0
Exp/Cntr=0.3,0.1

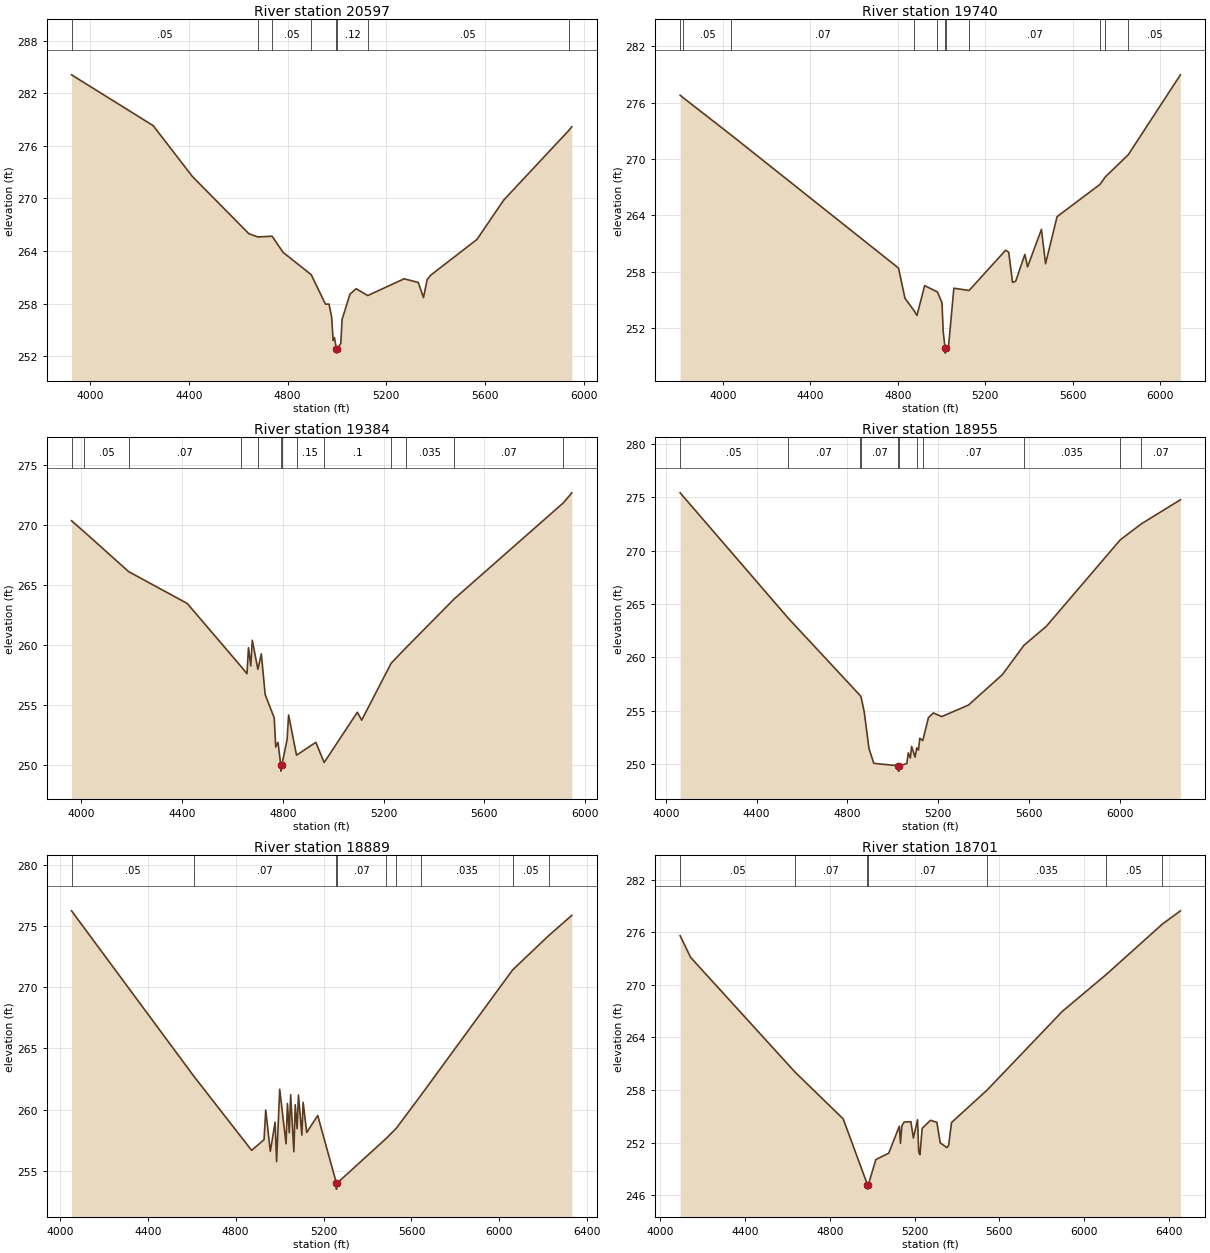
Type RM Length L Ch R = 1 ,20597   ,857,857,857
BEGIN DESCRIPTION:
Mapping XS 491c633b
END DESCRIPTION:
XS GIS Cut Line= 4
      2470473.71     13507983.75      2469942.49     13507181.71
      2469827.91     13506853.58      2469229.46     13506458.08
#Sta/Elev= 30
    3925  284.09  4255.5   278.3    4415  272.48  4643.6  265.96  4680.5  265.59
  4737.5  265.68    4782  263.84  4896.1  261.29  4953.8  257.93  4968.3  257.93
  4978.9  256.46  4984.9  253.79  4990.2  254.11    4998  252.84  4998.3  252.34
    5002  252.84  5015.9  253.45  5021.2  256.19    5053  259.06    5078  259.69
  5125.1  258.91  5272.7  260.82  5329.9   260.4  5350.9  258.68    5366  260.74
    5381  261.25  5567.6  265.31    5676   269.8  5938.6  277.71  5951.9  278.16
#Mann= 8 ,-1 , 0
    3925     .05       0  4680.5     .07       0  4737.5     .05       0
  4896.1     .12       0    4998     .05       0    5002     .12       0
  5125.1     .05       0  5938.6     .07       0
Bank Sta=4998,5002
XS Rating Curve= 0 ,0
Exp/Cntr=0.3,0.1

Type RM Length L Ch R = 1 ,19740   ,356,356,356
BEGIN DESCRIPTION:
Mapping XS 3efc5553
END DESCRIPTION:
XS GIS Cut Line= 4
      2470645.62     13507806.73      2470348.74     13506874.42
      2470223.74      13506551.5      2469309.42     13506250.19
#Sta/Elev= 30
  3804.8   276.8  3819.4  276.52  4039.1  272.54  4803.1   258.4    4833  255.17
  4874.3  253.86  4887.5  253.35  4922.8  256.53  4981.2  255.85  5001.9  254.71
  5007.8  251.58  5016.5  249.84  5016.8  249.34  5020.5  249.84  5031.8  250.02
  5056.4  256.25  5126.1  256.01  5292.7  260.29  5307.2  260.08  5324.5  256.89
  5338.8  256.98  5380.9  259.85  5393.3  258.53  5456.8  262.51  5475.6  258.86
  5528.3  263.87  5724.7  267.31  5748.7   268.1  5853.7  270.46  6092.2  278.97
#Mann= 11 ,-1 , 0
  3804.8     .07       0  3819.4     .05       0  4039.1     .07       0
  4874.3     .12       0  4981.2      .1       0  5016.5     .05       0
  5020.5      .1       0  5126.1     .07       0  5724.7     .05       0
  5748.7     .07       0  5853.7     .05       0
Bank Sta=5016.5,5020.5
XS Rating Curve= 0 ,0
Exp/Cntr=0.3,0.1

Type RM Length L Ch R = 1 ,19384   ,429,429,429
BEGIN DESCRIPTION:
Mapping XS bd02bbae
END DESCRIPTION:
XS GIS Cut Line= 3
      2471046.66       13507239.      2470520.62     13506447.33
       2469583.1     13506004.62
#Sta/Elev= 30
  3960.7  270.39  4012.1  269.45  4187.6  266.15  4420.1   263.5  4635.5  258.21
  4657.6  257.64  4663.6  259.81  4672.7  258.29  4678.7  260.43  4700.9  258.01
  4714.7  259.29  4729.8  255.91  4765.8  253.96  4771.9  251.53  4780.9  251.92
  4791.9  250.02  4792.2  249.52  4795.9  250.02    4817  252.15    4823   254.2
  4854.4  250.85  4931.2  251.92  4964.3  250.24  5096.1  254.43  5113.3  253.77
  5230.5  258.52  5288.2  259.78  5480.5  263.87  5914.7  271.89    5948  272.72
#Mann= 13 ,-1 , 0
  3960.7     .07       0  4012.1     .05       0  4187.6     .07       0
  4635.5      .1       0  4700.9     .07       0  4791.9     .05       0
  4795.9     .07       0  4854.4     .15       0  4964.3      .1       0
  5230.5     .07       0  5288.2    .035       0  5480.5     .07       0
  5914.7     .05       0
Bank Sta=4791.9,4795.9
XS Rating Curve= 0 ,0
Exp/Cntr=0.3,0.1

Type RM Length L Ch R = 1 ,18955   ,66,66,66
BEGIN DESCRIPTION:
Mapping XS cb0f9982
END DESCRIPTION:
XS GIS Cut Line= 4
      2471290.32     13507110.09      2470787.73     13506331.47
      2470649.71     13506237.72      2469613.22     13505841.87
#Sta/Elev= 30
  4063.2  275.42  4538.7  263.69  4855.3  256.45  4860.1  256.29  4873.9  254.89
    4895  251.45  4916.1  250.08  5023.8  249.85    5024  249.35  5027.6  249.35
  5027.9  249.85  5061.7  250.06  5067.8  251.06  5076.7  250.58  5082.7  251.66
  5097.7  250.66  5105.3  251.53  5112.6  251.32  5118.7  252.43  5131.6  252.21
  5156.6  254.36  5178.2   254.8  5215.4  254.46  5333.1  255.54  5482.2  258.39
  5577.5  261.14  5675.6  262.91  6001.1  271.01  6094.7  272.52  6266.3  274.77
#Mann= 11 ,-1 , 0
  4063.2     .05       0  4538.7     .07       0  4855.3     .15       0
  4860.1     .07       0  5023.8     .05       0  5027.9     .07       0
  5105.3      .1       0  5131.6     .07       0  5577.5    .035       0
  6001.1     .05       0  6094.7     .07       0
Bank Sta=5023.8,5027.9
XS Rating Curve= 0 ,0
Exp/Cntr=0.3,0.1

Type RM Length L Ch R = 1 ,18889   ,188,188,188
BEGIN DESCRIPTION:
Mapping XS b93f45ce
END DESCRIPTION:
XS GIS Cut Line= 6
       2471334.6      13507115.3      2470910.13     13506388.76
      2470837.21     13506305.42       2470769.5     13506255.94
      2470683.57     13506211.67      2469626.32      13505776.8
#Sta/Elev= 30
  4053.5  276.25  4609.6  262.73  4872.9  256.66  4929.3  257.54  4936.9  259.96
  4957.8  256.58  4979.6  258.96  4986.3  255.74  5000.5  261.66  5029.4   257.2
  5035.6  260.49  5044.1   258.1  5050.3  261.21  5064.9  256.55  5071.1  260.39
  5079.6  258.43  5085.8  261.19  5101.4  257.91    5107  260.59  5123.5  258.13
  5173.5  259.51  5258.3  253.99  5258.5  253.49  5262.4  253.99  5484.6  257.63
    5531  258.47  5641.6  261.13  6059.7  271.41    6224  274.22  6329.4  275.88
#Mann= 9 ,-1 , 0
  4053.5     .05       0  4609.6     .07       0  5258.3     .05       0
  5262.4     .07       0  5484.6    .035       0    5531     .07       0
  5641.6    .035       0  6059.7     .05       0    6224     .07       0
Bank Sta=5258.3,5262.4
XS Rating Curve= 0 ,0
Exp/Cntr=0.3,0.1

Type RM Length L Ch R = 1 ,18701   ,313,313,313
BEGIN DESCRIPTION:
DRY CREEK (GOLIAD) 39.0
END DESCRIPTION:
XS GIS Cut Line= 3
      2471376.29      13506959.1      2470933.57      13506164.8
      2469571.59      13505662.2
#Sta/Elev= 30
  4093.2   275.6  4142.6  273.13  4635.4  260.05  4862.7  254.71  4977.4   247.2
  4977.6   246.7  4981.5   247.2  5016.7  250.07  5077.6   250.8  5127.8  253.88
  5133.1  251.92  5139.6  253.92  5150.3  254.35  5182.2  254.39    5194  252.53
  5213.7  254.61  5219.1  250.95  5224.9  250.63  5235.5  253.63  5274.6  254.55
    5305  254.32  5320.8  251.97  5352.8  251.43  5360.6  251.73  5374.1   254.3
  5541.6  257.99  5896.4  266.96  6103.8  271.17  6368.9  276.92  6454.3  278.44
#Mann= 7 ,-1 , 0
  4093.2     .05       0  4635.4     .07       0  4977.4     .05       0
  4981.5     .07       0  5541.6    .035       0  6103.8     .05       0
  6368.9     .07       0
Bank Sta=4977.4,4981.5
XS Rating Curve= 0 ,0
Exp/Cntr=0.3,0.1

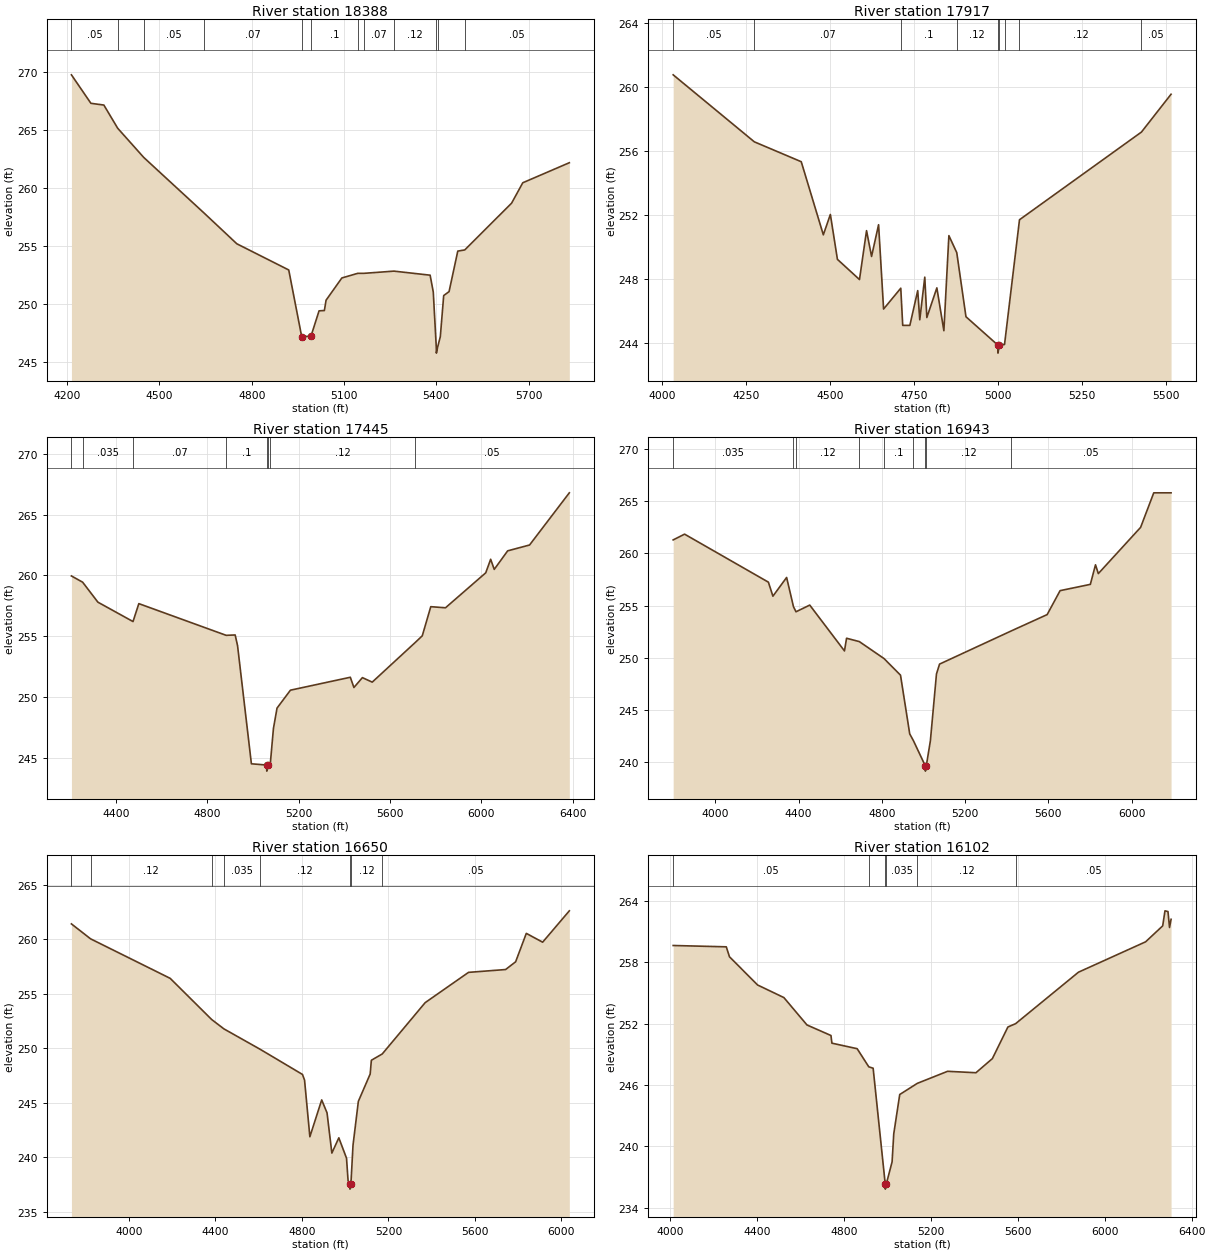
Type RM Length L Ch R = 1 ,18388   ,471,471,471
BEGIN DESCRIPTION:
DRY CREEK (GOLIAD) 38.0
END DESCRIPTION:
XS GIS Cut Line= 3
      2471425.01     13506725.02        2471175.       13505975.
      2470425.04     13505625.02
#Sta/Elev= 30
    4214  269.76  4277.3   267.3  4319.4  267.15  4364.3  265.15  4448.9  262.63
  4645.3  257.82  4751.6  255.17  4920.3  252.91  4962.4  247.15  4992.5  247.19
  5018.8  249.38  5036.1  249.41  5041.6   250.3  5092.9  252.22  5144.6  252.62
  5164.7  252.62  5262.3  252.81  5379.8  252.46    5390  251.01  5399.8  246.23
  5400.1  245.73    5404  246.23  5412.9  247.15  5423.9   250.7  5441.3  251.04
  5469.7  254.54  5492.3  254.64  5644.6  258.68  5680.9  260.44  5832.2  262.17
#Mann= 12 ,-1 , 0
    4214     .05       0  4364.3     .07       0  4448.9     .05       0
  4645.3     .07       0  4962.4     .05       0  4992.5      .1       0
  5144.6     .12       0  5164.7     .07       0  5262.3     .12       0
  5399.8     .07       0    5404     .12       0  5492.3     .05       0
Bank Sta=4962.4,4992.5
XS Rating Curve= 0 ,0
Exp/Cntr=0.3,0.1

Type RM Length L Ch R = 1 ,17917   ,472,472,472
BEGIN DESCRIPTION:
DRY CREEK (GOLIAD) 37.0
END DESCRIPTION:
XS GIS Cut Line= 3
      2471675.03     13506425.04        2471125.       13505625.
      2470624.97     13505524.99
#Sta/Elev= 30
  4033.8  260.75  4275.2  256.57  4414.7  255.33  4480.4  250.77  4501.3  252.04
  4522.3  249.24  4587.9  247.98  4608.9  251.03  4623.8  249.42  4644.7   251.4
  4659.6  246.14  4710.7  247.44  4716.5  245.12  4737.7  245.12  4761.1  247.29
  4767.2  245.47  4782.1  248.13  4788.2  245.61    4818  247.46  4838.9  244.79
  4853.8  250.72  4877.2  249.66  4904.6  245.66  4999.4  243.89  4999.7  243.39
  5003.9  243.89  5019.3  243.93  5063.8  251.71  5426.5  257.18  5514.6  259.54
#Mann= 9 ,-1 , 0
  4033.8     .05       0  4275.2     .07       0  4710.7      .1       0
  4877.2     .12       0  4999.4     .05       0  5003.9     .12       0
  5019.3      .1       0  5063.8     .12       0  5426.5     .05       0
Bank Sta=4999.4,5003.9
XS Rating Curve= 0 ,0
Exp/Cntr=0.3,0.1

Type RM Length L Ch R = 1 ,17445   ,502,502,502
BEGIN DESCRIPTION:
DRY CREEK (GOLIAD) 36.0
END DESCRIPTION:
XS GIS Cut Line= 3
      2472274.99       13505775.        2471525.       13505525.
        2470325.       13504825.
#Sta/Elev= 30
  4205.7  259.96  4254.7  259.45  4321.6  257.81  4475.3  256.22  4500.8  257.69
  4883.1  255.09  4922.5  255.12    4933  254.24  4993.6  244.55  5060.5  244.45
  5060.9  243.95  5065.1  244.45  5076.8  244.65  5090.1  247.45  5105.8  249.12
  5164.5  250.59  5426.7  251.65  5442.4  250.81  5479.6  251.62  5522.6  251.25
  5710.7   254.5  5741.7  255.05  5778.9  257.44  5843.4  257.35  6019.6  260.22
  6041.1  261.33  6056.8   260.5  6115.5  262.02  6211.4   262.5  6385.5  266.78
#Mann= 8 ,-1 , 0
  4205.7     .05       0  4254.7    .035       0  4475.3     .07       0
  4883.1      .1       0  5060.5     .05       0  5065.1      .1       0
  5076.8     .12       0  5710.7     .05       0
Bank Sta=5060.5,5065.1
XS Rating Curve= 0 ,0
Exp/Cntr=0.3,0.1

Type RM Length L Ch R = 1 ,16943   ,293,293,293
BEGIN DESCRIPTION:
Mapping XS c4966f02
END DESCRIPTION:
XS GIS Cut Line= 4
      2472537.95     13505646.97      2471704.64     13505169.55
      2471314.02     13504987.26      2470378.23     13504632.01
#Sta/Elev= 30
  3797.2  261.27    3852  261.82  4254.8  257.23  4276.4  255.89  4342.3  257.68
  4375.2  254.89  4387.3   254.4  4453.4  255.04  4620.3  250.66  4630.3  251.87
  4691.7  251.55  4810.3  249.93  4889.6  248.34  4933.8  242.73  4951.6  242.08
  5008.7  239.67    5009  239.17  5013.4  239.67  5033.1  242.07  5062.3  248.45
  5077.2   249.4  5418.4  252.54  5594.1  254.13  5656.4  256.42  5801.7  257.02
  5826.5  258.89  5840.1  258.05  6043.3  262.47  6106.4  265.77  6189.6  265.77
#Mann= 9 ,-1 , 0
  3797.2    .035       0  4375.2    .063       0  4387.3     .12       0
  4691.7     .07       0  4810.3      .1       0  4951.6     .12       0
  5008.7     .05       0  5013.4     .12       0  5418.4     .05       0
Bank Sta=5008.7,5013.4
XS Rating Curve= 0 ,0
Exp/Cntr=0.3,0.1

Type RM Length L Ch R = 1 ,16650   ,548,548,548
BEGIN DESCRIPTION:
Mapping XS 898dcf35
END DESCRIPTION:
XS GIS Cut Line= 3
      2472694.23     13505421.29      2471774.09      13504883.1
      2470619.83     13504440.48
#Sta/Elev= 30
  3734.4  261.43  3822.8  260.06  4191.1  256.43  4382.9  252.65  4439.6  251.79
  4606.9  249.92  4802.6  247.61  4812.3  247.09  4836.9  241.89  4891.6  245.27
  4916.3  244.08  4938.6  240.39  4970.8  241.79  5006.4  239.92  5013.6  237.84
    5022  237.58  5022.3  237.08  5026.7  237.58  5036.4  241.11  5061.1  245.14
  5115.8  247.65  5121.2  248.91  5171.6  249.49    5370   254.2  5570.5  256.98
  5741.9  257.24  5788.3  257.95  5837.7  260.56  5913.2  259.75  6036.6  262.63
#Mann= 8 ,-1 , 0
  3734.4     .05       0  3822.8     .12       0  4382.9    .063       0
  4439.6    .035       0  4606.9     .12       0    5022     .05       0
  5026.7     .12       0  5171.6     .05       0
Bank Sta=5022,5026.7
XS Rating Curve= 0 ,0
Exp/Cntr=0.3,0.1

Type RM Length L Ch R = 1 ,16102   ,519,519,519
BEGIN DESCRIPTION:
Mapping XS 22023db7
END DESCRIPTION:
XS GIS Cut Line= 4
      2472876.51     13505195.59      2472294.92     13504761.57
      2471982.42      13504570.6      2470838.26     13504215.21
#Sta/Elev= 30
  4015.3  259.65  4259.6  259.52  4274.2  258.55  4403.5  255.79  4524.4  254.56
  4630.7  251.88    4741  250.85  4745.4   250.1  4861.5  249.56  4914.9  247.79
    4935  247.65  4990.6  236.33    4991  235.83  4995.5  236.33  5022.2   238.5
  5029.8  241.23  5057.3  245.08    5138  246.17  5277.5  247.35  5407.8  247.21
  5483.4  248.59  5554.8  251.68  5590.5  252.01  5879.4  257.04  6188.2  260.01
  6266.8  261.57  6277.3  263.04  6291.1  262.97  6298.2  261.41  6305.3  262.21
#Mann= 6 ,-1 , 0
  4015.3     .05       0  4914.9    .035       0  4990.6    .035       0
  4995.5    .035       0    5138     .12       0  5590.5     .05       0
Bank Sta=4990.6,4995.5
XS Rating Curve= 0 ,0
Exp/Cntr=0.3,0.1