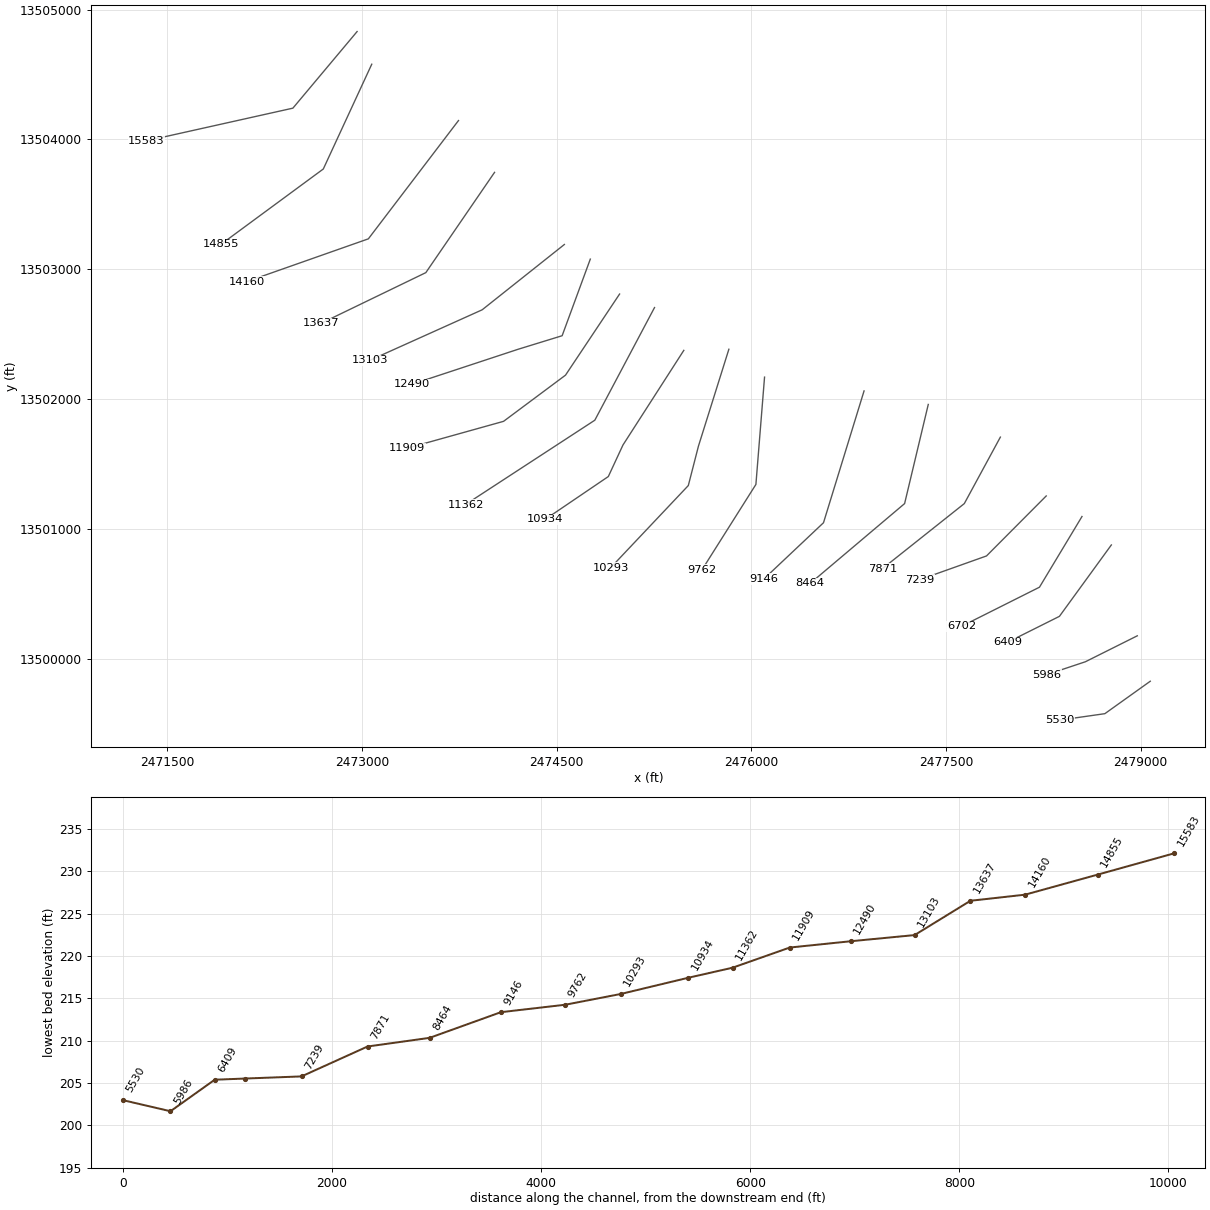
HEC-RAS study DRY CREEK GOLIAD.prj: DRY CREEK GOLIAD Base Level Engineering

--- DRY CREEK GOLIAD.g01 (geometry) --- (continued)

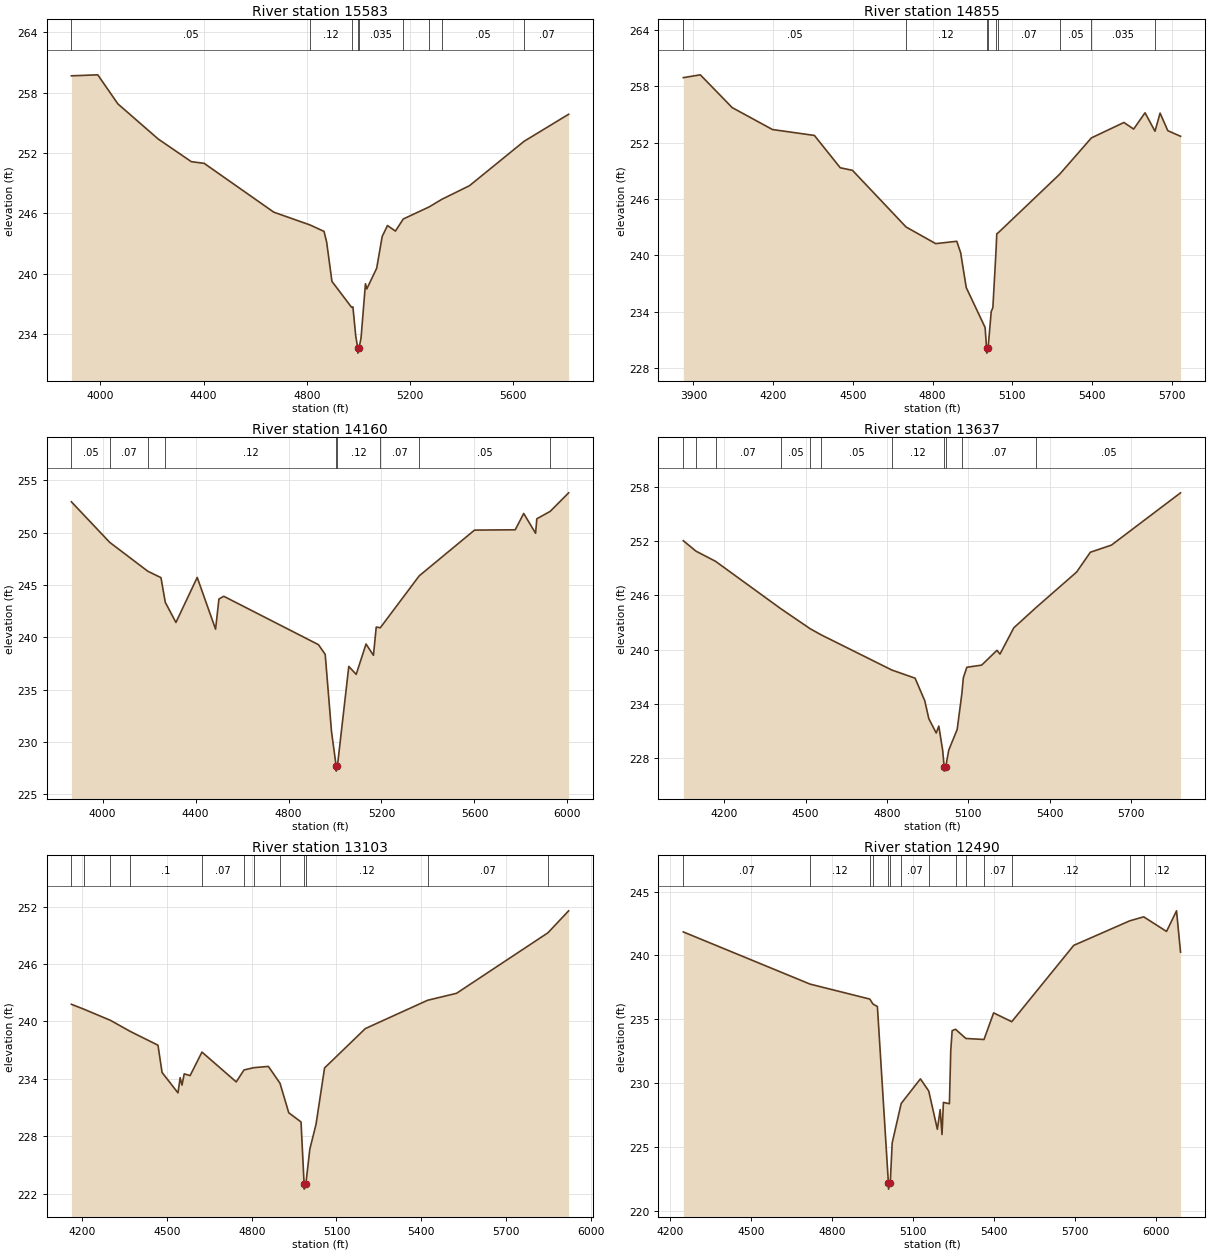
Type RM Length L Ch R = 1 ,15583   ,728,728,728
BEGIN DESCRIPTION:
Mapping XS 1201a0b5
END DESCRIPTION:
XS GIS Cut Line= 3
      2472963.34     13504831.03      2472468.53     13504240.74
      2471340.02     13503988.99
#Sta/Elev= 30
  3887.7  259.66  3989.9  259.76  4067.9  256.87  4224.1  253.38  4352.3  251.13
  4402.3  250.96  4671.8  246.11  4812.1  244.84  4866.5   244.2  4876.7  243.13
  4897.2  239.23  4973.4  236.65  4978.4   236.7  4989.4   233.8  4997.2   232.6
  4997.5   232.1  5002.2   232.6  5009.9   233.6    5027     239  5032.2  238.48
  5070.5  240.54  5091.9   243.7  5112.4  244.78  5143.1  244.23  5173.5  245.43
  5273.6  246.63  5323.1  247.39    5430  248.74    5642  253.16  5814.2  255.84
#Mann= 9 ,-1 , 0
  3887.7     .05       0  4812.1     .12       0  4973.4    .035       0
  4997.2    .035       0  5002.2    .035       0  5173.5     .05       0
  5273.6     .12       0  5323.1     .05       0    5642     .07       0
Bank Sta=4997.2,5002.2
XS Rating Curve= 0 ,0
Exp/Cntr=0.3,0.1

Type RM Length L Ch R = 1 ,14855   ,695,695,695
BEGIN DESCRIPTION:
Mapping XS 97e6870a
END DESCRIPTION:
XS GIS Cut Line= 3
      2473076.18      13504579.3      2472702.91     13503771.99
      2471912.96     13503190.37
#Sta/Elev= 30
  3862.1  258.91    3926  259.21  4046.1  255.72  4197.4  253.39  4355.2  252.76
  4452.5  249.32  4498.3  249.05    4700  243.02  4811.4  241.25  4890.8   241.5
  4905.4  240.27  4926.3  236.58  4997.3  232.33  5002.9   230.1  5003.4   229.6
  5008.4   230.1  5020.3  234.02  5026.5  234.44  5038.5  240.56  5041.2   242.3
  5046.4   242.4  5277.6  248.63  5397.2   252.5  5519.5  254.14  5556.1  253.44
  5598.9  255.17  5636.4  253.21  5655.5  255.14  5684.5  253.27  5732.5  252.67
#Mann= 9 ,-1 , 0
  3862.1     .05       0    4700     .12       0  5002.9     .05       0
  5008.4     .12       0  5038.5      .1       0  5046.4     .07       0
  5277.6     .05       0  5397.2    .035       0  5636.4     .07       0
Bank Sta=5002.9,5008.4
XS Rating Curve= 0 ,0
Exp/Cntr=0.3,0.1

Type RM Length L Ch R = 1 ,14160   ,523,523,523
BEGIN DESCRIPTION:
Mapping XS ac02aa6f
END DESCRIPTION:
XS GIS Cut Line= 3
      2473744.58     13504145.26      2473050.13     13503233.79
      2472112.64     13502903.93
#Sta/Elev= 30
  3865.6  252.95  4030.5  249.08  4194.5  246.32    4251  245.71  4269.7  243.35
  4315.4  241.43    4407  245.73    4486  240.79  4500.5  243.67  4521.3  243.93
  4928.7  239.31  4957.8  238.38  4984.9  231.01  5004.8  227.73  5005.2  227.23
  5010.4  227.73  5059.3  237.23  5091.1  236.47  5133.5  239.37  5165.3  238.29
  5177.4  240.99  5194.7  240.92  5362.3  245.88  5600.3  250.25  5775.5  250.28
    5812  251.84  5863.1  249.95  5868.4  251.33  5926.1  252.04  6005.3  253.81
#Mann= 9 ,-1 , 0
  3865.6     .05       0  4030.5     .07       0  4194.5      .1       0
  4269.7     .12       0  5004.8     .05       0  5010.4     .12       0
  5194.7     .07       0  5362.3     .05       0  5926.1    .035       0
Bank Sta=5004.8,5010.4
XS Rating Curve= 0 ,0
Exp/Cntr=0.3,0.1

Type RM Length L Ch R = 1 ,13637   ,534,534,534
BEGIN DESCRIPTION:
Mapping XS 470c7baf
END DESCRIPTION:
XS GIS Cut Line= 3
      2474022.38     13503745.98      2473492.84     13502973.37
      2472685.54     13502582.75
#Sta/Elev= 30
  4049.4  252.07  4096.1  250.91  4168.4  249.78  4408.7  244.53  4516.9  242.31
  4556.8  241.64  4817.9  237.73    4904  236.82  4939.8  234.31  4954.7  232.32
    4982  230.74  4991.5  231.51  5005.9  228.78  5011.1  227.01  5011.6  226.51
  5017.1  227.01  5028.1  228.84  5059.3  231.14  5076.6  235.13  5081.9  236.86
  5094.8  238.03  5149.6  238.27  5205.9  239.91    5217  239.49  5268.1  242.41
  5351.4  244.69  5499.6  248.59  5550.3  250.79    5628  251.58  5882.9  257.38
#Mann= 11 ,-1 , 0
  4049.4     .07       0  4096.1     .05       0  4168.4     .07       0
  4408.7     .05       0  4516.9     .12       0  4556.8     .05       0
  4817.9     .12       0  5011.1     .05       0  5017.1     .12       0
  5076.6     .07       0  5351.4     .05       0
Bank Sta=5011.1,5017.1
XS Rating Curve= 0 ,0
Exp/Cntr=0.3,0.1

Type RM Length L Ch R = 1 ,13103   ,613,613,613
BEGIN DESCRIPTION:
Mapping XS 30e975be
END DESCRIPTION:
XS GIS Cut Line= 3
      2474560.52     13503190.37      2473926.87     13502686.92
      2473059.37     13502296.54
#Sta/Elev= 30
  4161.4   241.8  4205.5  241.29  4299.7  240.12  4369.9  238.96    4468  237.52
  4482.4  234.67  4538.8  232.53  4546.5  234.12  4552.9  233.34  4560.9  234.52
  4581.7  234.34  4623.7   236.8  4745.1  233.68  4772.5  234.93  4807.8  235.17
  4858.9   235.3    4900  233.54    4931  230.45  4974.5  229.49  4985.4  222.96
  4985.9  222.46  4991.4  222.96  5005.7  226.66  5027.6  229.24  5057.8  235.14
  5202.2  239.26  5422.5  242.22  5525.1  242.95  5848.7  249.28    5922  251.58
#Mann= 12 ,-1 , 0
  4161.4     .12       0  4205.5      .1       0  4299.7     .07       0
  4369.9      .1       0  4623.7     .07       0  4772.5     .12       0
  4807.8     .07       0    4900     .12       0  4985.4     .05       0
  4991.4     .12       0  5422.5     .07       0  5848.7     .05       0
Bank Sta=4985.4,4991.4
XS Rating Curve= 0 ,0
Exp/Cntr=0.3,0.1

Type RM Length L Ch R = 1 ,12490   ,581,581,581
BEGIN DESCRIPTION:
Mapping XS e851fd9c
END DESCRIPTION:
XS GIS Cut Line= 4
      2474760.19     13503077.52      2474543.19     13502487.26
      2474204.64      13502383.1      2473389.32     13502114.21
#Sta/Elev= 30
  4247.8  241.84  4717.3  237.76  4938.5  236.59  4950.3   236.2  4966.6  236.01
  5007.3  222.23  5007.8  221.73  5014.3  222.23  5021.3  225.34  5054.8  228.43
  5125.9  230.35  5156.8   229.4  5188.7  226.41  5199.1  227.95  5205.9     226
  5211.1  228.51  5233.3  228.41  5238.3  232.57  5243.5  234.12    5256  234.23
  5294.2  233.51  5361.4  233.43  5397.1  235.51  5464.2  234.82  5693.8  240.79
  5901.5  242.71  5952.8  243.02  6037.5  241.88  6074.5  243.49  6089.4  240.26
#Mann= 14 ,-1 , 0
  4247.8     .07       0  4717.3     .12       0  4938.5     .07       0
  4950.3     .12       0  5007.3     .05       0  5014.3     .12       0
  5054.8     .07       0  5156.8     .12       0    5256     .07       0
  5294.2     .12       0  5361.4     .07       0  5464.2     .12       0
  5901.5     .07       0  5952.8     .12       0
Bank Sta=5007.3,5014.3
XS Rating Curve= 0 ,0
Exp/Cntr=0.3,0.1

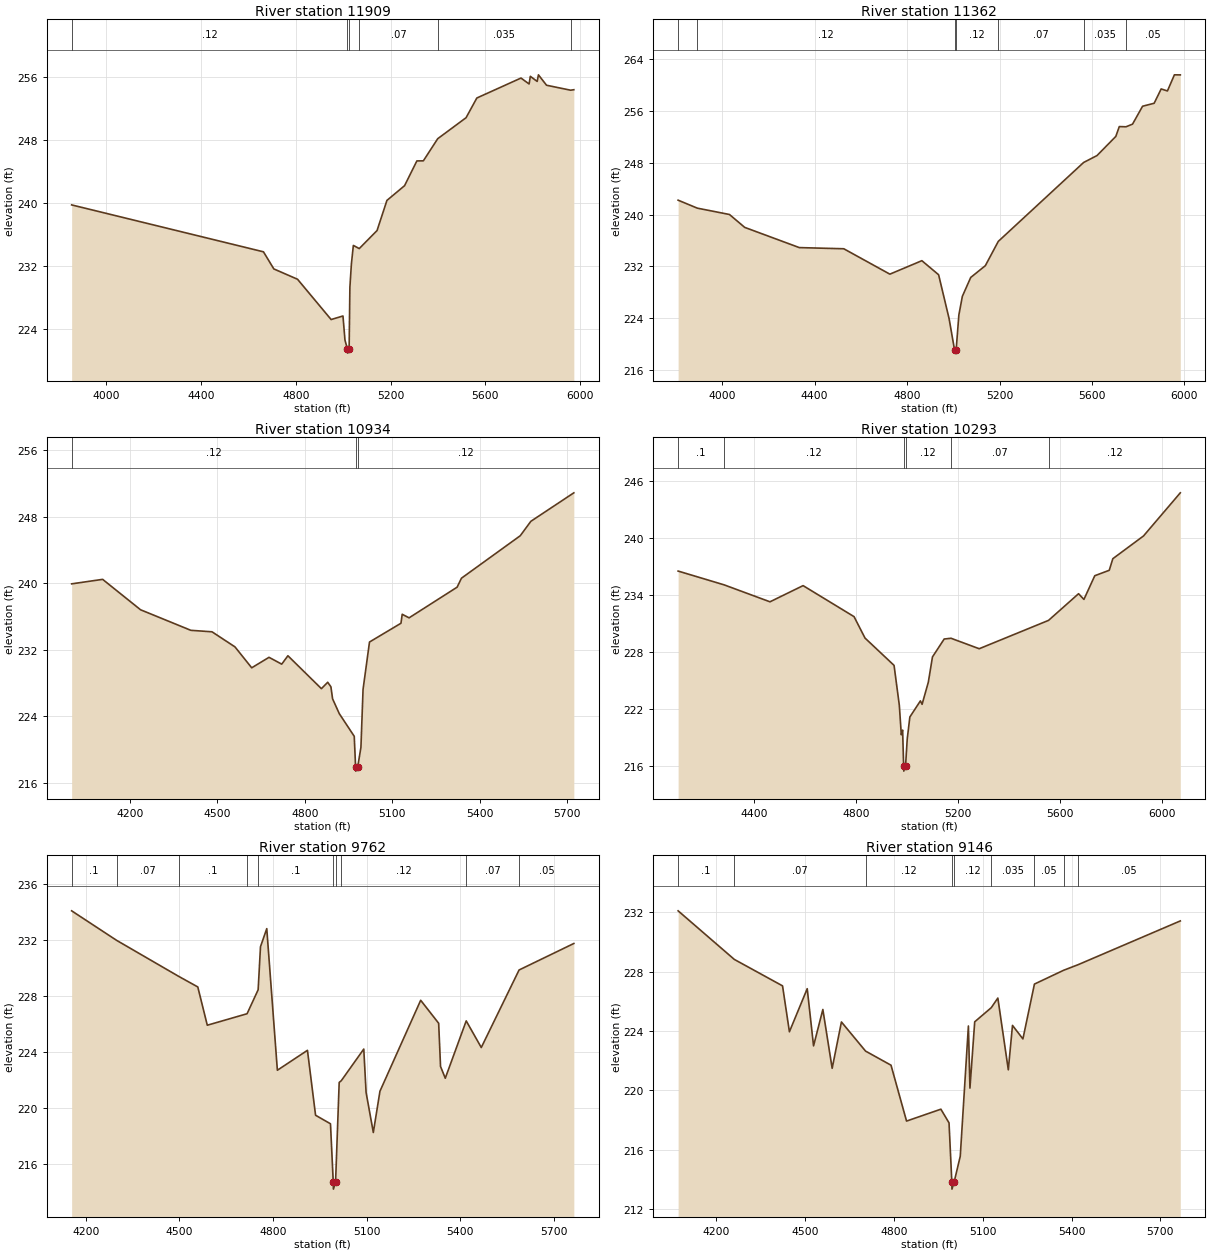
Type RM Length L Ch R = 1 ,11909   ,547,547,547
BEGIN DESCRIPTION:
Mapping XS 1e388db2
END DESCRIPTION:
XS GIS Cut Line= 4
      2474985.89     13502808.44      2474569.23     13502183.44
       2474091.8     13501827.54      2473346.71     13501619.61
#Sta/Elev= 30
  3853.3  239.79  4663.1  233.84  4706.9  231.67    4807  230.36  4948.8  225.25
  4998.8   225.7  5007.2  222.65  5017.8  221.49  5018.3  220.99  5024.8  221.49
    5028  229.33  5034.3  232.27  5042.6  234.65  5067.5  234.25  5142.7  236.54
  5184.4  240.36  5258.9  242.23  5310.8  245.37  5338.2  245.38  5398.9  248.19
  5518.5  250.85    5564  253.35  5750.4  255.88  5784.6  255.13  5789.8   256.1
  5818.8  255.45    5824  256.29  5858.2  254.97  5959.7  254.34  5973.5   254.4
#Mann= 6 ,-1 , 0
  3853.3     .12       0  5017.8     .05       0  5024.8     .12       0
  5067.5     .07       0  5398.9    .035       0  5959.7     .07       0
Bank Sta=5017.8,5024.8
XS Rating Curve= 0 ,0
Exp/Cntr=0.3,0.1

Type RM Length L Ch R = 1 ,11362   ,428,428,428
BEGIN DESCRIPTION:
Mapping XS 5a3451c8
END DESCRIPTION:
XS GIS Cut Line= 3
      2475255.01     13502704.31      2474794.92     13501836.22
      2473798.31     13501186.26
#Sta/Elev= 30
  3809.8  242.22  3892.8  240.99  4031.9  240.01  4097.9  238.02  4334.1   234.9
  4526.4  234.72  4725.8   230.8  4864.2  232.88  4936.6  230.71    4982  223.93
  5005.5  219.11    5006  218.61  5012.5  219.11  5024.2  224.49  5039.3  227.37
  5075.5  230.29  5138.8  232.11  5194.8  235.86  5563.9  248.04  5621.9  249.11
  5703.1  252.06  5718.2  253.58  5747.5  253.55  5775.5  253.96  5818.9  256.72
    5869  257.18  5899.3  259.39  5926.4  259.08  5956.6  261.57  5982.1  261.56
#Mann= 7 ,-1 , 0
  3809.8    .035       0  3892.8     .12       0  5005.5     .05       0
  5012.5     .12       0  5194.8     .07       0  5563.9    .035       0
  5747.5     .05       0
Bank Sta=5005.5,5012.5
XS Rating Curve= 0 ,0
Exp/Cntr=0.3,0.1

Type RM Length L Ch R = 1 ,10934   ,641,641,641
BEGIN DESCRIPTION:
Mapping XS c3612710
END DESCRIPTION:
XS GIS Cut Line= 4
      2475480.69     13502374.43      2475011.94     13501645.25
      2474899.09     13501402.19      2474412.97     13501072.33
#Sta/Elev= 30
  4000.2  239.94  4106.5  240.48  4236.6  236.82    4409  234.35  4481.6  234.17
  4560.2  232.36  4617.7  229.84  4677.1   231.1  4720.7  230.28  4741.9  231.29
  4856.8  227.33  4878.4   228.1  4889.4  227.55  4895.1  226.11    4918  224.33
  4969.4   221.6    4974  217.91  4974.5  217.41  4981.2  217.91  4992.3  220.27
  4999.6  227.24  5021.7  232.94  5129.6   235.2  5133.9  236.28  5157.4  235.85
  5322.2  239.54  5337.1  240.62  5538.8  245.73    5575  247.46  5722.5  250.89
#Mann= 3 ,-1 , 0
  4000.2     .12       0    4974     .05       0  4981.2     .12       0
Bank Sta=4974,4981.2
XS Rating Curve= 0 ,0
Exp/Cntr=0.3,0.1

Type RM Length L Ch R = 1 ,10293   ,531,531,531
BEGIN DESCRIPTION:
Mapping XS 2bcda08c
END DESCRIPTION:
XS GIS Cut Line= 4
       2475827.9     13502383.07      2475593.53     13501636.57
      2475515.41     13501332.75      2474916.92     13500699.56
#Sta/Elev= 30
  4102.4  236.53  4282.7  235.08  4462.3   233.3    4592     235  4791.7  231.74
  4834.6  229.49  4948.4  226.62    4969  222.43  4976.8  219.33  4981.9  219.82
    4986  216.01  4986.5  215.51  4993.3  216.01    5000  218.89  5010.3   221.2
  5051.6  222.89  5058.2  222.53  5082.6  224.85  5098.9  227.51  5144.8  229.39
  5171.5  229.47    5282  228.37  5553.7  231.35  5671.2  234.15  5692.2  233.55
  5734.7  236.04  5791.4  236.61  5805.5  237.83  5925.7  240.22  6069.8  244.75
#Mann= 6 ,-1 , 0
  4102.4      .1       0  4282.7     .12       0    4986     .05       0
  4993.3     .12       0  5171.5     .07       0  5553.7     .12       0
Bank Sta=4986,4993.3
XS Rating Curve= 0 ,0
Exp/Cntr=0.3,0.1

Type RM Length L Ch R = 1 ,9762    ,616,616,616
BEGIN DESCRIPTION:
Mapping XS e83d382f
END DESCRIPTION:
XS GIS Cut Line= 3
      2476102.84     13502168.27      2476036.24     13501341.43
      2475619.79     13500682.05
#Sta/Elev= 30
  4154.8  234.09  4299.2  231.98  4497.5  229.42  4559.1  228.66  4589.5  225.93
    4717  226.75  4752.5  228.46    4760  231.53  4780.1  232.82  4814.1  222.72
  4910.5  224.14  4936.5  219.51  4984.3   218.9  4993.2  214.74  4993.7  214.24
  5000.6  214.74  5012.2  221.85  5018.8  221.97    5091  224.23  5098.4  221.14
  5121.6  218.28  5142.8  221.22  5273.4  227.71    5331  226.07    5337  222.99
  5352.2  222.15  5419.3  226.24  5467.6  224.34  5588.7  229.87  5764.2  231.76
#Mann= 10 ,-1 , 0
  4154.8      .1       0  4299.2     .07       0  4497.5      .1       0
    4717     .07       0  4752.5      .1       0  4993.2     .05       0
  5000.6      .1       0  5018.8     .12       0  5419.3     .07       0
  5588.7     .05       0
Bank Sta=4993.2,5000.6
XS Rating Curve= 0 ,0
Exp/Cntr=0.3,0.1

Type RM Length L Ch R = 1 ,9146    ,682,682,682
BEGIN DESCRIPTION:
Mapping XS 7de4ad32
END DESCRIPTION:
XS GIS Cut Line= 4
      2476869.59     13502061.96      2476661.24     13501384.83
      2476557.08     13501046.29      2476096.97     13500612.23
#Sta/Elev= 30
    4072  232.09  4261.7  228.82  4424.5  227.04  4447.7  223.95  4507.8  226.85
  4529.2     223  4560.6  225.45    4592  221.49  4623.3  224.61  4704.7  222.65
  4790.7   221.7  4843.1  217.94    4959  218.74  4986.5  217.82  4995.9  213.86
  4996.4  213.36    5004  213.86  5024.4  215.57  5051.9  224.34  5057.1  220.16
  5073.2  224.62    5129  225.57  5151.3  226.22  5186.6  221.39  5200.7  224.38
  5235.9  223.47  5274.8  227.16  5373.5  228.09  5422.9  228.47  5767.2  231.41
#Mann= 9 ,-1 , 0
    4072      .1       0  4261.7     .07       0  4704.7     .12       0
  4995.9     .05       0    5004     .12       0    5129    .035       0
  5274.8     .05       0  5373.5    .035       0  5422.9     .05       0
Bank Sta=4995.9,5004
XS Rating Curve= 0 ,0
Exp/Cntr=0.3,0.1

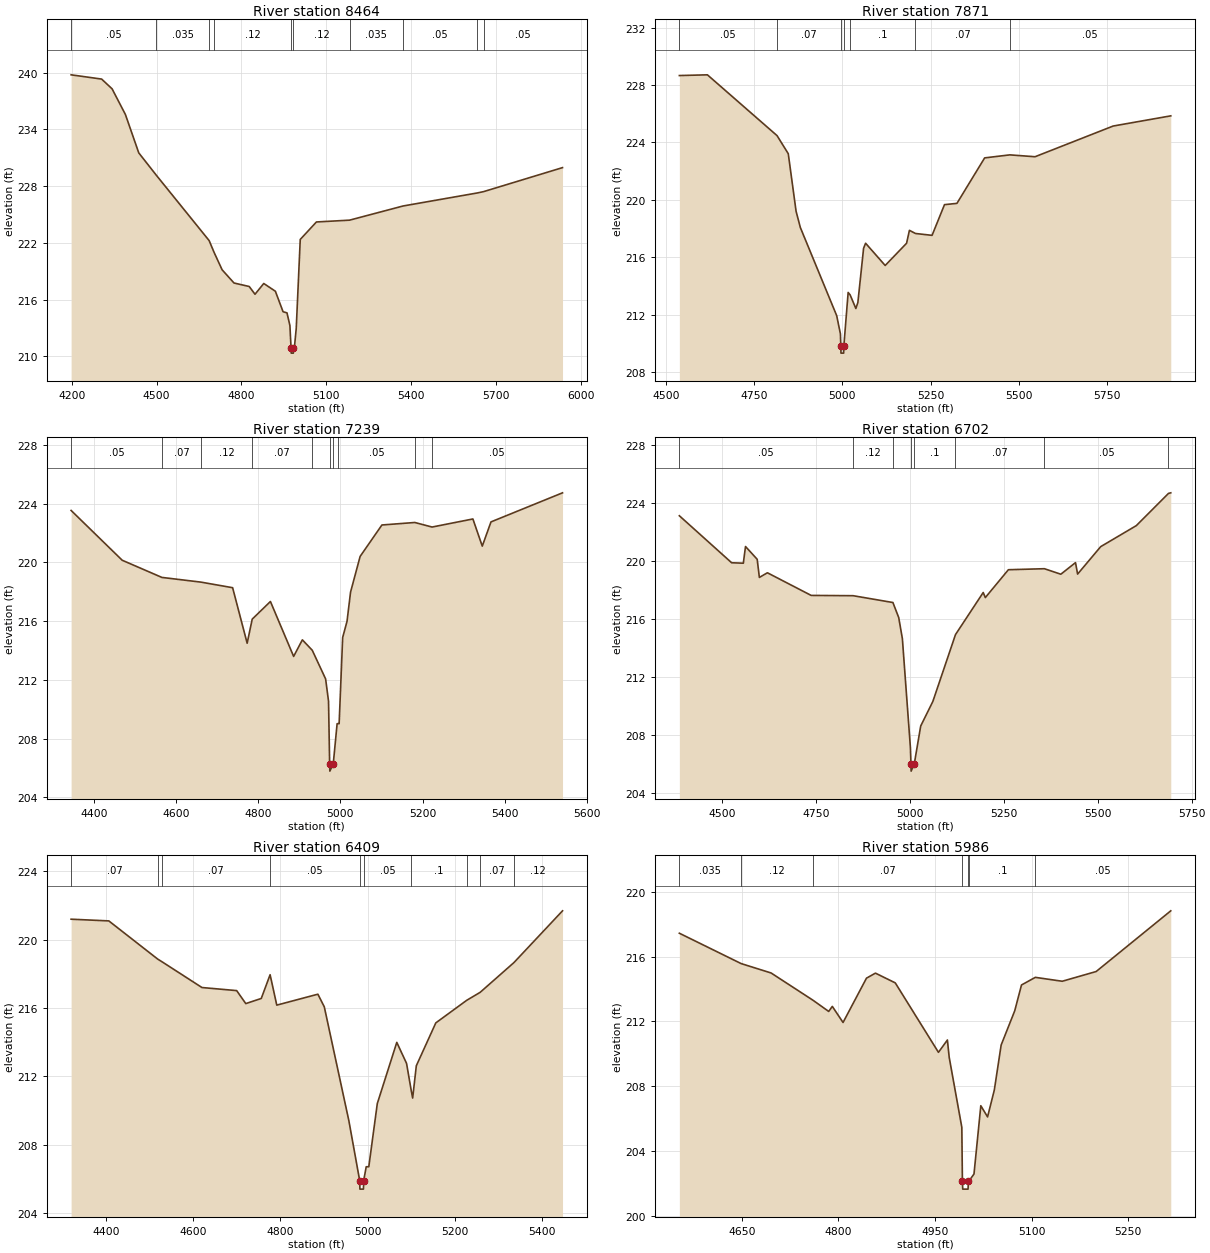
Type RM Length L Ch R = 1 ,8464    ,593,593,593
BEGIN DESCRIPTION:
Mapping XS f67cf248
END DESCRIPTION:
XS GIS Cut Line= 3
      2477364.37     13501957.77      2477182.08     13501193.86
      2476454.36     13500578.77
#Sta/Elev= 30
  4197.4  239.78  4305.3  239.33  4342.3   238.3  4389.5  235.58  4436.7  231.52
  4499.2  229.14  4685.6  222.24  4703.3  220.98  4731.5  219.15  4773.6  217.75
  4827.4  217.38  4847.9  216.56  4878.8   217.7  4919.9  216.88  4947.1  214.71
    4961  214.59  4971.3  213.25  4975.4  210.83  4975.9  210.33  4983.4  210.33
  4983.9  210.83  4987.1   210.9  4993.7  212.94  5007.9  222.36  5065.1  224.21
  5182.2   224.4  5371.6   225.9  5634.3  227.28  5656.4  227.42  5935.6  229.96
#Mann= 10 ,-1 , 0
  4197.4     .05       0  4499.2    .035       0  4685.6     .07       0
  4703.3     .12       0  4975.4     .05       0  4983.9     .12       0
  5182.2    .035       0  5371.6     .05       0  5634.3    .035       0
  5656.4     .05       0
Bank Sta=4975.4,4983.9
XS Rating Curve= 0 ,0
Exp/Cntr=0.3,0.1

Type RM Length L Ch R = 1 ,7871    ,632,632,632
BEGIN DESCRIPTION:
Mapping XS 9733a2a3
END DESCRIPTION:
XS GIS Cut Line= 3
      2477919.92     13501706.02      2477642.14     13501193.86
      2477009.23       13500691.
#Sta/Elev= 30
  4538.6  228.66    4618  228.71  4815.2  224.47  4846.9  223.21    4869   219.2
    4881  218.07    4984  211.92  4994.5  210.65  4995.6  209.81  4996.1  209.31
  5003.7  209.31  5004.2  209.81  5016.4  213.54    5022  213.37  5038.2  212.42
  5043.9  212.84  5060.1  216.62  5065.8  216.97  5121.2  215.42  5181.8  216.97
  5189.8  217.87    5207  217.65  5253.9  217.52  5289.1  219.66  5324.3  219.75
  5402.8  222.92    5474  223.13  5545.4     223  5766.5  225.14  5929.6  225.85
#Mann= 7 ,-1 , 0
  4538.6     .05       0  4815.2     .07       0  4995.6     .05       0
  5004.2     .07       0    5022      .1       0    5207     .07       0
    5474     .05       0
Bank Sta=4995.6,5004.2
XS Rating Curve= 0 ,0
Exp/Cntr=0.3,0.1

Type RM Length L Ch R = 1 ,7239    ,537,537,537
BEGIN DESCRIPTION:
Mapping XS 59b80459
END DESCRIPTION:
XS GIS Cut Line= 3
      2478273.21     13501252.64      2477813.16     13500790.42
      2477300.99     13500608.12
#Sta/Elev= 30
  4344.7  223.53    4469  220.14  4565.6  218.97  4660.5  218.65  4737.7  218.27
  4773.1  214.49  4785.4  216.13  4829.7  217.33  4886.2  213.59  4907.4  214.72
  4931.5  214.01    4964  212.06  4971.1  210.54  4973.8  206.28  4974.3  205.78
  4982.6  206.28    4992  209.01  4995.1  209.01  4996.9  209.01  5005.5  214.88
  5016.1  215.98  5024.7  217.97    5048   220.4    5101  222.54    5181  222.71
  5223.1   222.4  5322.4  222.95  5345.2   221.1  5366.4  222.75  5540.5  224.73
#Mann= 10 ,-1 , 0
  4344.7     .05       0  4565.6     .07       0  4660.5     .12       0
  4785.4     .07       0  4931.5      .1       0  4973.8     .05       0
  4982.6      .1       0  4995.1     .05       0    5181     .07       0
  5223.1     .05       0
Bank Sta=4973.8,4982.6
XS Rating Curve= 0 ,0
Exp/Cntr=0.3,0.1

Type RM Length L Ch R = 1 ,6702    ,293,293,293
BEGIN DESCRIPTION:
Mapping XS caaa6332
END DESCRIPTION:
XS GIS Cut Line= 3
      2478548.82     13501094.21      2478221.14     13500549.53
      2477620.02     13500247.89
#Sta/Elev= 30
  4386.2  223.13  4525.4  219.89  4556.5  219.86  4562.3  221.01  4593.4  220.13
  4599.2  218.88  4620.6   219.2  4737.1  217.64  4848.8  217.62  4954.7  217.15
  4970.2  216.11  4979.9  214.66  5001.3  207.14  5002.7  206.03  5003.2  205.53
  5011.6  206.03  5028.7  208.64    5061  210.33  5121.3  214.94  5195.1  217.84
  5200.7  217.49  5262.1  219.41    5358  219.48  5401.7   219.1  5440.8   219.9
  5446.4  219.11  5507.8     221  5602.7  222.45  5688.3  224.67  5694.4  224.71
#Mann= 8 ,-1 , 0
  4386.2     .05       0  4848.8     .12       0  4954.7      .1       0
  5002.7     .05       0  5011.6      .1       0  5121.3     .07       0
    5358     .05       0  5688.3     .07       0
Bank Sta=5002.7,5011.6
XS Rating Curve= 0 ,0
Exp/Cntr=0.3,0.1

Type RM Length L Ch R = 1 ,6409    ,423,423,423
BEGIN DESCRIPTION:
DRY CREEK (GOLIAD) 13.0
END DESCRIPTION:
XS GIS Cut Line= 3
      2478774.99     13500874.99        2478375.       13500325.
      2477974.98     13500124.99
#Sta/Elev= 30
  4319.7  221.19  4406.2  221.09  4518.1  218.86  4528.1   218.7  4619.9  217.19
  4699.5  217.01  4720.4  216.25  4755.9  216.55  4776.2  217.94  4791.5  216.16
  4885.8   216.8  4900.5  216.06  4956.9  209.39  4981.7  205.89  4982.2  205.39
  4990.3  205.39  4990.8  205.89  4996.7   206.7  5002.6   206.7  5022.1   210.4
  5066.8  213.98  5089.2  212.75  5100.5  211.08  5103.2  210.72  5111.6  212.61
  5156.3  215.12  5227.1  216.44  5258.1  216.91  5335.5  218.65    5447  221.68
#Mann= 10 ,-1 , 0
  4319.7     .07       0  4518.1     .05       0  4528.1     .07       0
  4776.2     .05       0  4981.7     .05       0  4990.8     .05       0
  5100.5      .1       0  5227.1     .05       0  5258.1     .07       0
  5335.5     .12       0
Bank Sta=4981.7,4990.8
XS Rating Curve= 0 ,0
Exp/Cntr=0.3,0.1

Type RM Length L Ch R = 1 ,5986    ,456,456,456
BEGIN DESCRIPTION:
DRY CREEK (GOLIAD) 12.0
END DESCRIPTION:
XS GIS Cut Line= 3
      2478974.98     13500174.99        2478575.       13499975.
      2478275.01       13499875.
#Sta/Elev= 30
  4552.8  217.44  4648.7  215.57  4695.3  214.99  4760.4  213.31  4784.8  212.62
  4790.4  212.93  4807.1  211.94  4843.5  214.67  4857.4  214.98  4888.2  214.38
  4955.3   210.1  4969.2  210.86    4972  209.79  4991.6  205.48  4992.5  202.17
    4993  201.67  5001.3  201.67  5001.8  202.17  5003.2   202.2  5010.5   202.6
  5021.1  206.81  5031.6  206.12  5042.1  207.78  5052.7  210.55  5073.8  212.66
  5084.3  214.25  5105.8  214.72  5147.6  214.48  5200.3  215.08  5316.2  218.82
#Mann= 7 ,-1 , 0
  4552.8    .035       0  4648.7     .12       0  4760.4     .07       0
  4992.5     .05       0  5001.8     .07       0  5003.2      .1       0
  5105.8     .05       0
Bank Sta=4992.5,5001.8
XS Rating Curve= 0 ,0
Exp/Cntr=0.3,0.1

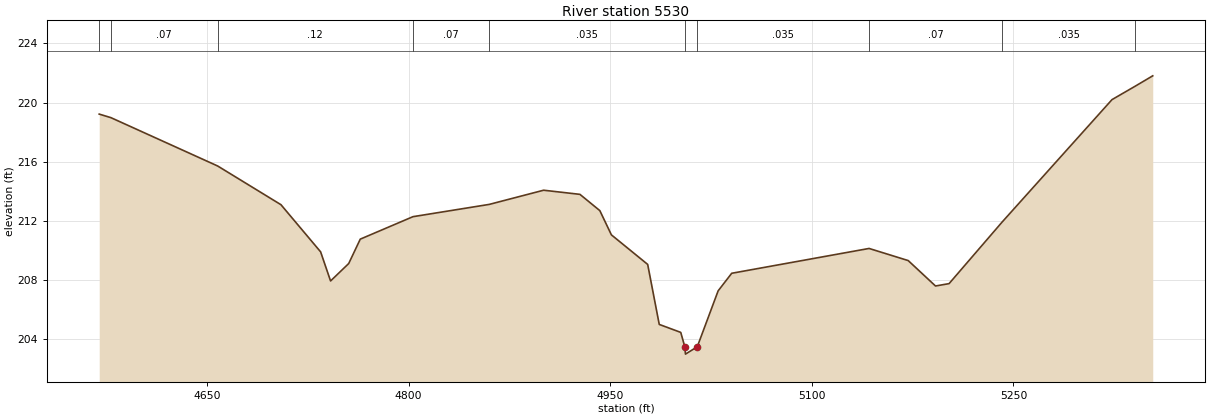
Type RM Length L Ch R = 1 ,5530    ,768,768,768
BEGIN DESCRIPTION:
DRY CREEK (GOLIAD) 11.0
END DESCRIPTION:
XS GIS Cut Line= 3
      2479075.01       13499825.        2478725.       13499575.
      2478374.98       13499525.
#Sta/Elev= 30
  4569.9  219.22  4578.6  218.98    4658  215.71  4705.1  213.09  4734.6   209.9
    4742  207.93  4755.5  209.11  4764.1  210.76  4803.3  212.28    4860  213.11
  4900.5  214.07  4927.5  213.79  4942.3  212.69  4950.9  211.05  4977.9  209.05
  4986.5  204.99  5002.5  204.45  5005.5  203.48    5006  202.98  5014.8  203.48
  5030.3  207.26  5040.4  208.45  5142.6  210.13  5171.7  209.31    5192  207.59
  5202.1  207.75  5241.5  211.91  5323.3   220.2  5340.4   221.1  5353.6  221.81
#Mann= 10 ,-1 , 0
  4569.9     .05       0  4578.6     .07       0    4658     .12       0
  4803.3     .07       0    4860    .035       0  5005.5    .035       0
  5014.8    .035       0  5142.6     .07       0  5241.5    .035       0
  5340.4     .07       0
Bank Sta=5005.5,5014.8
XS Rating Curve= 0 ,0
Exp/Cntr=0.3,0.1