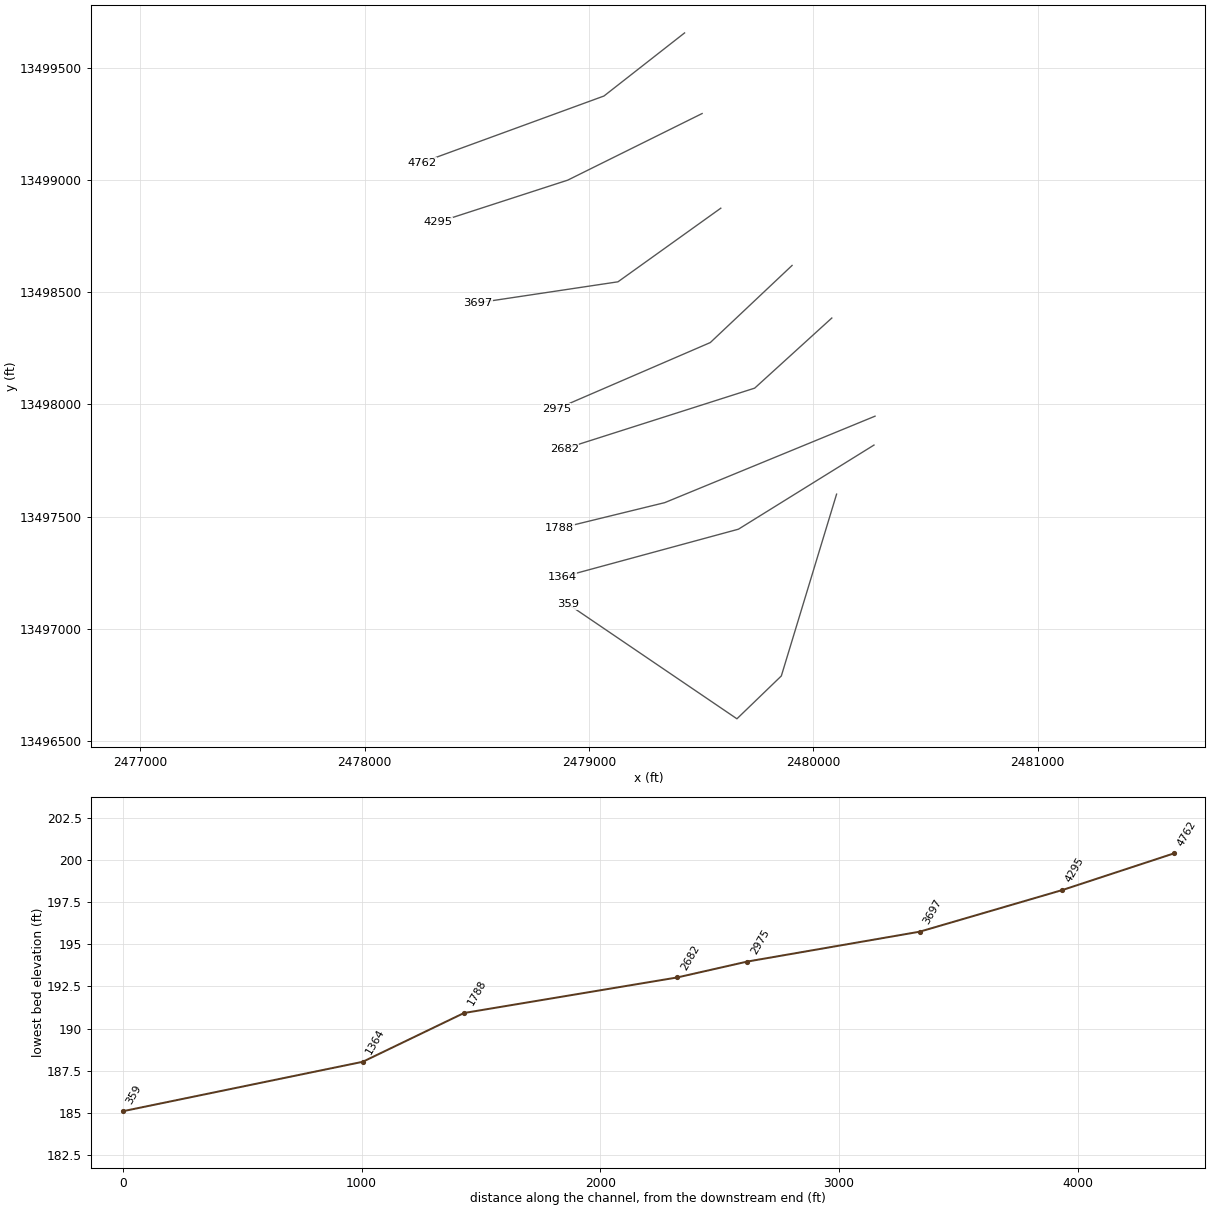
HEC-RAS study DRY CREEK GOLIAD.prj: DRY CREEK GOLIAD Base Level Engineering

--- DRY CREEK GOLIAD.g01 (geometry) --- (continued)

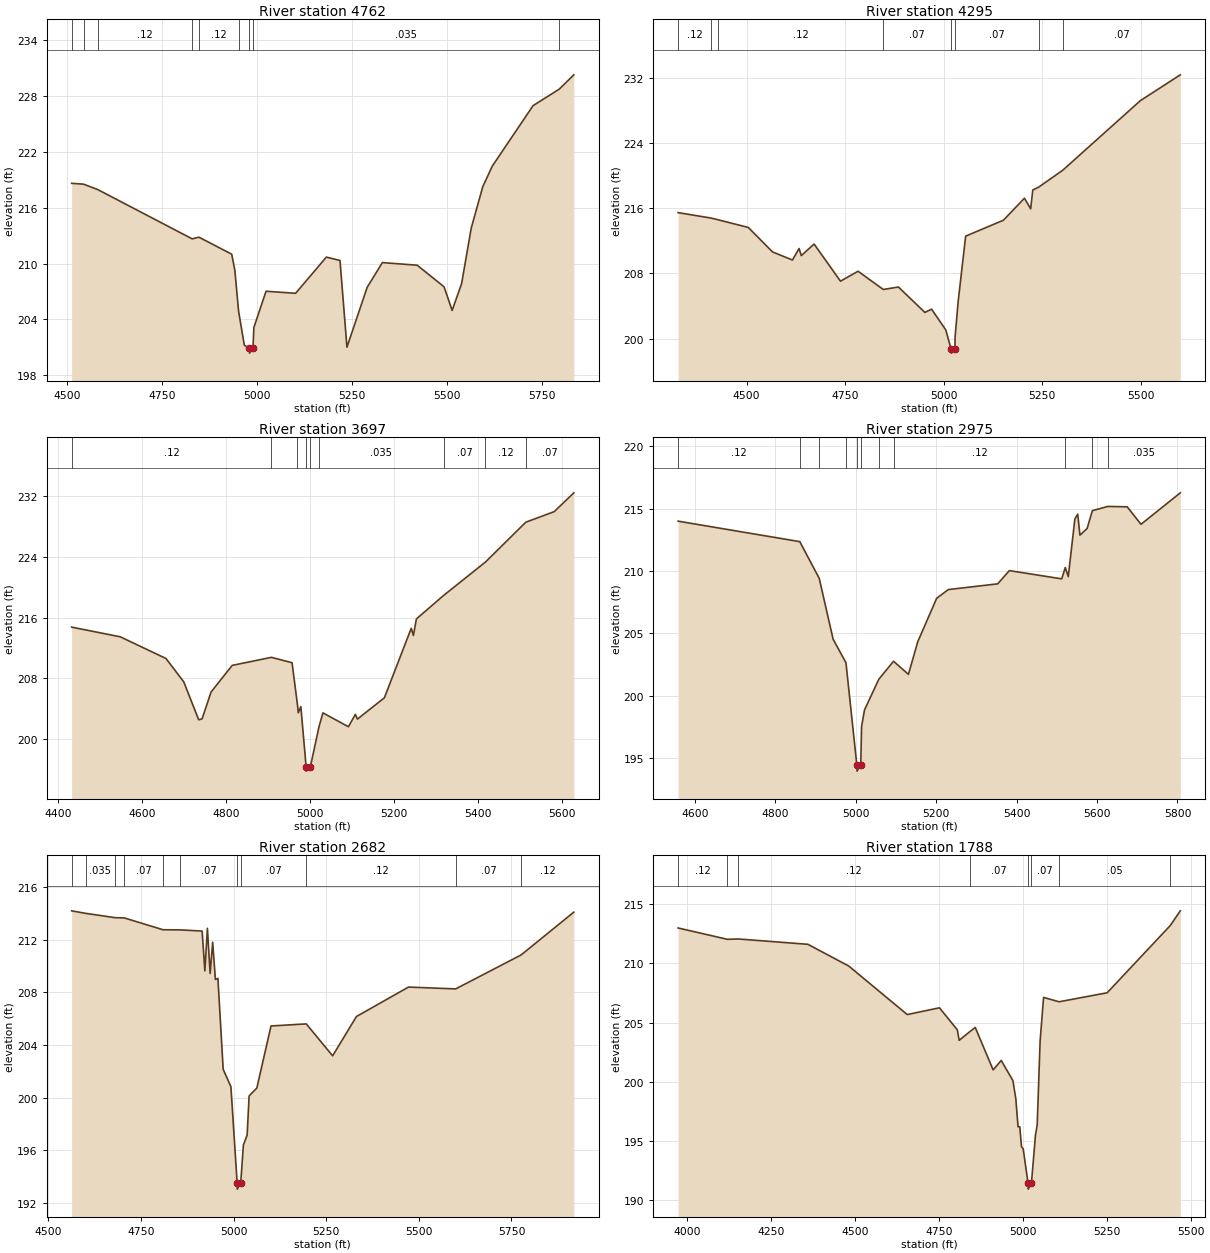
Type RM Length L Ch R = 1 ,4762    ,467,467,467
BEGIN DESCRIPTION:
Mapping XS b68acb21
END DESCRIPTION:
XS GIS Cut Line= 3
      2479426.15     13499656.16      2479066.78     13499374.91
      2478254.27     13499078.03
#Sta/Elev= 30
    4512  218.63  4543.2  218.54  4580.6  217.96  4829.2  212.66    4847  212.84
  4933.2  211.01  4941.4  209.29  4951.3  204.88  4966.3  201.24  4979.7  200.88
  4980.2  200.38  4989.1  200.88  4991.5  203.14  5023.5  207.03  5101.3  206.81
  5182.2   210.7  5218.1  210.34  5236.4  201.02  5289.6  207.45  5329.6  210.11
  5421.2  209.83  5491.9  207.51  5513.2  204.97  5538.1  207.85  5563.3  213.79
  5593.8  218.27    5619  220.49  5726.2  226.98  5794.7  228.74  5833.4  230.29
#Mann= 9 ,-1 , 0
    4512     .12       0  4543.2     .07       0  4580.6     .12       0
  4829.2     .07       0    4847     .12       0  4951.3    .035       0
  4979.7    .035       0  4989.1    .035       0  5794.7     .07       0
Bank Sta=4979.7,4989.1
XS Rating Curve= 0 ,0
Exp/Cntr=0.3,0.1

Type RM Length L Ch R = 1 ,4295    ,598,598,598
BEGIN DESCRIPTION:
Mapping XS 2e19df3f
END DESCRIPTION:
XS GIS Cut Line= 3
       2479504.3      13499296.8      2478905.32     13498999.91
      2478328.61     13498812.87
#Sta/Elev= 30
  4326.2  215.47  4410.2   214.8  4426.3  214.61  4504.3  213.65    4566  210.64
  4616.4  209.65  4633.3  211.06  4638.9  210.19  4671.4  211.61  4738.4  207.05
    4783  208.27    4847  206.03  4885.5  206.33  4952.7  203.21  4969.6  203.61
  5005.6  201.07  5019.3  198.71  5019.8  198.21  5028.9  198.71  5029.3  200.22
  5037.1  204.55  5056.1  212.58    5152  214.54  5205.3  217.24  5221.2  215.94
  5226.5  218.24  5242.3  218.63  5302.6  220.68  5499.7  229.23    5601   232.4
#Mann= 8 ,-1 , 0
  4326.2     .12       0  4410.2     .07       0  4426.3     .12       0
    4847     .07       0  5019.3     .05       0  5028.9     .07       0
  5242.3    .035       0  5302.6     .07       0
Bank Sta=5019.3,5028.9
XS Rating Curve= 0 ,0
Exp/Cntr=0.3,0.1

Type RM Length L Ch R = 1 ,3697    ,722,722,722
BEGIN DESCRIPTION:
Mapping XS b33eeea5
END DESCRIPTION:
XS GIS Cut Line= 3
      2479587.59      13498874.9      2479129.28     13498546.78
      2478504.23     13498453.03
#Sta/Elev= 30
    4432  214.75  4547.8  213.47  4656.6  210.61  4698.9  207.53  4734.5  202.52
  4742.6  202.64    4764  206.19  4814.3   209.7  4907.6  210.76  4956.8  210.05
  4969.6  204.53  4971.6  203.44  4977.7  204.26  4990.4  196.24  4990.9  195.74
  5000.1  196.24  5021.1  201.64  5030.3  203.43    5091   201.6  5107.5  203.23
  5112.5  202.61  5176.6  205.42  5240.6   214.6  5245.7  213.65  5252.8  215.83
    5318  218.95    5417  223.33  5513.3   228.6  5581.1     230  5627.7  232.48
#Mann= 9 ,-1 , 0
    4432     .12       0  4907.6    .035       0  4969.6     .07       0
  4990.4     .05       0  5000.1     .07       0  5021.1    .035       0
    5318     .07       0    5417     .12       0  5513.3     .07       0
Bank Sta=4990.4,5000.1
XS Rating Curve= 0 ,0
Exp/Cntr=0.3,0.1

Type RM Length L Ch R = 1 ,2975    ,293,293,293
BEGIN DESCRIPTION:
Mapping XS a95bc107
END DESCRIPTION:
XS GIS Cut Line= 3
      2479905.33     13498619.71      2479540.73     13498275.95
       2478854.3     13497979.54
#Sta/Elev= 30
  4558.3  213.99  4860.9  212.35  4909.2  209.41  4943.7  204.54  4975.7  202.65
  5002.7  194.47  5003.2  193.97  5012.5  194.47  5014.5  197.53  5021.8  198.87
  5057.4  201.33    5094  202.77    5131  201.72  5154.2  204.33  5201.2  207.81
  5230.1  208.51  5353.1  208.97    5382  210.03  5512.2  209.37  5521.1  210.28
  5528.5  209.55  5544.9  214.16    5552  214.55  5557.5  212.87  5575.5  213.41
  5588.4  214.83  5626.8  215.17    5675  215.14  5709.4  213.74  5807.1  216.26
#Mann= 11 ,-1 , 0
  4558.3     .12       0  4860.9     .07       0  4909.2     .12       0
  4975.7    .035       0  5002.7    .035       0  5012.5    .035       0
  5057.4     .07       0    5094     .12       0  5521.1    .035       0
  5588.4     .12       0  5626.8    .035       0
Bank Sta=5002.7,5012.5
XS Rating Curve= 0 ,0
Exp/Cntr=0.3,0.1

Type RM Length L Ch R = 1 ,2682    ,894,894,894
BEGIN DESCRIPTION:
Mapping XS 14ea756a
END DESCRIPTION:
XS GIS Cut Line= 3
      2480082.38     13498385.31      2479738.65     13498072.83
      2478889.84     13497802.04
#Sta/Elev= 30
  4562.9   214.2  4600.3  214.01  4680.1  213.68    4705  213.66  4809.6  212.76
  4856.4  212.75  4915.1  212.66  4922.5  209.63  4929.3  212.87  4936.7  209.44
  4943.5  211.81  4950.9  208.98  4957.7  209.06  4971.9  202.15  4992.8  200.82
  5009.5  193.53    5010  193.03  5019.3  193.53  5026.5  196.39  5036.6  197.14
  5041.9  200.12  5062.8  200.72    5101  205.44  5196.2   205.6  5267.3  203.17
  5331.6  206.16  5472.1   208.4  5599.4  208.26  5775.9  210.84  5918.4   214.1
#Mann= 11 ,-1 , 0
  4562.9     .05       0  4600.3    .035       0  4680.1     .12       0
    4705     .07       0  4809.6     .12       0  4856.4     .07       0
  5009.5     .05       0  5019.3     .07       0  5196.2     .12       0
  5599.4     .07       0  5775.9     .12       0
Bank Sta=5009.5,5019.3
XS Rating Curve= 0 ,0
Exp/Cntr=0.3,0.1

Type RM Length L Ch R = 1 ,1788    ,424,424,424
BEGIN DESCRIPTION:
Mapping XS 34634dee
END DESCRIPTION:
XS GIS Cut Line= 3
      2480275.13     13497947.84      2479337.61     13497562.41
      2478869.45     13497447.97
#Sta/Elev= 30
  3972.8     213  4119.7  212.04  4151.9  212.07  4359.2  211.62  4481.1  209.78
  4655.2  205.68  4751.1  206.25  4804.4  204.39  4809.8   203.5  4841.8  204.24
  4857.7  204.59    4911     201    4935   201.8  4969.8   200.1  4978.5  198.57
  4985.2  196.19  4990.4  196.19  4995.4  194.52  5000.6  194.31    5015  191.42
  5015.5  190.92    5025  191.42  5037.1   195.5  5042.2  196.34  5050.9  203.44
  5061.2  207.13  5107.4  206.76  5250.5  207.52  5438.3   213.2  5468.4  214.45
#Mann= 8 ,-1 , 0
  3972.8     .12       0  4119.7    .035       0  4151.9     .12       0
  4841.8     .07       0    5015     .05       0    5025     .07       0
  5107.4     .05       0  5438.3     .12       0
Bank Sta=5015,5025
XS Rating Curve= 0 ,0
Exp/Cntr=0.3,0.1

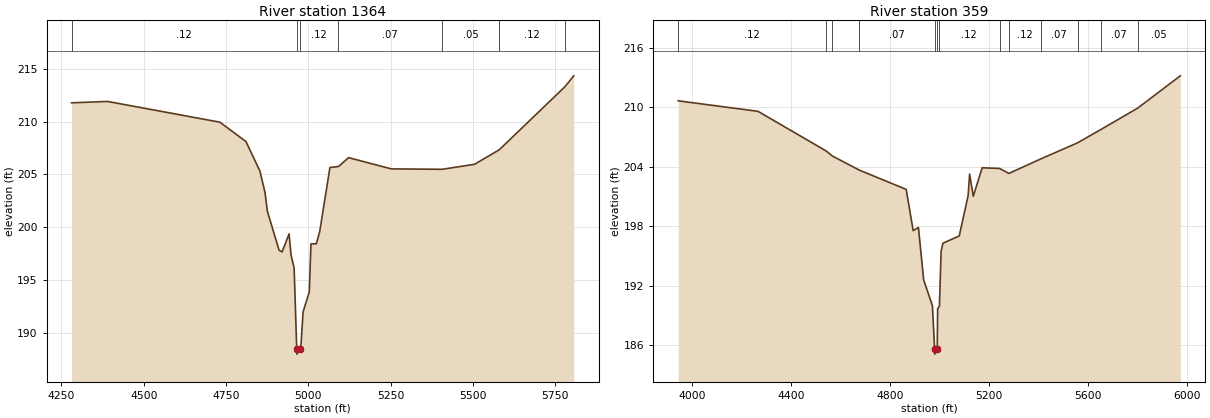
Type RM Length L Ch R = 1 ,1364    ,1005,1005,1005
BEGIN DESCRIPTION:
Mapping XS 947d9422
END DESCRIPTION:
XS GIS Cut Line= 3
      2480270.41      13497819.1      2479666.23     13497444.09
       2478879.9     13497230.59
#Sta/Elev= 30
  4280.9  211.77  4390.1   211.9  4731.5  209.94  4810.6  208.11  4853.1  205.32
  4868.4  203.32  4875.7  201.53  4911.1  197.86  4920.4  197.68  4941.7  199.39
  4947.6   197.4    4957  196.16  4964.9  188.53  4965.4  188.03  4974.9  188.53
  4978.3  189.09  4984.2  192.02    5003  193.89  5008.2  198.45  5024.4  198.45
  5034.7   199.6  5065.8  205.66  5091.7  205.75  5122.5  206.59  5252.3  205.53
  5406.8  205.49    5505  205.96  5580.2  207.33  5779.9  213.29  5806.8  214.32
#Mann= 7 ,-1 , 0
  4280.9     .12       0  4964.9     .05       0  4974.9     .12       0
  5091.7     .07       0  5406.8     .05       0  5580.2     .12       0
  5779.9     .05       0
Bank Sta=4964.9,4974.9
XS Rating Curve= 0 ,0
Exp/Cntr=0.3,0.1

Type RM Length L Ch R = 1 ,359     ,0,0,0
BEGIN DESCRIPTION:
DRY CREEK (GOLIAD) 1.0
END DESCRIPTION:
XS GIS Cut Line= 4
      2480103.72     13497600.33      2479857.42     13496789.94
       2479659.5     13496598.97      2478906.36     13497110.39
#Sta/Elev= 30
  3942.3  210.64  4265.6  209.58  4541.4  205.58  4566.7  205.07  4675.9  203.65
  4865.2  201.71  4893.5  197.55  4914.8  197.87  4935.9  192.59  4971.4  189.98
  4980.2   185.6  4980.7   185.1  4990.8   185.6  4992.5  189.66  4997.6  189.87
  4999.7  189.95  5006.6  195.47  5013.8  196.28  5079.9  197.02  5115.8  201.07
  5121.9  203.25  5136.8  201.02  5172.7  203.89  5243.2  203.82  5280.9  203.32
  5410.6  204.79  5558.6   206.4  5653.5  207.75    5802   209.9  5974.7  213.16
#Mann= 13 ,-1 , 0
  3942.3     .12       0  4541.4     .07       0  4566.7     .12       0
  4675.9     .07       0  4980.2     .05       0  4990.8     .07       0
  4997.6     .12       0  5243.2     .07       0  5280.9     .12       0
  5410.6     .07       0  5558.6     .12       0  5653.5     .07       0
    5802     .05       0
Bank Sta=4980.2,4990.8
XS Rating Curve= 0 ,0
Exp/Cntr=0.3,0.1

Chan Stop Cuts=-1
Use User Specified Reach Order=0
Composite Channel Slope=5