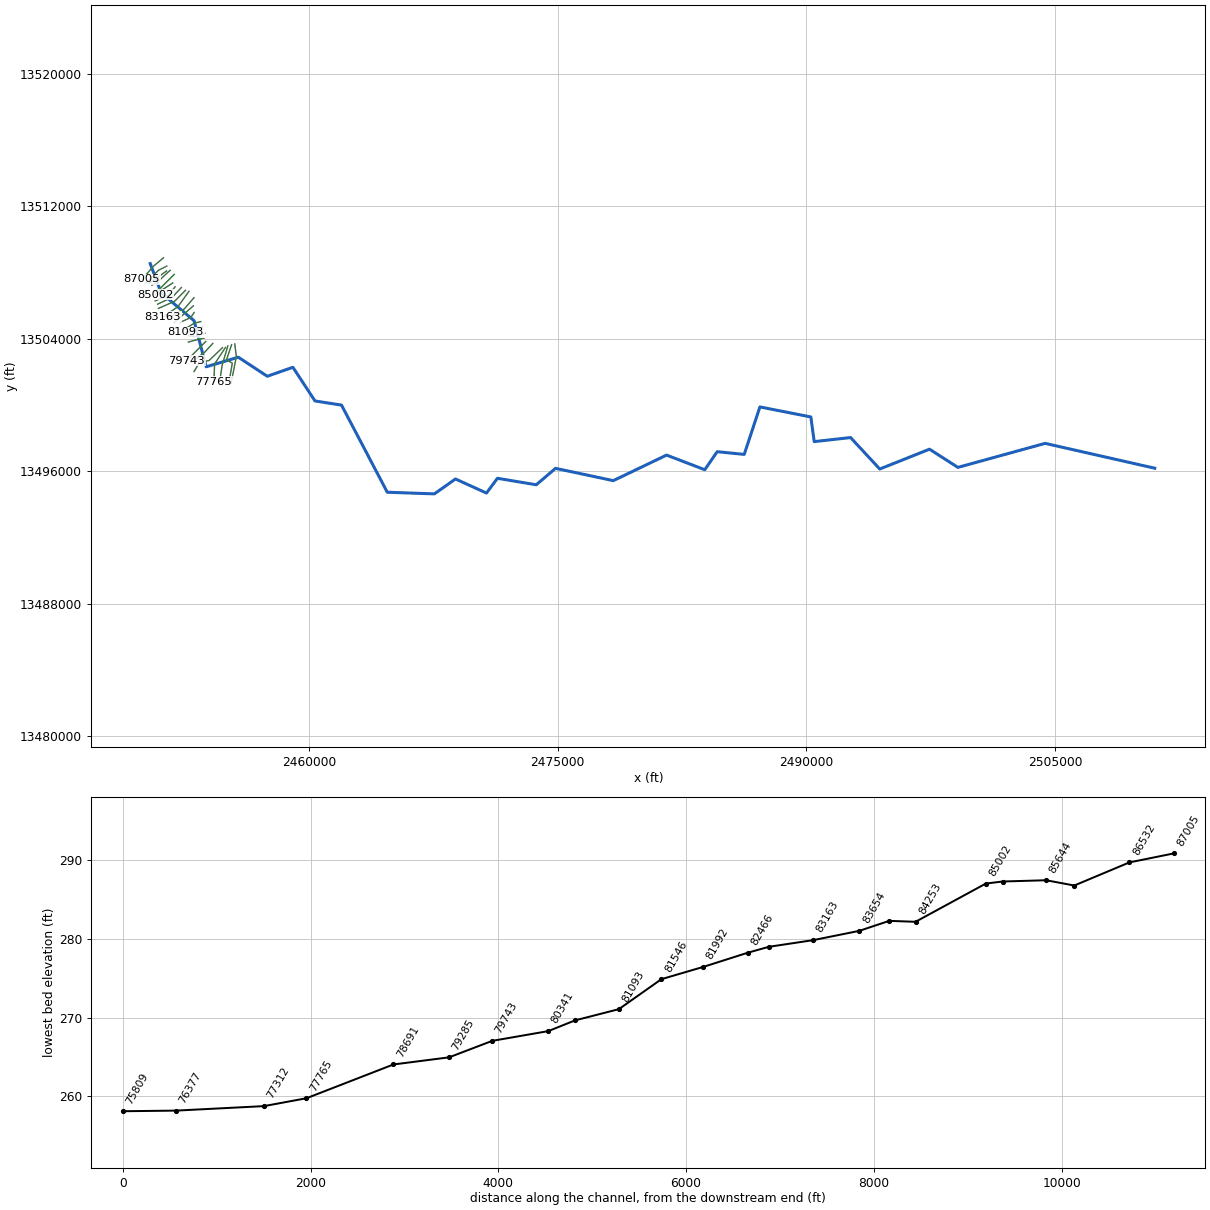
--- EIGHTEENMILE CREEK.prj (project) ---

Proj Title=EIGHTEENMILE CREEK Base Level Engineering
Current Plan=p01
Default Exp/Contr=0.3,0.1
English Units
Geom File=g01
Flow File=f01
Plan File=p01
Y Axis Title=Elevation
X Axis Title(PF)=Main Channel Distance
X Axis Title(XS)=Station
BEGIN DESCRIPTION:
EIGHTEENMILE CREEK
END DESCRIPTION:
DSS Export Rating Curves= 0
DSS Export Rating Curve Sorted= 0
DSS Export Volume Flow Curves= 0
DXF OffsetX= 0
DXF OffsetY= 0
DXF ScaleX= 1
DXF ScaleY= 10

--- EIGHTEENMILE CREEK.p01 (plan) ---

Plan Title=Multiple Run
Short Identifier=Multiple
Geom File=g01
Flow File=f01
Subcritical Flow
K Sum by GR= 0
Std Step Tol= 0.01
Critical Tol= 0.01
Num of Std Step Trials= 20
Max Error Tol= 0.3
Flow Tol Ratio= 0.001
Split Flow NTrial= 30
Split Flow Tol= 0.02
Split Flow Ratio= 0.02
Log Output Level= 0
Friction Slope Method= 1
Unsteady Friction Slope Method= 2
Unsteady Bridges Friction Slope Method= 1
Parabolic Critical Depth
Global Vel Dist=  1 , 1 , 1
Global Log Level= 0
CheckData=True
Encroach Param= -1, 0, 0, 0
BEGIN DESCRIPTION:
Multiple Run
END DESCRIPTION:

--- EIGHTEENMILE CREEK.f01 (steady flow) ---

Flow Title=Multiple
Program Version=4.10
Number of Profiles= 7
Profile Names=10-year,25-year,50-year,1pct_min,100-year,1pct_plu,500-year
River Rch & RM=EIGHTEENMILE CRE,Reach-1         ,87005
    1149    1914    2625    1739    3471    6925    6008
River Rch & RM=EIGHTEENMILE CRE,Reach-1         ,83163
    1260    2106    2893    1919    3830    7641    6647
River Rch & RM=EIGHTEENMILE CRE,Reach-1         ,79743
    1564    2641    3656    2441    4871    9718    8568
River Rch & RM=EIGHTEENMILE CRE,Reach-1         ,78691
    1674    2828    3915    2613    5214   10403    9167
River Rch & RM=EIGHTEENMILE CRE,Reach-1         ,74501
    1776    3005    4164    2782    5551   11076    9776
River Rch & RM=EIGHTEENMILE CRE,Reach-1         ,70701
    2544    4373    6125    4131    8243   16447   14798
River Rch & RM=EIGHTEENMILE CRE,Reach-1         ,68646
    2629    4521    6333    4271    8523   17005   15298
River Rch & RM=EIGHTEENMILE CRE,Reach-1         ,65576
    2732    4701    6588    4444    8867   17693   15923
River Rch & RM=EIGHTEENMILE CRE,Reach-1         ,62710
    3701    6438    9089    6172   12316   24573   22412
River Rch & RM=EIGHTEENMILE CRE,Reach-1         ,59137
    4104    7153   10111    6873   13713   27361   24998
River Rch & RM=EIGHTEENMILE CRE,Reach-1         ,55036
    4188    7299   10316    7011   13988   27911   25490
River Rch & RM=EIGHTEENMILE CRE,Reach-1         ,51153
    4572    7980   11292    7680   15324   30575   27965
River Rch & RM=EIGHTEENMILE CRE,Reach-1         ,47187
    4649    8114   11481    7808   15579   31084   28424
River Rch & RM=EIGHTEENMILE CRE,Reach-1         ,43428
    5771   10108   14342    9776   19506   38920   35737
River Rch & RM=EIGHTEENMILE CRE,Reach-1         ,40630
    6467   11363   16156   11033   22015   43925   40480
River Rch & RM=EIGHTEENMILE CRE,Reach-1         ,38610
    6460   11338   16110   10994   21936   43768   40276
River Rch & RM=EIGHTEENMILE CRE,Reach-1         ,34994
    6466   11332   16084   10964   21876   43649   40075
River Rch & RM=EIGHTEENMILE CRE,Reach-1         ,30840
    6765   11872   16865   11506   22957   45806   42120
River Rch & RM=EIGHTEENMILE CRE,Reach-1         ,29271
    7009   12305   17487   11933   23809   47506   43703
River Rch & RM=EIGHTEENMILE CRE,Reach-1         ,26853
    7199   12643   17971   12265   24472   48828   44932
River Rch & RM=EIGHTEENMILE CRE,Reach-1         ,24290
    7225   12679   18013   12287   24516   48916   44964
River Rch & RM=EIGHTEENMILE CRE,Reach-1         ,21101
    7295   12797   18177   12395   24732   49346   45331
River Rch & RM=EIGHTEENMILE CRE,Reach-1         ,17891
    7346   12881   18290   12468   24877   49637   45566
River Rch & RM=EIGHTEENMILE CRE,Reach-1         ,14589
    7329   12848   18239   12431   24803   49488   45409
River Rch & RM=EIGHTEENMILE CRE,Reach-1         ,13208
    8135   14292   20320   13867   27668   55205   50781
River Rch & RM=EIGHTEENMILE CRE,Reach-1         ,9146
    8317   14615   20783   14185   28302   56470   51957
River Rch & RM=EIGHTEENMILE CRE,Reach-1         ,6393
    8804   15443   21938   14958   29844   59547   54649
River Rch & RM=EIGHTEENMILE CRE,Reach-1         ,3376
    8797   15420   21897   14923   29776   59410   54474
Boundary for River Rch & Prof#=EIGHTEENMILE CRE,Reach-1         , 1
Up Type= 0
Dn Type= 3
Dn Slope=0.00127
Boundary for River Rch & Prof#=EIGHTEENMILE CRE,Reach-1         , 2
Up Type= 0
Dn Type= 3
Dn Slope=0.00127
Boundary for River Rch & Prof#=EIGHTEENMILE CRE,Reach-1         , 3
Up Type= 0
Dn Type= 3
Dn Slope=0.00127
Boundary for River Rch & Prof#=EIGHTEENMILE CRE,Reach-1         , 4
Up Type= 0
Dn Type= 3
Dn Slope=0.00127
Boundary for River Rch & Prof#=EIGHTEENMILE CRE,Reach-1         , 5
Up Type= 0
Dn Type= 3
Dn Slope=0.00127
Boundary for River Rch & Prof#=EIGHTEENMILE CRE,Reach-1         , 6
Up Type= 0
Dn Type= 3
Dn Slope=0.00127
Boundary for River Rch & Prof#=EIGHTEENMILE CRE,Reach-1         , 7
Up Type= 0
Dn Type= 3
Dn Slope=0.00127
DSS Import GetInterval= 0
DSS Import GetPeak= 0
DSS Import FillOption= 0

--- EIGHTEENMILE CREEK.g01 (geometry) ---

Geom Title=Existing Conditions
Program Version=4.10

River Reach=EIGHTEENMILE CRE,Reach-1
Reach XY= 30
        2450425.       13508525.      2451085.47     13506764.46
      2453069.54     13505077.46      2453801.42     13502297.85
      2455740.18     13502875.43      2457485.47     13501725.93
      2459031.35     13502267.58       2460365.2     13500235.48
      2461964.53     13499984.82        2464725.       13494725.
      2467564.32     13494625.75      2468840.18     13495525.44
       2470709.8      13494675.5      2471371.66     13495567.01
      2473714.56     13495176.05      2474874.91     13496167.65
       2478359.6     13495425.09        2481575.     13496967.44
       2483878.3     13496083.08      2484626.28     13497171.63
      2486258.36     13497008.29      2487204.85     13499875.36
      2490277.59     13499269.29      2490480.44     13497780.19
        2492675.       13498025.       2494435.5     13496126.22
       2497435.5     13497323.78      2499150.08      13496224.8
      2504409.81     13497675.44        2511025.       13496175.

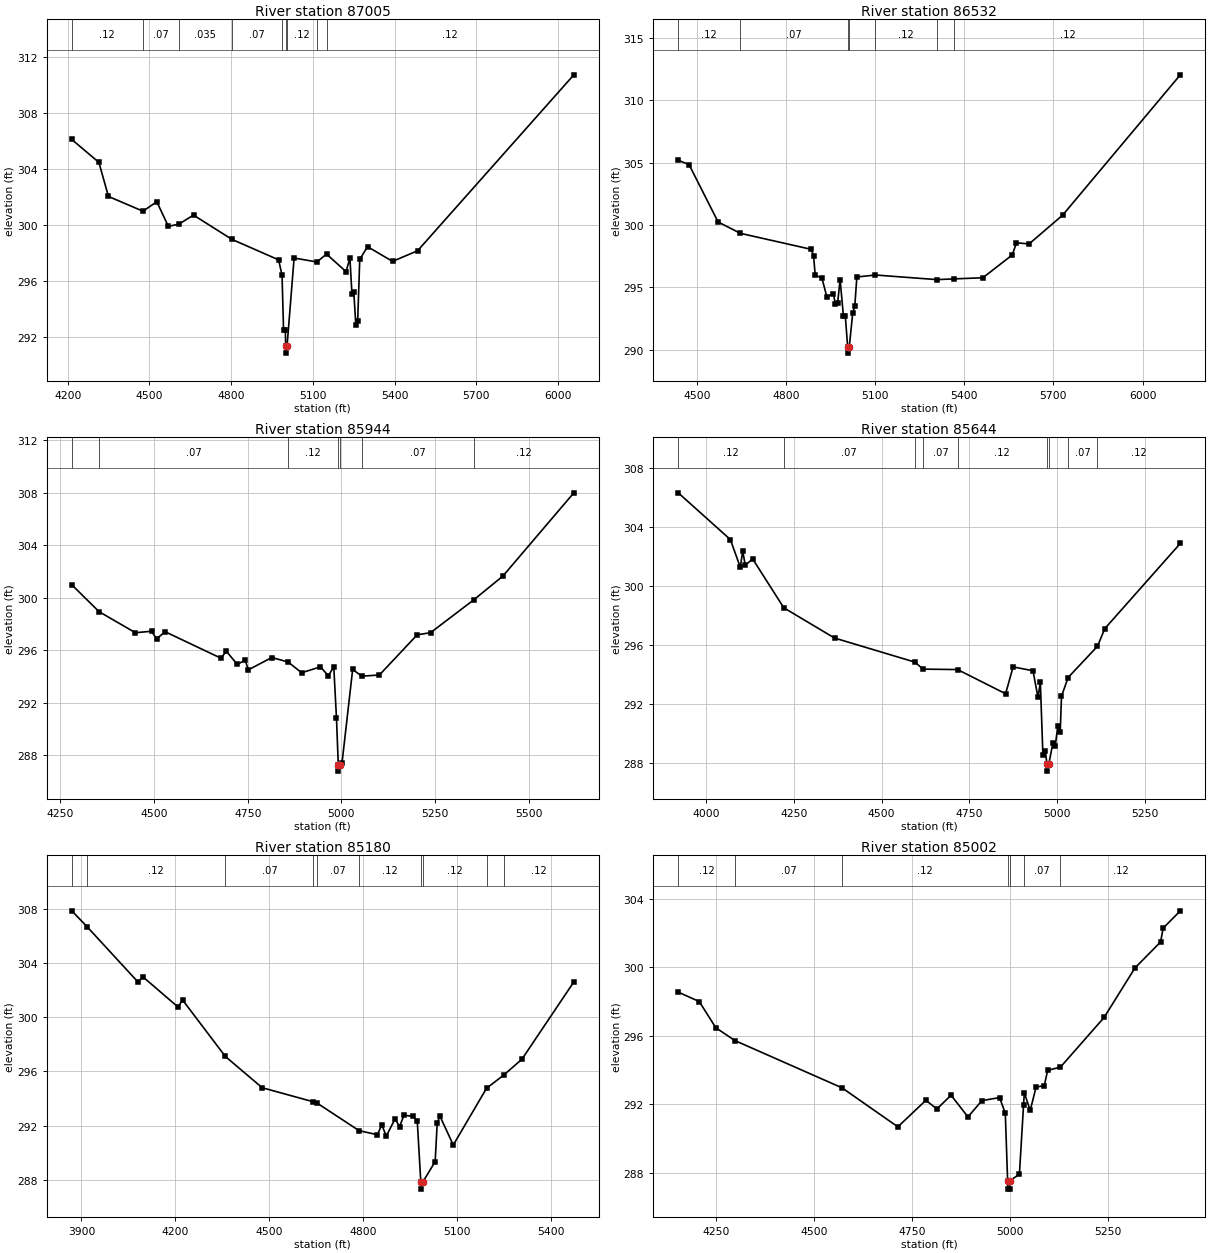
Type RM Length L Ch R = 1 ,87005   ,473,473,473
BEGIN DESCRIPTION:
EIGHTEENMILE CREEK 147.0
END DESCRIPTION:
XS GIS Cut Line= 3
      2451225.01     13508875.01        2450625.       13508375.
      2449924.97     13507574.97
#Sta/Elev= 30
  4214.6   306.1  4314.2  304.47  4349.3  302.04  4475.9  300.99    4527  301.66
  4569.3  299.91  4607.2  300.06  4661.8  300.71  4802.8  298.98  4974.2  297.52
  4986.9  296.43  4992.4  292.55    4999  292.55  5000.2  291.37  5000.6  290.87
  5005.3  291.37  5031.2  297.65    5115  297.37  5150.3  297.93    5222  296.68
  5236.2  297.64  5243.8  295.05  5250.5   295.2  5258.1  292.84  5264.7  293.13
  5272.3  297.55  5300.8  298.46  5392.8  297.41  5484.9  298.17  6058.7  310.71
#Mann= 9 ,-1 , 0
  4214.6     .12       0  4475.9     .07       0  4607.2    .035       0
  4802.8     .07       0  4986.9     .12       0  5000.2     .05       0
  5005.3     .12       0    5115     .07       0  5150.3     .12       0
Bank Sta=5000.2,5005.3
XS Rating Curve= 0 ,0
Exp/Cntr=0.3,0.1

Type RM Length L Ch R = 1 ,86532   ,588,588,588
BEGIN DESCRIPTION:
EIGHTEENMILE CREEK 146.0
END DESCRIPTION:
XS GIS Cut Line= 3
        2451425.       13508375.        2450925.       13508125.
      2450124.99     13507324.99
#Sta/Elev= 30
  4436.9  305.18  4473.2  304.84  4571.1  300.24  4646.1  299.33  4884.1  298.05
  4892.5  297.55  4898.1  295.96  4920.4  295.76  4937.2  294.25  4959.6   294.5
  4965.2   293.7  4973.6  293.77  4981.9  295.61  4993.1   292.7  4999.4   292.7
  5007.3  290.23  5007.8  289.73  5012.8  290.23  5024.2  292.91  5031.3   293.5
  5038.3  295.83  5100.7  295.99  5307.8  295.62  5366.9  295.68  5462.6  295.77
  5561.6   297.6  5575.7  298.57  5618.2  298.48  5731.3  300.79  6127.3  312.03
#Mann= 7 ,-1 , 0
  4436.9     .12       0  4646.1     .07       0  5007.3     .05       0
  5012.8     .07       0  5100.7     .12       0  5307.8     .07       0
  5366.9     .12       0
Bank Sta=5007.3,5012.8
XS Rating Curve= 0 ,0
Exp/Cntr=0.3,0.1

Type RM Length L Ch R = 1 ,85944   ,300,300,300
BEGIN DESCRIPTION:
Mapping XS aef943da
END DESCRIPTION:
XS GIS Cut Line= 3
      2451407.57     13508079.64      2450825.94     13507658.61
      2450318.16     13507298.39
#Sta/Elev= 30
  4280.1  300.98    4353  298.93    4450  297.33  4493.1  297.44  4506.4  296.87
  4529.7   297.4  4678.3  295.39  4692.8  295.92  4722.2  294.91  4743.1  295.25
  4751.6   294.5  4814.2  295.44  4857.7   295.1  4893.9  294.28  4944.2  294.73
    4965  294.05  4979.7  294.72  4986.9  290.82  4991.7  287.29  4992.1  286.79
  4997.2  287.29  5001.8  287.44  5030.1  294.53  5054.8  294.02  5101.5  294.11
  5202.4  297.17    5238  297.33  5353.4  299.83  5431.2  301.64  5620.7  307.98
#Mann= 7 ,-1 , 0
  4280.1     .12       0    4353     .07       0  4857.7     .12       0
  4991.7     .05       0  4997.2     .12       0  5054.8     .07       0
  5353.4     .12       0
Bank Sta=4991.7,4997.2
XS Rating Curve= 0 ,0
Exp/Cntr=0.3,0.1

Type RM Length L Ch R = 1 ,85644   ,464,464,464
BEGIN DESCRIPTION:
EIGHTEENMILE CREEK 144.0
END DESCRIPTION:
XS GIS Cut Line= 3
      2451624.98     13508124.98        2450825.       13507375.
      2450524.97     13507224.98
#Sta/Elev= 30
  3920.1  306.34  4068.8  303.17  4097.1  301.29    4104  302.39  4111.3  301.42
  4132.3  301.86  4221.2  298.54  4365.8  296.49  4594.4  294.86  4618.8  294.38
  4716.8  294.35  4853.8  292.71  4875.2  294.53  4931.9  294.27  4946.1  292.47
  4952.9  293.48  4960.2  288.54  4967.1  288.83  4971.6  287.96    4972  287.46
  4977.2  287.96  4988.6  289.36  4995.4  289.15  5002.7  290.54  5009.6   290.1
  5013.2  292.54  5032.1  293.81  5115.8  295.93  5136.8  297.13  5352.1  302.91
#Mann= 9 ,-1 , 0
  3920.1     .12       0  4221.2     .07       0  4594.4     .12       0
  4618.8     .07       0  4716.8     .12       0  4971.6     .05       0
  4977.2     .12       0  5032.1     .07       0  5115.8     .12       0
Bank Sta=4971.6,4977.2
XS Rating Curve= 0 ,0
Exp/Cntr=0.3,0.1

Type RM Length L Ch R = 1 ,85180   ,178,178,178
BEGIN DESCRIPTION:
EIGHTEENMILE CREEK 143.0
END DESCRIPTION:
XS GIS Cut Line= 3
      2451875.02     13507875.02        2451075.       13507075.
        2450675.       13506825.
#Sta/Elev= 30
  3869.2  307.86  3917.5   306.7  4081.4  302.58  4095.5     303  4208.6  300.75
  4222.8  301.28  4359.6   297.1  4477.3  294.79  4640.9  293.75  4651.6  293.67
  4786.5  291.62    4845  291.32  4859.2  292.06  4873.3  291.21  4901.6   292.5
  4915.7  291.91  4929.9  292.76  4958.2  292.68  4972.3  292.35  4983.7   287.8
  4984.1   287.3  4989.3   287.8  5029.5  289.33    5036  292.18  5044.8  292.69
  5087.3  290.56  5193.5  294.75  5248.7  295.73  5306.6   296.9  5472.3  302.61
#Mann= 10 ,-1 , 0
  3869.2     .07       0  3917.5     .12       0  4359.6     .07       0
  4640.9     .12       0  4651.6     .07       0  4786.5     .12       0
  4983.7     .05       0  4989.3     .12       0  5193.5     .07       0
  5248.7     .12       0
Bank Sta=4983.7,4989.3
XS Rating Curve= 0 ,0
Exp/Cntr=0.3,0.1

Type RM Length L Ch R = 1 ,85002   ,749,749,749
BEGIN DESCRIPTION:
Mapping XS 7c6bfa75
END DESCRIPTION:
XS GIS Cut Line= 3
      2451785.16     13507359.15      2451077.67     13506899.06
      2450713.09     13506656.01
#Sta/Elev= 30
  4152.8  298.55  4206.5     298  4248.7  296.47  4297.5  295.72  4570.9  292.96
  4713.6  290.68  4785.2  292.23  4813.3  291.72  4849.5  292.53  4892.6  291.26
  4928.3  292.21  4973.4  292.39    4988  291.47  4993.9  287.54  4994.4  287.04
  4999.1  287.04  4999.5  287.54    5024   287.9  5034.7  291.98  5036.5  292.67
  5051.6  291.64  5066.6     293  5087.6  293.09  5096.1  293.98  5128.9  294.17
  5240.3  297.07    5319  299.96  5384.5  301.48  5391.1  302.29  5434.9   303.3
#Mann= 7 ,-1 , 0
  4152.8     .12       0  4297.5     .07       0  4570.9     .12       0
  4993.9     .05       0  4999.5     .12       0  5034.7     .07       0
  5128.9     .12       0
Bank Sta=4993.9,4999.5
XS Rating Curve= 0 ,0
Exp/Cntr=0.3,0.1

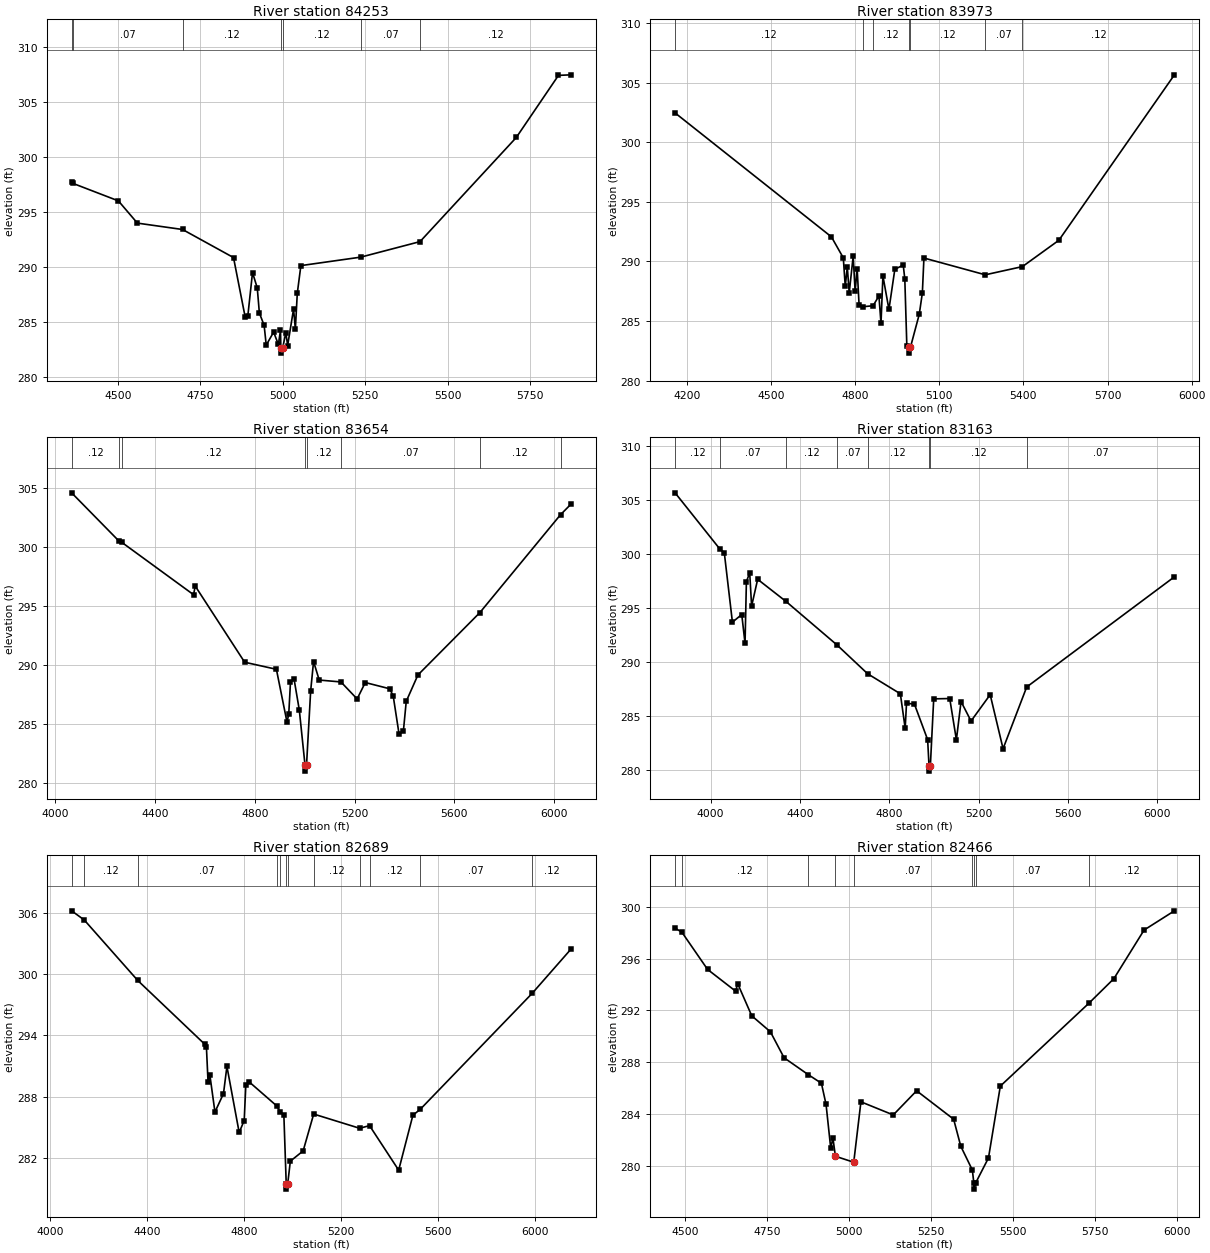
Type RM Length L Ch R = 1 ,84253   ,280,280,280
BEGIN DESCRIPTION:
EIGHTEENMILE CREEK 141.0
END DESCRIPTION:
XS GIS Cut Line= 3
      2451925.02     13507125.03        2451525.       13506625.
      2450724.96     13506274.98
#Sta/Elev= 30
  4359.6  297.69  4364.3  297.59  4501.3  296.01  4558.9  293.99  4695.8  293.41
  4850.3  290.86  4885.5  285.48  4893.5  285.51  4907.9   289.5  4922.3   288.1
  4928.7  285.82  4943.1  284.71  4949.5  282.91  4971.9  284.09  4986.3  282.97
  4992.7  284.25  4993.8  282.68  4994.3  282.18  4999.6  282.68  5008.9  284.05
  5014.4  282.87  5032.3  286.18  5037.8  284.37  5043.6  287.61  5054.5  290.13
  5236.1   290.9  5415.7  292.31  5707.5  301.77  5835.3  307.41  5873.2  307.46
#Mann= 7 ,-1 , 0
  4359.6     .12       0  4364.3     .07       0  4695.8     .12       0
  4993.8     .05       0  4999.6     .12       0  5236.1     .07       0
  5415.7     .12       0
Bank Sta=4993.8,4999.6
XS Rating Curve= 0 ,0
Exp/Cntr=0.3,0.1

Type RM Length L Ch R = 1 ,83973   ,319,319,319
BEGIN DESCRIPTION:
Mapping XS 5c5fe6da
END DESCRIPTION:
XS GIS Cut Line= 3
      2452304.79     13507083.05       2451752.7      13506494.5
      2450872.51     13506077.84
#Sta/Elev= 30
  4157.7  302.48  4715.2  292.07  4757.7   290.3  4764.6  287.91  4771.9  289.54
  4778.7  287.36  4792.9  290.45  4799.8  287.49  4807.1  289.38  4813.9  286.36
  4827.9   286.2  4863.8  286.28  4884.7   287.1  4892.1   284.8  4898.9  288.79
  4920.4  285.97  4941.4  289.34  4971.4   289.7    4977  288.53  4984.3  282.86
  4991.2   282.8  4991.7   282.3  4997.2   282.8  5028.5  285.56  5039.6  287.36
  5045.2  290.29    5264  288.88  5396.5  289.57  5526.4  291.78  5938.5  305.68
#Mann= 7 ,-1 , 0
  4157.7     .12       0  4827.9     .07       0  4863.8     .12       0
  4991.2     .05       0  4997.2     .12       0    5264     .07       0
  5396.5     .12       0
Bank Sta=4991.2,4997.2
XS Rating Curve= 0 ,0
Exp/Cntr=0.3,0.1

Type RM Length L Ch R = 1 ,83654   ,491,491,491
BEGIN DESCRIPTION:
Mapping XS ca634915
END DESCRIPTION:
XS GIS Cut Line= 3
       2452554.8     13506916.39      2451893.33     13506249.71
      2450919.67     13505822.76
#Sta/Elev= 30
    4065  304.59  4255.6  300.49    4266   300.4  4553.7  295.97  4560.8  296.69
  4758.8  290.25  4886.1  289.65  4928.5  285.19  4935.6  285.84  4942.6  288.57
  4956.8  288.84    4978   286.2  5000.9  281.53  5001.4  281.03  5006.9  281.53
  5023.5  287.82  5035.1  290.31  5057.8  288.74  5144.9  288.58  5209.8  287.14
  5242.5  288.53  5340.8     288  5354.6  287.38    5378  284.16  5395.4  284.44
  5406.8  286.94  5453.6  289.17    5702  294.45  6025.5  302.74  6067.3  303.63
#Mann= 8 ,-1 , 0
    4065     .12       0  4255.6     .07       0    4266     .12       0
  5000.9     .05       0  5006.9     .12       0  5144.9     .07       0
    5702     .12       0  6025.5     .07       0
Bank Sta=5000.9,5006.9
XS Rating Curve= 0 ,0
Exp/Cntr=0.3,0.1

Type RM Length L Ch R = 1 ,83163   ,474,474,474
BEGIN DESCRIPTION:
Mapping XS 27216d29
END DESCRIPTION:
XS GIS Cut Line= 3
      2452763.12     13506853.87      2452096.45     13505926.79
      2451195.43     13505307.01
#Sta/Elev= 30
  3841.2  305.69  4041.7  300.47  4061.5  300.14  4097.9  293.68  4139.7  294.39
  4154.4  291.71  4160.5  297.44  4175.3  298.27  4183.8  295.17  4210.9  297.66
  4338.1   295.6  4566.3  291.56  4703.3  288.89  4849.8  287.03  4871.3  283.83
  4877.4  286.16    4913  286.06  4971.9  282.77  4978.1  280.35  4978.6  279.85
  4984.1  280.35  4999.1  286.56  5070.8  286.59  5100.6  282.76  5121.5  286.31
  5166.2   284.5  5251.9  286.95  5309.6  281.93  5415.4  287.66  6076.7  297.89
#Mann= 8 ,-1 , 0
  3841.2     .12       0  4041.7     .07       0  4338.1     .12       0
  4566.3     .07       0  4703.3     .12       0  4978.1     .05       0
  4984.1     .12       0  5415.4     .07       0
Bank Sta=4978.1,4984.1
XS Rating Curve= 0 ,0
Exp/Cntr=0.3,0.1

Type RM Length L Ch R = 1 ,82689   ,223,223,223
BEGIN DESCRIPTION:
Mapping XS 4e534ab2
END DESCRIPTION:
XS GIS Cut Line= 3
      2453065.19     13506468.45      2452481.87     13505791.38
      2451478.35     13505198.63
#Sta/Elev= 30
  4089.7  306.17  4141.6  305.28  4362.4  299.37    4638  293.16  4645.6  292.84
  4652.2  289.49  4659.9  290.12  4680.7  286.53  4715.9  288.32  4730.1  290.98
  4780.6  284.53  4801.4   285.7    4808  289.14  4822.3  289.46  4934.8  287.14
    4950  286.54  4964.9  286.25  4974.7   279.5  4975.2     279  4980.7   279.5
  4991.6  281.73  5044.4  282.73  5087.9  286.33  5277.5  284.94  5318.2   285.2
  5438.4  280.85    5497  286.21  5527.7   286.8  5988.8  298.11  6148.9  302.43
#Mann= 12 ,-1 , 0
  4089.7     .07       0  4141.6     .12       0  4362.4     .07       0
  4934.8     .12       0    4950     .07       0  4974.7     .05       0
  4980.7     .07       0  5087.9     .12       0  5277.5     .07       0
  5318.2     .12       0  5527.7     .07       0  5988.8     .12       0
Bank Sta=4974.7,4980.7
XS Rating Curve= 0 ,0
Exp/Cntr=0.3,0.1

Type RM Length L Ch R = 1 ,82466   ,474,474,474
BEGIN DESCRIPTION:
EIGHTEENMILE CREEK 137.0
END DESCRIPTION:
XS GIS Cut Line= 3
      2453025.03     13505975.03        2452625.       13505625.
      2451875.01     13504975.01
#Sta/Elev= 30
  4468.5  298.34  4489.4  298.02  4567.7  295.16  4653.1  293.49  4659.8  294.05
  4702.5  291.59  4759.4  290.36  4801.2  288.36    4875  287.06  4915.1   286.4
  4929.3  284.77  4943.6  281.39  4950.2   282.2  4957.8  280.78  5013.8  280.32
  5035.7  284.97  5134.4  283.96  5205.7  285.82  5318.7  283.63  5340.5  281.55
  5375.8  279.72  5380.2  278.75  5380.7  278.25  5386.4  278.75    5425  280.65
  5461.2  286.18  5731.6  292.56  5807.8  294.45  5899.9  298.19  5992.5  299.67
#Mann= 9 ,-1 , 0
  4468.5     .07       0  4489.4     .12       0    4875     .07       0
  4957.8     .05       0  5013.8     .07       0  5375.8     .07       0
  5380.2     .07       0  5386.4     .07       0  5731.6     .12       0
Bank Sta=4957.8,5013.8
XS Rating Curve= 0 ,0
Exp/Cntr=0.3,0.1

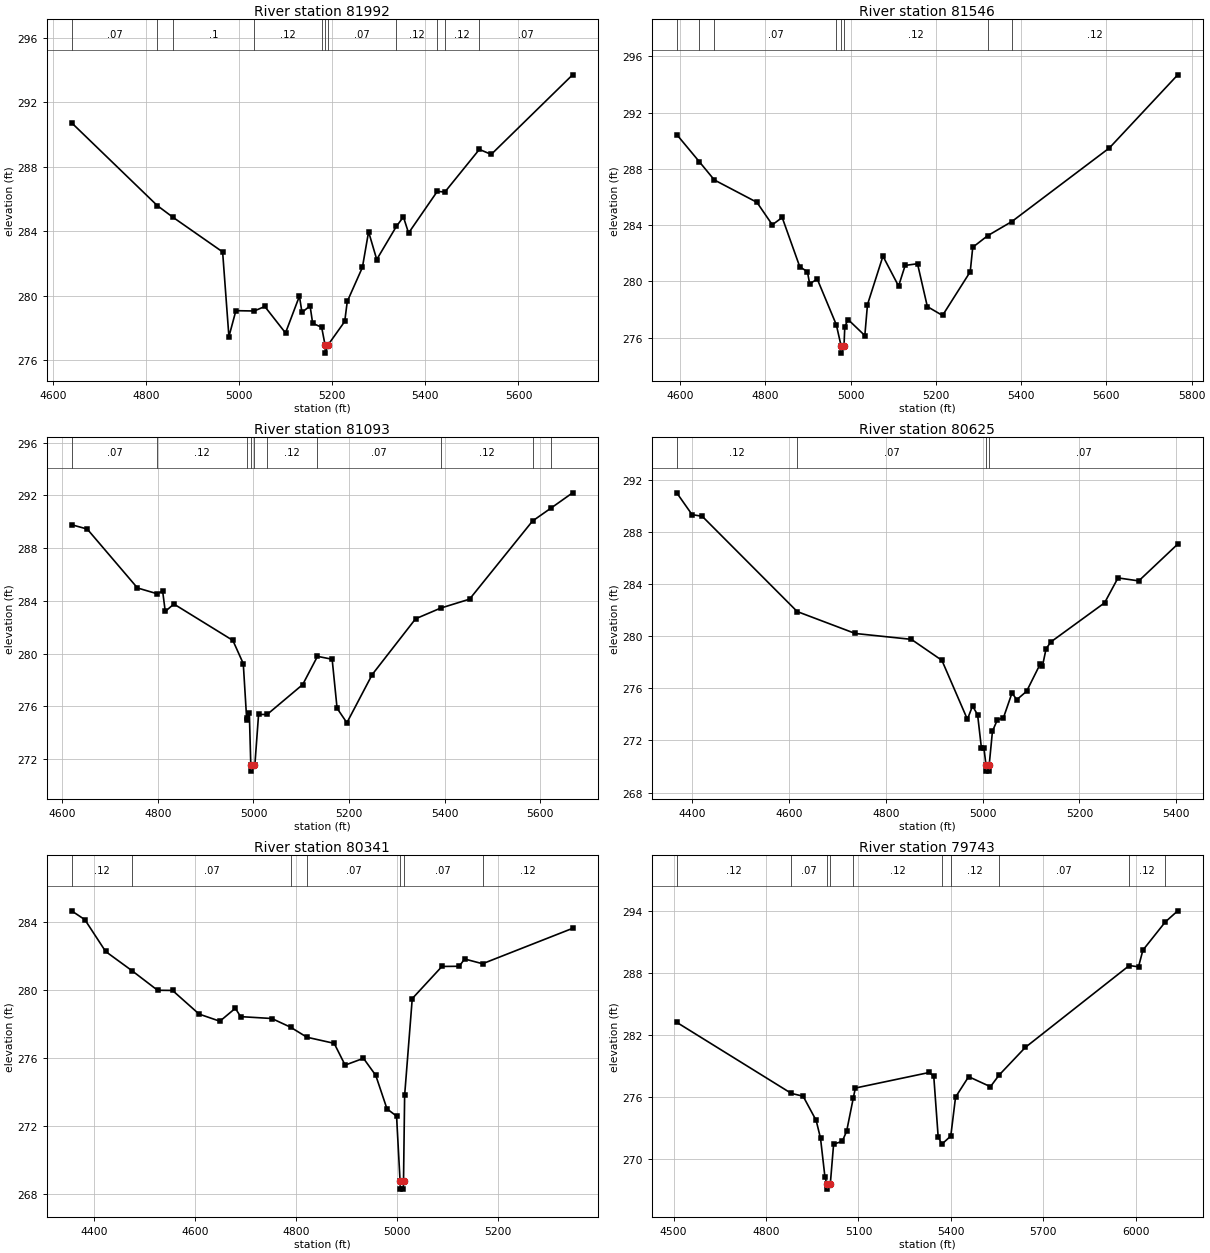
Type RM Length L Ch R = 1 ,81992   ,446,446,446
BEGIN DESCRIPTION:
EIGHTEENMILE CREEK 136.0
END DESCRIPTION:
XS GIS Cut Line= 3
      2453074.98     13505574.96        2452875.       13505275.
        2452225.       13504975.
#Sta/Elev= 30
  4639.9  290.72    4824  285.59    4857  284.88  4964.4  282.72  4977.9  277.47
  4992.9  279.08  5032.3  279.06    5055  279.34  5099.5   277.7  5129.4  279.98
  5134.9  278.97  5152.3  279.38  5157.8   278.3  5177.2  278.05  5184.5  276.95
    5185  276.45  5190.7  276.95  5226.7  278.41  5232.2  279.65  5264.7  281.76
    5278  283.97  5295.5  282.25  5337.7   284.3  5352.8  284.89  5363.9  283.89
  5425.6  286.47  5441.9  286.43    5516  289.07  5541.5  288.76  5716.3  293.69
#Mann= 11 ,-1 , 0
  4639.9     .07       0    4824     .05       0    4857      .1       0
  5032.3     .12       0  5177.2     .07       0  5184.5     .05       0
  5190.7     .07       0  5337.7     .12       0  5425.6     .07       0
  5441.9     .12       0    5516     .07       0
Bank Sta=5184.5,5190.7
XS Rating Curve= 0 ,0
Exp/Cntr=0.3,0.1

Type RM Length L Ch R = 1 ,81546   ,453,453,453
BEGIN DESCRIPTION:
EIGHTEENMILE CREEK 135.0
END DESCRIPTION:
XS GIS Cut Line= 3
      2453474.98     13505024.99        2453075.       13504925.
      2452425.01       13504525.
#Sta/Elev= 30
  4591.9  290.44  4644.8  288.51  4680.1  287.21    4780  285.62  4816.1  284.02
  4839.3  284.54  4880.5  281.04  4898.5  280.68  4903.7  279.83  4921.7  280.15
  4966.3  276.91  4977.6  275.39  4978.1  274.89  4984.3  275.39  4986.2  276.77
  4993.9  277.28  5033.2  276.14  5039.4  278.34  5075.7  281.79  5112.4  279.66
  5127.8  281.13  5156.8  281.25  5179.9   278.2  5215.5  277.57  5280.5  280.68
  5286.4  282.42  5321.2  283.24  5378.1  284.25  5607.1  289.49  5767.4  294.69
#Mann= 8 ,-1 , 0
  4591.9     .07       0  4644.8     .05       0  4680.1     .07       0
  4966.3     .12       0  4977.6     .05       0  4984.3     .12       0
  5321.2     .07       0  5378.1     .12       0
Bank Sta=4977.6,4984.3
XS Rating Curve= 0 ,0
Exp/Cntr=0.3,0.1

Type RM Length L Ch R = 1 ,81093   ,468,468,468
BEGIN DESCRIPTION:
EIGHTEENMILE CREEK 134.0
END DESCRIPTION:
XS GIS Cut Line= 3
      2453575.03     13504675.01        2453225.       13504525.
        2452575.       13504375.
#Sta/Elev= 30
  4619.6  289.78  4652.3  289.45  4757.4  284.98  4798.7  284.54    4810  284.75
  4815.5   283.2  4833.6  283.76  4956.9     281  4978.7  279.24  4985.9  274.97
  4987.2  275.09  4991.4  275.46  4994.4  271.58  4994.9  271.08  5001.1  271.58
    5003  271.58  5010.7  275.38  5028.6  275.38    5103  277.65  5133.9  279.79
  5164.6  279.57  5174.9  275.85  5195.4  274.75  5248.4  278.41  5339.1  282.64
  5391.4  283.45    5452  284.13  5583.7  290.06  5622.7  291.05  5667.5   292.2
#Mann= 10 ,-1 , 0
  4619.6     .07       0  4798.7     .12       0  4987.2     .07       0
  4994.4     .05       0  5001.1     .07       0  5028.6     .12       0
  5133.9     .07       0  5391.4     .12       0  5583.7     .07       0
  5622.7     .12       0
Bank Sta=4994.4,5001.1
XS Rating Curve= 0 ,0
Exp/Cntr=0.3,0.1

Type RM Length L Ch R = 1 ,80625   ,284,284,284
BEGIN DESCRIPTION:
EIGHTEENMILE CREEK 133.0
END DESCRIPTION:
XS GIS Cut Line= 3
      2453725.01       13504325.        2453125.       13504125.
      2452724.98       13504175.
#Sta/Elev= 30
  4367.5  290.98  4399.1  289.31  4420.2  289.18  4616.5  281.88  4736.4   280.2
  4852.4  279.75  4915.6  278.14  4968.3  273.62  4978.9  274.64  4989.4  273.97
  4997.3  271.41  5002.5  271.41  5006.6  270.15  5007.1  269.65  5012.9  269.65
  5013.4  270.15  5020.1  272.71  5030.2  273.58  5042.8  273.74  5060.4  275.63
  5070.5  275.13  5090.7  275.77  5118.4  277.83  5123.4  277.69    5131  279.04
  5141.1  279.56  5251.9  282.55  5279.6  284.46  5322.5  284.23  5403.1  287.05
#Mann= 4 ,-1 , 0
  4367.5     .12       0  4616.5     .07       0  5006.6     .05       0
  5013.4     .07       0
Bank Sta=5006.6,5013.4
XS Rating Curve= 0 ,0
Exp/Cntr=0.3,0.1

Type RM Length L Ch R = 1 ,80341   ,598,598,598
BEGIN DESCRIPTION:
Mapping XS a8c47384
END DESCRIPTION:
XS GIS Cut Line= 3
       2453690.5     13504038.81       2453074.2     13503886.91
      2452728.48     13503791.83
#Sta/Elev= 30
  4354.6  284.65  4380.9  284.13  4422.1  282.26  4474.8  281.12  4525.1  279.98
  4554.7  279.97  4607.4  278.58  4648.6  278.16  4679.2  278.92  4689.8  278.43
  4751.6  278.32  4788.7  277.81  4821.1  277.22  4875.2  276.86  4896.9  275.58
  4933.3  275.98  4957.6  274.98  4979.9  273.01  4998.9  272.58  5005.8  268.79
  5006.3  268.29  5012.2  268.29  5012.7  268.79  5014.9   273.8    5030  279.49
  5088.9  281.38  5123.3  281.39  5133.7  281.82  5169.4  281.54  5347.9  283.62
#Mann= 7 ,-1 , 0
  4354.6     .12       0  4474.8     .07       0  4788.7     .12       0
  4821.1     .07       0  5005.8     .05       0  5012.7     .07       0
  5169.4     .12       0
Bank Sta=5005.8,5012.7
XS Rating Curve= 0 ,0
Exp/Cntr=0.3,0.1

Type RM Length L Ch R = 1 ,79743   ,458,458,458
BEGIN DESCRIPTION:
EIGHTEENMILE CREEK 131.0
END DESCRIPTION:
XS GIS Cut Line= 3
      2453775.03     13503825.03        2453425.       13503475.
      2452624.99     13502674.99
#Sta/Elev= 30
    4510   283.2    4882  276.32  4920.2  276.05  4962.6   273.7  4976.7  271.98
  4990.9  268.27  4997.1  267.55  4997.6  267.05  5005.9  267.55  5008.5  267.55
  5019.2   271.4  5047.4  271.68  5061.6  272.67  5083.1  275.87  5089.9  276.84
  5330.3  278.35  5344.4  277.96  5358.6  272.14  5370.4   271.4  5399.6  272.19
  5415.1  275.96  5457.6  277.94  5528.3  276.97  5556.6   278.1  5641.4  280.77
    5979   288.7  6009.1  288.58  6023.2  290.19  6096.2  292.93  6136.4     294
#Mann= 10 ,-1 , 0
    4510     .12       0    4882     .07       0  4997.1     .05       0
  5005.9     .07       0  5083.1     .12       0  5370.4      .1       0
  5399.6     .12       0  5556.6     .07       0    5979     .12       0
  6096.2     .07       0
Bank Sta=4997.1,5005.9
XS Rating Curve= 0 ,0
Exp/Cntr=0.3,0.1

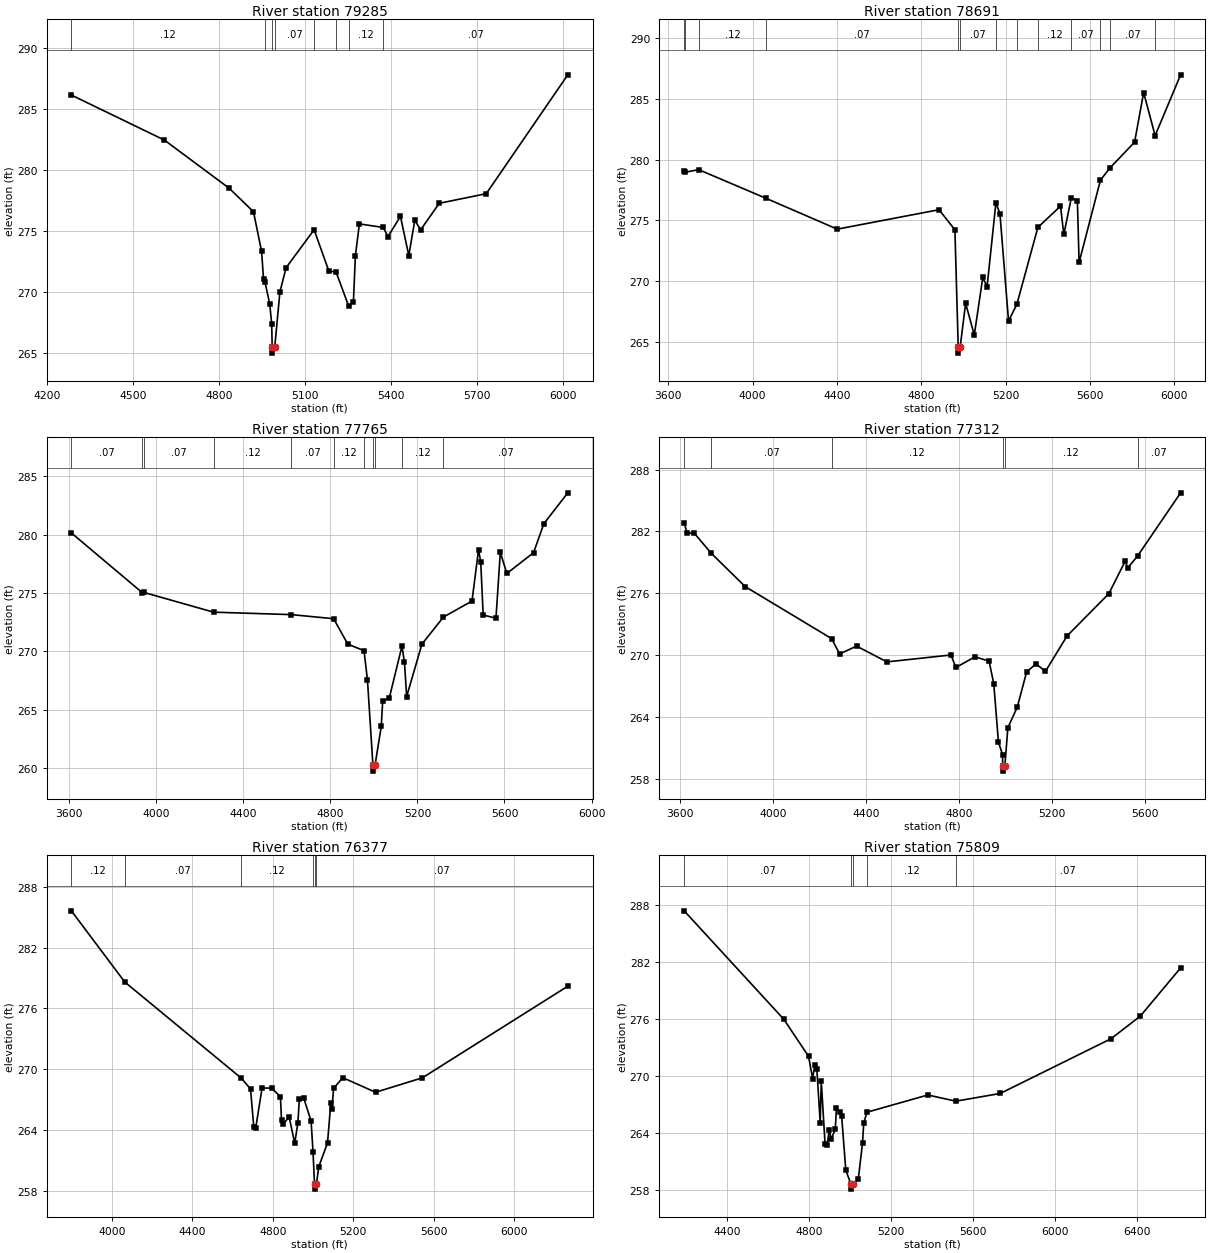
Type RM Length L Ch R = 1 ,79285   ,594,594,594
BEGIN DESCRIPTION:
Mapping XS a93208ce
END DESCRIPTION:
XS GIS Cut Line= 3
      2454200.65     13503708.07      2453721.45     13503187.21
      2452903.75     13502567.43
#Sta/Elev= 30
  4284.6  286.13  4609.3  282.44  4835.6  278.49  4920.6  276.56    4949   273.3
  4955.8  271.02  4960.8  270.79  4977.4  268.99  4984.2  267.38    4986  265.46
  4986.5  264.96  4994.9  265.46    5013  269.99  5034.6  271.97  5132.4  275.08
  5184.4  271.66  5208.5  271.65  5253.1  268.82  5269.7  269.17  5276.5  272.94
  5290.5  275.56  5373.9  275.27  5390.4  274.52    5434  276.18  5463.1  272.96
    5484  275.85  5504.8  275.08  5569.3  277.25  5733.6  278.04  6018.4  287.79
#Mann= 8 ,-1 , 0
  4284.6     .12       0  4960.8     .07       0    4986     .05       0
  4994.9     .07       0  5132.4     .12       0  5208.5      .1       0
  5253.1     .12       0  5373.9     .07       0
Bank Sta=4986,4994.9
XS Rating Curve= 0 ,0
Exp/Cntr=0.3,0.1

Type RM Length L Ch R = 1 ,78691   ,926,926,926
BEGIN DESCRIPTION:
Mapping XS bf02b964
END DESCRIPTION:
XS GIS Cut Line= 4
      2454783.92      13503452.8      2453976.66     13502676.79
      2453398.54     13502567.42      2453070.39     13502010.09
#Sta/Elev= 30
  3675.3  279.09  3681.1  278.97  3744.6  279.17  4065.2   276.8  4401.4  274.27
  4884.3  275.87  4959.6  274.22  4975.3  264.55  4975.8  264.05  4984.5  264.55
  5010.5  268.16  5051.5  265.54  5091.9  270.29  5112.2  269.51  5154.1  276.44
  5173.3  275.54    5214   266.7  5253.6  268.08  5353.1  274.41  5460.5  276.17
  5476.2  273.83  5511.9  276.86  5540.6  276.63  5548.7  271.53  5650.1  278.31
  5693.2  279.28    5812  281.44  5854.9  285.53  5909.4  281.98  6030.2  286.99
#Mann= 13 ,-1 , 0
  3675.3     .12       0  3681.1     .07       0  3744.6     .12       0
  4065.2     .07       0  4975.3     .05       0  4984.5     .07       0
  5154.1     .12       0  5253.6     .07       0  5353.1     .12       0
  5511.9     .07       0  5650.1     .12       0  5693.2     .07       0
  5909.4     .05       0
Bank Sta=4975.3,4984.5
XS Rating Curve= 0 ,0
Exp/Cntr=0.3,0.1

Type RM Length L Ch R = 1 ,77765   ,453,453,453
BEGIN DESCRIPTION:
Mapping XS 6f730117
END DESCRIPTION:
XS GIS Cut Line= 3
      2454966.26     13503468.49      2454309.99     13502473.67
      2454263.12     13501385.16
#Sta/Elev= 30
  3609.6  280.14  3935.3  275.03  3942.5  275.05  4263.1  273.36  4620.5  273.15
  4814.8   272.8  4880.1  270.62  4954.4  270.07  4970.2  267.57  4995.5  260.26
    4996  259.76    5005  260.26  5033.7  263.59  5040.3  265.75  5070.3  265.99
  5128.9  270.46  5140.4  269.06  5150.4  266.14  5220.4  270.62  5319.4  272.94
  5450.7  274.31  5480.7   278.7  5490.7  277.67  5502.1  273.12  5560.8  272.84
  5580.8  278.47  5610.8  276.67  5733.5  278.45    5781  280.93  5890.9  283.57
#Mann= 11 ,-1 , 0
  3609.6     .07       0  3935.3     .12       0  3942.5     .07       0
  4263.1     .12       0  4620.5     .07       0  4814.8     .12       0
  4954.4     .07       0  4995.5     .05       0    5005     .07       0
  5128.9     .12       0  5319.4     .07       0
Bank Sta=4995.5,5005
XS Rating Curve= 0 ,0
Exp/Cntr=0.3,0.1

Type RM Length L Ch R = 1 ,77312   ,935,935,935
BEGIN DESCRIPTION:
Mapping XS 3e2a7f79
END DESCRIPTION:
XS GIS Cut Line= 3
      2455106.87     13503557.01      2454763.12     13502390.33
      2454627.78      13501479.4
#Sta/Elev= 30
  3616.6  282.86  3629.1  281.83  3660.4  281.82  3733.2  279.88  3879.3  276.65
  4251.2  271.61  4285.9  270.12  4358.9  270.88  4489.6  269.35  4765.4  270.02
  4786.3  268.81  4868.6  269.84  4929.2  269.43  4949.5  267.23  4969.7  261.55
  4987.5  260.36  4987.8  259.26  4988.3  258.76  4997.3  259.26  5010.1  262.96
  5050.6  264.96    5091  268.38  5131.4  269.16  5171.9  268.43  5265.1  271.87
  5444.8  275.96  5515.6  279.13  5525.7  278.44  5568.4  279.61  5753.8  285.74
#Mann= 6 ,-1 , 0
  3616.6     .12       0  3733.2     .07       0  4251.2     .12       0
  4987.8     .05       0  4997.3     .12       0  5568.4     .07       0
Bank Sta=4987.8,4997.3
XS Rating Curve= 0 ,0
Exp/Cntr=0.3,0.1

Type RM Length L Ch R = 1 ,76377   ,568,568,568
BEGIN DESCRIPTION:
Mapping XS c5cd6faf
END DESCRIPTION:
XS GIS Cut Line= 4
      2455336.05     13503635.16      2455023.54     13502713.25
       2455377.7     13502520.54      2455190.21     13501442.46
#Sta/Elev= 30
  3797.3  285.63  4063.2  278.61  4643.2  269.13    4689  268.06  4705.5  264.27
  4715.1  264.23  4746.5  268.16    4794  268.15  4837.7  267.31  4843.4  264.96
  4852.1  264.61  4881.3  265.31    4909  262.71    4925  264.75  4931.8  267.06
  4954.5  267.13  4990.6  264.89  5000.2  261.83  5007.6  258.69  5008.1  258.19
  5017.2  258.69  5028.6  260.39  5072.3  262.75  5088.4  266.64  5094.1  266.05
  5102.5  268.12  5148.1  269.18  5311.5  267.74    5545  269.17  6268.2   278.2
#Mann= 6 ,-1 , 0
  3797.3     .12       0  4063.2     .07       0  4643.2     .12       0
  5000.2     .07       0  5007.6     .05       0  5017.2     .07       0
Bank Sta=5007.6,5017.2
XS Rating Curve= 0 ,0
Exp/Cntr=0.3,0.1

Type RM Length L Ch R = 1 ,75809   ,571,571,571
BEGIN DESCRIPTION:
Mapping XS 9b515026
END DESCRIPTION:
XS GIS Cut Line= 3
      2455523.54     13503676.77      2455622.49     13502921.58
       2455299.8     13501292.48
#Sta/Elev= 30
  4190.9  287.41  4676.8     276  4797.8   272.1    4818  269.74  4828.1  271.19
  4838.2  270.78  4854.8  265.08  4859.9  269.49  4878.5  262.85  4888.6  262.75
  4898.7   264.3  4908.8  263.39  4928.6  264.45  4933.7  266.62  4952.5  266.18
  4959.3  265.81  4979.6   260.1  5005.2  258.61  5005.7  258.11  5015.2  258.61
  5040.8  259.19  5061.2  262.96  5067.3  265.11  5083.4  266.21  5379.7  268.02
  5516.8  267.37  5733.1  268.18  6274.3  273.95    6417  276.33  6613.3   281.4
#Mann= 5 ,-1 , 0
  4190.9     .07       0  5005.2     .05       0  5015.2     .07       0
  5083.4     .12       0  5516.8     .07       0
Bank Sta=5005.2,5015.2
XS Rating Curve= 0 ,0
Exp/Cntr=0.3,0.1