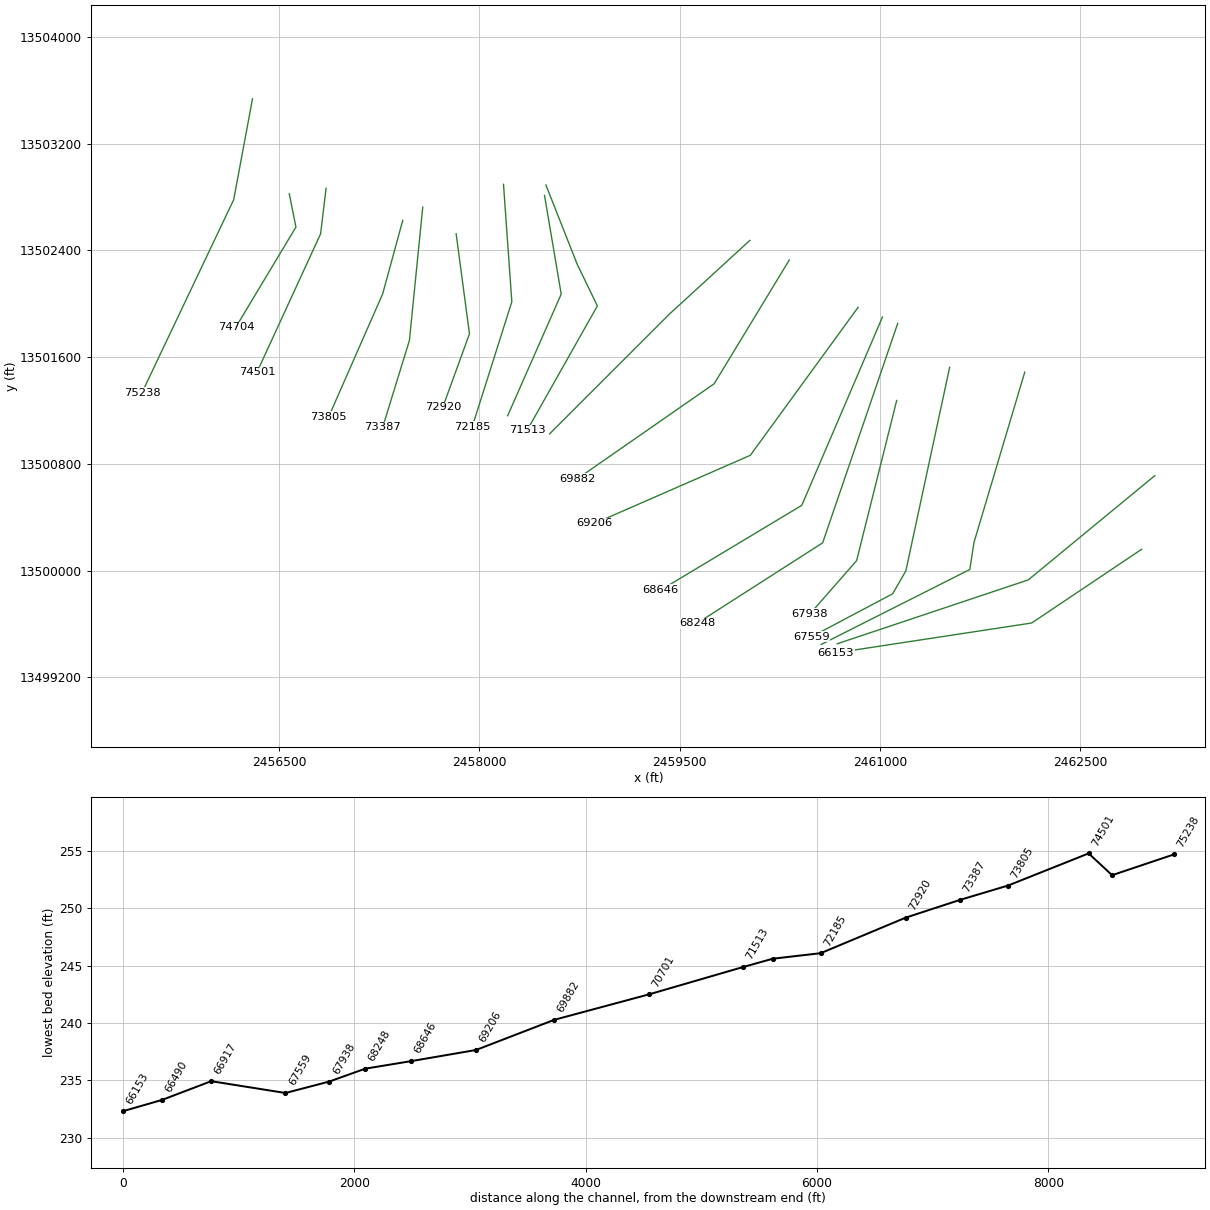
HEC-RAS study EIGHTEENMILE CREEK.prj: EIGHTEENMILE CREEK Base Level Engineering

--- EIGHTEENMILE CREEK.g01 (geometry) --- (continued)

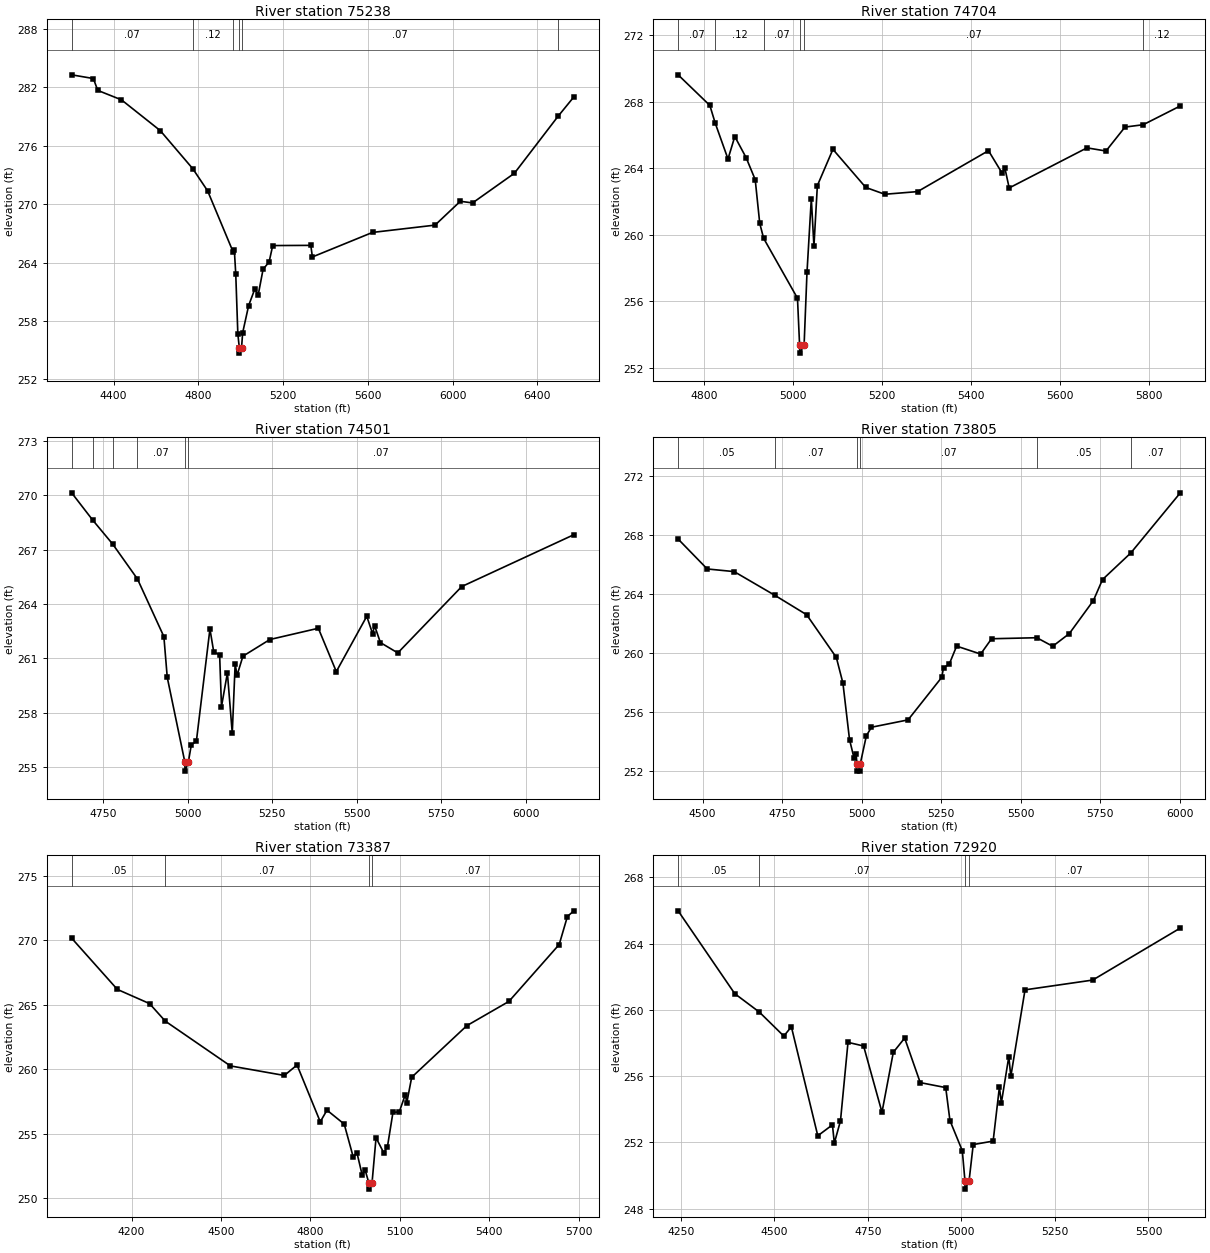
Type RM Length L Ch R = 1 ,75238   ,534,534,534
BEGIN DESCRIPTION:
Mapping XS d650c8d3
END DESCRIPTION:
XS GIS Cut Line= 3
      2456299.58     13503536.19      2456158.95     13502780.96
      2455471.44     13501333.01
#Sta/Elev= 30
  4201.8  283.28  4304.2   282.9  4325.1  281.68    4437  280.71  4620.1  277.55
  4773.9  273.63  4843.8  271.36  4965.3  265.03    4970  265.24  4976.6  262.83
  4986.5  256.65  4993.7  255.19  4994.2  254.69  5003.8  255.19  5009.2  256.78
  5037.5  259.58  5065.8  261.23    5083  260.71  5105.7  263.31    5134  264.05
  5151.1  265.74  5330.9  265.76  5338.5  264.57  5622.3  267.09  5917.6  267.84
  6036.9  270.29  6094.7  270.12  6292.4  273.17    6498  279.01  6572.9  281.01
#Mann= 6 ,-1 , 0
  4201.8     .07       0  4773.9     .12       0  4965.3     .07       0
  4993.7     .05       0  5003.8     .07       0    6498     .12       0
Bank Sta=4993.7,5003.8
XS Rating Curve= 0 ,0
Exp/Cntr=0.3,0.1

Type RM Length L Ch R = 1 ,74704   ,203,203,203
BEGIN DESCRIPTION:
EIGHTEENMILE CREEK 123.0
END DESCRIPTION:
XS GIS Cut Line= 3
        2456575.     13502824.99        2456625.       13502575.
      2456174.99     13501824.99
#Sta/Elev= 30
  4740.8  269.61  4812.2  267.77  4824.2  266.71    4853  264.55  4868.3   265.9
  4893.8  264.63  4914.2  263.31  4924.4  260.68  4933.2  259.78  5009.3  256.18
    5014  253.38  5014.5  252.88  5024.2  253.38  5030.7  257.74  5040.4  262.17
  5046.3  259.31    5054  262.95    5089  265.13  5162.9  262.84  5205.7  262.43
  5279.5  262.59  5438.9  265.05    5470  263.68  5475.8     264  5485.5  262.81
  5660.5  265.22  5703.2  265.03    5746  266.47  5786.9  266.61  5870.4  267.74
#Mann= 6 ,-1 , 0
  4740.8     .07       0  4824.2     .12       0  4933.2     .07       0
    5014     .05       0  5024.2     .07       0  5786.9     .12       0
Bank Sta=5014,5024.2
XS Rating Curve= 0 ,0
Exp/Cntr=0.3,0.1

Type RM Length L Ch R = 1 ,74501   ,696,696,696
BEGIN DESCRIPTION:
EIGHTEENMILE CREEK 122.0
END DESCRIPTION:
XS GIS Cut Line= 3
       2456850.8     13502866.11      2456809.78     13502524.46
      2456332.56     13501485.85
#Sta/Elev= 30
  4655.9  270.13  4718.5  268.62  4777.5   267.3  4850.7  265.38    4929   262.2
    4939  259.95  4991.1  255.28  4991.6  254.78  5001.4  255.28  5010.4  256.24
  5025.2  256.42  5065.4  262.62  5076.6  261.36  5094.1  261.19  5099.6  258.34
  5117.1   260.2  5131.5  256.87  5140.1   260.7  5145.6  260.06  5163.1  261.12
    5243  262.04  5386.4  262.66  5439.6  260.27  5529.8  263.32  5547.3  262.35
  5552.8  262.81  5570.2  261.87  5621.7   261.3    5811  264.96    6143  267.82
#Mann= 6 ,-1 , 0
  4655.9     .05       0  4718.5     .07       0  4777.5     .12       0
  4850.7     .07       0  4991.1     .05       0  5001.4     .07       0
Bank Sta=4991.1,5001.4
XS Rating Curve= 0 ,0
Exp/Cntr=0.3,0.1

Type RM Length L Ch R = 1 ,73805   ,418,418,418
BEGIN DESCRIPTION:
EIGHTEENMILE CREEK 121.0
END DESCRIPTION:
XS GIS Cut Line= 3
      2457424.99     13502624.98        2457275.       13502075.
      2456869.51     13501151.03
#Sta/Elev= 30
  4423.2  267.74  4514.7  265.71  4599.4  265.53  4728.1  263.91  4827.4   262.6
  4920.7   259.7  4941.4  257.96  4962.2  254.12    4976   252.9  4982.9  253.15
  4985.4  252.48  4985.9  251.98  4995.5  251.98    4996  252.48  5015.1  254.38
    5031  254.96  5146.2  255.46  5252.2  258.35  5257.7     259  5275.6  259.24
    5299  260.47  5374.5  259.93  5408.8  260.97  5551.1  261.04  5601.1  260.46
  5653.3  261.32  5728.9  263.56  5757.7  264.99  5846.8   266.8  6002.3  270.88
#Mann= 6 ,-1 , 0
  4423.2     .05       0  4728.1     .07       0  4985.4     .05       0
    4996     .07       0  5551.1     .05       0  5846.8     .07       0
Bank Sta=4985.4,4996
XS Rating Curve= 0 ,0
Exp/Cntr=0.3,0.1

Type RM Length L Ch R = 1 ,73387   ,467,467,467
BEGIN DESCRIPTION:
EIGHTEENMILE CREEK 120.0
END DESCRIPTION:
XS GIS Cut Line= 3
        2457575.     13502725.02        2457475.       13501725.
        2457275.     13501074.98
#Sta/Elev= 30
    3999  270.17  4152.3   266.2  4260.3   265.1  4313.2  263.74  4531.7  260.27
  4712.6  259.53  4755.3  260.34  4833.2  255.94  4855.8  256.84  4913.6  255.76
  4943.7  253.22  4956.3  253.54  4973.9  251.81  4983.9  252.19    4996  251.22
  4996.5  250.72    5007  251.22  5020.4   254.7  5045.9  253.55  5058.3  253.96
  5077.2  256.67  5098.2   256.7  5118.4  258.03  5123.7  257.43    5140  259.39
  5325.1  263.39  5466.3  265.27    5635  269.68  5662.5  271.85  5684.1  272.29
#Mann= 4 ,-1 , 0
    3999     .05       0  4313.2     .07       0    4996     .05       0
    5007     .07       0
Bank Sta=4996,5007
XS Rating Curve= 0 ,0
Exp/Cntr=0.3,0.1

Type RM Length L Ch R = 1 ,72920   ,735,735,735
BEGIN DESCRIPTION:
EIGHTEENMILE CREEK 119.0
END DESCRIPTION:
XS GIS Cut Line= 3
        2457825.     13502524.96        2457925.       13501775.
      2457725.01     13501225.03
#Sta/Elev= 30
  4243.3  265.98  4394.6  260.98  4460.2  259.87  4525.7  258.42  4545.9  258.98
  4616.5   252.4  4655.6  253.06  4660.7  251.96  4677.1   253.3  4697.2  258.04
  4738.9  257.82    4788  253.82  4818.3  257.44  4848.6   258.3  4890.2  255.61
  4958.3  255.31  4969.6  253.32  5002.6   251.5  5009.7  249.68  5010.2  249.18
  5020.7  249.68  5031.8  251.87    5085  252.08  5101.7  255.33    5107  254.39
  5126.9  257.18  5132.2  255.98  5170.2  261.21    5351   261.8  5585.1  264.94
#Mann= 4 ,-1 , 0
  4243.3     .05       0  4460.2     .07       0  5009.7     .05       0
  5020.7     .07       0
Bank Sta=5009.7,5020.7
XS Rating Curve= 0 ,0
Exp/Cntr=0.3,0.1

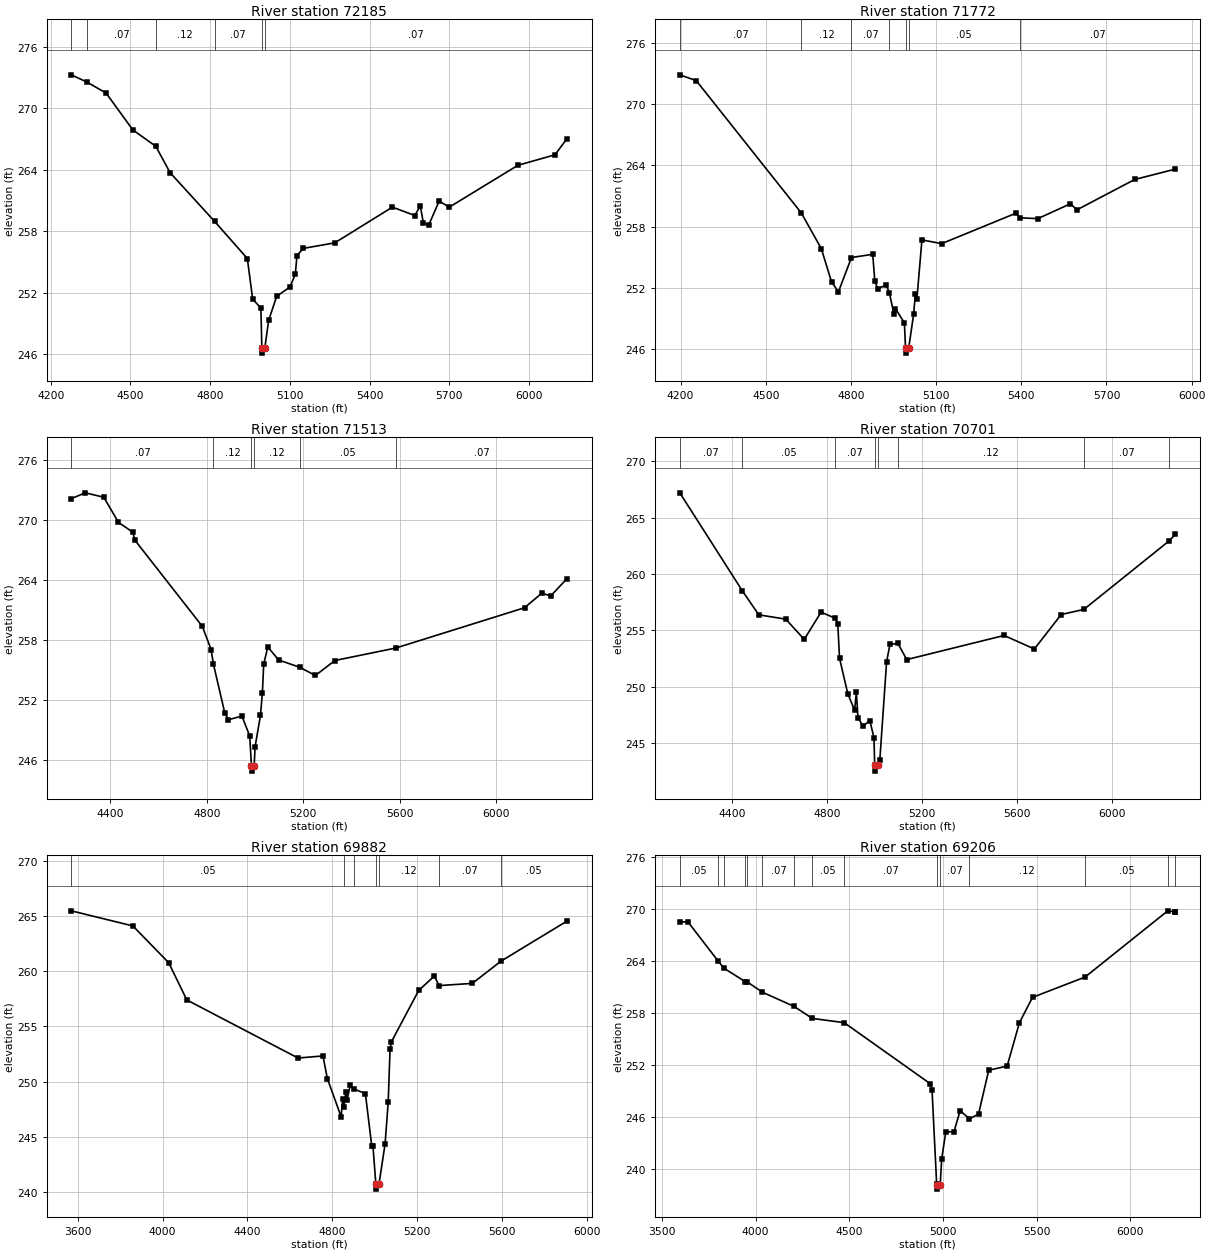
Type RM Length L Ch R = 1 ,72185   ,413,413,413
BEGIN DESCRIPTION:
Mapping XS cdcde2cd
END DESCRIPTION:
XS GIS Cut Line= 3
      2458179.79     13502895.51      2458242.29     13502015.33
      2457945.77     13501078.95
#Sta/Elev= 30
  4277.8  273.26    4338  272.53  4408.6  271.48  4508.9  267.89  4595.9  266.27
  4649.2  263.71  4816.6  258.95    4940  255.32    4960  251.36  4990.9  250.48
  4994.6  246.58  4995.1  246.08  5005.7  246.58  5020.2  249.28  5050.2  251.62
  5100.4  252.54  5120.4  253.78  5126.7  255.61  5150.5  256.31  5268.9  256.85
  5485.7  260.34  5570.1  259.52  5590.6  260.47  5602.4  258.77  5622.1  258.58
  5661.7  260.93  5699.3  260.33  5957.6  264.42  6097.3  265.45  6142.4  267.02
#Mann= 6 ,-1 , 0
  4277.8     .05       0    4338     .07       0  4595.9     .12       0
  4816.6     .07       0  4994.6     .05       0  5005.7     .07       0
Bank Sta=4994.6,5005.7
XS Rating Curve= 0 ,0
Exp/Cntr=0.3,0.1

Type RM Length L Ch R = 1 ,71772   ,259,259,259
BEGIN DESCRIPTION:
Mapping XS c8281514
END DESCRIPTION:
XS GIS Cut Line= 3
      2458487.09     13502812.17      2458612.08     13502072.63
      2458211.04     13501161.18
#Sta/Elev= 30
  4197.1  272.88  4255.1  272.31  4625.1  259.34  4695.4  255.85  4731.7  252.58
  4755.9  251.61  4801.7  254.97  4876.7  255.29  4883.9   252.7    4894   251.9
  4924.4  252.29  4935.7  251.45  4951.1  249.48  4956.6  249.96  4988.2  248.57
  4992.2   246.1  4992.7   245.6  5003.4   246.1    5021  249.46  5026.6  251.35
  5032.1  250.87    5050   256.7  5119.3  256.33  5381.5  259.32    5395  258.87
    5458  258.78  5572.9  260.24  5596.2  259.65  5799.3  262.62  5942.9  263.64
#Mann= 7 ,-1 , 0
  4197.1     .07       0  4625.1     .12       0  4801.7     .07       0
  4935.7     .05       0  4992.2     .05       0  5003.4     .05       0
    5395     .07       0
Bank Sta=4992.2,5003.4
XS Rating Curve= 0 ,0
Exp/Cntr=0.3,0.1

Type RM Length L Ch R = 1 ,71513   ,812,812,812
BEGIN DESCRIPTION:
Mapping XS 78daa7d9
END DESCRIPTION:
XS GIS Cut Line= 4
      2458497.51     13502890.31      2458731.87     13502296.58
      2458882.91     13501984.08      2458356.85     13501051.75
#Sta/Elev= 30
  4238.4  272.14  4296.1  272.72  4373.1  272.28    4434  269.76  4493.5  268.78
  4502.1  267.98  4781.7  259.36  4818.2  257.04    4828  255.56  4874.9   250.7
  4889.6  250.01    4946  250.38  4978.4  248.39  4985.6  245.37  4986.1  244.87
  4996.8  245.37  5000.6   247.3  5022.9  250.44  5030.8  252.64  5036.4  255.59
  5053.4  257.29  5098.6  255.99  5186.1  255.26  5250.8  254.44  5331.6  255.94
  5584.5  257.19  6118.3  261.22  6189.6  262.67  6227.1  262.41  6294.3  264.13
#Mann= 6 ,-1 , 0
  4238.4     .07       0    4828     .12       0  4985.6     .05       0
  4996.8     .12       0  5186.1     .05       0  5584.5     .07       0
Bank Sta=4985.6,4996.8
XS Rating Curve= 0 ,0
Exp/Cntr=0.3,0.1

Type RM Length L Ch R = 1 ,70701   ,819,819,819
BEGIN DESCRIPTION:
EIGHTEENMILE CREEK 115.0
END DESCRIPTION:
XS GIS Cut Line= 3
      2460025.04     13502475.03        2459425.       13501925.
      2458524.99     13501024.99
#Sta/Elev= 30
  4181.2  267.19  4443.7  258.52  4513.9  256.36  4627.4  255.98  4705.1  254.18
    4776   256.6  4835.3  256.06  4846.3  255.58  4853.7  252.51  4888.8  249.34
  4917.2   247.9  4924.6  249.48  4931.4  247.21    4953   246.5  4981.3  246.97
  4998.7  245.46  5001.8  242.99  5002.3  242.49  5016.8  242.99  5023.5  243.51
  5051.8  252.16  5065.9  253.74  5099.6  253.82  5136.6  252.39  5546.7  254.53
    5674  253.33  5787.1  256.39  5882.4  256.84  6241.8  262.93    6268  263.52
#Mann= 8 ,-1 , 0
  4181.2     .07       0  4443.7     .05       0  4835.3     .07       0
  5001.8     .05       0  5016.8     .07       0  5099.6     .12       0
  5882.4     .07       0  6241.8     .05       0
Bank Sta=5001.8,5016.8
XS Rating Curve= 0 ,0
Exp/Cntr=0.3,0.1

Type RM Length L Ch R = 1 ,69882   ,676,676,676
BEGIN DESCRIPTION:
Mapping XS d210604d
END DESCRIPTION:
XS GIS Cut Line= 3
      2460320.42     13502327.86      2459757.91     13501400.75
      2458731.85     13500687.19
#Sta/Elev= 30
  3570.5  265.47  3860.4   264.1  4029.1  260.77  4114.4   257.4  4638.2  252.14
  4755.6  252.33  4776.5  250.27  4841.2  246.82  4848.1  248.39  4854.1  247.68
  4862.9  249.03    4869  248.33  4883.9  249.66    4901  249.34  4955.4  248.92
  4985.1  244.22  4991.2  244.13  5004.5  240.77    5005  240.27  5019.8  240.77
  5048.2  244.37  5062.8  248.12  5071.5  252.92  5077.6   253.6  5206.6  258.26
  5279.7  259.56  5302.9   258.7  5459.1   258.9  5593.8  260.91  5904.7  264.54
#Mann= 7 ,-1 , 0
  3570.5     .05       0  4854.1     .07       0    4901     .12       0
  5004.5     .05       0  5019.8     .12       0  5302.9     .07       0
  5593.8     .05       0
Bank Sta=5004.5,5019.8
XS Rating Curve= 0 ,0
Exp/Cntr=0.3,0.1

Type RM Length L Ch R = 1 ,69206   ,560,560,560
BEGIN DESCRIPTION:
Mapping XS a4855934
END DESCRIPTION:
XS GIS Cut Line= 3
      2460836.04     13501973.68      2460028.74     13500864.29
      2458862.05     13500353.86
#Sta/Elev= 30
  3595.3  268.43  3638.3  268.48  3800.2  263.94  3832.1   263.1  3944.9  261.57
  3956.6  261.52  4036.7  260.35  4205.7  258.71  4302.4  257.33  4472.8  256.84
  4933.4  249.78  4941.7  249.06  4966.3  238.22  4969.6  238.14  4970.1  237.64
  4985.3  238.14  4993.2  241.13  5015.1  244.25  5058.7  244.25  5091.5  246.69
  5141.3  245.75  5189.7  246.29  5244.3  251.36  5342.5  251.83    5408  256.83
    5478  259.76  5758.4   262.1  6199.9  269.74  6240.2  269.61  6240.8  269.61
#Mann= 15 ,-1 , 0
  3595.3     .05       0  3800.2     .07       0  3832.1     .05       0
  3944.9     .07       0  3956.6    .035       0  4036.7     .07       0
  4205.7     .12       0  4302.4     .05       0  4472.8     .07       0
  4969.6     .05       0  4985.3     .07       0  5141.3     .12       0
  5758.4     .05       0  6199.9     .07       0  6240.2     .05       0
Bank Sta=4969.6,4985.3
XS Rating Curve= 0 ,0
Exp/Cntr=0.3,0.1

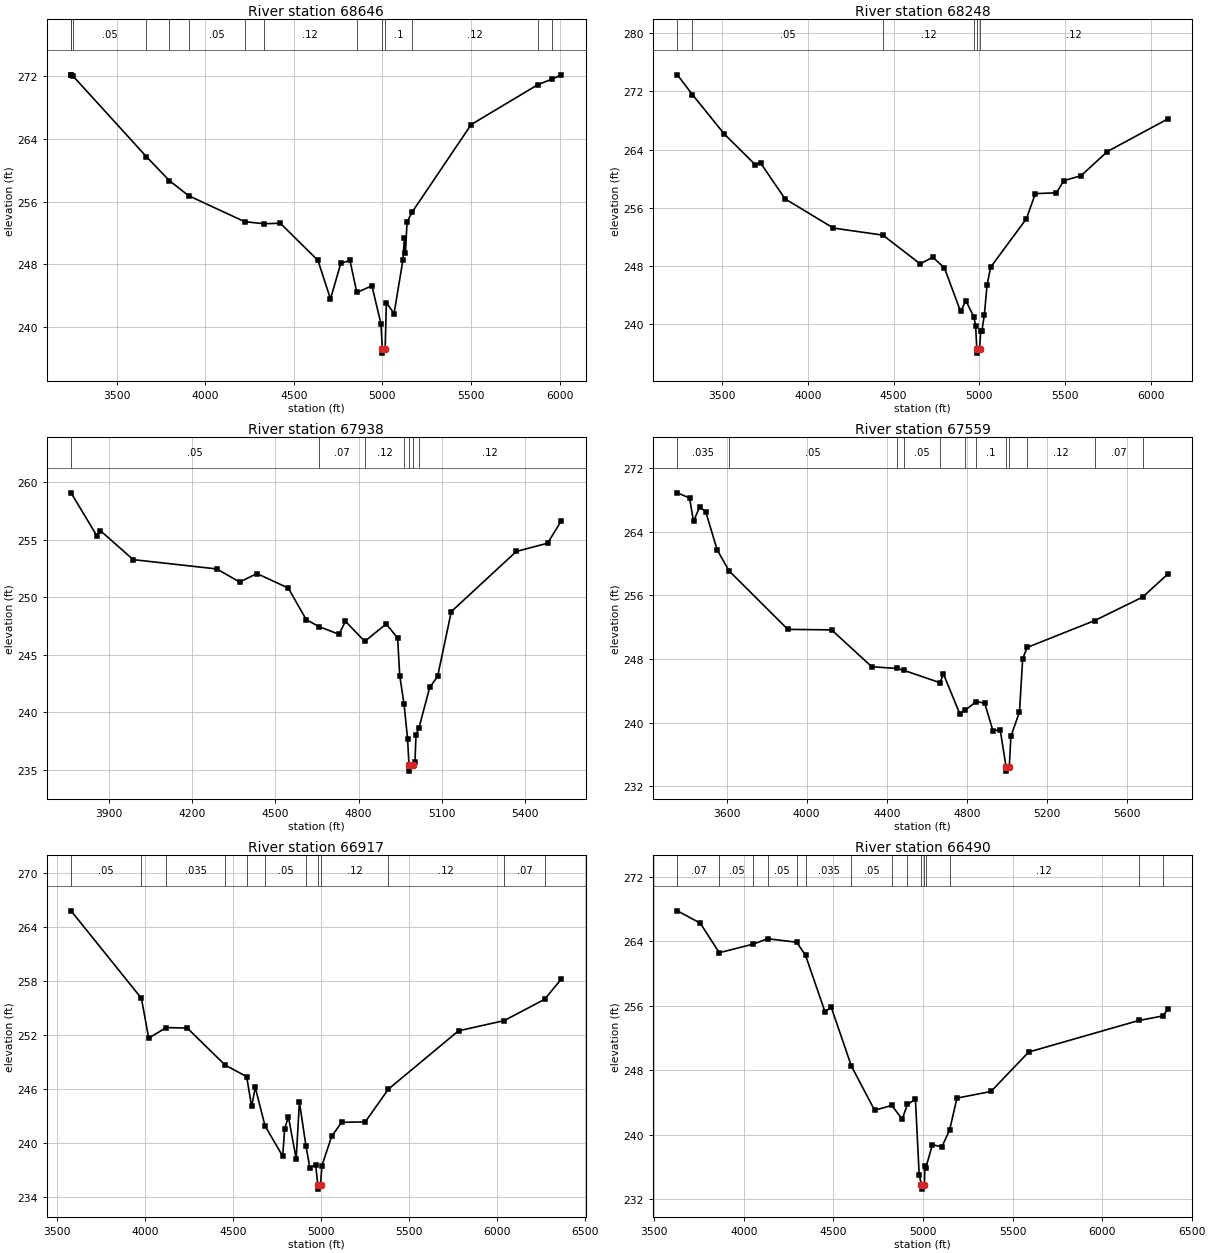
Type RM Length L Ch R = 1 ,68646   ,398,398,398
BEGIN DESCRIPTION:
Mapping XS d80fbcc6
END DESCRIPTION:
XS GIS Cut Line= 3
      2461018.33     13501900.76      2460414.16     13500489.29
      2459358.39     13499854.79
#Sta/Elev= 30
  3243.3  272.15    3245   272.1  3255.2  271.97  3668.3  261.72  3798.1  258.66
  3906.6  256.74  4222.8  253.43  4329.7  253.17  4424.3  253.22  4636.6  248.49
  4707.2  243.57  4765.4  248.12  4817.3  248.48  4855.7   244.4    4941  245.25
  4992.2  240.39  4999.8  237.17  5000.3  236.67  5015.6  237.17  5022.7  243.11
    5066  241.71    5116  248.55  5124.3   251.4  5130.1   249.4  5139.3   253.4
    5168  254.65  5501.2  265.81  5876.3  270.88  5957.4  271.61  6010.4  272.15
#Mann= 14 ,-1 , 0
  3243.3    .063       0    3245    .035       0  3255.2     .05       0
  3668.3    .035       0  3798.1     .07       0  3906.6     .05       0
  4222.8     .07       0  4329.7     .12       0  4855.7      .1       0
  4999.8     .05       0  5015.6      .1       0    5168     .12       0
  5876.3     .07       0  5957.4     .05       0
Bank Sta=4999.8,5015.6
XS Rating Curve= 0 ,0
Exp/Cntr=0.3,0.1

Type RM Length L Ch R = 1 ,68248   ,310,310,310
BEGIN DESCRIPTION:
Mapping XS 35925f01
END DESCRIPTION:
XS GIS Cut Line= 3
      2461132.92      13501853.9      2460570.41     13500208.04
      2459628.82     13499604.59
#Sta/Elev= 30
  3240.3  274.29  3328.1  271.57  3513.9  266.15  3693.6  261.94  3725.3  262.16
  3867.8  257.23  4149.6  253.21  4438.2  252.24  4655.2  248.29  4728.7   249.2
  4796.6  247.73  4890.6  241.75  4921.9  243.22  4968.5  240.96  4978.6  239.78
  4985.3  236.51  4985.8  236.01  5001.2  236.51  5008.5  239.11  5014.4  238.99
  5029.6  241.32  5044.8  245.36    5066  247.83  5274.8  254.51  5326.3  257.95
  5449.3  258.06  5492.9  259.74  5592.7  260.41  5746.2  263.74    6098  268.22
#Mann= 6 ,-1 , 0
  3240.3    .035       0  3328.1     .05       0  4438.2     .12       0
  4968.5      .1       0  4985.3     .05       0  5001.2     .12       0
Bank Sta=4985.3,5001.2
XS Rating Curve= 0 ,0
Exp/Cntr=0.3,0.1

Type RM Length L Ch R = 1 ,67938   ,379,379,379
BEGIN DESCRIPTION:
EIGHTEENMILE CREEK 110.0
END DESCRIPTION:
XS GIS Cut Line= 3
      2461125.01     13501275.05        2460825.       13500075.
      2460474.99     13499674.99
#Sta/Elev= 30
    3763  259.09  3855.8  255.36  3868.7   255.8  3987.2  253.28  4288.7  252.47
  4371.2  251.33  4433.1  252.07  4546.4  250.81  4610.9  248.07  4656.9  247.46
  4729.4  246.79  4752.6  247.92  4822.2  246.17  4899.5  247.69  4940.7  246.46
  4948.4  243.19  4963.9  240.71  4976.8  237.66  4981.7  235.39  4982.2  234.89
  4997.7  235.39  5003.3   235.7  5007.1  238.05  5017.8  238.66  5056.5  242.17
  5084.9  243.12  5134.3  248.76  5368.7  253.99  5481.7  254.71  5531.5  256.67
#Mann= 7 ,-1 , 0
    3763     .05       0  4656.9     .07       0  4822.2     .12       0
  4963.9      .1       0  4981.7     .05       0  4997.7      .1       0
  5017.8     .12       0
Bank Sta=4981.7,4997.7
XS Rating Curve= 0 ,0
Exp/Cntr=0.3,0.1

Type RM Length L Ch R = 1 ,67559   ,642,642,642
BEGIN DESCRIPTION:
Mapping XS c6321546
END DESCRIPTION:
XS GIS Cut Line= 4
       2461521.8     13501524.03      2461193.68     13499997.97
      2461094.72      13499826.1      2460485.35     13499503.18
#Sta/Elev= 30
  3354.6  268.89  3415.4  268.24  3435.4  265.29  3466.1  267.15  3496.8  266.46
  3553.3  261.72    3613  259.07  3905.9  251.72  4125.1  251.65  4325.3  247.02
  4452.5   246.8  4486.4  246.56  4666.3  245.01  4683.3  246.12  4765.1  241.09
  4789.7  241.52    4847  242.62  4889.2  242.46  4930.5  238.96  4966.9  239.08
  4996.3  234.39  4996.8  233.89  5012.3  234.39  5020.1  238.25  5063.2  241.35
    5079  248.01    5101  249.44  5439.2  252.83  5678.1  255.78  5803.5  258.66
#Mann= 12 ,-1 , 0
  3354.6    .035       0    3613     .05       0  4452.5     .12       0
  4486.4     .05       0  4666.3     .12       0  4789.7     .07       0
    4847      .1       0  4996.3     .05       0  5012.3      .1       0
    5101     .12       0  5439.2     .07       0  5678.1     .12       0
Bank Sta=4996.3,5012.3
XS Rating Curve= 0 ,0
Exp/Cntr=0.3,0.1

Type RM Length L Ch R = 1 ,66917   ,427,427,427
BEGIN DESCRIPTION:
Mapping XS 2a5973a9
END DESCRIPTION:
XS GIS Cut Line= 4
      2462084.31     13501487.58      2461704.09     13500211.52
      2461672.84     13500008.39      2460559.15     13499446.34
#Sta/Elev= 30
  3581.4  265.79  3980.8  256.09  4022.3  251.67  4121.8  252.84  4241.5  252.78
  4456.9  248.67  4578.5   247.4  4606.7  244.09  4627.5   246.2  4682.3  241.96
    4783  238.58  4794.5  241.61  4815.4  242.96  4859.8  238.28    4878  244.59
  4915.4  239.69  4937.2   237.3  4970.1  237.63  4982.3  235.42  4982.8  234.92
  4998.4  235.42  5005.5  237.49  5061.1  240.77  5117.6  242.33    5252  242.38
  5383.3  246.01  5781.6  252.48  6040.6  253.61  6270.9  255.98  6365.9  258.24
#Mann= 12 ,-1 , 0
  3581.4     .05       0  3980.8     .07       0  4121.8    .035       0
  4456.9     .05       0  4578.5     .12       0  4682.3     .05       0
  4915.4     .12       0  4982.3     .05       0  4998.4     .12       0
  5383.3     .12       0  6040.6     .07       0  6270.9     .12       0
Bank Sta=4982.3,4998.4
XS Rating Curve= 0 ,0
Exp/Cntr=0.3,0.1

Type RM Length L Ch R = 1 ,66490   ,337,337,337
BEGIN DESCRIPTION:
Mapping XS 6deefaa4
END DESCRIPTION:
XS GIS Cut Line= 3
      2463058.28     13500711.53      2462110.34     13499930.27
      2460679.01     13499451.42
#Sta/Elev= 30
  3628.7  267.77  3756.5  266.24  3862.6  262.58  4053.4  263.65  4132.9  264.31
  4294.6  263.88  4344.4  262.25  4452.3  255.29  4488.2  255.79  4600.1  248.54
  4729.8  243.06  4826.2  243.65  4883.8  241.94  4912.9  243.77  4957.7  244.41
  4978.7  235.08  4991.6  233.78  4992.1  233.28  5008.1  233.78  5010.3  236.16
  5015.6   235.9  5052.5   238.8    5105   238.5  5148.7  240.61  5189.6  244.56
  5379.4  245.38  5590.3  250.27  6204.9  254.18  6338.7  254.74  6366.4  255.55
#Mann= 15 ,-1 , 0
  3628.7     .07       0  3862.6     .05       0  4053.4     .07       0
  4132.9     .05       0  4294.6     .07       0  4344.4    .035       0
  4600.1     .05       0  4826.2     .07       0  4912.9      .1       0
  4991.6     .05       0  5008.1      .1       0  5015.6     .07       0
  5148.7     .12       0  6204.9     .07       0  6338.7     .12       0
Bank Sta=4991.6,5008.1
XS Rating Curve= 0 ,0
Exp/Cntr=0.3,0.1

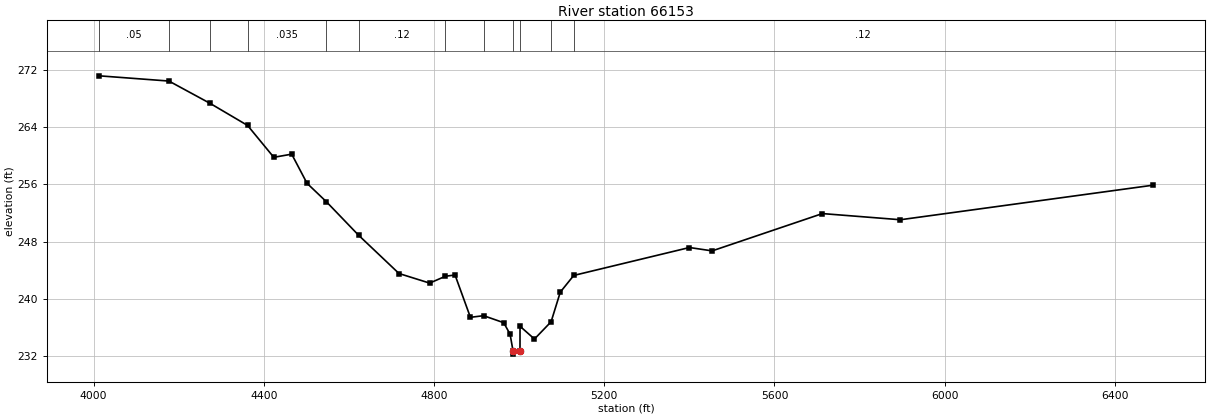
Type RM Length L Ch R = 1 ,66153   ,577,577,577
BEGIN DESCRIPTION:
Mapping XS e22347d9
END DESCRIPTION:
XS GIS Cut Line= 3
      2462959.34     13500159.46      2462136.38     13499607.35
      2460668.84     13499383.57
#Sta/Elev= 30
  4013.3  271.17  4177.1  270.44  4274.2  267.31  4361.9  264.24  4423.5  259.79
  4465.6  260.23  4501.6  256.16  4546.8   253.6  4622.7  248.91  4717.7  243.56
  4789.7  242.22  4826.9  243.18  4849.4  243.35  4885.5  237.44  4916.5  237.67
  4963.7  236.69  4978.7  235.09  4985.5   232.8    4986   232.3    5002   232.8
  5002.1  236.19    5036  234.41  5075.1  236.82  5096.7  240.96  5128.3  243.29
  5400.2  247.19  5453.5  246.72  5712.6  251.93  5895.9  251.07  6488.8  255.89
#Mann= 12 ,-1 , 0
  4013.3     .05       0  4177.1     .07       0  4274.2     .05       0
  4361.9    .035       0  4546.8     .07       0  4622.7     .12       0
  4826.9     .07       0  4916.5      .1       0  4985.5     .05       0
    5002      .1       0  5075.1     .07       0  5128.3     .12       0
Bank Sta=4985.5,5002
XS Rating Curve= 0 ,0
Exp/Cntr=0.3,0.1