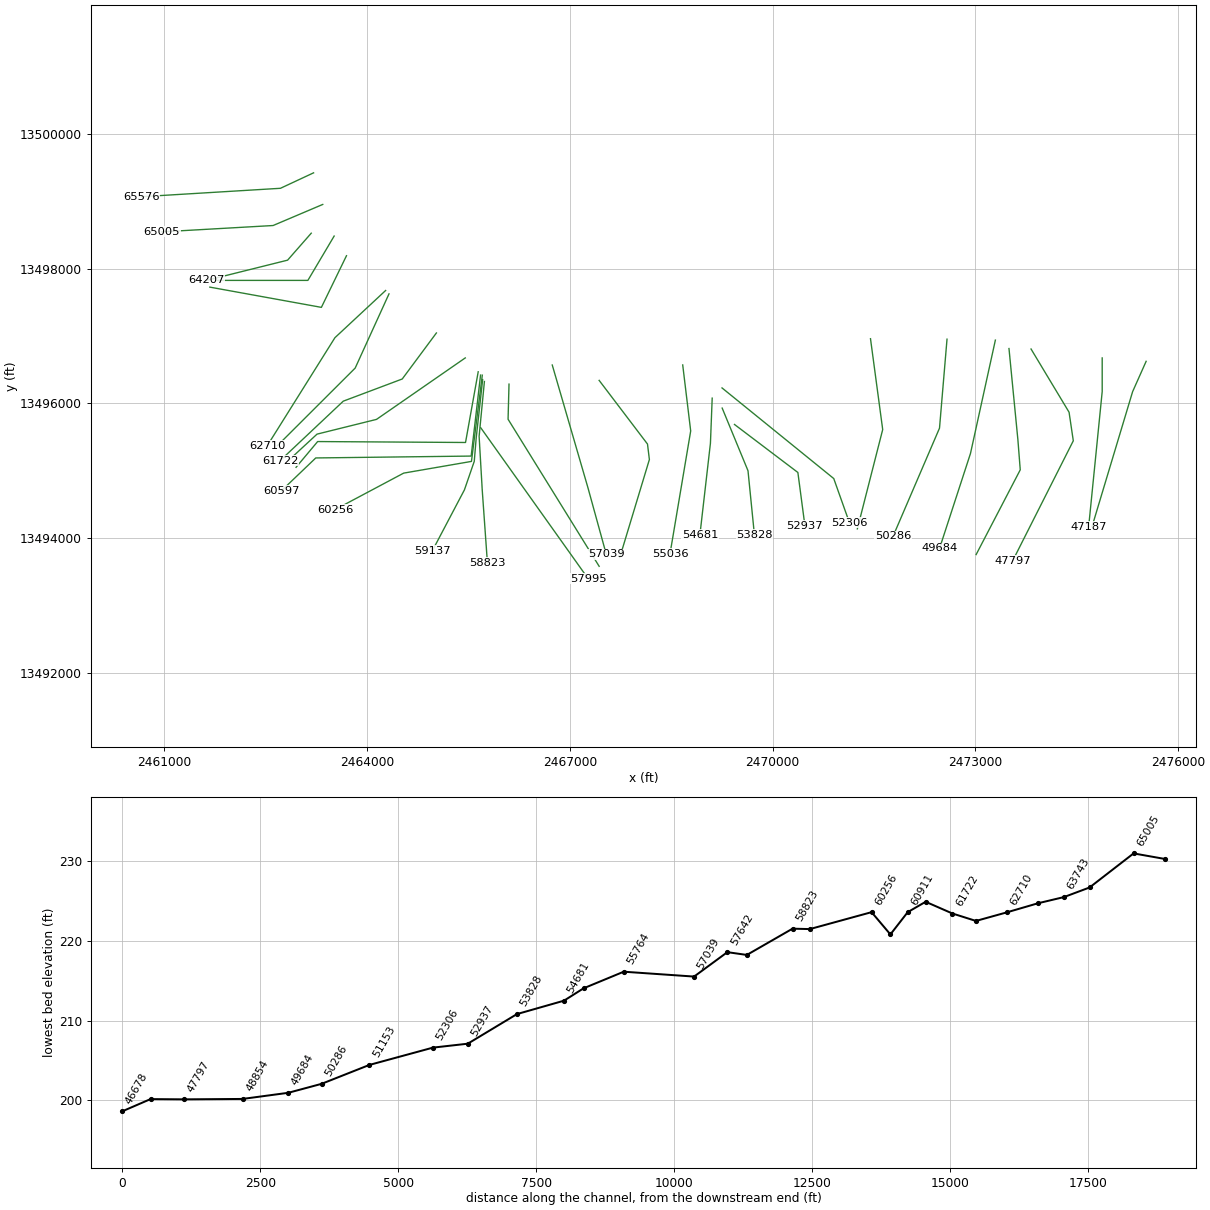
HEC-RAS study EIGHTEENMILE CREEK.prj: EIGHTEENMILE CREEK Base Level Engineering

--- EIGHTEENMILE CREEK.g01 (geometry) --- (continued)

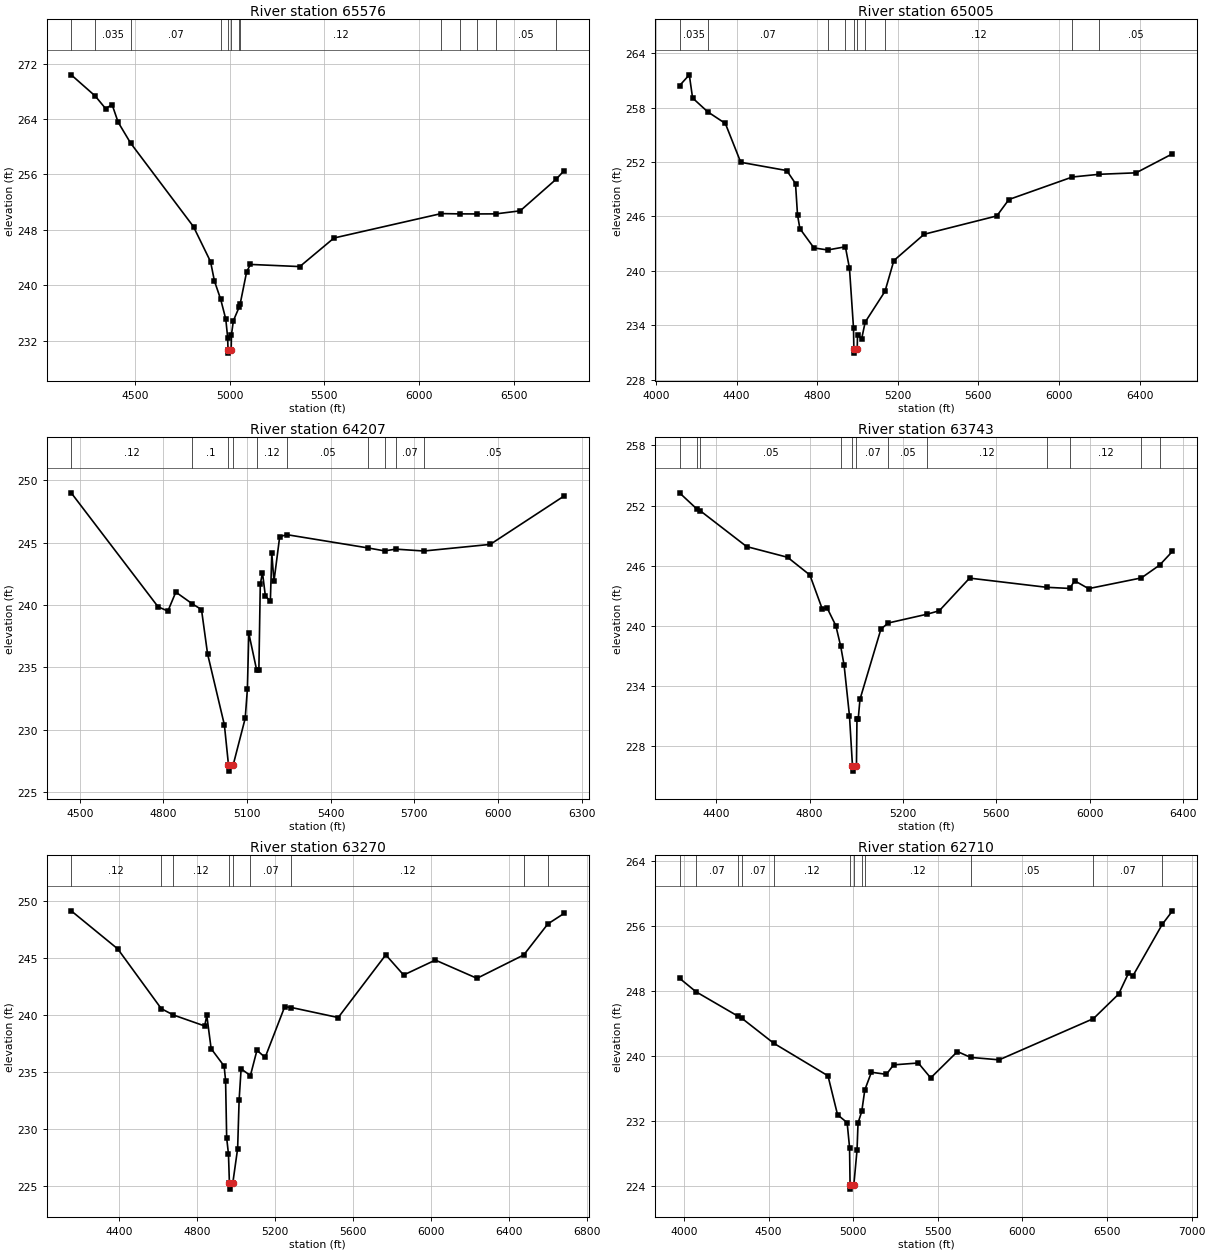
Type RM Length L Ch R = 1 ,65576   ,571,571,571
BEGIN DESCRIPTION:
Mapping XS 7c7a4599
END DESCRIPTION:
XS GIS Cut Line= 3
       2463209.3     13499419.85      2462719.72     13499190.68
      2460662.47     13499065.68
#Sta/Elev= 30
  4164.2  270.37  4290.8  267.32  4345.6  265.51  4380.2  266.07  4411.9  263.54
  4477.7  260.53  4809.7  248.47  4899.8  243.42  4919.9  240.66  4953.3  237.98
    4980  235.14    4990  232.46  4991.7  230.74  4992.2  230.24  5008.4  230.74
    5010  232.92  5020.1  234.91  5051.6  236.94  5055.6  237.29  5090.2  241.98
  5110.2  243.03  5370.6  242.72    5551  246.84  6116.5  250.36  6214.3  250.32
  6303.8  250.31  6405.3  250.32  6533.8  250.76  6723.1  255.31  6765.8  256.57
#Mann= 13 ,-1 , 0
  4164.2     .05       0  4290.8    .035       0  4477.7     .07       0
  4953.3      .1       0  4991.7     .05       0  5008.4      .1       0
  5051.6     .07       0  5055.6     .12       0  6116.5     .07       0
  6214.3     .05       0  6303.8     .07       0  6405.3     .05       0
  6723.1     .07       0
Bank Sta=4991.7,5008.4
XS Rating Curve= 0 ,0
Exp/Cntr=0.3,0.1

Type RM Length L Ch R = 1 ,65005   ,798,798,798
BEGIN DESCRIPTION:
Mapping XS 8fc7cc37
END DESCRIPTION:
XS GIS Cut Line= 3
      2463344.69     13498951.09      2462610.34      13498638.6
      2460964.48     13498544.85
#Sta/Elev= 30
  4116.5  260.41  4165.1  261.61  4181.4  259.06  4256.1  257.54    4344  256.25
  4420.4  251.97  4648.7  251.06  4692.2  249.63  4702.1  246.19  4713.9  244.66
  4783.9  242.53  4852.4  242.31  4939.7  242.66    4960  240.29    4980  233.73
  4981.7  231.44  4982.2  230.94  4998.4  231.44    5000  232.98  5020.1  232.48
    5038  234.36  5136.3  237.75  5180.3  241.14  5330.6  244.04  5691.2  246.06
  5751.3  247.87  6066.1  250.35  6200.6  250.65  6382.3  250.81  6563.1  252.91
#Mann= 10 ,-1 , 0
  4116.5    .035       0  4256.1     .07       0  4852.4     .12       0
  4939.7      .1       0  4981.7     .05       0  4998.4      .1       0
    5038     .05       0  5136.3     .12       0  6066.1     .07       0
  6200.6     .05       0
Bank Sta=4981.7,4998.4
XS Rating Curve= 0 ,0
Exp/Cntr=0.3,0.1

Type RM Length L Ch R = 1 ,64207   ,464,464,464
BEGIN DESCRIPTION:
EIGHTEENMILE CREEK 103.0
END DESCRIPTION:
XS GIS Cut Line= 3
      2463174.97     13498524.97        2462825.       13498125.
      2461624.99       13497825.
#Sta/Elev= 30
  4469.1  249.01  4780.8  239.86    4816  239.52  4844.4  241.04  4904.1  240.09
  4936.5  239.64  4958.3  236.08  5018.6  230.38  5033.3  227.17  5033.8  226.67
  5050.2  227.17  5093.3  230.91  5101.1  233.25  5106.2  237.74  5134.2   234.8
  5142.3  234.77  5147.4  241.66  5155.2  242.61  5165.5  240.75  5183.5  240.29
  5188.7  244.17  5196.4   241.9    5217  245.49    5243  245.65  5532.8  244.59
  5593.2  244.35  5633.4  244.49  5734.1  244.34  5972.1  244.87  6237.5  248.76
#Mann= 10 ,-1 , 0
  4469.1     .12       0  4904.1      .1       0  5033.3     .05       0
  5050.2      .1       0  5134.2     .12       0    5243     .05       0
  5532.8     .07       0  5593.2     .05       0  5633.4     .07       0
  5734.1     .05       0
Bank Sta=5033.3,5050.2
XS Rating Curve= 0 ,0
Exp/Cntr=0.3,0.1

Type RM Length L Ch R = 1 ,63743   ,473,473,473
BEGIN DESCRIPTION:
EIGHTEENMILE CREEK 102.0
END DESCRIPTION:
XS GIS Cut Line= 3
      2463513.78      13498482.5        2463125.       13497825.
      2461775.04       13497825.
#Sta/Elev= 30
  4241.9  253.27  4315.6  251.67  4330.1  251.49  4529.8   247.9  4705.4  246.83
  4800.9  245.06  4853.6  241.69  4875.1  241.76  4912.2     240  4933.2  237.93
  4947.7  236.04  4970.7  230.99  4983.6  225.97  4984.1  225.47  5000.6  225.97
  5002.8  230.69  5008.2  230.69  5015.7  232.64  5105.7  239.67  5137.5  240.27
    5304  241.15  5355.7  241.49  5485.7  244.75  5817.3  243.83  5915.6  243.72
  5935.7  244.49  5995.7   243.7  6222.2  244.77  6300.5  246.05  6355.7  247.43
#Mann= 12 ,-1 , 0
  4241.9    .035       0  4315.6     .07       0  4330.1     .05       0
  4933.2     .07       0  4983.6     .05       0  5000.6     .07       0
  5137.5     .05       0    5304     .12       0  5817.3     .07       0
  5915.6     .12       0  6222.2     .07       0  6300.5     .05       0
Bank Sta=4983.6,5000.6
XS Rating Curve= 0 ,0
Exp/Cntr=0.3,0.1

Type RM Length L Ch R = 1 ,63270   ,560,560,560
BEGIN DESCRIPTION:
EIGHTEENMILE CREEK 101.0
END DESCRIPTION:
XS GIS Cut Line= 3
      2463696.06     13498190.79        2463325.       13497425.
        2461675.       13497725.
#Sta/Elev= 30
  4154.8   249.1  4393.5  245.76  4616.7  240.52  4677.7  239.97  4839.2     239
  4850.2  239.92  4872.4  237.01  4939.1  235.48  4946.5  234.21  4952.1  229.17
  4961.3  227.77  4966.2  225.19  4966.7  224.69  4983.2  225.19  5008.3  228.25
  5015.9   232.5  5026.1  235.24  5073.8  234.65  5107.4  236.87  5149.3  236.24
  5249.7  240.69  5284.3  240.62  5524.1  239.74    5768  245.24  5859.5  243.47
  6022.1  244.78  6235.6  243.18  6475.4  245.23    6599  247.95  6682.8  248.88
#Mann= 9 ,-1 , 0
  4154.8     .12       0  4616.7     .07       0  4677.7     .12       0
  4966.2     .05       0  4983.2     .12       0  5073.8     .07       0
  5284.3     .12       0  6475.4     .07       0    6599     .05       0
Bank Sta=4966.2,4983.2
XS Rating Curve= 0 ,0
Exp/Cntr=0.3,0.1

Type RM Length L Ch R = 1 ,62710   ,562,562,562
BEGIN DESCRIPTION:
EIGHTEENMILE CREEK 100.0
END DESCRIPTION:
XS GIS Cut Line= 3
      2464275.01     13497675.01        2463525.       13496975.
      2462525.01     13495375.02
#Sta/Elev= 30
  3974.1  249.56  4071.7  247.89    4318   244.9  4343.9   244.6  4530.6  241.55
  4851.3  237.53  4907.9  232.73  4964.6  231.75  4978.8  228.69  4981.9  224.06
  4982.4  223.56    5004  224.06    5023  228.37  5028.9  231.72  5050.9  233.14
  5068.8  235.78  5107.9  237.97  5196.4  237.71  5238.8  238.88    5385  239.11
  5458.2  237.27  5616.2  240.52  5694.1   239.8  5862.6   239.5  6419.6  244.58
  6568.4   247.6  6626.8  250.18  6653.9  249.89  6826.2   256.2  6886.8  257.87
#Mann= 12 ,-1 , 0
  3974.1    .035       0  4071.7     .07       0    4318     .12       0
  4343.9     .07       0  4530.6     .12       0  4981.9     .05       0
    5004     .12       0  5050.9     .07       0  5068.8     .12       0
  5694.1     .05       0  6419.6     .07       0  6826.2    .035       0
Bank Sta=4981.9,5004
XS Rating Curve= 0 ,0
Exp/Cntr=0.3,0.1

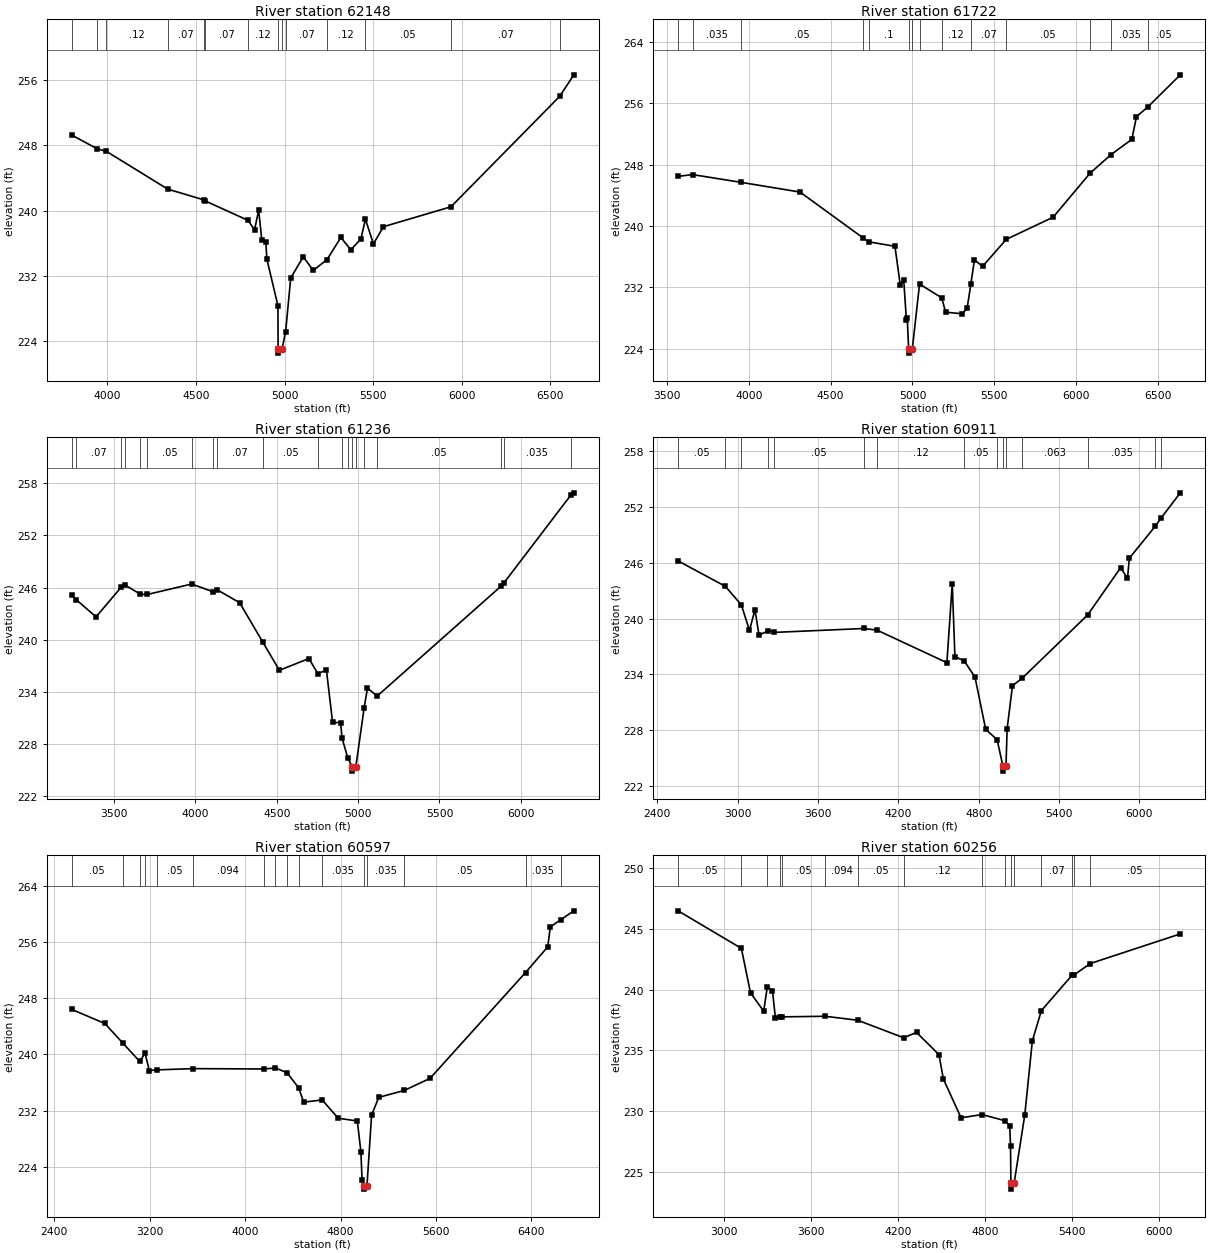
Type RM Length L Ch R = 1 ,62148   ,426,426,426
BEGIN DESCRIPTION:
EIGHTEENMILE CREEK 99.0
END DESCRIPTION:
XS GIS Cut Line= 3
      2464325.01     13497625.03        2463825.       13496525.
      2462674.98     13495374.98
#Sta/Elev= 30
  3798.3  249.27  3942.1  247.59  3994.3  247.27  4340.4  242.63  4542.9  241.32
  4551.9  241.18  4793.9  238.79  4830.9  237.63  4853.9  240.05  4871.5  236.42
  4894.6  236.16  4900.1  234.04  4962.7  228.31  4963.7  222.98  4964.2  222.48
  4985.8  222.98  5006.2  225.12  5034.9  231.71  5105.6  234.31  5162.2  232.64
  5240.2  233.98  5317.8  236.69  5374.3  235.18  5430.9   236.5  5456.6  238.93
  5501.6   235.9  5558.2  238.01  5939.5  240.46  6553.2  254.03    6633  256.67
#Mann= 14 ,-1 , 0
  3798.3    .035       0  3942.1     .07       0  3994.3     .12       0
  4340.4     .07       0  4542.9     .12       0  4551.9     .07       0
  4793.9     .12       0  4963.7     .05       0  4985.8     .12       0
  5006.2     .07       0  5240.2     .12       0  5456.6     .05       0
  5939.5     .07       0  6553.2    .035       0
Bank Sta=4963.7,4985.8
XS Rating Curve= 0 ,0
Exp/Cntr=0.3,0.1

Type RM Length L Ch R = 1 ,61722   ,486,486,486
BEGIN DESCRIPTION:
Mapping XS 73b1bfb8
END DESCRIPTION:
XS GIS Cut Line= 4
       2465026.1     13497045.24      2464520.87     13496362.92
      2463648.54       13496034.      2462711.78     13495149.28
#Sta/Elev= 30
  3567.6  246.48  3655.7  246.71    3955  245.69  4312.8  244.43  4697.5  238.46
  4731.6  237.94  4893.1  237.35  4925.2  232.35  4946.6     233    4963  227.74
  4968.3  227.95  4976.8  223.91  4977.3  223.41    4999  223.91  5043.4  232.43
  5178.6  230.63  5203.1  228.75  5304.1  228.55  5334.3  229.27  5356.9  232.41
  5379.1  235.59  5428.5  234.72  5573.1  238.25  5860.1  241.15  6085.6  246.89
  6214.6  249.33  6341.2  251.31  6369.5  254.27  6438.9  255.54  6637.4  259.73
#Mann= 14 ,-1 , 0
  3567.6     .07       0  3655.7    .035       0    3955     .05       0
  4697.5     .07       0  4731.6      .1       0  4976.8     .05       0
    4999      .1       0  5043.4     .07       0  5178.6     .12       0
  5356.9     .07       0  5573.1     .05       0  6085.6     .07       0
  6214.6    .035       0  6438.9     .05       0
Bank Sta=4976.8,4999
XS Rating Curve= 0 ,0
Exp/Cntr=0.3,0.1

Type RM Length L Ch R = 1 ,61236   ,325,325,325
BEGIN DESCRIPTION:
Mapping XS 12b1d60a
END DESCRIPTION:
XS GIS Cut Line= 4
      2465453.19     13496675.43      2464140.66     13495763.96
      2463260.45     13495545.21      2462833.71     13495149.69
#Sta/Elev= 30
  3239.2  245.15  3266.2  244.62  3389.1  242.62  3544.8  246.06  3568.8  246.27
  3662.2  245.22  3704.3   245.2    3977   246.4  4109.6   245.5  4131.6  245.76
  4271.8  244.25  4415.3  239.68  4516.2  236.48  4697.9  237.83  4752.5  236.08
  4805.2  236.52    4843   230.5  4892.2  230.44  4901.5  228.66  4936.6  226.39
  4963.7  225.38  4964.2  224.88    4986  225.38  5037.2  232.18  5057.6  234.43
    5117  233.51    5879  246.16    5894  246.47  6309.6  256.68    6326  256.89
#Mann= 20 ,-1 , 0
  3239.2     .05       0  3266.2     .07       0  3544.8    .035       0
  3568.8    .063       0  3662.2    .035       0  3704.3     .05       0
    3977     .07       0  4109.6     .12       0  4131.6     .07       0
  4415.3     .05       0  4752.5     .07       0  4901.5     .05       0
  4936.6      .1       0  4963.7     .05       0    4986      .1       0
  5037.2     .12       0    5117     .05       0    5879     .07       0
    5894    .035       0  6309.6     .05       0
Bank Sta=4963.7,4986
XS Rating Curve= 0 ,0
Exp/Cntr=0.3,0.1

Type RM Length L Ch R = 1 ,60911   ,314,314,314
BEGIN DESCRIPTION:
Mapping XS 609da5bf
END DESCRIPTION:
XS GIS Cut Line= 4
      2465644.66     13496469.88      2465457.16     13495421.25
      2463269.66     13495435.14      2462950.23     13495053.21
#Sta/Elev= 30
    2555   246.2  2907.5  243.47    3027  241.48    3088  238.73  3128.8  240.95
  3159.3  238.22  3228.4  238.68  3273.8  238.51  3942.9  238.93  4041.2  238.75
  4562.4  235.25  4602.4  243.74  4622.4  235.89  4691.2  235.46  4772.4  233.69
  4852.4  228.07  4937.5  226.97  4981.3  224.08  4981.8  223.58  5003.6  224.08
  5012.4  228.16  5052.4  232.78  5122.8  233.55  5614.4   240.4  5860.3  245.48
  5911.1  244.32  5925.3   246.5    6119  249.94  6162.9  250.83  6305.7  253.53
#Mann= 15 ,-1 , 0
    2555     .05       0  2907.5    .035       0    3027    .063       0
  3228.4    .035       0  3273.8     .05       0  3942.9    .063       0
  4041.2     .12       0  4691.2     .05       0  4937.5     .12       0
  4981.3     .05       0  5003.6     .12       0  5122.8    .063       0
  5614.4    .035       0    6119     .05       0  6162.9    .035       0
Bank Sta=4981.3,5003.6
XS Rating Curve= 0 ,0
Exp/Cntr=0.3,0.1

Type RM Length L Ch R = 1 ,60597   ,341,341,341
BEGIN DESCRIPTION:
Mapping XS 8ca2da14
END DESCRIPTION:
XS GIS Cut Line= 4
      2465679.38     13496421.26      2465540.49     13495219.86
      2463241.88     13495192.08      2462734.95     13494705.99
#Sta/Elev= 30
  2545.2  246.43  2823.3  244.42  2972.3  241.66  3115.9  239.01  3161.1  240.17
  3195.8  237.71  3260.7   237.8  3559.5  237.98  4154.6  237.93  4252.9  238.07
  4351.2   237.4  4449.5  235.21  4490.1   233.2    4646  233.51  4780.2   230.9
  4940.2  230.51  4970.2  226.15  4980.2  222.12    4999  221.29  4999.5  220.79
  5021.3  221.29  5060.2  231.36  5120.2  233.88    5334  234.87  5550.2  236.59
  6350.8  251.69    6537  255.36  6558.4   258.2  6645.8  259.22  6755.7  260.49
#Mann= 16 ,-1 , 0
  2545.2     .05       0  2972.3    .035       0  3115.9    .063       0
  3161.1    .035       0  3260.7     .05       0  3559.5    .094       0
  4154.6    .063       0  4252.9    .094       0  4351.2    .063       0
  4449.5    .094       0    4646    .035       0    4999    .035       0
  5021.3    .035       0    5334     .05       0  6350.8    .035       0
  6645.8     .05       0
Bank Sta=4999,5021.3
XS Rating Curve= 0 ,0
Exp/Cntr=0.3,0.1

Type RM Length L Ch R = 1 ,60256   ,1119,1119,1119
BEGIN DESCRIPTION:
Mapping XS eea3ee56
END DESCRIPTION:
XS GIS Cut Line= 4
      2465705.15     13496419.54      2465544.74      13495140.7
      2464542.14     13494967.08       2463526.1     13494425.43
#Sta/Elev= 30
  2686.8  246.49  3122.3   243.4  3185.2  239.74  3275.9  238.23  3301.2  240.25
  3336.4  239.91  3356.6   237.7  3390.2  237.74  3400.9  237.76  3700.1  237.81
  3924.2  237.48  4239.7  236.04  4328.5  236.48  4482.8  234.65  4513.3  232.64
  4635.1  229.45  4778.9  229.72  4934.9  229.22    4970  228.79  4975.6  227.15
    4978  224.08  4978.5  223.58  5000.5  224.08  5073.5  229.67  5125.9  235.79
  5188.2  238.28  5397.8  241.17  5414.8  241.23  5524.5  242.15  6144.6  244.59
#Mann= 16 ,-1 , 0
  2686.8     .05       0  3122.3    .035       0  3301.2    .063       0
  3390.2    .035       0  3400.9     .05       0  3700.1    .094       0
  3924.2     .05       0  4239.7     .12       0  4778.9     .07       0
  4934.9      .1       0    4978     .05       0  5000.5      .1       0
  5188.2     .07       0  5397.8      .1       0  5414.8     .07       0
  5524.5     .05       0
Bank Sta=4978,5000.5
XS Rating Curve= 0 ,0
Exp/Cntr=0.3,0.1

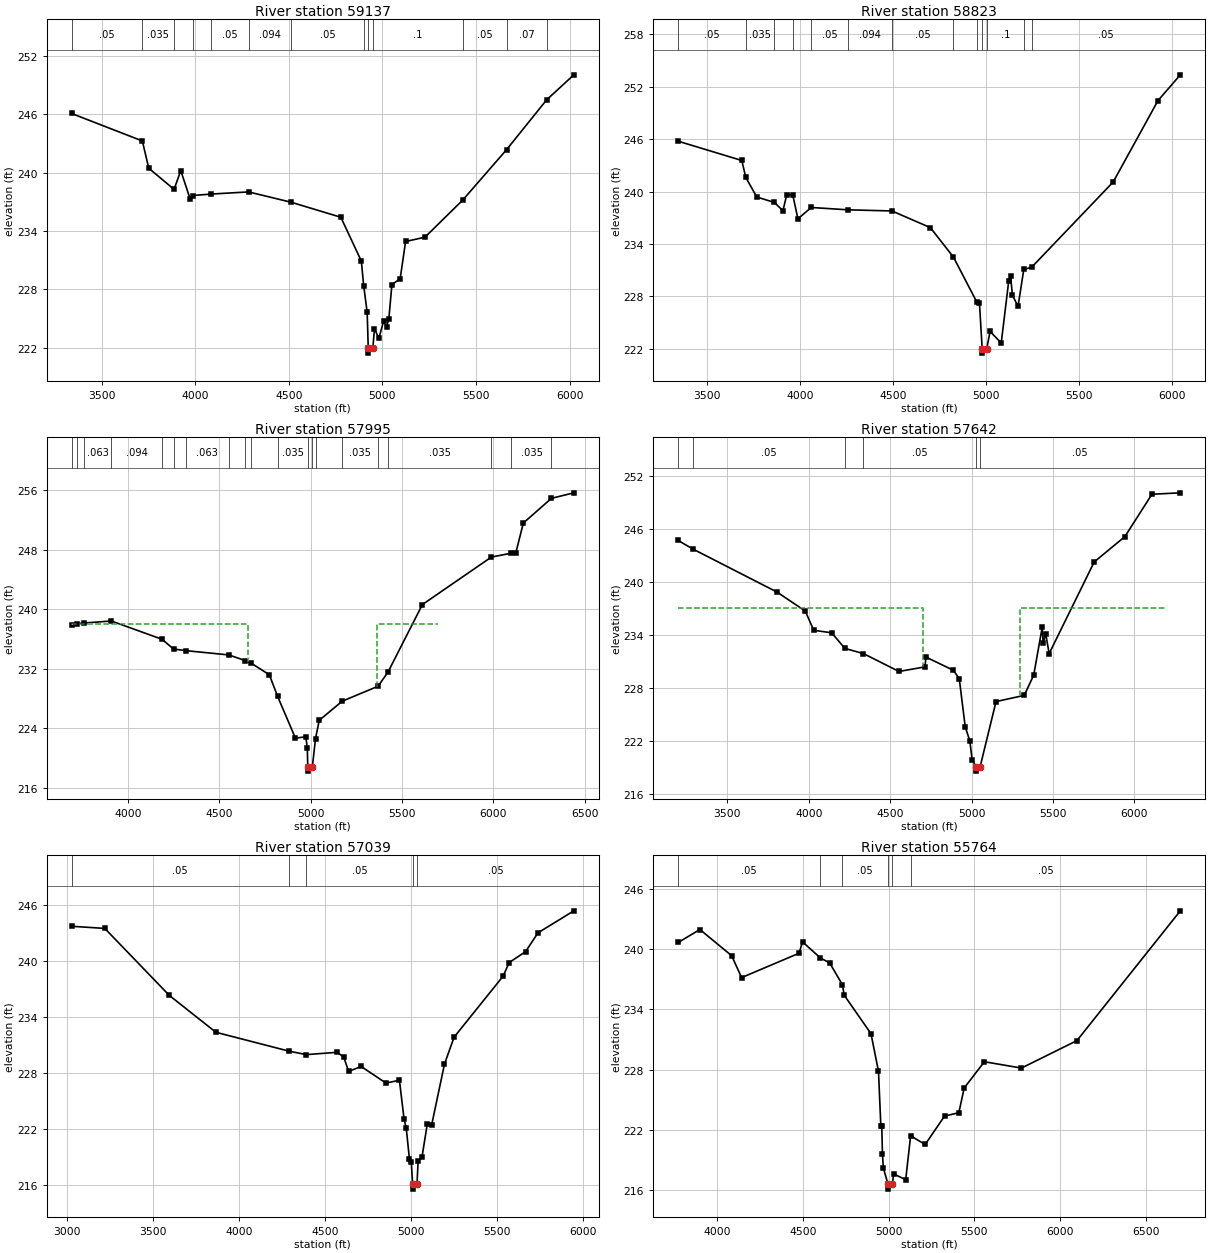
Type RM Length L Ch R = 1 ,59137   ,314,314,314
BEGIN DESCRIPTION:
Mapping XS 5663a5fc
END DESCRIPTION:
XS GIS Cut Line= 5
      2465710.35      13496354.4      2465614.68     13495486.73
       2465586.5     13495142.26      2465440.66     13494718.65
      2464968.44     13493819.35
#Sta/Elev= 30
  3340.3  246.06  3717.9  243.24  3752.2  240.44  3887.4  238.27  3923.2   240.2
  3973.5  237.26  3986.9  237.64  4086.4  237.79  4285.2  238.01  4512.5  236.95
    4778  235.41  4887.6  230.91  4900.1  228.39  4918.8  225.64  4924.5  221.96
    4925  221.46  4948.9  221.96  4957.8  223.97  4981.2  222.97  5006.1  224.72
  5022.3  224.16  5034.5     225  5050.9   228.5    5095  229.09  5123.9  232.92
  5227.3  233.36  5428.6  237.16    5663  242.34  5877.2  247.46  6022.6  250.03
#Mann= 13 ,-1 , 0
  3340.3     .05       0  3717.9    .035       0  3887.4    .063       0
  3986.9    .035       0  4086.4     .05       0  4285.2    .094       0
  4512.5     .05       0  4900.1      .1       0  4924.5     .05       0
  4948.9      .1       0  5428.6     .05       0    5663     .07       0
  5877.2     .05       0
Bank Sta=4924.5,4948.9
XS Rating Curve= 0 ,0
Exp/Cntr=0.3,0.1

Type RM Length L Ch R = 1 ,58823   ,828,828,828
BEGIN DESCRIPTION:
Mapping XS 5d9f2f11
END DESCRIPTION:
XS GIS Cut Line= 4
      2465736.39     13496325.75      2465658.18     13495513.25
      2465704.55      13494711.7      2465780.94     13493635.35
#Sta/Elev= 30
  3343.9  245.78  3686.2  243.57  3707.4  241.63  3766.6  239.39  3860.4  238.77
  3907.2  237.82  3927.3  239.64  3959.7  239.65  3987.6  236.89  4059.1  238.19
    4257  237.92  4492.9  237.79  4699.3  235.88  4823.4   232.5  4947.2  227.42
    4963  227.23  4977.6  222.01  4978.1  221.51    5002  222.01  5019.9  223.99
    5080  222.68  5120.1  229.75  5130.2  230.29  5140.2  228.14  5170.3  226.86
  5201.1   231.1  5243.2  231.34  5681.5  241.11  5922.2  250.43  6042.1  253.38
#Mann= 13 ,-1 , 0
  3343.9     .05       0  3707.4    .035       0  3860.4    .063       0
  3959.7    .035       0  4059.1     .05       0    4257    .094       0
  4492.9     .05       0  4823.4     .12       0  4947.2      .1       0
  4977.6     .05       0    5002      .1       0  5201.1     .07       0
  5243.2     .05       0
Bank Sta=4977.6,5002
XS Rating Curve= 0 ,0
Exp/Cntr=0.3,0.1

Type RM Length L Ch R = 1 ,57995   ,353,353,353
BEGIN DESCRIPTION:
Mapping XS 30a2d2cf
END DESCRIPTION:
XS GIS Cut Line= 2
      2465681.96     13495640.03      2467273.16     13493398.85
#Sta/Elev= 30
  3692.4  237.93  3723.3  238.08  3757.7  238.15  3909.5  238.43  4186.8  235.97
  4249.9  234.66    4316  234.44    4553  233.86  4642.2   233.1  4671.5  232.81
  4774.5  231.19  4819.1  228.31  4917.1  222.66    4974  222.84  4982.4  221.29
  4984.7  218.72  4985.2  218.22  5009.5  218.72  5027.1  222.61  5047.6  225.06
    5173  227.63  5369.7  229.65  5423.8  231.55  5612.1  240.64  5989.5  247.03
  6099.5  247.56  6122.7  247.52  6164.5  251.61  6318.4  254.94    6441  255.68
#Mann= 20 ,-1 , 0
  3692.4    .035       0  3723.3     .05       0  3757.7    .063       0
  3909.5    .094       0  4186.8    .063       0  4249.9    .094       0
    4316    .063       0    4553    .035       0  4642.2    .063       0
  4671.5    .035       0  4819.1    .035       0  4984.7    .035       0
  5009.5    .035       0  5027.1    .063       0    5173    .035       0
  5369.7     .07       0  5423.8    .035       0  5989.5     .05       0
  6099.5    .035       0  6318.4     .05       0
#XS Ineff= 2 ,-1
    3692    4660     238    5361    5700     238
Permanent Ineff=
       F       F
Bank Sta=4984.7,5009.5
XS Rating Curve= 0 ,0
Exp/Cntr=0.3,0.1

Type RM Length L Ch R = 1 ,57642   ,603,603,603
BEGIN DESCRIPTION:
Mapping XS 934429d8
END DESCRIPTION:
XS GIS Cut Line= 3
      2466100.36     13496286.64      2466086.47     13495765.77
      2467433.68     13493585.23
#Sta/Elev= 30
  3197.6  244.68  3288.1  243.71  3804.6  238.84  3978.4  236.69  4030.4  234.51
  4140.4  234.23    4222  232.46  4335.9  231.87  4554.1  229.85  4713.8  230.37
  4719.6  231.48  4887.5  229.99  4924.2  229.04  4960.9  223.58  4989.1  221.99
  5003.4  219.86  5027.6  219.07  5028.1  218.57  5052.5  219.07    5150  226.44
  5323.8  227.15  5381.7  229.45  5433.8  234.87  5439.6  233.02    5455  234.13
  5476.3  231.87  5753.1  242.25  5941.2  245.11  6107.6  249.91  6281.8  250.07
#Mann= 6 ,-1 , 0
  3197.6    .035       0  3288.1     .05       0    4222    .094       0
  4335.9     .05       0  5027.6     .05       0  5052.5     .05       0
#XS Ineff= 2 ,-1
    3197    4700     237    5300    6197     237
Permanent Ineff=
       F       F
Bank Sta=5027.6,5052.5
XS Rating Curve= 0 ,0
Exp/Cntr=0.3,0.1

Type RM Length L Ch R = 1 ,57039   ,1275,1275,1275
BEGIN DESCRIPTION:
Mapping XS d031ee74
END DESCRIPTION:
XS GIS Cut Line= 3
       2466740.1     13496569.93      2467267.88     13494750.49
      2467538.72     13493764.34
#Sta/Elev= 30
  3027.3  243.75  3219.8  243.52  3594.7  236.32  3865.4  232.36  4288.4  230.34
  4390.3  229.96  4569.3  230.21  4608.1   229.7  4635.9  228.15  4708.8  228.69
  4853.5   226.9  4931.2  227.21  4958.5     223  4970.8  222.07  4989.7   218.7
    5000  218.43  5008.3  216.01  5008.8  215.51  5033.3  216.01  5039.7  218.48
  5062.2  218.93  5093.4  222.55  5118.9  222.44    5193  228.94  5248.9  231.84
    5534   238.4  5568.4  239.85  5663.7  241.02  5736.3  243.05  5944.4  245.41
#Mann= 5 ,-1 , 0
  3027.3     .05       0  4288.4    .035       0  4390.3     .05       0
  5008.3     .05       0  5033.3     .05       0
Bank Sta=5008.3,5033.3
XS Rating Curve= 0 ,0
Exp/Cntr=0.3,0.1

Type RM Length L Ch R = 1 ,55764   ,728,728,728
BEGIN DESCRIPTION:
Mapping XS c5eccaf3
END DESCRIPTION:
XS GIS Cut Line= 4
      2467433.71     13496342.14      2468148.97     13495397.71
      2468176.75     13495168.55      2467739.26      13493717.2
#Sta/Elev= 30
  3771.7  240.65  3898.9  241.94  4084.1  239.34  4142.3  237.16  4477.3  239.58
  4498.1  240.71  4602.5  239.11  4656.2  238.62  4730.2  236.47  4741.5   235.4
  4897.6  231.58  4941.3  227.84    4955  222.42  4960.3  222.42  4964.6  219.57
  4969.6  218.22  4996.9  216.62  4997.4  216.12  5022.2  216.62  5029.7  217.63
  5100.2  217.06  5128.9  221.42  5213.9  220.56  5326.7  223.38  5410.3  223.72
  5441.6  226.18  5559.4  228.79  5775.8  228.16  6099.6  230.89  6703.1   243.8
#Mann= 6 ,-1 , 0
  3771.7     .05       0  4602.5    .035       0  4730.2     .05       0
  4996.9     .05       0  5022.2     .05       0  5128.9     .05       0
Bank Sta=4996.9,5022.2
XS Rating Curve= 0 ,0
Exp/Cntr=0.3,0.1

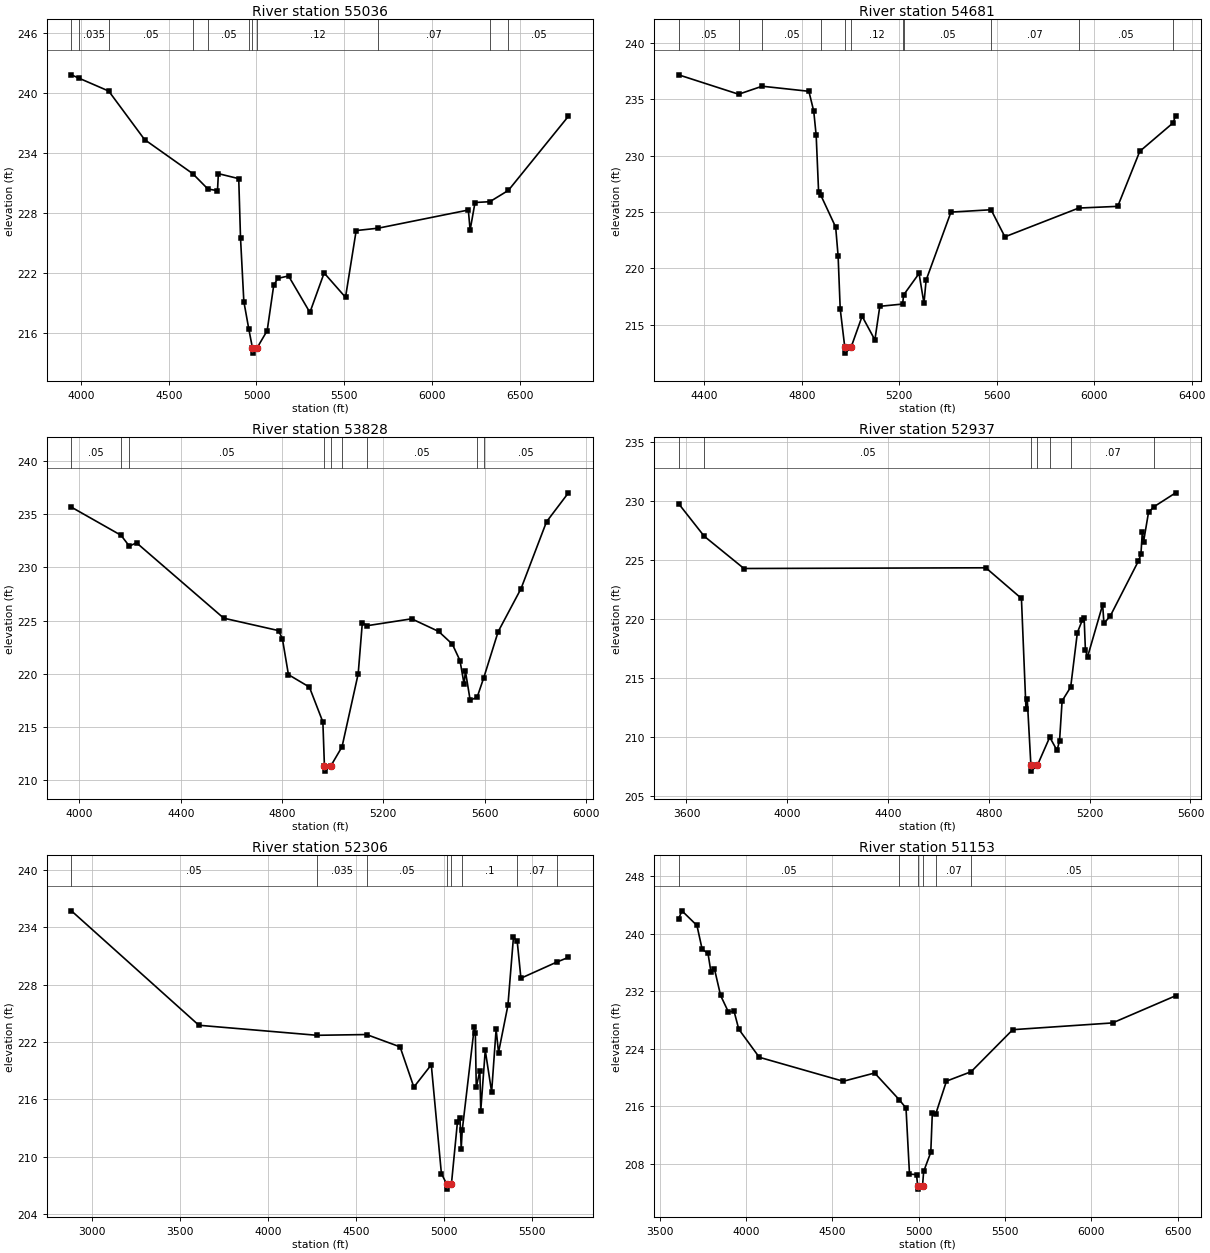
Type RM Length L Ch R = 1 ,55036   ,355,355,355
BEGIN DESCRIPTION:
Mapping XS 1c79b839
END DESCRIPTION:
XS GIS Cut Line= 3
       2468669.8     13496571.33      2468787.86     13495592.16
       2468482.3      13493772.7
#Sta/Elev= 30
  3945.8  241.81    3987  241.49  4158.4  240.19  4362.6  235.35  4636.8  231.95
  4723.1  230.42    4778  230.25    4783  231.95    4899  231.45  4909.1  225.55
  4928.1  219.19  4956.5  216.43  4977.3  214.54  4977.8  214.04  5002.7  214.54
    5061  216.28  5098.4  220.82  5121.8   221.5  5182.7  221.74  5304.4   218.1
  5385.5  222.04  5507.2  219.61    5568  226.27  5694.2  226.51  6206.8  228.32
    6217  226.32  6244.9  229.07  6329.3  229.15    6435  230.28    6777  237.68
#Mann= 11 ,-1 , 0
  3945.8     .05       0    3987    .035       0  4158.4     .05       0
  4636.8    .035       0  4723.1     .05       0  4956.5     .12       0
  4977.3     .05       0  5002.7     .12       0  5694.2     .07       0
  6329.3     .12       0    6435     .05       0
Bank Sta=4977.3,5002.7
XS Rating Curve= 0 ,0
Exp/Cntr=0.3,0.1

Type RM Length L Ch R = 1 ,54681   ,853,853,853
BEGIN DESCRIPTION:
Mapping XS cda4bf33
END DESCRIPTION:
XS GIS Cut Line= 3
      2469105.96     13496079.05      2469079.91     13495410.63
      2468923.79     13494048.87
#Sta/Elev= 30
  4294.8  237.16  4541.2  235.44  4637.5  236.15  4829.3   235.7  4849.3  233.94
  4859.3  231.79  4869.3  226.75  4877.2  226.54  4939.3  223.66  4949.3   221.1
  4957.9  216.41  4976.8  212.99  4977.3  212.49  5002.2  212.99  5047.8  215.76
  5100.2  213.66  5120.4  216.64  5213.9  216.84  5218.2  217.65  5281.4  219.55
  5301.6   216.9  5310.4  218.96  5412.3  224.99    5577   225.2  5633.7   222.8
  5936.6  225.35  6096.7   225.5  6187.2  230.38  6322.8  232.88  6334.4  233.52
#Mann= 11 ,-1 , 0
  4294.8     .05       0  4541.2    .035       0  4637.5     .05       0
  4877.2     .12       0  4976.8     .05       0  5002.2     .12       0
  5213.9     .07       0  5218.2     .05       0    5577     .07       0
  5936.6     .05       0  6322.8    .035       0
Bank Sta=4976.8,5002.2
XS Rating Curve= 0 ,0
Exp/Cntr=0.3,0.1

Type RM Length L Ch R = 1 ,53828   ,891,891,891
BEGIN DESCRIPTION:
Mapping XS 724a5ac2
END DESCRIPTION:
XS GIS Cut Line= 3
      2469253.54     13495931.44      2469635.47     13495002.65
      2469730.85     13494048.85
#Sta/Elev= 30
  3968.1  235.68  4164.1  233.03  4196.8  232.01  4225.4  232.32  4569.7  225.22
    4786  224.05  4801.2   223.3  4825.2   219.9  4907.9  218.73  4961.2  215.44
  4967.3  211.31  4967.8  210.81  4992.8  211.31  5036.8   213.1  5100.6  219.97
    5117  224.79  5135.6  224.51  5311.7  225.16  5418.5  223.97  5472.5  222.77
  5502.6  221.23    5519     219  5524.1  220.24  5542.8  217.49  5570.4  217.77
  5596.8  219.63  5653.4  223.95  5743.8  228.01  5844.3   234.3  5930.9  237.03
#Mann= 9 ,-1 , 0
  3968.1     .05       0  4164.1    .035       0  4196.8     .05       0
  4967.3     .05       0  4992.8     .05       0  5036.8      .1       0
  5135.6     .05       0  5570.4     .12       0  5596.8     .05       0
Bank Sta=4967.3,4992.8
XS Rating Curve= 0 ,0
Exp/Cntr=0.3,0.1

Type RM Length L Ch R = 1 ,52937   ,631,631,631
BEGIN DESCRIPTION:
Mapping XS 9697fffc
END DESCRIPTION:
XS GIS Cut Line= 3
      2469435.81     13495688.42      2470373.32     13494976.61
      2470477.26     13494188.34
#Sta/Elev= 30
    3569  229.79  3670.5  227.03  3828.2  224.29  4788.1  224.35  4929.3  221.75
  4947.3  212.37  4952.4  213.19  4966.8   207.6  4967.3   207.1  4992.7   207.6
  5041.6  209.98  5070.5  208.86  5080.6  209.69  5090.7  213.06  5124.7  214.23
  5151.2  218.85  5171.4  219.94    5178   220.1  5183.1   217.4  5191.5  216.78
  5251.6  221.22  5256.6  219.63  5282.3  220.28  5393.3  224.92  5403.4  225.48
  5408.8  227.36  5413.8  226.55  5433.6  229.06  5455.8  229.54  5541.2  230.71
#Mann= 7 ,-1 , 0
    3569    .035       0  3670.5     .05       0  4966.8     .05       0
  4992.7     .05       0  5041.6      .1       0  5124.7     .07       0
  5455.8     .05       0
Bank Sta=4966.8,4992.7
XS Rating Curve= 0 ,0
Exp/Cntr=0.3,0.1

Type RM Length L Ch R = 1 ,52306   ,1153,1153,1153
BEGIN DESCRIPTION:
Mapping XS 7cc962d5
END DESCRIPTION:
XS GIS Cut Line= 3
      2469251.22     13496230.36      2470904.02     13494886.59
      2471136.66     13494230.34
#Sta/Elev= 30
  2882.4  235.72  3607.4  223.75    4279   222.7  4560.9  222.78  4751.5  221.49
  4829.8  217.28  4928.9  219.62  4986.4  208.24  5017.2  207.11  5017.7  206.61
  5043.3  207.11  5077.9  213.68    5092  214.07  5099.1  210.85  5104.8  212.75
  5173.4  223.52  5179.4  222.96  5184.7  217.26    5205  218.98  5210.3  214.83
  5235.8  221.13    5272  216.77  5297.6  223.33  5311.3   220.9  5364.7  225.83
  5396.2  232.96  5417.5  232.54  5438.6  228.67  5645.1  230.38  5708.8  230.85
#Mann= 8 ,-1 , 0
  2882.4     .05       0    4279    .035       0  4560.9     .05       0
  5017.2     .05       0  5043.3     .05       0  5104.8      .1       0
  5417.5     .07       0  5645.1     .05       0
Bank Sta=5017.2,5043.3
XS Rating Curve= 0 ,0
Exp/Cntr=0.3,0.1

Type RM Length L Ch R = 1 ,51153   ,867,867,867
BEGIN DESCRIPTION:
Mapping XS c832097c
END DESCRIPTION:
XS GIS Cut Line= 3
      2471447.58     13496960.23      2471628.14     13495612.99
      2471253.14     13494140.78
#Sta/Elev= 30
  3609.2  242.06  3628.5  243.17  3715.4  241.13  3745.6  237.81  3779.5  237.25
  3796.1   234.7  3816.3  235.13  3852.4  231.39    3897  229.12  3930.4  229.19
  3957.5   226.7  4076.3  222.79  4562.9  219.45  4744.5   220.6  4886.9  216.88
  4926.1  215.72  4946.3  206.53    4987  206.46  4993.4  204.94  4993.9  204.44
  5021.9  204.94  5028.3   206.9  5069.6  209.56  5078.6  215.08  5098.2  214.89
  5160.4  219.47  5303.2  220.78  5544.3  226.63  6122.2  227.57  6487.7  231.35
#Mann= 6 ,-1 , 0
  3609.2     .05       0  4886.9      .1       0  4993.4     .05       0
  5021.9      .1       0  5098.2     .07       0  5303.2     .05       0
Bank Sta=4993.4,5021.9
XS Rating Curve= 0 ,0
Exp/Cntr=0.3,0.1

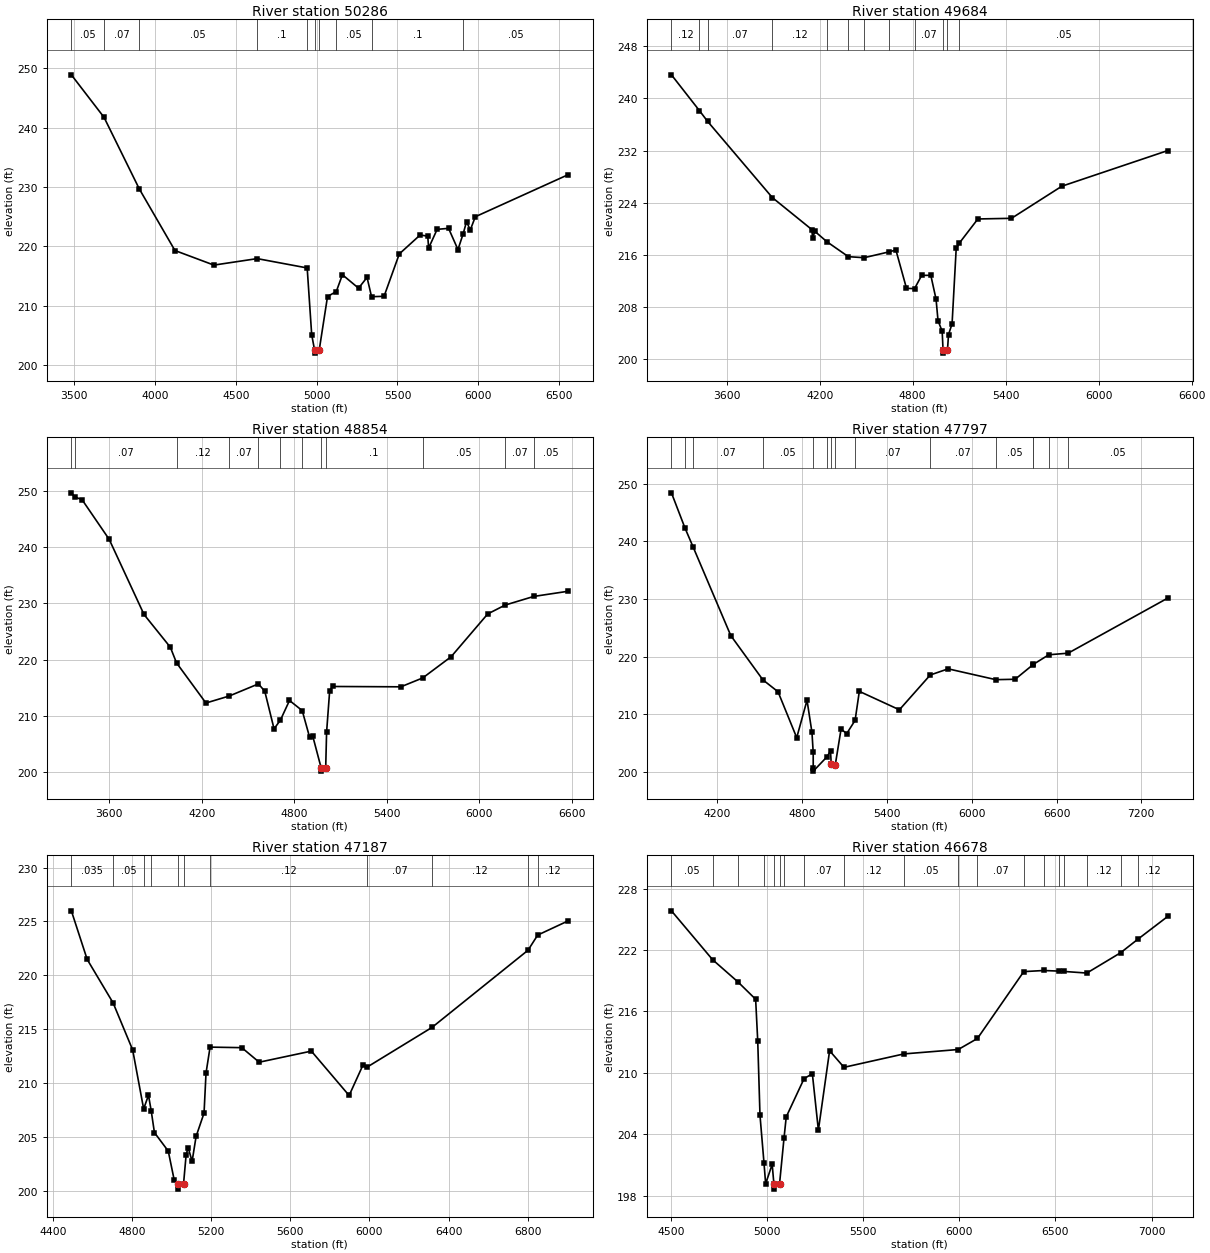
Type RM Length L Ch R = 1 ,50286   ,602,602,602
BEGIN DESCRIPTION:
Mapping XS 1570e77c
END DESCRIPTION:
XS GIS Cut Line= 3
      2472579.52     13496953.24      2472468.41     13495633.82
      2471780.98     13494029.81
#Sta/Elev= 30
  3483.5  248.86  3685.6  241.71  3903.7  229.67    4124  219.32  4364.9  216.87
  4632.4  217.96  4941.6  216.39  4969.5  205.17  4987.4  202.57  4987.9  202.07
  5015.9  202.57  5067.4  211.59  5121.5  212.42  5159.4  215.25  5259.2  212.99
  5311.7   214.8  5339.6  211.56  5416.9  211.62  5511.2  218.75    5640  221.93
  5687.1  221.74  5692.5  219.73  5745.1  222.88  5815.8  223.05  5873.9  219.48
  5906.1  222.14  5926.9  224.17    5950  222.77  5981.3     225  6552.7  232.04
#Mann= 10 ,-1 , 0
  3483.5     .05       0  3685.6     .07       0  3903.7     .05       0
  4632.4      .1       0  4941.6     .07       0  4987.4     .05       0
  5015.9     .07       0  5121.5     .05       0  5339.6      .1       0
  5906.1     .05       0
Bank Sta=4987.4,5015.9
XS Rating Curve= 0 ,0
Exp/Cntr=0.3,0.1

Type RM Length L Ch R = 1 ,49684   ,830,830,830
BEGIN DESCRIPTION:
Mapping XS cd0aa22f
END DESCRIPTION:
XS GIS Cut Line= 3
      2473294.81     13496939.43      2472926.75     13495258.82
      2472468.57     13493849.57
#Sta/Elev= 30
  3243.9  243.62  3424.8  238.12  3477.6  236.47  3894.7   224.8  4149.3   219.9
  4154.5  218.64  4169.8  219.61  4246.3  218.04  4385.2  215.74  4486.8  215.58
    4645  216.46  4691.9  216.76  4760.3  210.88  4812.3  210.84  4858.2  212.87
  4917.1  212.88    4951  209.22  4963.7  205.92  4990.4  204.31  4996.1  201.45
  4996.6  200.95  5024.8  201.45  5031.4   203.8  5054.3  205.44    5081  217.01
  5100.2  217.79  5220.7  221.52  5437.6  221.62  5762.3  226.54  6446.2  232.01
#Mann= 12 ,-1 , 0
  3243.9     .12       0  3424.8      .1       0  3477.6     .07       0
  3894.7     .12       0  4246.3      .1       0  4385.2     .07       0
  4486.8     .12       0    4645     .05       0  4812.3     .07       0
  4996.1     .05       0  5024.8     .07       0  5100.2     .05       0
Bank Sta=4996.1,5024.8
XS Rating Curve= 0 ,0
Exp/Cntr=0.3,0.1

Type RM Length L Ch R = 1 ,48854   ,1057,1057,1057
BEGIN DESCRIPTION:
Mapping XS 2a817505
END DESCRIPTION:
XS GIS Cut Line= 4
      2473496.19     13496814.37      2473628.14     13495460.21
      2473662.86     13495015.77      2473010.41     13493759.45
#Sta/Elev= 30
  3353.1  249.66    3375  248.94  3422.8  248.43  3598.6  241.39  3824.7  228.03
  3995.5  222.21  4035.7  219.43  4226.6  212.29  4378.4  213.54  4567.3  215.69
  4608.4  214.39  4668.7   207.7  4709.9  209.24    4769  212.74  4851.6  210.94
  4899.4  206.22  4919.5  206.45  4975.2  200.68  4975.7  200.18  5003.9  200.68
  5009.8  207.11  5029.8  214.47  5049.9  215.23  5491.9  215.17  5633.9  216.75
  5818.1  220.52  6055.7  228.13  6168.4   229.7  6354.5  231.24  6575.1  232.15
#Mann= 12 ,-1 , 0
  3353.1     .12       0    3375     .07       0  4035.7     .12       0
  4378.4     .07       0  4567.3     .12       0  4709.9    .035       0
  4851.6      .1       0  4975.2     .05       0  5003.9      .1       0
  5633.9     .05       0  6168.4     .07       0  6354.5     .05       0
Bank Sta=4975.2,5003.9
XS Rating Curve= 0 ,0
Exp/Cntr=0.3,0.1

Type RM Length L Ch R = 1 ,47797   ,610,610,610
BEGIN DESCRIPTION:
Mapping XS 437d930c
END DESCRIPTION:
XS GIS Cut Line= 4
       2473822.6     13496807.41      2474385.08     13495869.94
      2474447.58     13495446.32      2473552.11     13493669.26
#Sta/Elev= 30
  3876.1  248.45    3972  242.33  4028.7  239.09  4295.8  223.67  4522.9  215.98
  4630.1  213.91  4762.3  205.94  4835.2  212.44  4870.2  206.84  4878.9  203.37
  4879.1  200.63  4879.6  200.13  4976.8  202.63  5001.3  203.62  5006.4  201.42
    5035  201.21    5076  207.43  5115.9  206.64  5175.3  208.95  5205.2  213.98
  5488.6  210.78  5706.8  216.82  5833.4  217.89  6170.8  216.01  6307.5  216.08
  6434.7  218.63    6435  218.65  6545.2  220.33  6682.3  220.61  7387.5  230.18
#Mann= 15 ,-1 , 0
  3876.1     .07       0    3972     .05       0  4028.7     .07       0
  4522.9     .05       0  4879.1     .05       0  4976.8     .05       0
  5006.4     .05       0    5035     .05       0  5175.3     .07       0
  5706.8     .07       0  6170.8     .05       0  6434.7     .12       0
    6435     .05       0  6545.2      .1       0  6682.3     .05       0
Bank Sta=5006.4,5035
XS Rating Curve= 0 ,0
Exp/Cntr=0.3,0.1

Type RM Length L Ch R = 1 ,47187   ,509,509,509
BEGIN DESCRIPTION:
EIGHTEENMILE CREEK 78.0
END DESCRIPTION:
XS GIS Cut Line= 3
        2474875.     13496675.02        2474875.       13496175.
        2474675.       13494175.
#Sta/Elev= 30
  4492.5  225.99  4572.5  221.48  4703.7  217.44  4802.5  213.08  4858.1   207.6
  4882.5  208.88  4896.6  207.39  4912.5  205.41  4982.5  203.69  5012.6     201
  5030.7  200.66  5031.2  200.16  5059.8  200.66  5072.9  203.36    5083  204.02
  5103.1  202.74  5123.2  205.05  5163.4  207.22  5173.4  210.93  5193.9  213.34
  5354.3  213.29  5442.3  211.94  5706.1  212.97    5897  208.85  5967.4  211.69
  5989.3   211.5  6316.2  215.17  6801.5  222.33  6850.6  223.74  7002.5  225.04
#Mann= 11 ,-1 , 0
  4492.5    .035       0  4703.7     .05       0  4858.1     .12       0
  4896.6     .05       0  5030.7     .05       0  5059.8     .05       0
  5193.9     .12       0  5989.3     .07       0  6316.2     .12       0
  6801.5     .07       0  6850.6     .12       0
Bank Sta=5030.7,5059.8
XS Rating Curve= 0 ,0
Exp/Cntr=0.3,0.1

Type RM Length L Ch R = 1 ,46678   ,506,506,506
BEGIN DESCRIPTION:
EIGHTEENMILE CREEK 77.0
END DESCRIPTION:
XS GIS Cut Line= 3
      2475524.99     13496624.98        2475325.       13496175.
      2474724.99     13494174.98
#Sta/Elev= 30
  4503.7  225.83  4717.4  221.06  4849.1  218.89  4941.4  217.19  4952.3   213.1
    4964  205.86  4984.8  201.21  4993.4  199.16  5027.4  201.07  5036.3  199.14
  5036.8  198.64  5065.6  199.14  5089.2  203.68  5100.5   205.7  5193.1  209.43
  5236.2  209.92  5267.6   204.4  5325.9  212.16  5400.7  210.54  5712.2  211.85
  5994.6  212.28  6094.5  213.36  6335.2  219.89    6439     220  6519.6  219.94
  6542.9  219.91  6663.1  219.75  6838.4  221.73  6929.4  223.07  7084.2  225.29
#Mann= 19 ,-1 , 0
  4503.7     .05       0  4717.4     .07       0  4849.1     .05       0
  4984.8      .1       0  5036.3     .05       0  5065.6      .1       0
  5089.2     .12       0  5193.1     .07       0  5400.7     .12       0
  5712.2     .05       0  5994.6     .12       0  6094.5     .07       0
  6335.2     .12       0    6439     .05       0  6519.6     .12       0
  6542.9     .07       0  6663.1     .12       0  6838.4     .07       0
  6929.4     .12       0
Bank Sta=5036.3,5065.6
XS Rating Curve= 0 ,0
Exp/Cntr=0.3,0.1