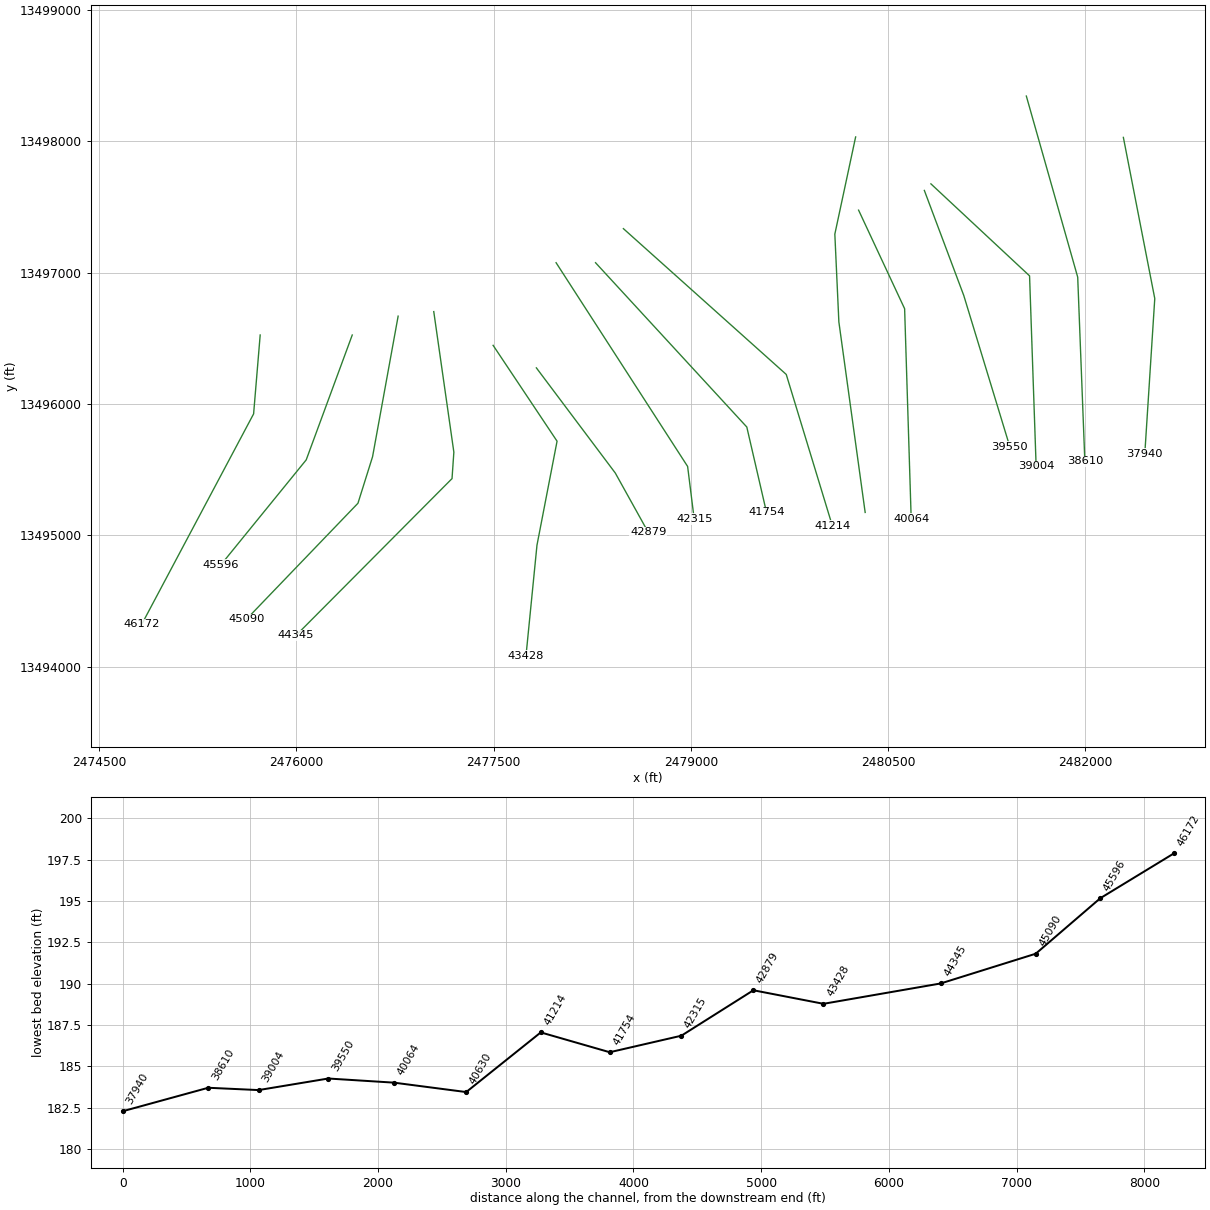
HEC-RAS study EIGHTEENMILE CREEK.prj: EIGHTEENMILE CREEK Base Level Engineering

--- EIGHTEENMILE CREEK.g01 (geometry) --- (continued)

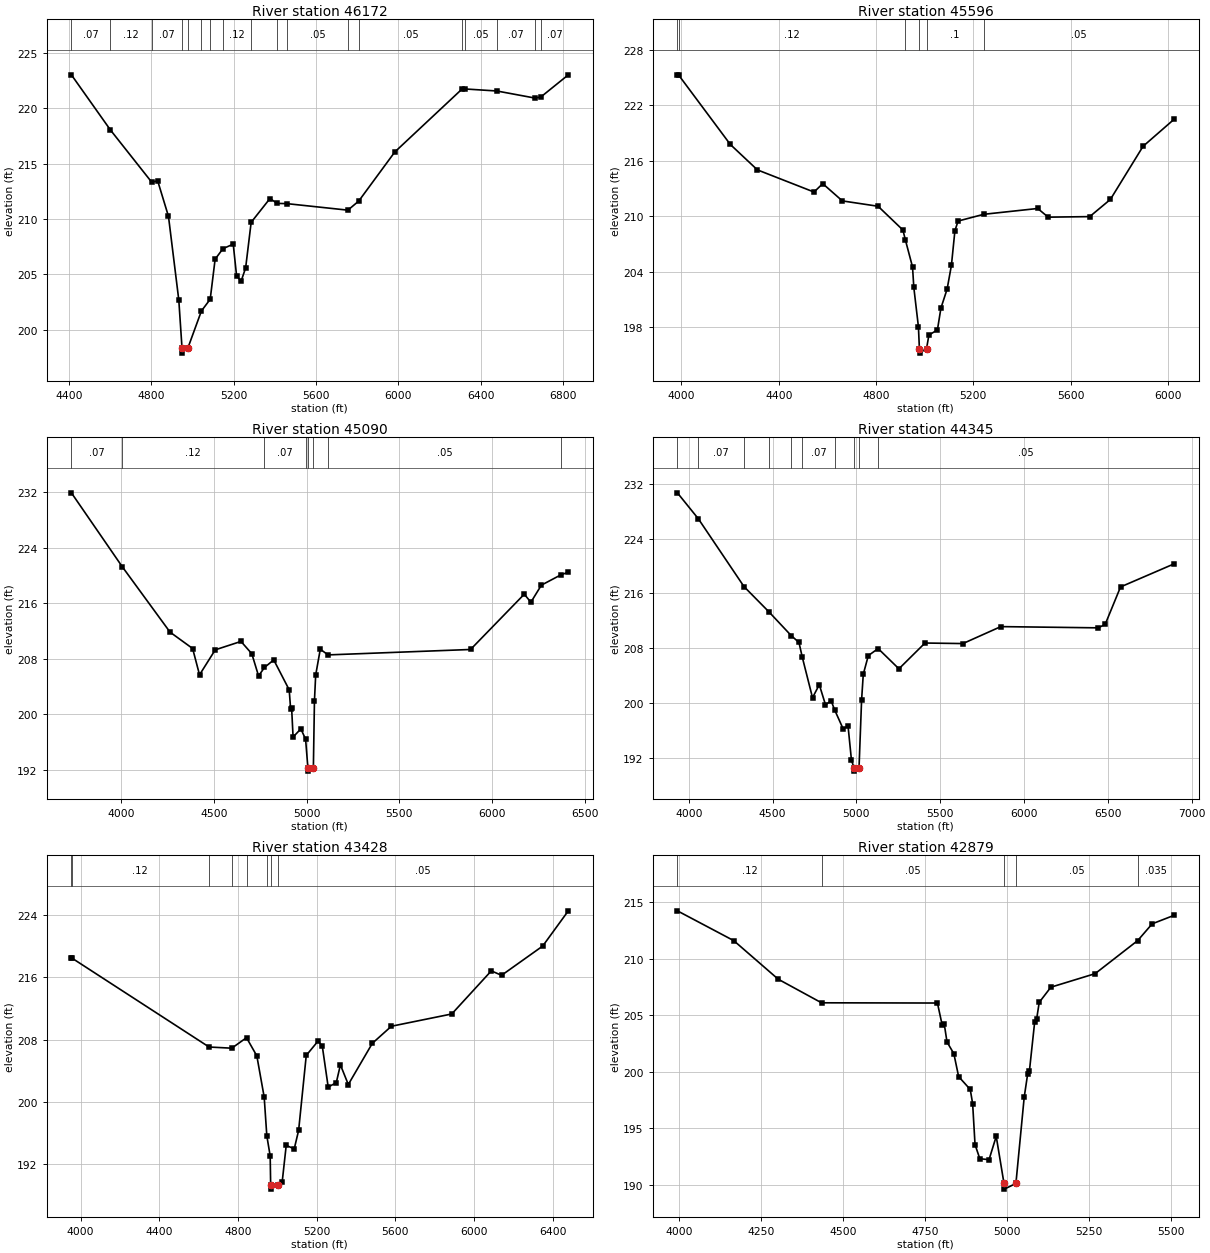
Type RM Length L Ch R = 1 ,46172   ,576,576,576
BEGIN DESCRIPTION:
EIGHTEENMILE CREEK 76.0
END DESCRIPTION:
XS GIS Cut Line= 3
        2475725.     13496525.02        2475675.       13495925.
      2474824.98     13494324.97
#Sta/Elev= 30
  4412.2  223.03  4601.7  218.05  4802.7  213.32  4831.2  213.46  4883.8  210.24
    4934  202.67  4949.4  198.38  4949.9  197.88  4978.8  198.38  5043.8  201.69
  5086.5  202.75  5110.4  206.37  5148.5  207.32  5198.3  207.73  5214.6  204.87
  5236.6  204.38  5258.6  205.58  5285.4   209.7  5376.7  211.85  5412.1  211.41
  5458.7  211.39  5755.2   210.8  5807.9  211.62  5983.3  216.06  6309.4  221.74
  6326.4  221.75  6478.8  221.57  6663.8  220.93  6692.7  221.03  6826.1  223.03
#Mann= 18 ,-1 , 0
  4412.2     .07       0  4601.7     .12       0  4802.7     .07       0
  4949.4     .05       0  4978.8     .07       0  5043.8      .1       0
  5086.5     .07       0  5148.5     .12       0  5285.4     .05       0
  5412.1     .12       0  5458.7     .05       0  5755.2    .035       0
  5807.9     .05       0  6309.4     .07       0  6326.4     .05       0
  6478.8     .07       0  6663.8     .12       0  6692.7     .07       0
Bank Sta=4949.4,4978.8
XS Rating Curve= 0 ,0
Exp/Cntr=0.3,0.1

Type RM Length L Ch R = 1 ,45596   ,506,506,506
BEGIN DESCRIPTION:
EIGHTEENMILE CREEK 75.0
END DESCRIPTION:
XS GIS Cut Line= 3
      2476425.01     13496525.04        2476075.       13495575.
      2475425.02     13494775.03
#Sta/Elev= 30
  3983.1   225.3  3988.4  225.27  4200.8  217.76    4312  215.01  4544.9  212.61
  4580.7  213.52  4661.4  211.65  4808.3  211.07  4910.3   208.5  4920.6  207.42
  4949.9   204.5  4955.2  202.28  4974.2  198.01  4978.1  195.67  4978.6  195.17
  5007.7  195.67  5017.1  197.12  5052.3  197.69  5066.7  200.05  5092.2  202.11
  5109.8  204.68  5124.2  208.43  5137.3  209.47  5242.8   210.2  5464.6  210.83
  5507.7  209.89  5678.5  209.95  5763.4  211.81  5897.7  217.56  6026.3  220.51
#Mann= 6 ,-1 , 0
  3983.1     .07       0  3988.4     .12       0  4920.6      .1       0
  4978.1     .05       0  5007.7      .1       0  5242.8     .05       0
Bank Sta=4978.1,5007.7
XS Rating Curve= 0 ,0
Exp/Cntr=0.3,0.1

Type RM Length L Ch R = 1 ,45090   ,745,745,745
BEGIN DESCRIPTION:
Mapping XS c17e88ab
END DESCRIPTION:
XS GIS Cut Line= 4
      2476773.98     13496668.59      2476579.53      13495599.1
      2476468.41     13495244.94      2475621.17     13494362.96
#Sta/Elev= 30
  3730.5  231.87  4004.5  221.25  4262.7  211.82  4384.6  209.46  4421.9  205.67
  4506.6  209.27  4645.5  210.48  4703.9  208.71  4740.4  205.51  4772.2  206.73
  4822.3  207.82  4905.7  203.51  4913.5  200.71  4918.8  200.87  4926.6  196.72
  4968.6  197.89  4994.1  196.41  5006.4  192.31  5006.9  191.81  5036.1  192.31
  5041.9  201.92  5048.5  205.63  5073.4  209.36  5115.3  208.54  5884.1  209.32
    6174  217.28  6209.6  216.12  6266.2  218.58  6372.7  220.08  6411.7  220.44
#Mann= 8 ,-1 , 0
  3730.5     .07       0  4004.5     .12       0  4772.2     .07       0
  4994.1      .1       0  5006.4     .05       0  5036.1      .1       0
  5115.3     .05       0  6372.7     .07       0
Bank Sta=5006.4,5036.1
XS Rating Curve= 0 ,0
Exp/Cntr=0.3,0.1

Type RM Length L Ch R = 1 ,44345   ,917,917,917
BEGIN DESCRIPTION:
Mapping XS 41b869f3
END DESCRIPTION:
XS GIS Cut Line= 4
      2477044.81     13496703.22      2477197.58     13495633.82
      2477183.69     13495432.44      2475997.19       13494239.
#Sta/Elev= 30
  3931.7   230.7  4056.6  226.91  4329.2  216.99  4478.6  213.28  4611.1  209.82
  4657.2  208.82    4677  206.66    4738  200.74  4778.4  202.65  4815.4  199.71
  4849.1  200.29  4869.3     199  4919.9  196.23  4950.2  196.54  4970.4  191.59
  4985.8  190.51  4986.3  190.01  5015.5  190.51  5030.8  200.42  5040.8  204.17
  5070.9   206.9  5129.5  207.93  5253.5  204.97  5409.1  208.74  5635.3  208.66
  5861.6  211.14  6441.4  210.96  6483.9  211.45  6575.8  216.94  6896.7  220.33
#Mann= 10 ,-1 , 0
  3931.7     .12       0  4056.6     .07       0  4329.2     .12       0
  4478.6     .07       0  4611.1     .12       0    4677     .07       0
  4869.3    .035       0  4985.8    .035       0  5015.5    .035       0
  5129.5     .05       0
Bank Sta=4985.8,5015.5
XS Rating Curve= 0 ,0
Exp/Cntr=0.3,0.1

Type RM Length L Ch R = 1 ,43428   ,549,549,549
BEGIN DESCRIPTION:
Mapping XS 30909df4
END DESCRIPTION:
XS GIS Cut Line= 4
      2477496.19     13496446.32       2477982.3     13495717.16
      2477829.53     13494925.49      2477746.19     13494085.23
#Sta/Elev= 30
  3953.3  218.51  3954.3  218.51  4653.5  207.05  4768.8   206.9  4843.8  208.25
  4896.3  205.91  4933.7  200.61  4947.1  195.63  4964.2  193.04  4966.6  189.28
  4967.5  188.78  5002.6  189.28  5025.4  189.75  5045.7   194.4  5086.5  193.96
  5108.8  196.33  5147.6  205.97  5207.4  207.81    5229  207.19  5259.2   201.9
  5300.3  202.47  5321.3  204.76  5361.4  202.23  5483.7  207.53  5580.5  209.72
  5887.6   211.3  6088.6  216.84  6140.8  216.27  6349.9  220.03  6480.3  224.56
#Mann= 8 ,-1 , 0
  3953.3     .07       0  3954.3     .12       0  4653.5     .07       0
  4768.8     .05       0  4843.8     .07       0  4947.1     .05       0
  4966.6     .05       0  5002.6     .05       0
Bank Sta=4966.6,5002.6
XS Rating Curve= 0 ,0
Exp/Cntr=0.3,0.1

Type RM Length L Ch R = 1 ,42879   ,564,564,564
BEGIN DESCRIPTION:
EIGHTEENMILE CREEK 70.0
END DESCRIPTION:
XS GIS Cut Line= 3
      2477824.99     13496275.02        2478425.       13495475.
        2478675.       13495025.
#Sta/Elev= 30
  3995.8  214.23  4167.7  211.59  4303.1  208.18  4435.2  206.09  4788.5  206.07
  4803.1   204.1  4809.4  204.19  4817.7  202.62  4838.5  201.59  4853.1  199.56
  4888.5  198.42  4895.8  197.17  4903.1  193.54  4917.7  192.29  4945.8  192.21
  4967.7  194.27  4991.4   190.1  4992.3   189.6  5027.7   190.1    5053  197.74
  5063.3  199.75    5069  200.09    5085  204.42  5090.8  204.64  5098.8  206.13
  5134.2  207.47  5269.2  208.67    5399   211.6  5443.1  213.08  5510.6  213.84
#Mann= 5 ,-1 , 0
  3995.8     .12       0  4435.2     .05       0  4991.4     .05       0
  5027.7     .05       0    5399    .035       0
Bank Sta=4991.4,5027.7
XS Rating Curve= 0 ,0
Exp/Cntr=0.3,0.1

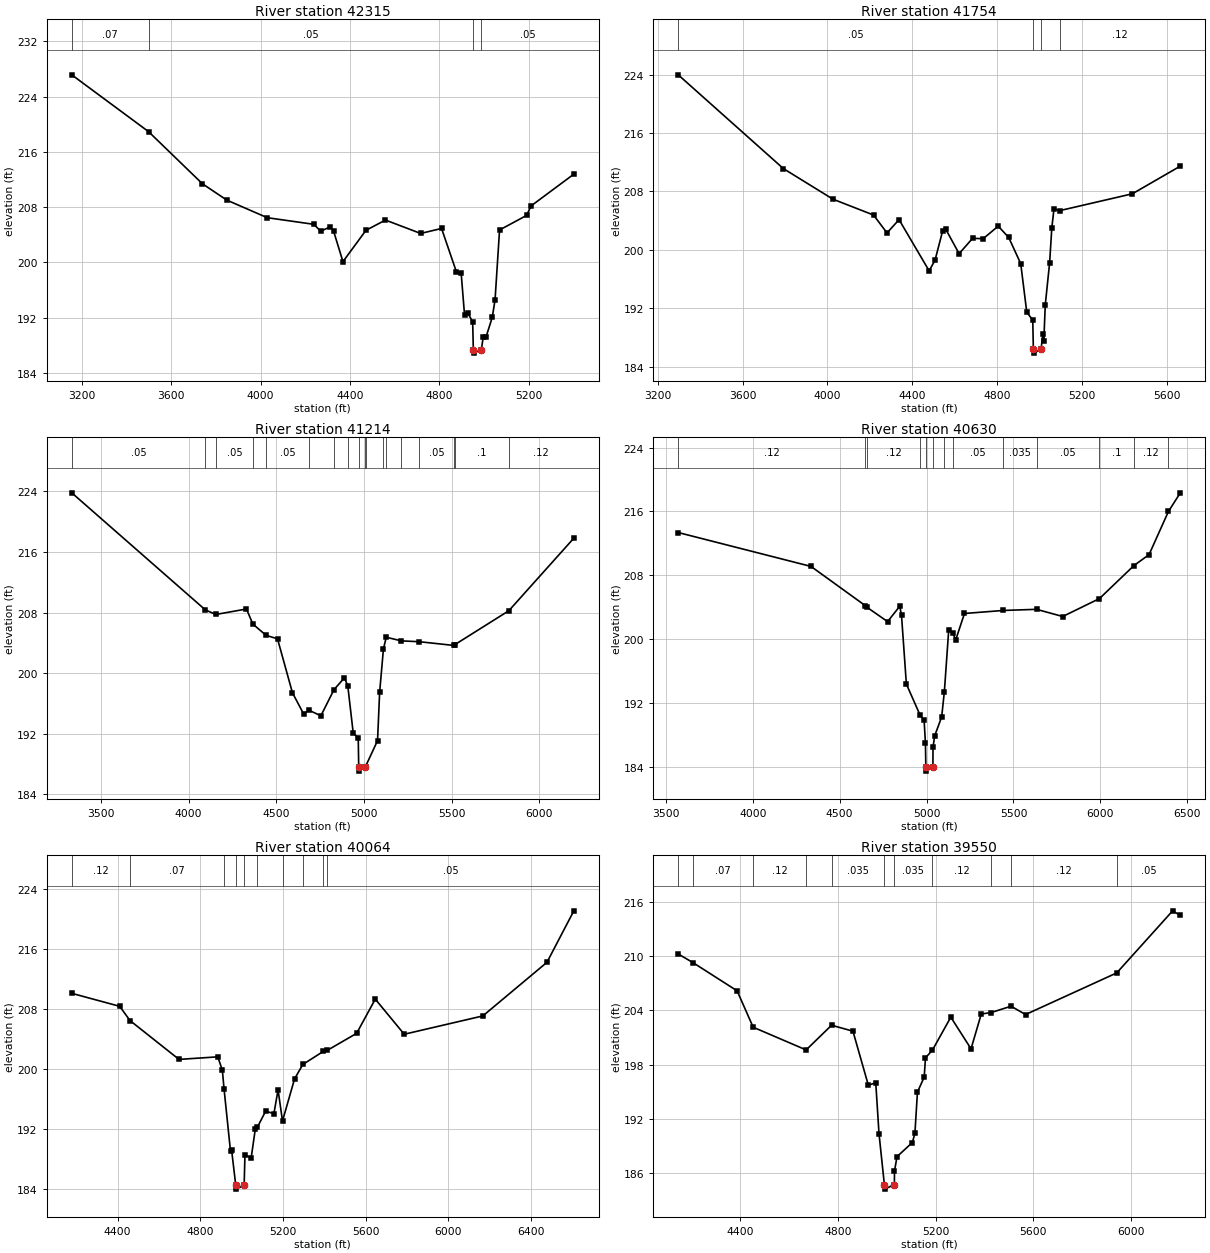
Type RM Length L Ch R = 1 ,42315   ,561,561,561
BEGIN DESCRIPTION:
EIGHTEENMILE CREEK 69.0
END DESCRIPTION:
XS GIS Cut Line= 3
        2477975.     13497075.01        2478975.       13495525.
        2479025.     13495125.01
#Sta/Elev= 30
    3155  227.17  3498.7  218.94  3740.1  211.38    3849  209.02  4030.4  206.47
    4239  205.51  4269.3  204.51  4311.6  205.14  4326.8  204.56    4369   200.1
    4472  204.64  4559.3  206.13  4716.8  204.19  4810.5  204.91  4877.2   198.6
  4898.3  198.41  4913.5  192.32  4928.2  192.67  4949.8  191.36  4952.7  187.35
  4953.6  186.85    4989  187.35  4996.6  189.17  5009.7   189.2  5037.4  192.03
    5050  194.58  5070.1  204.69  5191.1   206.8  5211.2  208.18  5402.7  212.78
#Mann= 4 ,-1 , 0
    3155     .07       0  3498.7     .05       0  4952.7     .05       0
    4989     .05       0
Bank Sta=4952.7,4989
XS Rating Curve= 0 ,0
Exp/Cntr=0.3,0.1

Type RM Length L Ch R = 1 ,41754   ,540,540,540
BEGIN DESCRIPTION:
EIGHTEENMILE CREEK 68.0
END DESCRIPTION:
XS GIS Cut Line= 3
      2478274.97     13497075.03        2479425.       13495825.
      2479575.01     13495174.96
#Sta/Elev= 30
    3297  223.96  3792.4  211.12  4026.1  206.93  4217.2  204.76  4280.7  202.31
  4337.4  204.13  4479.2  197.12    4507  198.58  4542.7  202.57  4556.9  202.85
  4620.4  199.47  4683.9  201.57  4733.9  201.52  4804.7  203.24  4854.1  201.69
  4910.8   198.1  4939.2  191.46  4967.5  190.37  4970.3  186.35  4971.1  185.85
  5006.7  186.35  5014.4  188.43  5019.5  187.52  5026.4  192.46  5046.9  198.22
  5057.2  202.99  5067.4   205.6  5095.4  205.37  5436.9  207.67  5662.7  211.46
#Mann= 4 ,-1 , 0
    3297     .05       0  4970.3     .05       0  5006.7     .05       0
  5095.4     .12       0
Bank Sta=4970.3,5006.7
XS Rating Curve= 0 ,0
Exp/Cntr=0.3,0.1

Type RM Length L Ch R = 1 ,41214   ,584,584,584
BEGIN DESCRIPTION:
EIGHTEENMILE CREEK 67.0
END DESCRIPTION:
XS GIS Cut Line= 3
      2478486.85     13497334.24        2479725.       13496225.
      2480074.99     13495075.03
#Sta/Elev= 30
  3333.3  223.82  4095.5  208.35  4155.4  207.75  4329.9  208.47  4366.4  206.48
  4441.8  204.99  4507.1  204.53  4592.3   197.4  4655.9  194.61  4685.2  195.11
  4754.5  194.36  4829.2  197.81  4889.1  199.39  4908.1  198.29  4939.2  192.05
  4967.6  191.47  4970.4  187.55  4971.2  187.05  5006.8  187.55  5009.2  187.66
  5077.8  191.08  5089.7  197.47  5111.4   203.2  5127.4  204.74  5213.6  204.26
  5315.8  204.15  5511.7  203.66  5520.1  203.78  5826.7  208.24  6197.7  217.83
#Mann= 18 ,-1 , 0
  3333.3     .05       0  4095.5     .07       0  4155.4     .05       0
  4366.4     .07       0  4441.8     .05       0  4685.2     .12       0
  4829.2     .05       0  4908.1     .07       0  4970.4     .05       0
  5006.8     .07       0  5009.2    .035       0  5111.4      .1       0
  5127.4    .035       0  5213.6     .07       0  5315.8     .05       0
  5511.7     .12       0  5520.1      .1       0  5826.7     .12       0
Bank Sta=4970.4,5006.8
XS Rating Curve= 0 ,0
Exp/Cntr=0.3,0.1

Type RM Length L Ch R = 1 ,40630   ,566,566,566
BEGIN DESCRIPTION:
EIGHTEENMILE CREEK 66.0
END DESCRIPTION:
XS GIS Cut Line= 4
      2480252.51     13498032.13      2480094.39      13497292.7
        2480125.       13496625.        2480325.     13495174.98
#Sta/Elev= 30
  3571.4  213.36  4335.3  209.11  4646.4  204.21  4656.4     204  4775.7  202.19
  4845.8  204.12  4855.8  202.98  4883.8  194.36  4962.5  190.47  4985.9   189.8
  4993.4  186.99  4995.9  183.94  4996.9  183.44  5036.4  183.94    5037  186.41
  5046.4  187.85  5086.8  190.23  5102.4  193.42  5127.2  201.08  5149.6  200.82
  5167.6   199.9    5218  203.21  5442.4  203.59  5632.8  203.73  5783.3  202.83
  5994.7  205.08    6193  209.22  6279.9  210.59  6391.3     216  6459.7  218.34
#Mann= 13 ,-1 , 0
  3571.4     .12       0  4646.4     .07       0  4656.4     .12       0
  4962.5     .15       0  4995.9     .05       0  5036.4     .15       0
  5102.4     .07       0  5149.6     .05       0  5442.4    .035       0
  5632.8     .05       0  5994.7      .1       0    6193     .12       0
  6391.3     .05       0
Bank Sta=4995.9,5036.4
XS Rating Curve= 0 ,0
Exp/Cntr=0.3,0.1

Type RM Length L Ch R = 1 ,40064   ,514,514,514
BEGIN DESCRIPTION:
EIGHTEENMILE CREEK 65.0
END DESCRIPTION:
XS GIS Cut Line= 3
      2480274.99     13497475.02        2480625.       13496725.
        2480675.     13495124.95
#Sta/Elev= 30
  4178.6  210.09  4410.4  208.36  4460.4  206.46  4697.3  201.29  4884.9  201.63
    4907  199.84  4915.3  197.33  4946.4  189.05  4951.9  189.17  4971.8  184.51
  4972.8  184.01  5012.3  184.51  5016.3  188.56  5046.3  188.17  5066.3     192
  5076.4  192.26  5116.3  194.39  5156.3  194.07  5176.4  197.23  5197.9  193.09
  5256.4  198.71  5296.4  200.62    5395  202.35  5413.5  202.48  5556.5  204.76
  5646.6  209.32  5786.7  204.64  6166.8  207.08    6477  214.22  6607.1  221.08
#Mann= 10 ,-1 , 0
  4178.6     .12       0  4460.4     .07       0  4915.3    .035       0
  4971.8    .035       0  5012.3    .035       0  5076.4     .15       0
  5197.9     .05       0  5296.4     .07       0    5395    .035       0
  5413.5     .05       0
Bank Sta=4971.8,5012.3
XS Rating Curve= 0 ,0
Exp/Cntr=0.3,0.1

Type RM Length L Ch R = 1 ,39550   ,546,546,546
BEGIN DESCRIPTION:
EIGHTEENMILE CREEK 64.0
END DESCRIPTION:
XS GIS Cut Line= 3
        2480775.     13497624.99        2481075.       13496825.
      2481425.01     13495674.98
#Sta/Elev= 30
    4146  210.24  4205.6   209.3  4387.2  206.17  4452.9  202.15  4669.9  199.64
  4774.1  202.37  4861.6  201.71  4924.7  195.74    4955  196.02  4968.4  190.38
  4990.3  184.76  4991.3  184.26  5031.3  184.76  5031.8  186.27  5042.2  187.85
  5104.9  189.41  5115.4  190.42  5125.8  194.98  5153.5  196.64  5158.7  198.76
  5187.2  199.62  5262.5  203.26  5345.3  199.76  5387.2  203.61  5427.7  203.77
  5509.3  204.47  5568.6  203.55  5942.1  208.15  6171.1  215.01  6202.5   214.5
#Mann= 11 ,-1 , 0
    4146     .12       0  4205.6     .07       0  4452.9     .12       0
  4669.9     .07       0  4774.1    .035       0  4990.3    .035       0
  5031.3    .035       0  5187.2     .12       0  5427.7     .07       0
  5509.3     .12       0  5942.1     .05       0
Bank Sta=4990.3,5031.3
XS Rating Curve= 0 ,0
Exp/Cntr=0.3,0.1

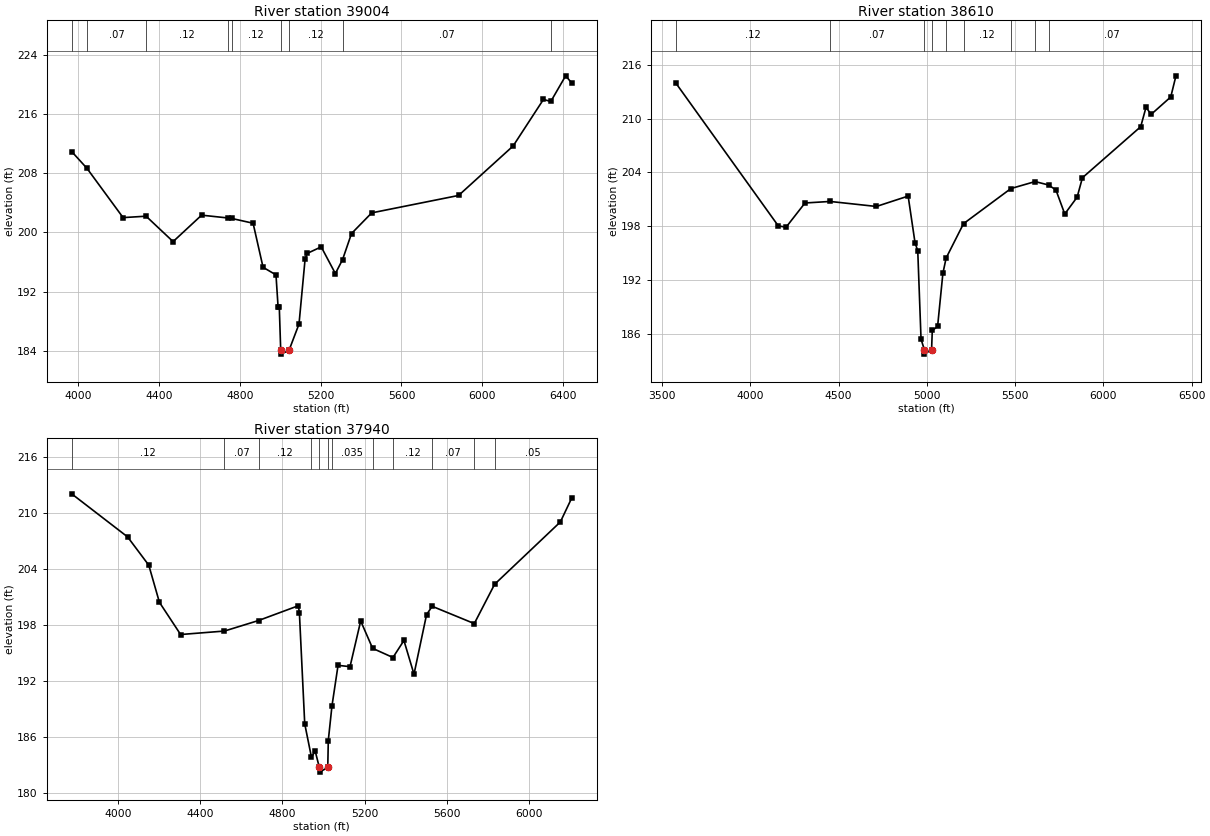
Type RM Length L Ch R = 1 ,39004   ,394,394,394
BEGIN DESCRIPTION:
EIGHTEENMILE CREEK 63.0
END DESCRIPTION:
XS GIS Cut Line= 3
      2480825.02     13497674.98        2481575.       13496975.
        2481625.     13495524.95
#Sta/Elev= 30
  3966.5  210.91  4042.3  208.64  4221.2  201.99  4335.1  202.18  4468.9  198.75
  4610.1  202.32  4740.7  201.94  4760.2  201.87  4865.1  201.23  4914.5  195.28
  4978.5  194.26    4989  189.88  4994.9  189.88  5001.9  184.06  5002.9  183.56
  5042.9  184.06  5092.5  187.62  5122.5  196.34  5132.5  197.15  5202.5  198.04
  5272.6  194.44  5308.3  196.32  5352.6  199.84  5452.7  202.63  5882.9  204.98
  6153.1  211.66  6303.2  217.94  6339.8  217.67  6413.2  221.13  6443.3  220.17
#Mann= 9 ,-1 , 0
  3966.5     .12       0  4042.3     .07       0  4335.1     .12       0
  4740.7     .07       0  4760.2     .12       0  5001.9     .05       0
  5042.9     .12       0  5308.3     .07       0  6339.8     .05       0
Bank Sta=5001.9,5042.9
XS Rating Curve= 0 ,0
Exp/Cntr=0.3,0.1

Type RM Length L Ch R = 1 ,38610   ,670,670,670
BEGIN DESCRIPTION:
Mapping XS 5c832e10
END DESCRIPTION:
XS GIS Cut Line= 3
      2481550.42     13498343.24      2481941.05     13496965.19
       2481995.3     13495565.49
#Sta/Elev= 30
    3578  213.96  4158.1  198.02  4202.4  197.88  4309.4  200.58  4451.7  200.75
  4713.7  200.19  4893.8  201.35  4932.9  196.12  4948.2  195.25  4966.8  185.38
  4985.4   184.2  4986.4   183.7  5026.5   184.2  5030.6  186.34  5060.6  186.79
  5090.6  192.72  5108.9  194.43  5207.5  198.27  5475.8  202.19  5613.1  202.97
  5689.1  202.59  5731.1  202.03  5781.1  199.35  5851.2  201.23  5881.2   203.4
  6211.4   209.1  6241.5  211.27  6270.3  210.47  6381.6  212.42  6411.1  214.78
#Mann= 9 ,-1 , 0
    3578     .12       0  4451.7     .07       0  4985.4     .05       0
  5026.5     .07       0  5108.9    .035       0  5207.5     .12       0
  5475.8     .07       0  5613.1     .12       0  5689.1     .07       0
Bank Sta=4985.4,5026.5
XS Rating Curve= 0 ,0
Exp/Cntr=0.3,0.1

Type RM Length L Ch R = 1 ,37940   ,661,661,661
BEGIN DESCRIPTION:
Mapping XS 9f24685e
END DESCRIPTION:
XS GIS Cut Line= 3
      2482288.27     13498028.58      2482526.99     13496802.43
      2482451.04     13495619.84
#Sta/Elev= 30
  3773.8  212.07    4046  207.46  4149.2  204.43  4200.9  200.46  4304.1  197.01
  4517.2  197.38  4683.6  198.51  4877.2  200.09  4882.3  199.35  4908.3  187.45
  4941.1  183.87  4959.2  184.54  4979.4  182.78  4980.4  182.28  5020.5  182.78
    5023  185.66  5040.8  189.35  5070.5  193.71  5128.8  193.57  5180.7  198.46
  5238.8  195.53  5337.8  194.55  5391.2  196.37  5440.2  192.76  5501.4  199.14
  5528.8  200.03  5733.7  198.18  5832.7  202.39  6152.7  209.06    6208  211.62
#Mann= 12 ,-1 , 0
  3773.8     .12       0  4517.2     .07       0  4683.6     .12       0
  4941.1     .15       0  4979.4     .05       0  5020.5     .15       0
  5040.8    .035       0  5238.8     .05       0  5337.8     .12       0
  5528.8     .07       0  5733.7     .12       0  5832.7     .05       0
Bank Sta=4979.4,5020.5
XS Rating Curve= 0 ,0
Exp/Cntr=0.3,0.1