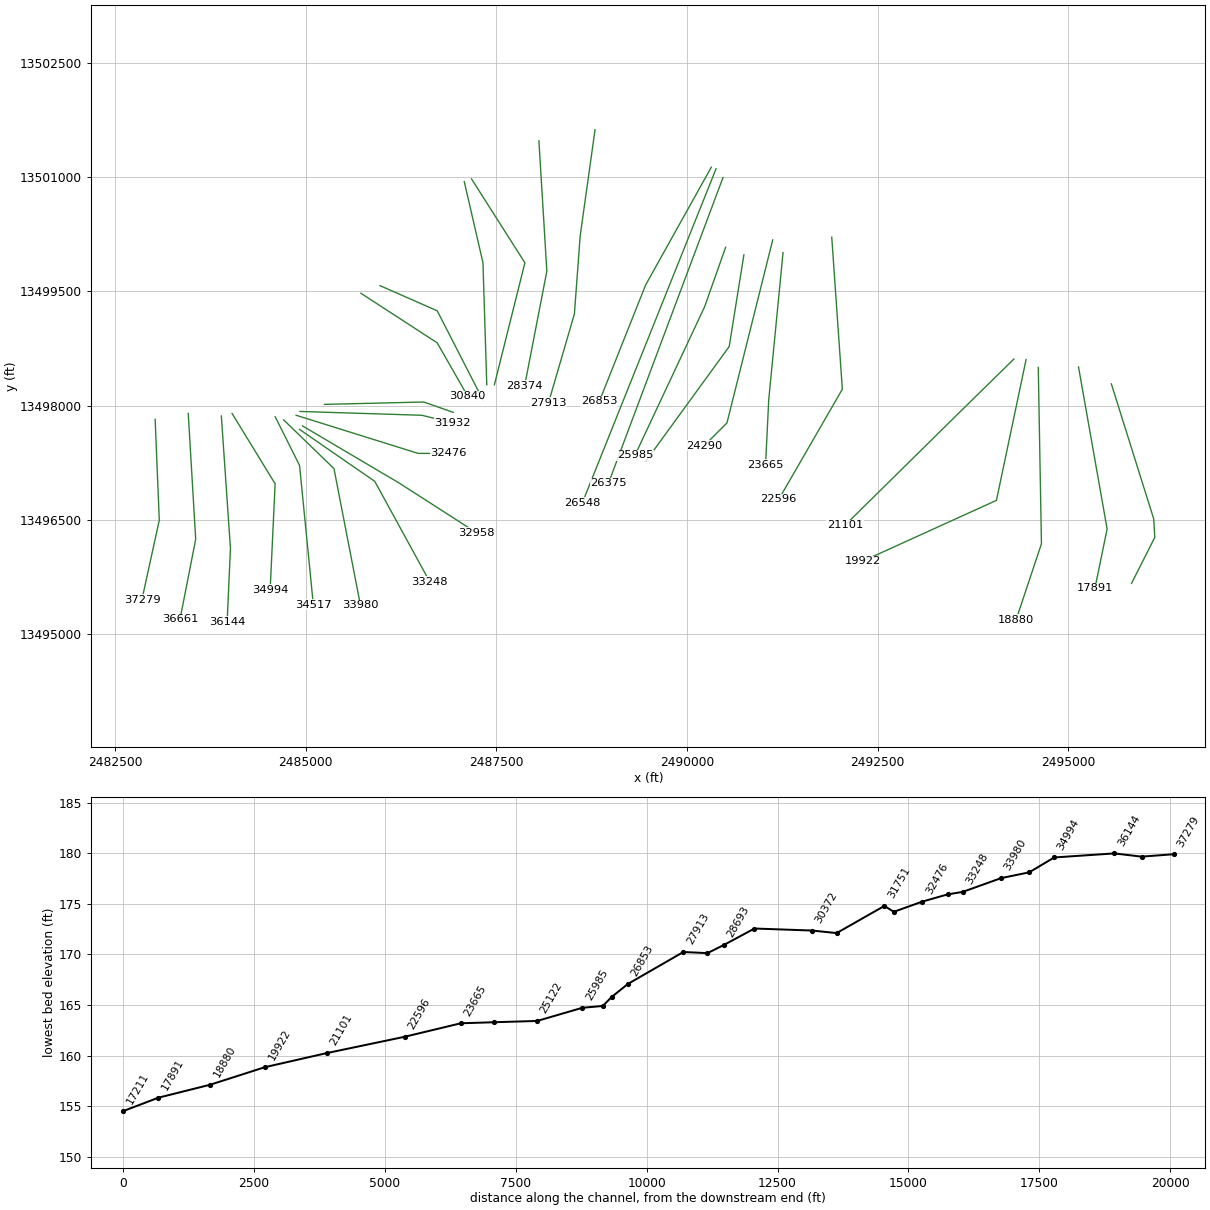
HEC-RAS study EIGHTEENMILE CREEK.prj: EIGHTEENMILE CREEK Base Level Engineering

--- EIGHTEENMILE CREEK.g01 (geometry) --- (continued)

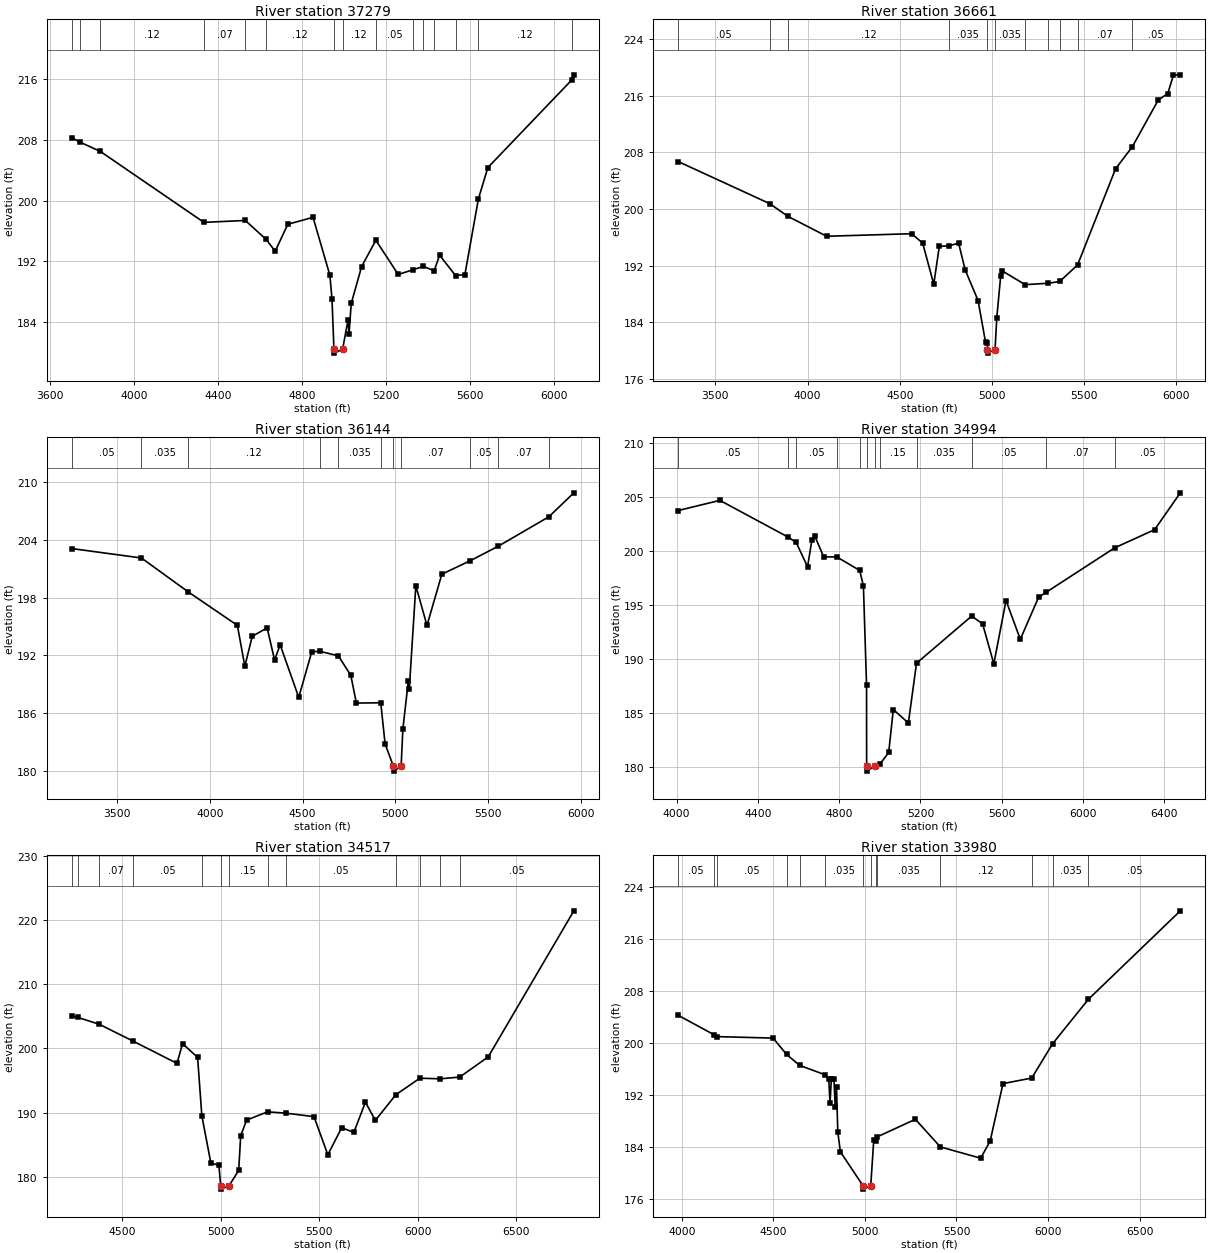
Type RM Length L Ch R = 1 ,37279   ,618,618,618
BEGIN DESCRIPTION:
Mapping XS d39d7e68
END DESCRIPTION:
XS GIS Cut Line= 3
      2483026.12     13497822.35      2483080.37     13496498.61
      2482852.84     13495458.46
#Sta/Elev= 30
  3704.9  208.31  3742.4  207.74  3840.9  206.49  4333.8  197.14  4530.9  197.39
  4629.5   194.9  4673.1  193.34  4733.1  196.89  4853.2   197.8  4933.3  190.18
  4943.3  187.08  4952.8   180.4  4953.8   179.9  4993.9   180.4  5019.5  184.24
  5024.5  182.45    5035  186.45  5084.6  191.32  5152.2  194.78  5258.7  190.27
  5328.3  190.88  5378.4  191.34  5429.8  190.75  5455.5  192.81  5531.4  190.13
    5576  190.26  5640.3  200.24  5685.1  204.36  6086.5  215.97  6094.5  216.59
#Mann= 15 ,-1 , 0
  3704.9     .05       0  3742.4     .07       0  3840.9     .12       0
  4333.8     .07       0  4530.9      .1       0  4629.5     .12       0
  4952.8    .035       0  4993.9     .12       0  5152.2     .05       0
  5328.3     .12       0  5378.4     .05       0  5429.8     .12       0
  5531.4     .05       0  5640.3     .12       0  6086.5     .05       0
Bank Sta=4952.8,4993.9
XS Rating Curve= 0 ,0
Exp/Cntr=0.3,0.1

Type RM Length L Ch R = 1 ,36661   ,517,517,517
BEGIN DESCRIPTION:
Mapping XS 15f6ce2a
END DESCRIPTION:
XS GIS Cut Line= 3
      2483460.15     13497898.38      2483557.81     13496249.04
      2483351.98     13495198.24
#Sta/Elev= 30
  3298.8  206.69  3794.4  200.76    3893  198.97  4103.6  196.15  4564.4  196.51
  4624.5  195.19  4684.6  189.38  4714.7  194.72    4768  194.81  4819.4  195.18
  4854.9  191.41    4925  187.08  4965.3  181.22  4975.5  181.11  4975.8  180.16
  4976.8  179.66  5016.9  180.16  5026.5  184.64  5047.8   190.6    5057  191.25
  5180.4  189.32  5305.5  189.52  5367.7  189.77  5464.5   192.1  5670.7  205.67
  5761.3  208.77  5902.8   215.4  5953.8  216.27  5984.8  218.93  6021.8  218.91
#Mann= 11 ,-1 , 0
  3298.8     .05       0  3794.4     .07       0    3893     .12       0
    4768    .035       0  4975.8    .035       0  5016.9    .035       0
  5180.4      .1       0  5305.5     .12       0  5367.7      .1       0
  5464.5     .07       0  5761.3     .05       0
Bank Sta=4975.8,5016.9
XS Rating Curve= 0 ,0
Exp/Cntr=0.3,0.1

Type RM Length L Ch R = 1 ,36144   ,1150,1150,1150
BEGIN DESCRIPTION:
Mapping XS 958a75cd
END DESCRIPTION:
XS GIS Cut Line= 3
      2483894.17     13497865.82      2484013.53     13496129.68
      2483970.13     13495163.99
#Sta/Elev= 30
    3256   203.1  3631.7  202.12  3885.3  198.58  4148.9  195.12    4189  190.88
  4229.1  193.99  4309.3  194.86  4349.4  191.52  4379.5   193.1  4479.7  187.64
  4549.9  192.38  4594.6  192.42  4693.2  191.96  4760.4  189.93  4790.4  187.05
  4921.9  187.08  4945.3   182.8  4990.2  180.48  4991.2  179.98  5031.7  180.48
    5041  184.33  5070.5  189.33  5075.5  188.46    5111  199.24  5171.1  195.11
  5251.2  200.44  5404.6  201.84    5555  203.34  5828.2   206.4  5962.9  208.89
#Mann= 11 ,-1 , 0
    3256     .05       0  3631.7    .035       0  3885.3     .12       0
  4594.6     .07       0  4693.2    .035       0  4921.9     .07       0
  4990.2     .05       0  5031.7     .07       0  5404.6     .05       0
    5555     .07       0  5828.2     .05       0
Bank Sta=4990.2,5031.7
XS Rating Curve= 0 ,0
Exp/Cntr=0.3,0.1

Type RM Length L Ch R = 1 ,34994   ,477,477,477
BEGIN DESCRIPTION:
Mapping XS 75db4bed
END DESCRIPTION:
XS GIS Cut Line= 3
      2484035.25     13497898.33      2484599.47     13496976.04
      2484534.43     13495588.55
#Sta/Elev= 30
  4008.3  203.76  4213.2   204.7  4547.1  201.31  4588.5   200.8  4644.6  198.54
  4665.9  201.02  4680.4  201.38  4723.9  199.45  4787.6  199.46  4901.2   198.2
  4919.4  196.75  4934.8  187.56  4935.2  180.08  4936.2  179.58    4977  180.08
  5001.4  180.25  5043.8  181.31  5066.4  185.29  5140.6  184.05  5180.6  189.59
  5451.8  193.96  5505.7  193.25    5561  189.54  5621.1  195.41  5691.2  191.81
  5781.3  195.71  5818.3  196.17  6155.9   200.3  6351.9  201.98  6478.5   205.4
#Mann= 12 ,-1 , 0
  4008.3     .05       0  4547.1     .07       0  4588.5     .05       0
  4787.6     .07       0  4901.2    .035       0  4935.2    .035       0
    4977    .035       0  5001.4     .15       0  5180.6    .035       0
  5451.8     .05       0  5818.3     .07       0  6155.9     .05       0
Bank Sta=4935.2,4977
XS Rating Curve= 0 ,0
Exp/Cntr=0.3,0.1

Type RM Length L Ch R = 1 ,34517   ,537,537,537
BEGIN DESCRIPTION:
Mapping XS 4c1e431a
END DESCRIPTION:
XS GIS Cut Line= 3
      2484600.37     13497856.03       2484919.8     13497217.16
      2485100.18     13495392.63
#Sta/Elev= 30
  4244.2  205.04  4273.3  204.85  4382.7  203.78  4554.8  201.15  4778.2  197.68
  4806.2  200.75  4882.6  198.62  4904.3  189.51  4949.7  182.22  4990.8  181.79
    5000  178.61    5001  178.11  5041.8  178.61  5091.3  181.03  5101.3  186.41
  5131.5  188.85  5237.6  190.14  5331.3  189.93  5473.4  189.39  5543.5  183.46
  5613.8  187.66  5675.6  186.95  5734.4  191.64  5784.6  188.81  5888.7   192.8
  6010.4  195.37  6114.1  195.28  6212.9  195.55  6357.4  198.69  6791.9  221.42
#Mann= 13 ,-1 , 0
  4244.2     .07       0  4273.3     .05       0  4382.7     .07       0
  4554.8     .05       0  4904.3     .15       0    5000     .05       0
  5041.8     .15       0  5237.6    .035       0  5331.3     .05       0
  5888.7    .035       0  6010.4     .12       0  6114.1     .07       0
  6212.9     .05       0
Bank Sta=5000,5041.8
XS Rating Curve= 0 ,0
Exp/Cntr=0.3,0.1

Type RM Length L Ch R = 1 ,33980   ,732,732,732
BEGIN DESCRIPTION:
Mapping XS d78ea295
END DESCRIPTION:
XS GIS Cut Line= 3
      2484711.49     13497814.36      2485371.19     13497175.49
      2485718.41     13495383.87
#Sta/Elev= 30
  3979.6  204.25  4174.4  201.28  4189.3  200.98    4498  200.75    4572  198.23
  4642.3  196.57    4780  195.13    4802  194.52    4809  190.73  4816.2  194.47
  4830.3  194.53  4837.3  190.13  4844.5  193.17  4851.4  186.31  4865.6  183.28
  4989.6  178.04  4990.6  177.54  5031.4  178.04  5047.7  185.02  5059.3  184.86
  5066.6  185.57  5275.3  188.27  5411.7  184.03  5632.2  182.29    5684  184.94
  5754.1  193.76  5911.1  194.61    6026  199.92  6220.9  206.72  6722.9  220.31
#Mann= 14 ,-1 , 0
  3979.6     .05       0  4174.4     .07       0  4189.3     .05       0
    4572     .12       0  4642.3     .05       0    4780    .035       0
  4989.6    .035       0  5031.4    .035       0  5059.3     .15       0
  5066.6    .035       0  5411.7     .12       0  5911.1     .05       0
    6026    .035       0  6220.9     .05       0
Bank Sta=4989.6,5031.4
XS Rating Curve= 0 ,0
Exp/Cntr=0.3,0.1

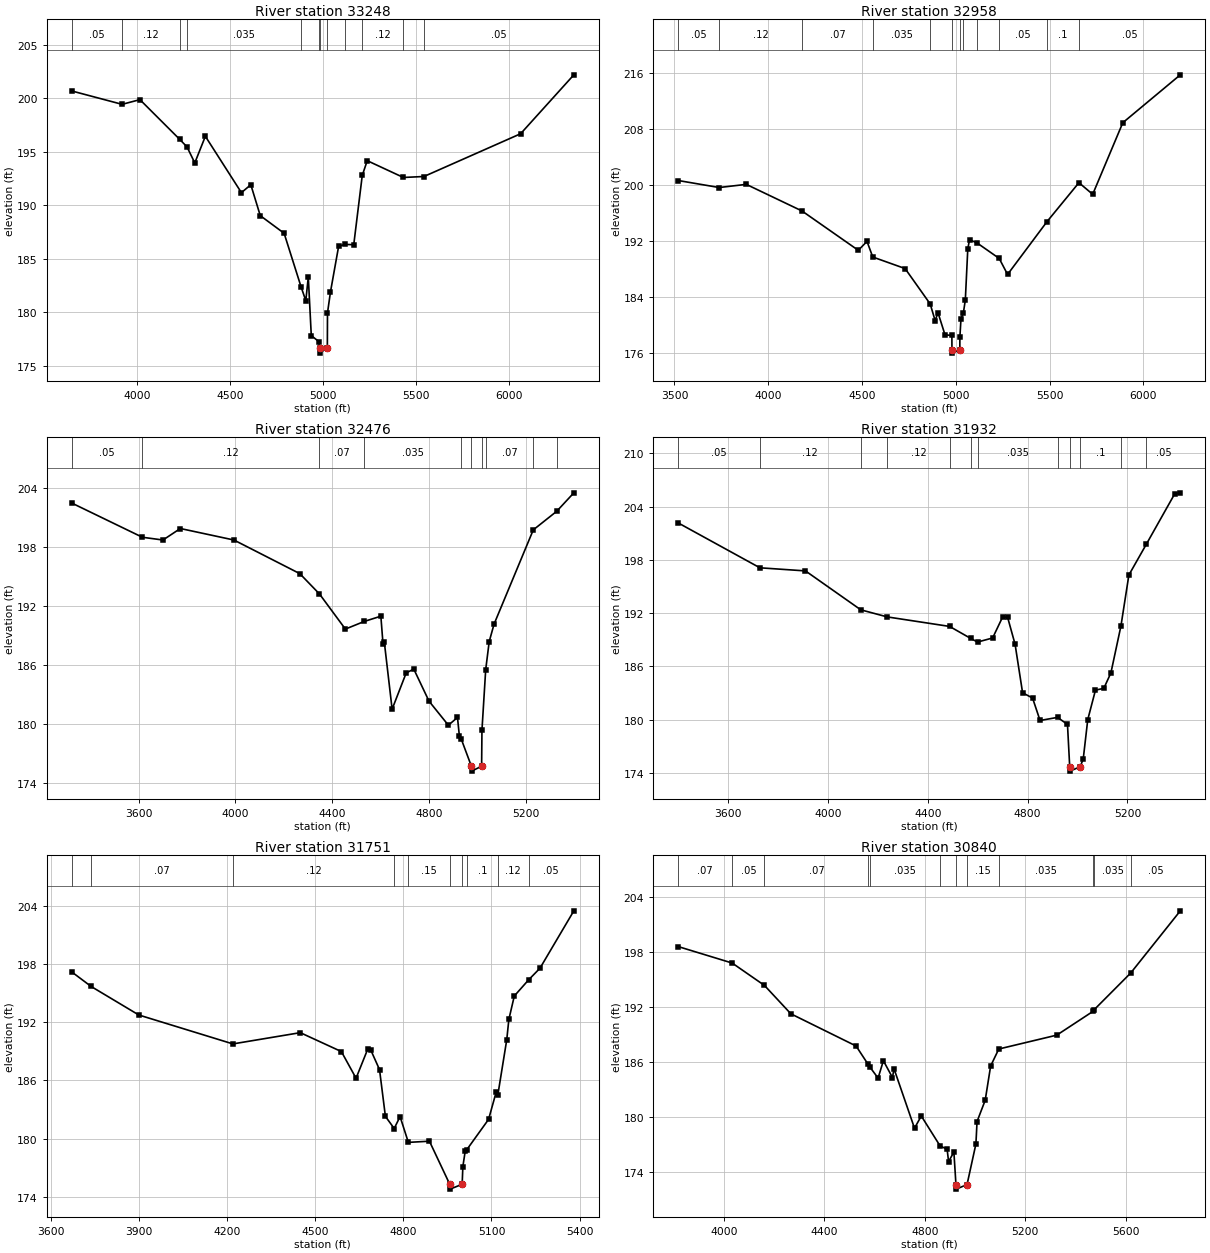
Type RM Length L Ch R = 1 ,33248   ,290,290,290
BEGIN DESCRIPTION:
Mapping XS 0a72afde
END DESCRIPTION:
XS GIS Cut Line= 3
      2484919.82     13497689.37      2485905.91     13497008.82
      2486627.99     13495689.65
#Sta/Elev= 30
  3648.8   200.7  3919.7  199.45  4015.5  199.89  4229.9  196.17  4268.9  195.47
  4310.9  193.97  4367.7  196.46  4561.7  191.19  4612.4  191.93  4663.2  189.04
  4791.6  187.39  4882.8  182.38  4908.3  181.08  4921.7   183.3  4937.8  177.82
  4978.5  177.26  4982.2  176.68  4983.2  176.18  5024.2  176.68    5025  179.94
  5041.1  181.91  5084.8  186.16    5118  186.35  5166.3  186.32  5212.1   192.8
  5238.9  194.18  5433.4  192.61  5544.1   192.7  6064.4   196.7  6350.8  202.21
#Mann= 12 ,-1 , 0
  3648.8     .05       0  3919.7     .12       0  4229.9     .05       0
  4268.9    .035       0  4882.8     .15       0  4978.5    .035       0
  4982.2    .035       0  5024.2    .035       0    5118      .1       0
  5212.1     .12       0  5433.4    .035       0  5544.1     .05       0
Bank Sta=4982.2,5024.2
XS Rating Curve= 0 ,0
Exp/Cntr=0.3,0.1

Type RM Length L Ch R = 1 ,32958   ,482,482,482
BEGIN DESCRIPTION:
Mapping XS c1a20042
END DESCRIPTION:
XS GIS Cut Line= 3
      2484958.74     13497735.24      2486219.15     13496990.45
      2487239.23     13496335.23
#Sta/Elev= 30
  3520.1  200.59  3738.4  199.59  3882.9  200.04  4179.8  196.24  4479.8  190.62
  4526.3  191.89  4557.1  189.66  4729.5  188.01  4863.3  182.95  4889.4  180.59
  4905.1  181.68  4942.2  178.54  4978.8  178.46  4979.2  176.43  4980.2  175.93
  5021.2  176.43  5021.4  178.19  5027.3  180.82  5040.3  181.72  5050.5  183.52
  5063.6  190.83  5072.9  192.13    5112  191.69    5231  189.46  5275.7  187.17
  5486.3  194.73  5656.1  200.28  5729.5  198.62    5890  208.85  6196.5  215.69
#Mann= 12 ,-1 , 0
  3520.1     .05       0  3738.4     .12       0  4179.8     .07       0
  4557.1    .035       0  4863.3     .15       0  4979.2     .05       0
  5021.2     .15       0  5040.3      .1       0    5112     .12       0
    5231     .05       0  5486.3      .1       0  5656.1     .05       0
Bank Sta=4979.2,5021.2
XS Rating Curve= 0 ,0
Exp/Cntr=0.3,0.1

Type RM Length L Ch R = 1 ,32476   ,544,544,544
BEGIN DESCRIPTION:
EIGHTEENMILE CREEK 54.0
END DESCRIPTION:
XS GIS Cut Line= 3
      2484874.97     13497875.01        2486475.       13497375.
      2486874.96       13497375.
#Sta/Elev= 30
  3323.2  202.49  3615.3  199.01  3700.4  198.73  3772.2   199.9  3993.8  198.73
  4266.2  195.31  4347.6  193.24  4454.7  189.67  4533.1  190.45  4601.4  190.98
  4610.3  188.17  4615.6  188.37    4648  181.52  4706.2  185.21  4737.6   185.6
  4800.5  182.34  4880.6  179.89  4918.3  180.68  4926.2  178.78  4933.2  178.53
  4975.8  175.72  4976.8  175.22  5018.1  175.72  5019.5  179.38    5035  185.55
  5049.5   188.4  5069.5  190.17  5231.7  199.76  5328.5  201.65  5399.5  203.53
#Mann= 10 ,-1 , 0
  3323.2     .05       0  3615.3     .12       0  4347.6     .07       0
  4533.1    .035       0  4933.2     .15       0  4975.8     .05       0
  5018.1     .15       0    5035     .07       0  5231.7     .12       0
  5328.5     .05       0
Bank Sta=4975.8,5018.1
XS Rating Curve= 0 ,0
Exp/Cntr=0.3,0.1

Type RM Length L Ch R = 1 ,31932   ,181,181,181
BEGIN DESCRIPTION:
EIGHTEENMILE CREEK 53.0
END DESCRIPTION:
XS GIS Cut Line= 3
      2484925.02       13497925.        2486525.       13497875.
      2486925.03     13497774.99
#Sta/Elev= 30
  3398.9  202.15  3726.4   197.1  3909.1  196.75  4130.8  192.37  4237.1  191.57
    4487   190.5  4570.9  189.16  4598.9  188.74  4659.5   189.2  4699.5  191.56
  4719.5  191.53  4749.5  188.49  4779.6  183.03  4819.6  182.44  4849.6  179.91
  4919.7  180.26  4959.6  179.47  4968.5  174.71  4969.5  174.21  5010.8  174.71
  5022.9  175.61  5040.9  180.01  5071.8  183.33  5105.3  183.53  5133.7  185.27
    5174  190.56  5205.8  196.29  5276.1  199.77  5388.8  205.39    5412  205.54
#Mann= 12 ,-1 , 0
  3398.9     .05       0  3726.4     .12       0  4130.8     .07       0
  4237.1     .12       0    4487     .07       0  4570.9     .12       0
  4598.9    .035       0  4919.7      .1       0  4968.5     .05       0
  5010.8      .1       0    5174     .12       0  5276.1     .05       0
Bank Sta=4968.5,5010.8
XS Rating Curve= 0 ,0
Exp/Cntr=0.3,0.1

Type RM Length L Ch R = 1 ,31751   ,911,911,911
BEGIN DESCRIPTION:
Mapping XS 3c95e753
END DESCRIPTION:
XS GIS Cut Line= 3
      2485246.48     13498017.79      2486548.58     13498049.04
      2486934.01     13497913.62
#Sta/Elev= 30
  3669.7  197.18  3735.8  195.68  3898.3  192.74  4218.8  189.76  4448.4  190.92
  4588.5  188.97  4638.5  186.22  4678.5  189.24  4688.5  189.14  4718.5  187.11
  4738.5  182.29  4768.5  181.04  4788.5  182.27  4816.7  179.61  4888.6  179.73
  4957.8  175.29  4958.8  174.79  5000.1  175.29  5002.5  177.12  5010.8  178.77
  5016.2  178.87  5090.1  181.98  5115.8  184.77  5121.5  184.47  5152.1   190.2
  5159.2  192.28  5177.8   194.7  5226.7  196.37  5265.2  197.56  5380.7  203.48
#Mann= 10 ,-1 , 0
  3669.7     .05       0  3735.8     .07       0  4218.8     .12       0
  4768.5    .035       0  4816.7     .15       0  4957.8     .05       0
  5000.1     .15       0  5016.2      .1       0  5121.5     .12       0
  5226.7     .05       0
Bank Sta=4957.8,5000.1
XS Rating Curve= 0 ,0
Exp/Cntr=0.3,0.1

Type RM Length L Ch R = 1 ,30840   ,468,468,468
BEGIN DESCRIPTION:
EIGHTEENMILE CREEK 51.0
END DESCRIPTION:
XS GIS Cut Line= 3
      2485724.97     13499475.02        2486725.       13498825.
      2487125.02     13498124.96
#Sta/Elev= 30
  3818.1  198.63  4032.9  196.83  4161.5  194.38  4266.5  191.28  4526.2  187.76
  4574.4  185.74  4580.8  185.47  4613.8  184.25  4634.9  186.15  4671.1  184.31
  4677.1  185.28  4758.8  178.77  4785.8  180.11    4861  176.82  4888.6  176.48
  4894.5  175.12  4915.6  176.17  4923.8  172.61  4924.8  172.11    4968  172.61
  5003.3  177.05  5007.8   179.5  5040.3  181.83  5061.9  185.57  5094.3  187.43
  5325.4  188.95  5470.7  191.57  5474.9  191.75  5619.6  195.74  5817.1  202.54
#Mann= 12 ,-1 , 0
  3818.1     .07       0  4032.9     .05       0  4161.5     .07       0
  4574.4     .05       0  4580.8    .035       0    4861     .15       0
  4923.8     .05       0    4968     .15       0  5094.3    .035       0
  5470.7     .05       0  5474.9    .035       0  5619.6     .05       0
Bank Sta=4923.8,4968
XS Rating Curve= 0 ,0
Exp/Cntr=0.3,0.1

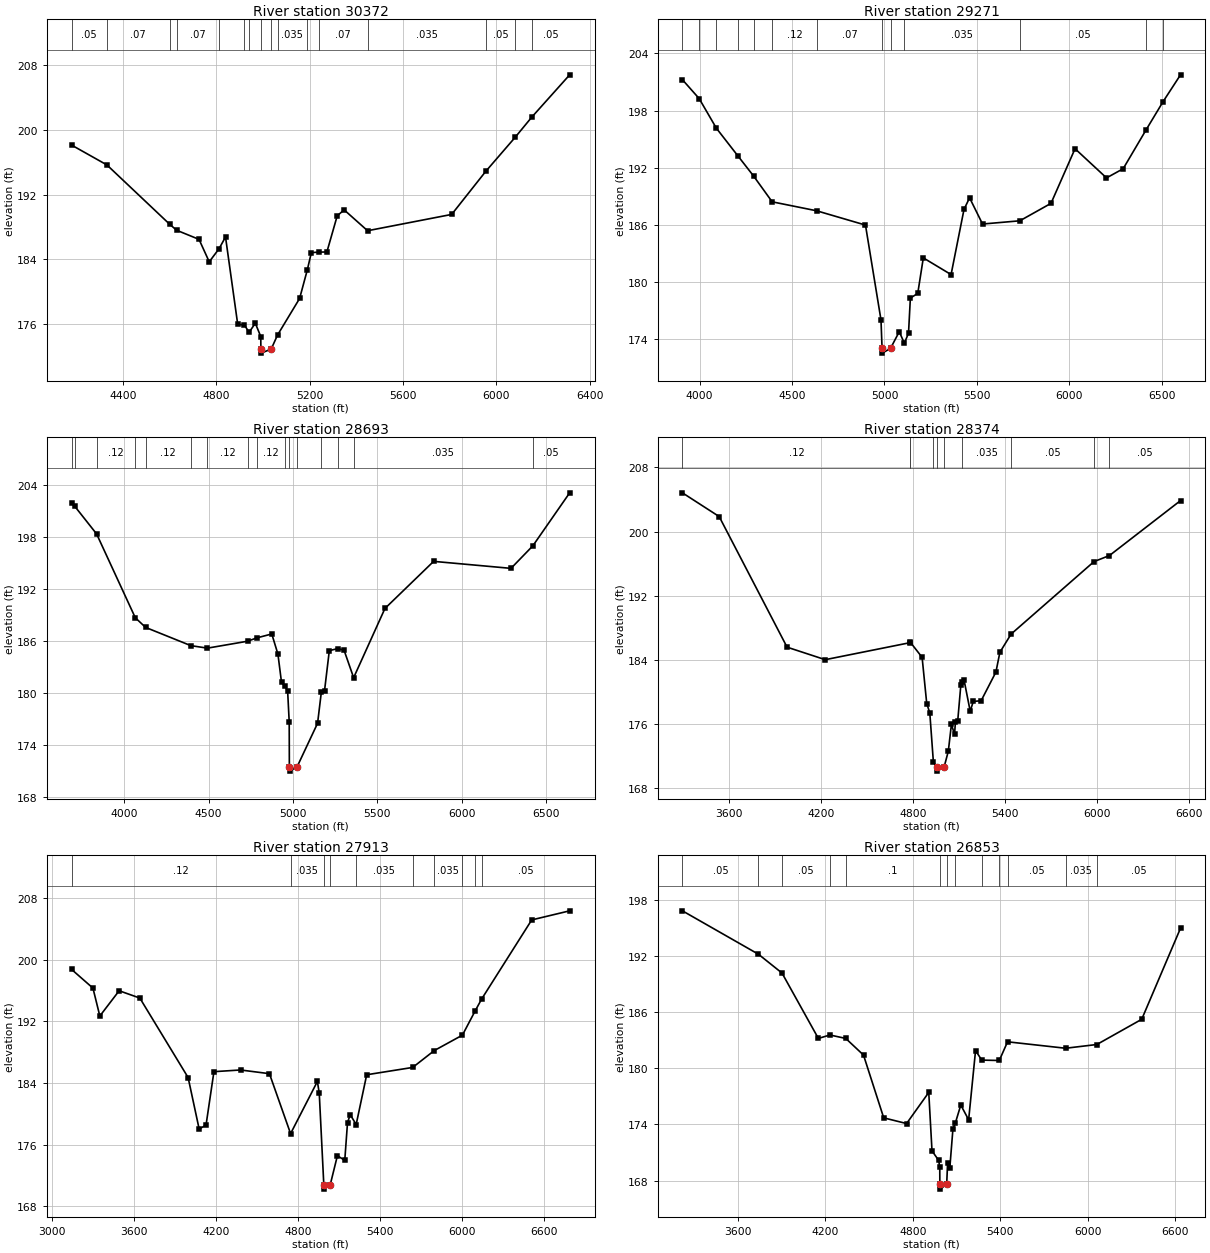
Type RM Length L Ch R = 1 ,30372   ,1101,1101,1101
BEGIN DESCRIPTION:
EIGHTEENMILE CREEK 50.0
END DESCRIPTION:
XS GIS Cut Line= 3
      2485974.96     13499575.02      2486725.35     13499245.15
      2487324.98     13498075.04
#Sta/Elev= 30
  4180.3  198.13  4331.7  195.67  4600.4  188.33  4630.5  187.58  4726.5  186.45
  4770.2  183.67  4812.5   185.3    4840  186.75  4892.2  175.94  4921.2  175.83
    4941  174.94  4967.7  176.06  4991.1  174.41  4991.5  172.86  4992.5  172.36
  5035.7  172.86  5062.9   174.6  5157.5  179.13  5190.4  182.66  5207.8  184.81
  5239.6  184.87  5274.4  184.89  5318.8  189.38  5348.5   190.1  5448.8  187.52
  5809.2  189.54  5954.8  194.86  6080.6  199.07  6152.1  201.58  6314.8  206.83
#Mann= 16 ,-1 , 0
  4180.3     .05       0  4331.7     .07       0  4600.4     .05       0
  4630.5     .07       0  4812.5     .12       0  4921.2    .035       0
    4941     .15       0  4991.5     .05       0  5035.7     .15       0
  5062.9    .035       0  5190.4     .15       0  5239.6     .07       0
  5448.8    .035       0  5954.8     .05       0  6080.6    .035       0
  6152.1     .05       0
Bank Sta=4991.5,5035.7
XS Rating Curve= 0 ,0
Exp/Cntr=0.3,0.1

Type RM Length L Ch R = 1 ,29271   ,578,578,578
BEGIN DESCRIPTION:
EIGHTEENMILE CREEK 49.0
END DESCRIPTION:
XS GIS Cut Line= 3
      2487079.83     13500939.67        2487325.       13499875.
        2487375.     13498275.02
#Sta/Elev= 30
  3907.5  201.24  3998.1  199.26  4091.2  196.15  4207.8  193.24  4292.2  191.14
  4392.8  188.43  4633.3  187.49  4897.4  185.99  4981.2  176.05  4987.1  173.06
  4988.1  172.56  5032.9  173.06  5080.1  174.81  5107.5   173.6  5130.1  174.65
  5140.1  178.33  5180.1  178.83  5210.1  182.55  5360.2   180.8  5430.2  187.64
  5460.3  188.85  5530.3   186.1  5732.1  186.44  5900.5  188.27  6030.5     194
  6200.6  190.94  6290.7   191.9  6414.1  195.96  6506.6  198.94  6600.8  201.75
#Mann= 13 ,-1 , 0
  3907.5     .12       0  3998.1    .035       0  4091.2     .12       0
  4207.8    .035       0  4292.2     .07       0  4392.8     .12       0
  4633.3     .07       0  4987.1     .05       0  5032.9     .07       0
  5107.5    .035       0  5732.1     .05       0  6414.1    .035       0
  6506.6     .05       0
Bank Sta=4987.1,5032.9
XS Rating Curve= 0 ,0
Exp/Cntr=0.3,0.1

Type RM Length L Ch R = 1 ,28693   ,319,319,319
BEGIN DESCRIPTION:
EIGHTEENMILE CREEK 48.0
END DESCRIPTION:
XS GIS Cut Line= 3
      2487174.98     13500975.03        2487875.       13499875.
      2487475.01     13498275.02
#Sta/Elev= 30
    3688  201.99  3706.2  201.61  3836.5  198.39  4065.7   188.7  4126.8  187.58
    4395  185.47  4493.6  185.18  4731.4  185.98  4785.1  186.36    4875  186.82
  4911.4  184.49  4932.6  181.23  4952.4  180.81    4969  180.21  4978.3  176.64
  4979.2  171.45  4980.2  170.95  5025.1  171.45  5146.5  176.49    5169  180.13
  5187.7  180.25  5216.1  184.89  5266.4  185.13  5303.7  184.93  5360.3  181.76
  5545.9  189.77  5834.5  195.22  6293.2  194.41  6422.8  197.02  6641.1  203.15
#Mann= 16 ,-1 , 0
    3688     .07       0  3706.2    .035       0  3836.5     .12       0
  4065.7    .035       0  4126.8     .12       0    4395     .07       0
  4493.6     .12       0  4731.4     .07       0  4785.1     .12       0
  4952.4      .1       0  4979.2     .05       0  5025.1      .1       0
    5169    .035       0  5266.4     .05       0  5360.3    .035       0
  6422.8     .05       0
Bank Sta=4979.2,5025.1
XS Rating Curve= 0 ,0
Exp/Cntr=0.3,0.1

Type RM Length L Ch R = 1 ,28374   ,461,461,461
BEGIN DESCRIPTION:
Mapping XS 75110ab9
END DESCRIPTION:
XS GIS Cut Line= 3
      2488058.69     13501474.12      2488162.86     13499765.77
      2487871.31     13498259.44
#Sta/Elev= 30
    3298  204.84  3537.6  201.88    3980  185.59  4228.8  184.03  4783.4  186.16
  4784.2  186.18    4860  184.32  4890.1  178.56  4910.1  177.39  4933.6  171.22
  4957.3  170.63  4958.3  170.13  5003.2  170.63  5030.7  172.61    5051  175.97
  5071.4   174.7  5076.9  176.26  5091.8  176.34  5112.2  180.85  5121.6  181.19
  5133.7  181.46  5173.3  177.61  5193.6  178.82  5244.6  178.91  5340.8  182.48
  5366.8  184.95  5439.7  187.22  5979.9  196.26  6080.9  197.02  6543.8  203.87
#Mann= 10 ,-1 , 0
    3298     .12       0  4783.4     .07       0  4784.2     .12       0
  4933.6      .1       0  4957.3     .05       0  5003.2      .1       0
  5121.6    .035       0  5439.7     .05       0  5979.9    .035       0
  6080.9     .05       0
Bank Sta=4957.3,5003.2
XS Rating Curve= 0 ,0
Exp/Cntr=0.3,0.1

Type RM Length L Ch R = 1 ,27913   ,1060,1060,1060
BEGIN DESCRIPTION:
Mapping XS e3728514
END DESCRIPTION:
XS GIS Cut Line= 4
       2488794.8     13501619.94      2488600.36     13500231.05
      2488523.97     13499203.27      2488184.18     13498038.26
#Sta/Elev= 30
  3140.7  198.75  3297.2  196.32  3347.6   192.7    3489  195.98  3640.5  195.03
  3993.9  184.72  4074.7  178.04  4125.1  178.55  4182.9  185.48  4377.6   185.7
  4589.3  185.22  4744.1  177.44  4940.3  184.21    4954  182.68  4987.5  170.74
  4988.5  170.24  5033.4  170.74  5086.7  174.57  5140.8  173.98  5160.9  178.88
  5180.9   179.9  5224.2  178.62  5301.3  185.08  5638.1  186.03  5796.2  188.22
    6002  190.22  6096.1  193.39  6143.3  194.92  6509.4  205.17  6787.3  206.35
#Mann= 10 ,-1 , 0
  3140.7     .12       0  4744.1    .035       0  4987.5     .05       0
  5033.4    .035       0  5224.2    .035       0  5638.1     .05       0
  5796.2    .035       0    6002     .05       0  6096.1    .035       0
  6143.3     .05       0
Bank Sta=4987.5,5033.4
XS Rating Curve= 0 ,0
Exp/Cntr=0.3,0.1

Type RM Length L Ch R = 1 ,26853   ,305,305,305
BEGIN DESCRIPTION:
Mapping XS e22dde66
END DESCRIPTION:
XS GIS Cut Line= 3
      2490319.33     13501128.78      2489458.28     13499583.95
      2488850.63     13498056.14
#Sta/Elev= 30
  3221.7  196.87    3743  192.22  3904.1  190.21  4153.3  183.21  4232.4  183.58
    4341  183.21  4462.5  181.43    4601  174.71  4757.6   174.1  4909.6  177.43
  4931.8  171.18  4977.6  170.15  4985.1   169.4  4985.5  167.58  4986.5  167.08
  5032.4  167.58  5038.7  169.88  5053.7  169.32  5075.2  173.52  5091.7  174.15
  5129.1  176.08  5182.9   174.5  5230.2  181.91  5272.8  180.89  5392.8  180.85
  5449.5  182.85  5847.2  182.16  6061.2  182.56  6368.8  185.26  6634.5  195.01
#Mann= 13 ,-1 , 0
  3221.7     .05       0    3743    .035       0  3904.1     .05       0
  4232.4     .07       0    4341      .1       0  4985.5     .05       0
  5032.4      .1       0  5091.7     .07       0  5272.8     .05       0
  5392.8    .035       0  5449.5     .05       0  5847.2    .035       0
  6061.2     .05       0
Bank Sta=4985.5,5032.4
XS Rating Curve= 0 ,0
Exp/Cntr=0.3,0.1

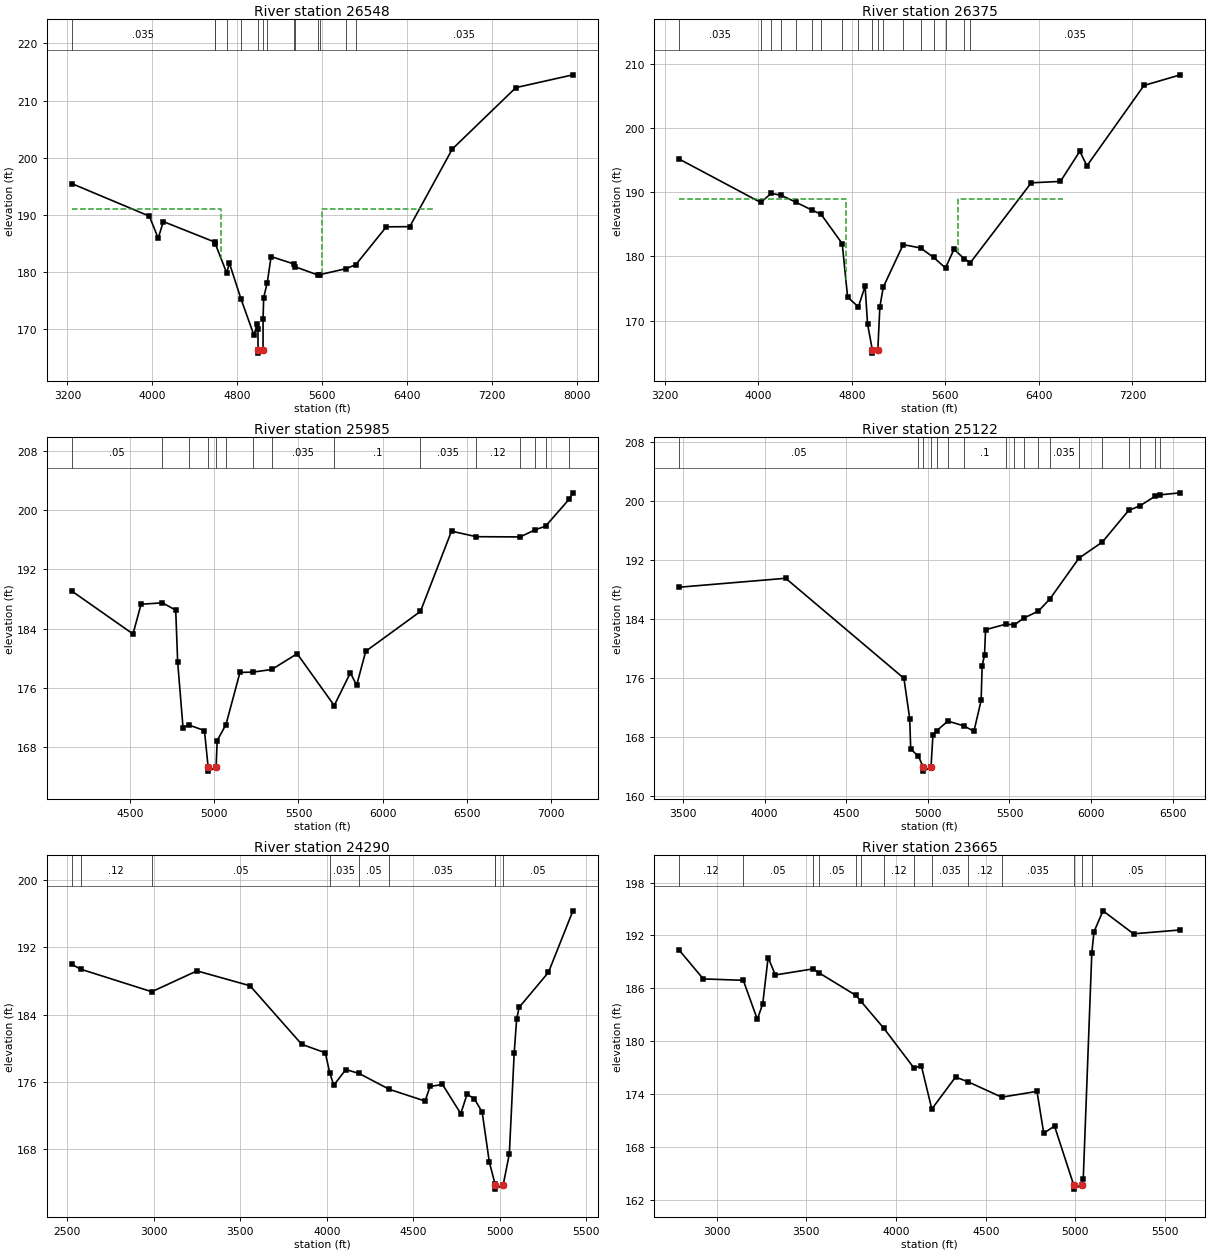
Type RM Length L Ch R = 1 ,26548   ,173,173,173
BEGIN DESCRIPTION:
Mapping XS 13835406
END DESCRIPTION:
XS GIS Cut Line= 2
      2490381.85     13501107.99      2488627.96     13496725.95
#Sta/Elev= 30
  3241.1  195.48    3972  189.78  4055.5  185.93  4103.9  188.83  4588.8  185.24
  4592.8  184.97  4700.2  179.85  4725.8  181.56  4835.9  175.25  4956.9  168.96
  4989.3  170.91    4995     170  4995.7  166.31  4996.7  165.81  5042.7  166.31
  5043.1  171.82  5048.8  175.54    5083  178.16  5118.5  182.71  5330.1  181.43
  5344.8  180.92  5559.6  179.48  5577.2  179.54  5824.3  180.59  5916.4  181.29
  6203.7  187.91  6424.4  187.94  6825.5  201.53  7423.6  212.27  7961.1  214.51
#Mann= 14 ,-1 , 0
  3241.1    .035       0  4588.8      .1       0  4592.8    .035       0
  4700.2    .063       0  4835.9    .035       0  4995.7    .035       0
  5042.7    .035       0    5083    .035       0  5330.1     .05       0
  5344.8    .035       0  5559.6    .063       0  5577.2    .035       0
  5824.3     .05       0  5916.4    .035       0
#XS Ineff= 2 ,-1
    3238    4650     191    5600    6658     191
Permanent Ineff=
       F       F
Bank Sta=4995.7,5042.7
XS Rating Curve= 0 ,0
Exp/Cntr=0.3,0.1

Type RM Length L Ch R = 1 ,26375   ,390,390,390
BEGIN DESCRIPTION:
Mapping XS 2bbaf439
END DESCRIPTION:
XS GIS Cut Line= 2
      2490473.04     13500993.46      2488970.01     13496981.25
#Sta/Elev= 30
  3324.9  195.21  4022.4  188.43  4111.9  189.85  4197.5  189.55  4324.7  188.46
    4458  187.26  4537.6   186.6  4718.6  182.01  4764.9  173.66  4856.8  172.13
  4914.4  175.36  4935.7  169.42  4976.3  165.41  4977.3  164.91  5023.3  165.41
  5040.5  172.12  5069.7  175.21  5239.7  181.85    5389  181.33  5500.2  179.85
  5601.8  178.21  5674.5  181.13  5760.8  179.66  5814.7  179.04  6334.6   191.5
  6584.4  191.72    6750  196.43  6810.5  194.15  7298.5   206.7  7609.4  208.36
#Mann= 18 ,-1 , 0
  3324.9    .035       0  4022.4    .063       0  4111.9    .035       0
  4197.5    .063       0  4324.7    .035       0    4458    .063       0
  4537.6    .035       0  4718.6    .063       0  4856.8    .035       0
  4976.3     .05       0  5023.3    .035       0  5069.7    .035       0
  5239.7    .063       0    5389    .035       0  5500.2    .063       0
  5601.8    .035       0  5760.8    .063       0  5814.7    .035       0
#XS Ineff= 2 ,-1
    3316    4750     189    5711    6610     189
Permanent Ineff=
       F       F
Bank Sta=4976.3,5023.3
XS Rating Curve= 0 ,0
Exp/Cntr=0.3,0.1

Type RM Length L Ch R = 1 ,25985   ,863,863,863
BEGIN DESCRIPTION:
Mapping XS f61cfe3a
END DESCRIPTION:
XS GIS Cut Line= 3
      2490507.24     13500078.15      2490231.19     13499296.87
      2489319.46     13497352.09
#Sta/Elev= 30
  4153.6  189.08  4517.5  183.27  4565.4  187.29  4692.5  187.48  4771.2  186.49
  4782.7  179.51  4814.5  170.61  4847.3  170.98  4941.8  170.21  4963.9  165.23
  4964.9  164.73  5010.9  165.23  5017.4  168.86  5069.7  171.03  5152.7  178.07
  5231.4  178.12  5341.7  178.47  5492.3   180.6  5712.5   173.6  5808.3  178.01
  5845.7  176.34  5899.6  180.93  6224.7  186.32    6409  197.17  6555.8  196.42
  6816.9  196.39  6904.1  197.34  6967.5  197.84  7107.6  201.48  7130.1  202.35
#Mann= 15 ,-1 , 0
  4153.6     .05       0  4692.5     .12       0  4847.3     .07       0
  4963.9     .05       0  5010.9     .07       0  5069.7      .1       0
  5231.4     .07       0  5341.7    .035       0  5712.5      .1       0
  6224.7    .035       0  6555.8     .12       0  6816.9    .035       0
  6904.1     .12       0  6967.5    .035       0  7107.6     .07       0
Bank Sta=4963.9,5010.9
XS Rating Curve= 0 ,0
Exp/Cntr=0.3,0.1

Type RM Length L Ch R = 1 ,25122   ,832,832,832
BEGIN DESCRIPTION:
Mapping XS df0a0258
END DESCRIPTION:
XS GIS Cut Line= 3
      2490746.82     13499979.14      2490554.11     13498776.04
      2489465.49     13497279.05
#Sta/Elev= 30
    3477  188.35  4129.3  189.56  4853.4  176.01  4888.9  170.55  4895.1   166.4
  4942.4  165.46  4972.1  163.93  4973.1  163.43  5019.1  163.93  5031.1  168.28
  5054.2   168.9  5122.2  170.21  5218.5  169.58  5282.3  168.83  5326.3  173.01
  5332.5  177.68  5347.2  179.19  5353.4  182.59  5478.6  183.35  5530.5  183.25
    5586  184.15  5676.7  185.11  5746.8  186.74  5925.6  192.29  6068.6  194.47
  6229.5  198.75  6299.1  199.38  6390.4  200.66  6423.6  200.87  6546.4  201.14
#Mann= 18 ,-1 , 0
    3477     .05       0  4942.4     .07       0  4972.1     .05       0
  5019.1     .07       0  5054.2      .1       0  5122.2     .07       0
  5218.5      .1       0  5478.6     .12       0  5530.5      .1       0
    5586    .035       0  5676.7      .1       0  5746.8    .035       0
  5925.6      .1       0  6068.6    .035       0  6229.5     .12       0
  6299.1      .1       0  6390.4     .07       0  6423.6      .1       0
Bank Sta=4972.1,5019.1
XS Rating Curve= 0 ,0
Exp/Cntr=0.3,0.1

Type RM Length L Ch R = 1 ,24290   ,625,625,625
BEGIN DESCRIPTION:
EIGHTEENMILE CREEK 42.0
END DESCRIPTION:
XS GIS Cut Line= 3
      2491125.01     13500175.02        2490525.       13497775.
      2490224.97     13497474.97
#Sta/Elev= 30
  2525.4  189.95  2577.5  189.37  2988.3   186.7  3249.5  189.17  3556.2  187.41
  3855.1  180.47  3991.7  179.46  4017.3  177.08  4040.7  175.62  4110.2  177.47
  4186.4  177.02  4361.9  175.13  4568.9  173.74  4597.3  175.47  4669.4  175.71
  4775.1  172.25  4811.2  174.53  4852.4  174.04  4898.8  172.44    4940  166.53
  4972.5  163.96    4973   163.8    4974   163.3  5020.4   163.8  5055.9  167.48
  5084.1  179.49  5098.3  183.46  5112.4  184.84  5282.1     189  5423.6  196.29
#Mann= 9 ,-1 , 0
  2525.4     .05       0  2577.5     .12       0  2988.3     .05       0
  4017.3    .035       0  4186.4     .05       0  4361.9    .035       0
  4972.5     .05       0    4973     .05       0  5020.4     .05       0
Bank Sta=4973,5020.4
XS Rating Curve= 0 ,0
Exp/Cntr=0.3,0.1

Type RM Length L Ch R = 1 ,23665   ,1069,1069,1069
BEGIN DESCRIPTION:
Mapping XS 9fd04ff1
END DESCRIPTION:
XS GIS Cut Line= 3
      2491260.08     13500008.82      2491072.58     13498078.27
      2491030.92     13497224.12
#Sta/Elev= 30
  2790.6  190.34  2925.1  187.07  3148.2  186.91  3226.5  182.48  3256.6  184.24
  3286.7   189.5  3326.9  187.52  3538.1  188.21  3567.9  187.79  3776.9  185.19
    3802  184.58  3932.2  181.46  4100.1  176.95    4141  177.21  4199.4  172.29
  4331.6  175.92  4399.2  175.41  4589.3  173.64  4785.9   174.3  4823.6  169.55
  4883.7  170.36  4990.1   163.7  4991.1   163.2  5037.5   163.7  5043.9  164.35
  5091.7  190.04  5103.9  192.42    5154   194.8  5324.2  192.19  5585.4  192.63
#Mann= 14 ,-1 , 0
  2790.6     .12       0  3148.2     .05       0  3538.1    .035       0
  3567.9     .05       0  3776.9    .035       0    3802     .07       0
  3932.2     .12       0  4100.1     .07       0  4199.4    .035       0
  4399.2     .12       0  4589.3    .035       0  4990.1    .035       0
  5037.5    .035       0  5091.7     .05       0
Bank Sta=4990.1,5037.5
XS Rating Curve= 0 ,0
Exp/Cntr=0.3,0.1

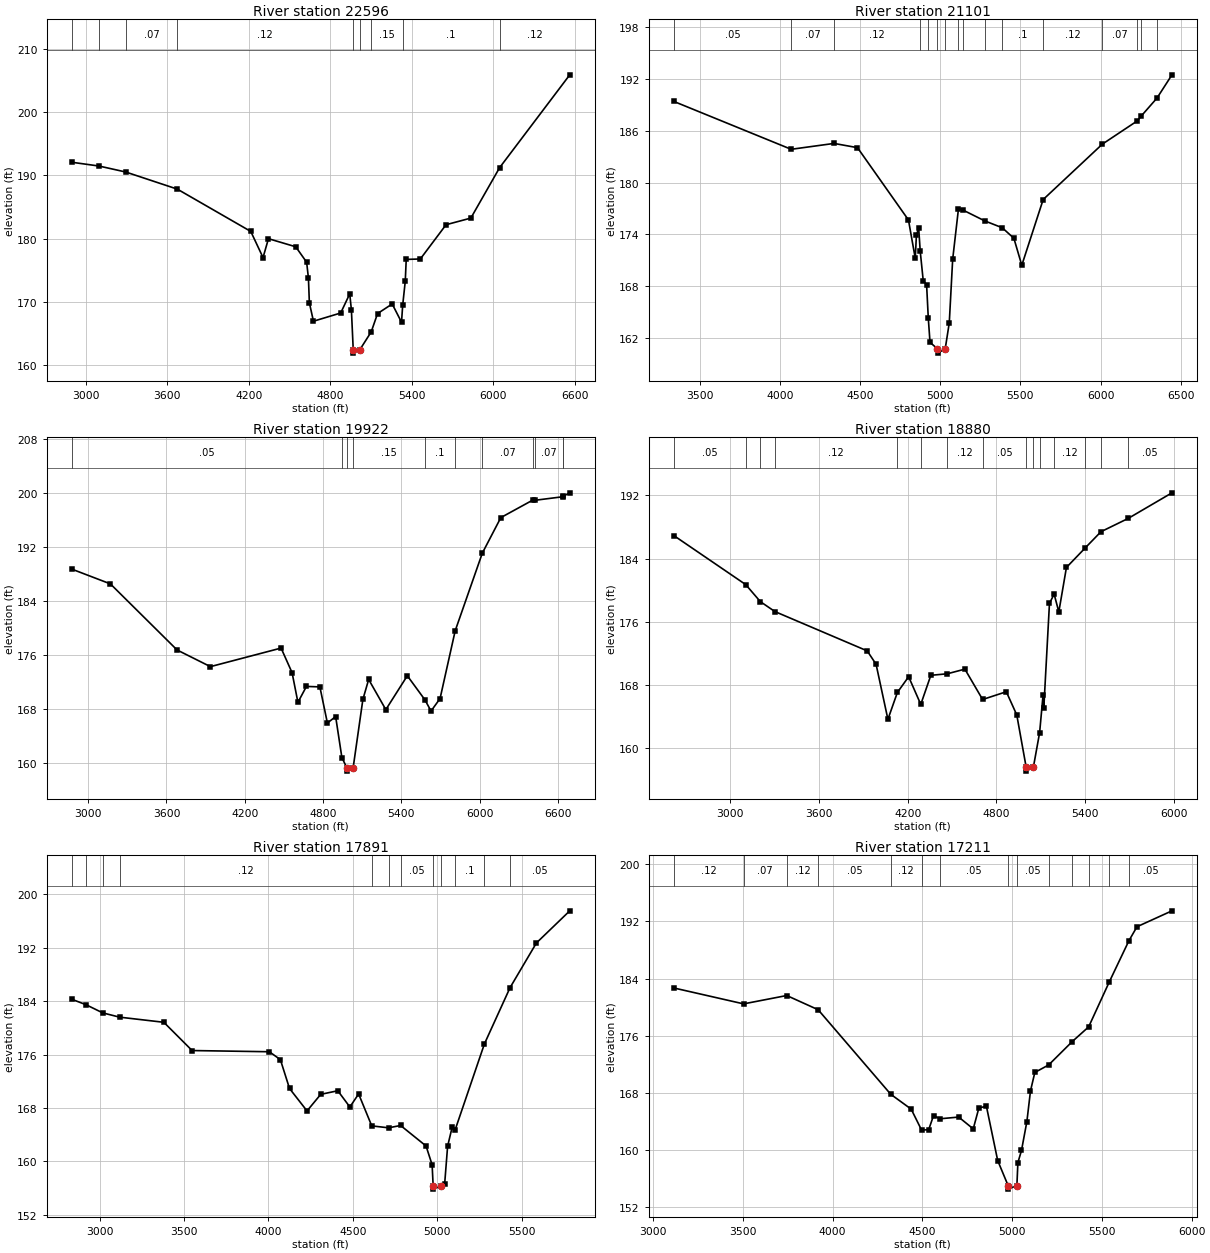
Type RM Length L Ch R = 1 ,22596   ,1495,1495,1495
BEGIN DESCRIPTION:
Mapping XS 82fddd57
END DESCRIPTION:
XS GIS Cut Line= 3
      2491898.97     13500210.25      2492037.86     13498217.16
      2491204.53     13496772.73
#Sta/Elev= 30
  2895.7  192.08    3097  191.48  3294.3  190.53    3674  187.82  4214.1  181.13
  4304.4  176.99  4344.2  179.98  4544.9   178.7  4625.1  176.26  4638.4  173.75
  4645.2  169.84  4675.3  166.92  4875.7  168.22  4942.3  171.25  4954.5  168.72
  4968.1  162.37  4969.1  161.87  5015.5  162.37  5100.4  165.24  5146.9  168.13
  5254.7  169.65  5323.3  166.76  5331.9  169.45  5350.9  173.27  5357.9   176.7
  5461.8  176.77    5651  182.19  5833.4  183.24    6045  191.22  6561.2  205.91
#Mann= 9 ,-1 , 0
  2895.7    .035       0    3097     .12       0  3294.3     .07       0
    3674     .12       0  4968.1    .035       0  5015.5     .15       0
  5100.4     .15       0  5331.9      .1       0    6045     .12       0
Bank Sta=4968.1,5015.5
XS Rating Curve= 0 ,0
Exp/Cntr=0.3,0.1

Type RM Length L Ch R = 1 ,21101   ,1179,1179,1179
BEGIN DESCRIPTION:
Mapping XS b301bbd6
END DESCRIPTION:
XS GIS Cut Line= 3
      2494287.89     13498613.03      2493551.75     13497890.77
      2492072.56     13496432.42
#Sta/Elev= 30
  3337.4  189.42  4070.1  183.87  4337.5  184.55  4483.6  184.06  4801.8  175.68
  4844.2  171.23  4851.3  173.91  4865.5  174.74  4875.3  172.03  4893.8  168.66
  4914.9  168.18  4925.6  164.27  4936.2   161.5  4982.7  160.75  4983.7  160.25
  5031.1  160.75  5056.4  163.76  5077.6  171.12  5113.9     177  5143.9  176.81
  5278.2  175.57  5386.8  174.78  5459.5  173.56  5508.9  170.43  5642.3  178.05
  6011.6  184.47  6230.2  187.17  6254.4  187.73  6352.6  189.81  6445.9   192.5
#Mann= 16 ,-1 , 0
  3337.4     .05       0  4070.1     .07       0  4337.5     .12       0
  4875.3     .07       0  4925.6     .15       0  4982.7     .05       0
  5031.1     .15       0  5113.9     .07       0  5143.9    .035       0
  5278.2     .07       0  5386.8      .1       0  5642.3     .12       0
  6011.6     .07       0  6230.2     .12       0  6254.4     .07       0
  6352.6     .12       0
Bank Sta=4982.7,5031.1
XS Rating Curve= 0 ,0
Exp/Cntr=0.3,0.1

Type RM Length L Ch R = 1 ,19922   ,1042,1042,1042
BEGIN DESCRIPTION:
Mapping XS 250afc41
END DESCRIPTION:
XS GIS Cut Line= 3
      2494447.59     13498606.07      2494058.69     13496758.82
      2492301.72      13495960.2
#Sta/Elev= 30
  2872.6   188.8    3170   186.6    3681  176.81  3936.5  174.34  4478.1  177.09
  4562.4  173.44  4607.1  169.05  4672.3  171.41  4775.4  171.34  4832.9  165.99
  4896.2  166.94    4944  160.87  4981.9  159.36  4982.9  158.86  5030.3  159.36
  5104.9  169.48  5149.2  172.44  5280.7  167.97  5445.4  172.99  5580.8  169.41
  5627.1  167.76  5696.3  169.61  5812.2  179.65    6020  191.15    6162  196.42
  6407.4  199.02  6421.5  198.98  6637.1  199.51  6639.8  199.58  6690.3  200.09
#Mann= 11 ,-1 , 0
  2872.6     .05       0    4944     .15       0  4981.9     .05       0
  5030.3     .15       0  5580.8      .1       0  5812.2     .12       0
    6020     .07       0  6407.4     .12       0  6421.5     .07       0
  6637.1     .12       0  6639.8     .07       0
Bank Sta=4981.9,5030.3
XS Rating Curve= 0 ,0
Exp/Cntr=0.3,0.1

Type RM Length L Ch R = 1 ,18880   ,989,989,989
BEGIN DESCRIPTION:
Mapping XS f0c53bcf
END DESCRIPTION:
XS GIS Cut Line= 3
       2494607.3     13498501.91      2494648.97     13496189.38
      2494315.73     13495189.67
#Sta/Elev= 30
  2619.2  186.93  3105.6  180.72  3204.2  178.57  3302.8  177.31  3926.3  172.34
  3986.3  170.65  4066.3  163.68  4130.2  167.08  4206.4  169.07  4288.4  165.57
  4356.4  169.25    4467  169.44  4586.4  170.03  4706.3  166.19  4866.5  167.17
  4937.1  164.24  5000.6  157.63  5001.6  157.13  5049.4  157.63  5091.6  162.01
  5114.6  166.73  5119.9  165.14  5158.1  178.36  5189.7  179.51  5221.3  177.27
  5272.7  182.89  5401.1  185.39    5506  187.41  5689.8  189.09  5985.9  192.33
#Mann= 15 ,-1 , 0
  2619.2     .05       0  3105.6     .12       0  3204.2     .05       0
  3302.8     .12       0  4130.2     .05       0  4288.4     .07       0
    4467     .12       0  4706.3     .05       0  5000.6     .05       0
  5049.4     .05       0  5091.6      .1       0  5189.7     .12       0
  5401.1    .035       0    5506     .07       0  5689.8     .05       0
Bank Sta=5000.6,5049.4
XS Rating Curve= 0 ,0
Exp/Cntr=0.3,0.1

Type RM Length L Ch R = 1 ,17891   ,680,680,680
BEGIN DESCRIPTION:
Mapping XS a8b148a8
END DESCRIPTION:
XS GIS Cut Line= 3
      2495135.08     13498508.83      2495510.08     13496383.82
      2495350.35       13495606.
#Sta/Elev= 30
  2833.3  184.29  2918.3  183.47  3017.9  182.24  3117.6   181.6    3380  180.83
  3547.5   176.6    4005  176.42  4070.5  175.24  4124.6  170.92  4228.4  167.56
  4309.6  170.04  4410.7  170.58  4482.2  168.15  4534.2   170.1  4611.9  165.32
  4711.6  165.03  4782.9  165.38  4933.6  162.31  4969.6  159.49  4975.7  156.35
  4976.7  155.85  5024.6  156.35  5043.7  156.58  5061.4  162.27  5088.9  165.19
  5106.5  164.76  5279.4  177.59  5431.4  186.02  5587.6  192.71  5785.2  197.52
#Mann= 12 ,-1 , 0
  2833.3    .035       0  2918.3     .12       0  3017.9      .1       0
  3117.6     .12       0  4611.9     .05       0  4711.6    .035       0
  4782.9     .05       0  4975.7     .05       0  5024.6     .05       0
  5106.5      .1       0  5279.4     .12       0  5431.4     .05       0
Bank Sta=4975.7,5024.6
XS Rating Curve= 0 ,0
Exp/Cntr=0.3,0.1

Type RM Length L Ch R = 1 ,17211   ,486,486,486
BEGIN DESCRIPTION:
Mapping XS 732a4162
END DESCRIPTION:
XS GIS Cut Line= 4
      2495565.62     13498286.65      2496121.19     13496515.77
      2496135.08     13496272.71      2495830.14     13495669.77
#Sta/Elev= 30
  3115.2  182.68  3504.2  180.45  3744.4  181.62  3919.4  179.63  4323.9  167.79
  4437.7  165.71  4495.5  162.78    4535  162.83  4562.2  164.81  4597.9  164.36
  4702.3   164.6  4783.3  162.95  4814.8  165.88  4856.7  166.11  4919.6  158.51
  4977.5  155.01  4978.5  154.51  5026.5  155.01    5032  158.22  5052.1  159.92
  5082.1  163.97  5102.2  168.26  5126.4  170.85  5203.5   171.9  5335.1  175.18
  5426.2  177.23  5541.4  183.54  5650.4  189.29  5695.4  191.25  5890.3  193.48
#Mann= 14 ,-1 , 0
  3115.2     .12       0  3504.2     .07       0  3744.4     .12       0
  3919.4     .05       0  4323.9     .12       0  4495.5    .035       0
  4597.9     .05       0  4977.5     .05       0  5026.5     .05       0
  5203.5     .12       0  5335.1    .035       0  5426.2     .12       0
  5541.4    .035       0  5650.4     .05       0
Bank Sta=4977.5,5026.5
XS Rating Curve= 0 ,0
Exp/Cntr=0.3,0.1