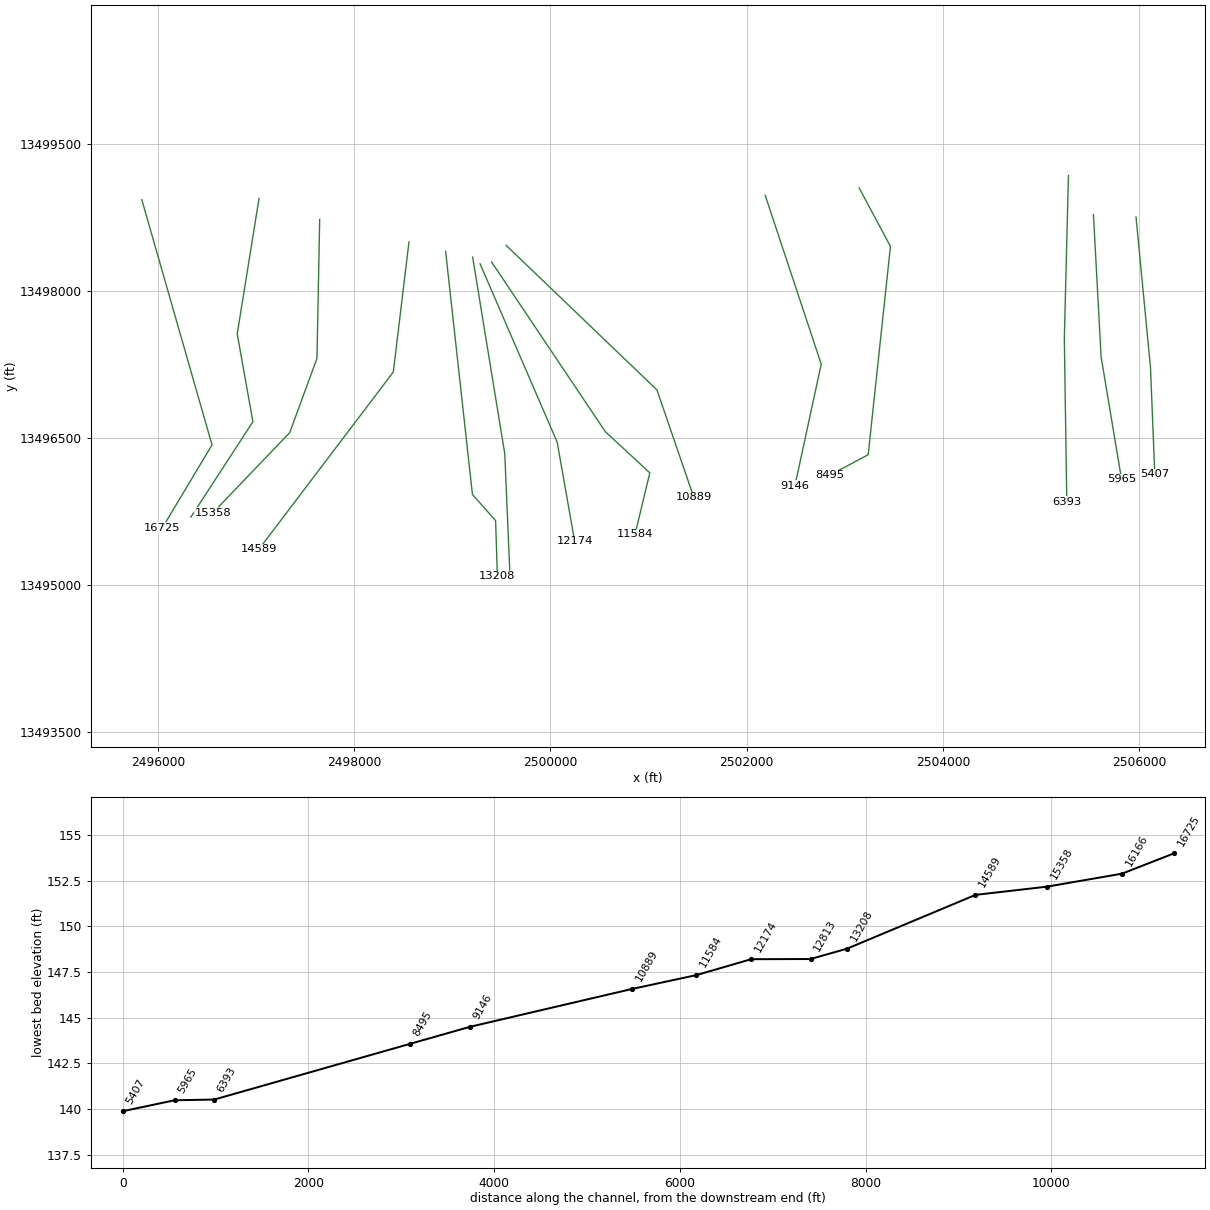
HEC-RAS study EIGHTEENMILE CREEK.prj: EIGHTEENMILE CREEK Base Level Engineering

--- EIGHTEENMILE CREEK.g01 (geometry) --- (continued)

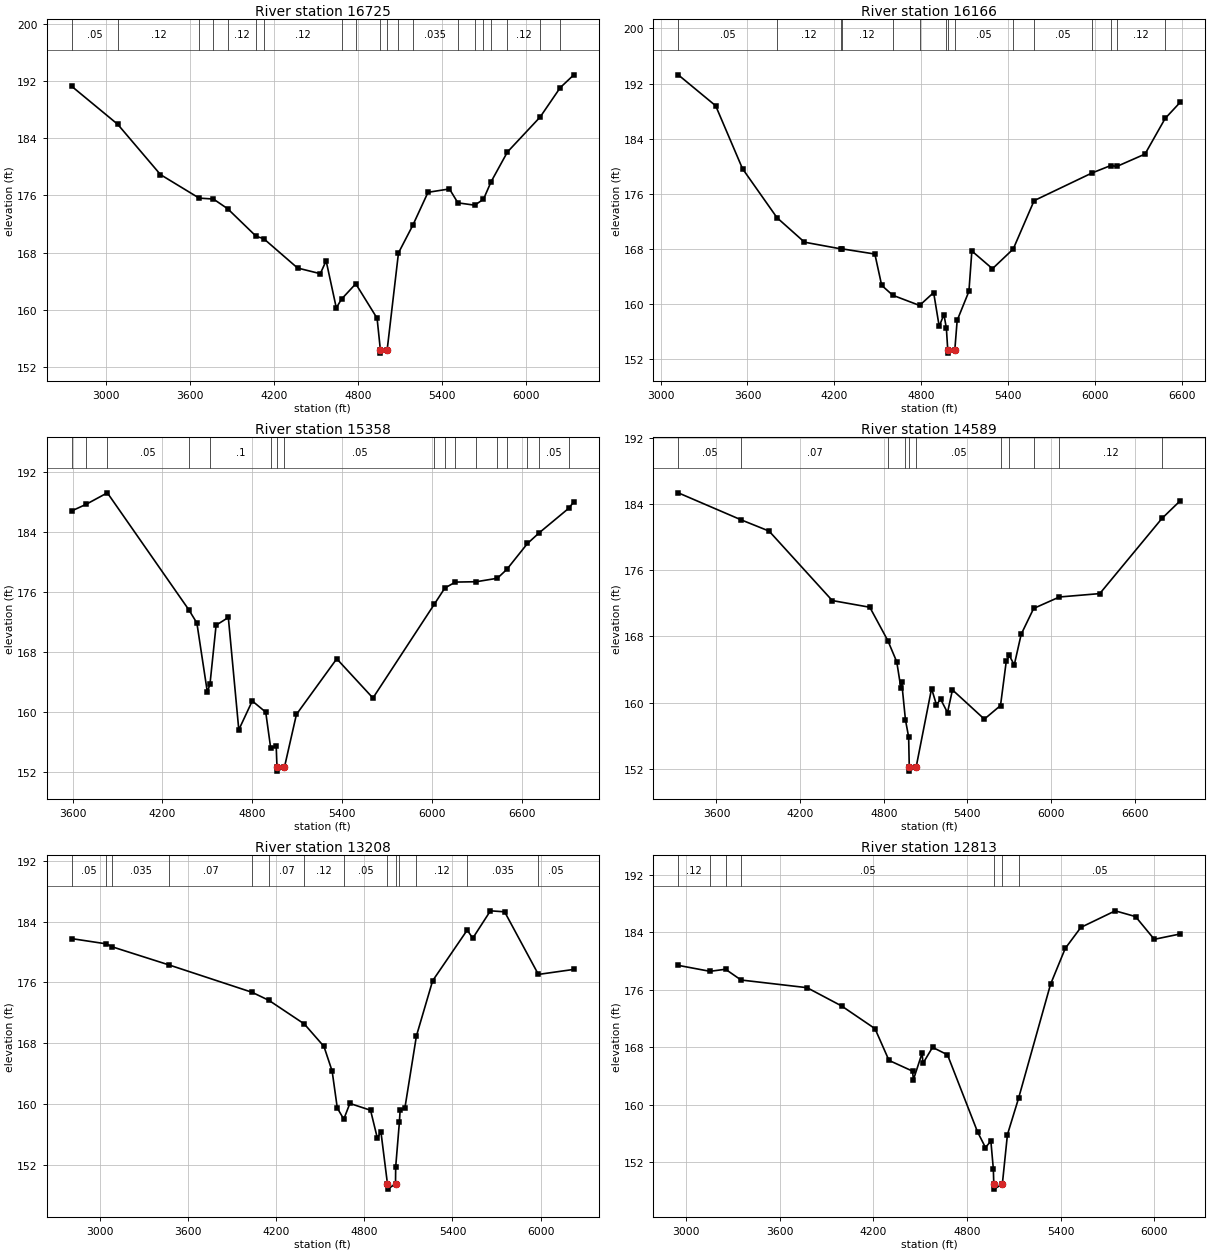
Type RM Length L Ch R = 1 ,16725   ,559,559,559
BEGIN DESCRIPTION:
Mapping XS b7aeb725
END DESCRIPTION:
XS GIS Cut Line= 3
      2495836.48     13498932.42      2496551.75     13496432.44
       2496044.8     13495585.21
#Sta/Elev= 30
  2756.4  191.23  3084.3  185.94  3390.3  178.91  3666.6  175.63  3768.4   175.5
  3870.1  174.15  4074.3  170.29  4127.2  169.98  4369.9  165.87  4532.3  165.08
  4573.9  166.88  4646.7   160.3  4683.9  161.53  4785.7  163.67    4938  158.86
  4961.3  154.49  4962.3  153.99  5010.3  154.49  5090.9  167.98  5192.6  171.81
    5302  176.44  5455.1  176.91  5515.4  174.97  5635.7  174.64  5698.2  175.47
  5752.6  177.91  5869.5  182.07  6103.3  186.95  6246.7  191.05    6344  192.84
#Mann= 20 ,-1 , 0
  2756.4     .05       0  3084.3     .12       0  3666.6    .035       0
  3768.4     .12       0  3870.1     .12       0  4074.3     .05       0
  4127.2     .12       0  4683.9    .035       0  4785.7     .05       0
  4961.3     .05       0  5010.3     .05       0  5090.9     .12       0
  5192.6    .035       0  5515.4     .12       0  5635.7    .035       0
  5698.2     .12       0  5752.6    .035       0  5869.5     .12       0
  6103.3    .035       0  6246.7     .05       0
Bank Sta=4961.3,5010.3
XS Rating Curve= 0 ,0
Exp/Cntr=0.3,0.1

Type RM Length L Ch R = 1 ,16166   ,808,808,808
BEGIN DESCRIPTION:
Mapping XS 7083ef40
END DESCRIPTION:
XS GIS Cut Line= 4
      2497030.92     13498946.35      2496808.69     13497564.38
      2496968.41     13496668.55      2496336.49     13495696.36
#Sta/Elev= 30
  3121.6  193.27  3380.3  188.78  3565.9  179.64  3804.3  172.53    3994  168.98
    4248     168  4251.1  168.02  4480.2  167.26  4527.3  162.72  4603.8  161.28
  4789.1   159.8  4886.4  161.67  4924.7  156.77  4957.5  158.48  4974.3   156.5
  4983.8  153.38  4984.8  152.88  5032.8  153.38  5048.9  157.63  5130.2  161.85
  5150.4   167.7  5292.7  165.13  5436.3  167.99  5580.7  175.01    5980  179.02
  6109.6   180.1  6152.9  179.98  6346.9  181.77  6486.1  186.94  6590.8   189.3
#Mann= 15 ,-1 , 0
  3121.6     .05       0  3804.3     .12       0    4248      .1       0
  4251.1     .12       0  4603.8     .05       0  4789.1      .1       0
  4974.3     .05       0  4983.8     .05       0  5032.8     .05       0
  5436.3    .035       0  5580.7     .05       0    5980     .07       0
  6109.6     .05       0  6152.9     .12       0  6486.1     .07       0
Bank Sta=4983.8,5032.8
XS Rating Curve= 0 ,0
Exp/Cntr=0.3,0.1

Type RM Length L Ch R = 1 ,15358   ,769,769,769
BEGIN DESCRIPTION:
Mapping XS 5bfcd1c8
END DESCRIPTION:
XS GIS Cut Line= 4
      2497648.97     13498731.05      2497621.19     13497314.38
      2497343.41     13496557.44      2496560.31     13495739.68
#Sta/Elev= 30
  3593.7  186.81  3688.6  187.67  3831.4  189.21  4376.8  173.62  4429.9  171.88
  4499.9  162.67  4517.5  163.77  4558.2  171.59    4640  172.62    4710  157.67
    4800  161.51    4890  160.02    4923  155.26    4960  155.46  4965.3  152.67
  4966.3  152.17  5014.8  152.67  5095.2  159.72  5364.6  167.12  5606.5   161.9
  6017.2   174.4  6087.1  176.54  6157.5  177.33  6297.9  177.38  6438.2  177.84
  6501.3  179.02  6639.4  182.47  6718.9  183.91  6915.5  187.16  6949.2  188.02
#Mann= 17 ,-1 , 0
  3593.7     .05       0  3688.6     .07       0  3831.4     .05       0
  4376.8     .12       0  4517.5      .1       0    4923     .05       0
  4965.3     .05       0  5014.8     .05       0  6017.2    .035       0
  6087.1     .05       0  6157.5     .07       0  6297.9    .035       0
  6438.2     .07       0  6501.3    .035       0  6639.4     .07       0
  6718.9     .05       0  6915.5     .07       0
Bank Sta=4965.3,5014.8
XS Rating Curve= 0 ,0
Exp/Cntr=0.3,0.1

Type RM Length L Ch R = 1 ,14589   ,1381,1381,1381
BEGIN DESCRIPTION:
Mapping XS 840170ab
END DESCRIPTION:
XS GIS Cut Line= 3
       2498558.7      13498501.9      2498398.97     13497175.49
      2497030.91     13495369.93
#Sta/Elev= 30
  3325.7  185.33  3777.9  182.06  3977.3  180.71  4430.5  172.32  4699.9  171.51
  4829.1  167.48  4893.1  164.92  4922.2  161.81  4928.5  162.46  4955.4  157.92
  4978.4  155.84  4982.8  152.22  4983.8  151.72  5032.3  152.22  5142.8  161.69
  5178.1  159.72  5207.2  160.42  5257.2  158.79  5292.6  161.53  5521.4     158
  5637.3  159.64  5678.6  164.99  5700.7  165.69  5735.7  164.53  5785.6  168.25
  5875.2  171.37  6059.6  172.75  6349.4  173.16  6794.9  182.23    6927  184.38
#Mann= 11 ,-1 , 0
  3325.7     .05       0  3777.9     .07       0  4829.1     .12       0
  4955.4     .05       0  4982.8     .05       0  5032.3     .05       0
  5637.3     .12       0  5700.7     .05       0  5875.2    .035       0
  6059.6     .12       0  6794.9     .05       0
Bank Sta=4982.8,5032.3
XS Rating Curve= 0 ,0
Exp/Cntr=0.3,0.1

Type RM Length L Ch R = 1 ,13208   ,395,395,395
BEGIN DESCRIPTION:
Mapping XS 7b49e9f5
END DESCRIPTION:
XS GIS Cut Line= 4
      2498931.98     13498406.31      2499205.29       13495927.
      2499441.31      13495660.4      2499459.76       13495094.
#Sta/Elev= 30
  2808.8  181.75  3044.6  181.06  3084.1  180.67  3473.5  178.27  4035.5  174.69
  4150.2  173.63  4391.3  170.52  4525.1  167.56  4580.8  164.32    4616  159.45
  4660.1  157.99  4701.5  160.06  4842.4  159.16  4888.7  155.48  4912.8  156.34
  4957.3  149.48  4958.4  148.78  5012.1  149.48  5013.4  151.71  5038.7  157.62
  5043.6  159.21  5075.6  159.41  5154.6  168.95  5264.9  176.21    5500  182.87
    5538  181.81  5658.2  185.41  5754.7  185.28  5984.5  177.04  6225.9   177.7
#Mann= 14 ,-1 , 0
  2808.8     .05       0  3044.6     .07       0  3084.1    .035       0
  3473.5     .07       0  4035.5     .12       0  4150.2     .07       0
  4391.3     .12       0  4660.1     .05       0  4957.3    .035       0
  5012.1     .05       0  5038.7     .05       0  5154.6     .12       0
    5500    .035       0  5984.5     .05       0
Bank Sta=4957.3,5012.1
XS Rating Curve= 0 ,0
Exp/Cntr=0.3,0.1

Type RM Length L Ch R = 1 ,12813   ,639,639,639
BEGIN DESCRIPTION:
Mapping XS 0ec3c34b
END DESCRIPTION:
XS GIS Cut Line= 3
      2499207.52     13498347.58        2499535.     13496340.69
      2499585.31      13495158.4
#Sta/Elev= 30
  2950.7  179.39  3154.2  178.56  3253.7  178.85  3353.1  177.35  3776.2  176.28
  3996.9  173.74  4211.4  170.57  4300.9  166.15  4452.1  164.65  4457.2  163.44
  4513.5  167.19  4518.6  165.73    4580  167.97  4675.8  166.93  4868.3  156.19
    4919  154.01  4953.8   154.9  4969.6  151.01  4972.4  148.91  4973.6  148.21
  5027.2  148.91  5059.9  155.81  5130.8  160.84    5336  176.75  5430.2  181.75
  5530.3  184.68  5750.5  186.99  5880.6  186.19  6000.7  183.02  6167.5  183.77
#Mann= 7 ,-1 , 0
  2950.7     .12       0  3154.2     .07       0  3253.7    .035       0
  3353.1     .05       0  4972.4     .05       0  5027.2     .05       0
  5130.8     .05       0
Bank Sta=4972.4,5027.2
XS Rating Curve= 0 ,0
Exp/Cntr=0.3,0.1

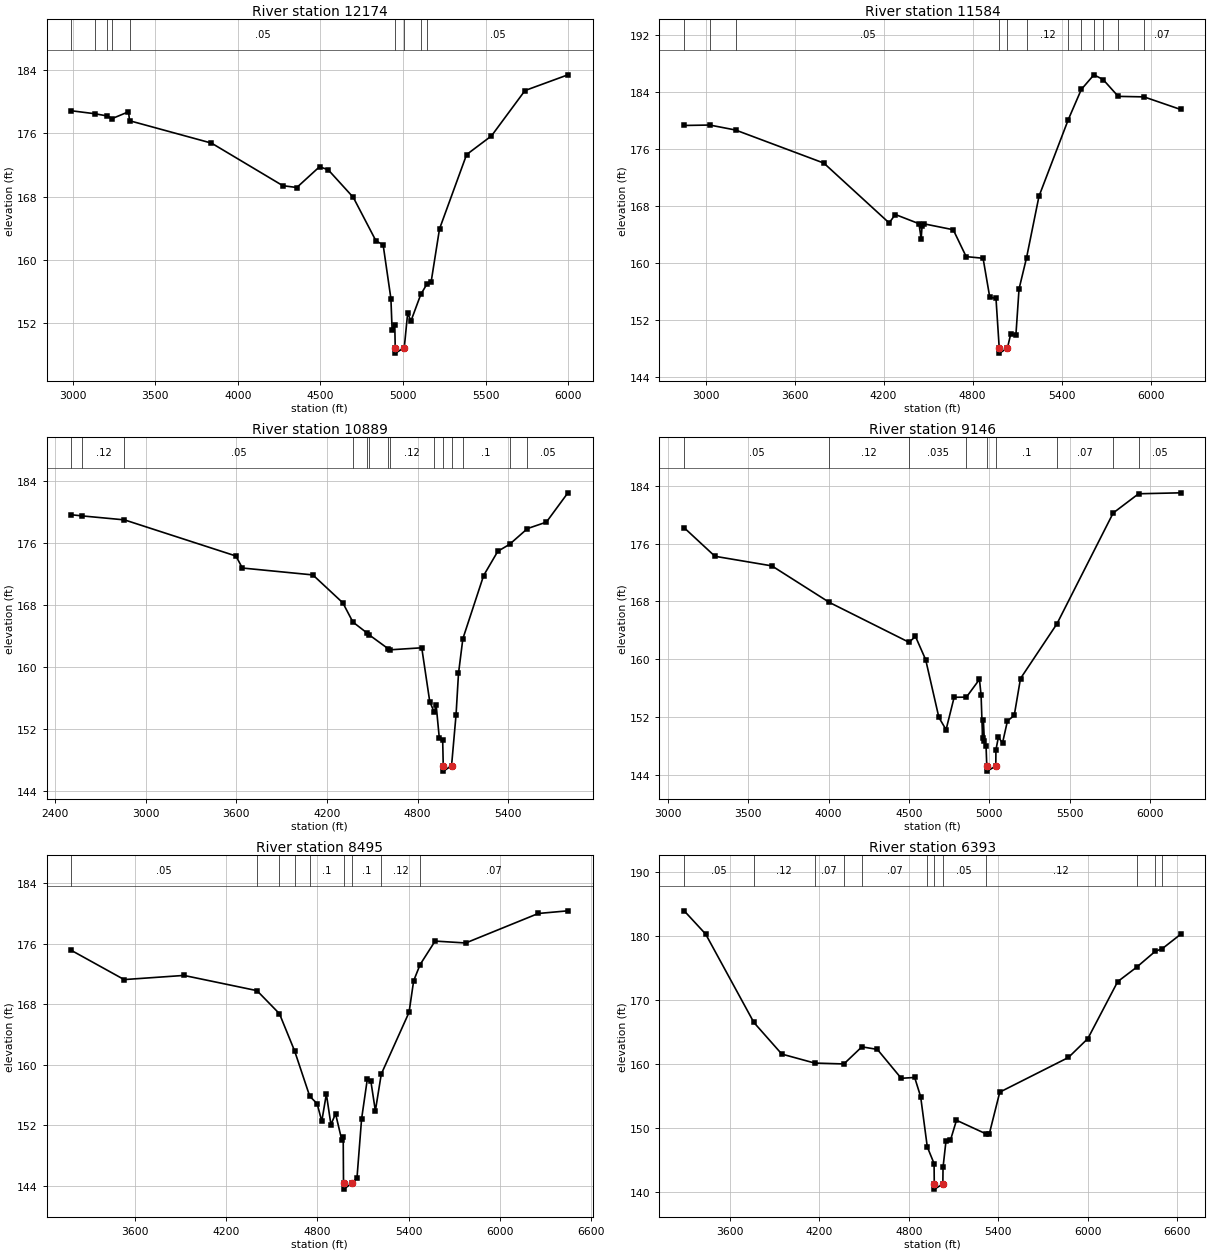
Type RM Length L Ch R = 1 ,12174   ,590,590,590
BEGIN DESCRIPTION:
Mapping XS c574ea8a
END DESCRIPTION:
XS GIS Cut Line= 3
      2499283.54     13498277.88      2500069.13     13496459.28
      2500246.91     13495449.03
#Sta/Elev= 30
  2992.1  178.87  3131.9   178.5  3207.9  178.22    3238  177.88  3337.3  178.74
  3344.1  177.61    3840  174.78  4272.2  169.39  4356.9  169.16  4494.6  171.79
  4547.1   171.4    4699  167.91  4836.2  162.41  4879.8   161.9  4926.8   155.1
  4934.2   151.1  4950.3  151.81  4952.9   148.9  4954.1   148.2  5007.8   148.9
  5028.2  153.24  5048.5  152.28  5107.8  155.63  5146.1  156.98  5170.4   157.2
  5221.2  163.92  5385.4  173.33  5535.9  175.69    5739  181.43  5998.9  183.42
#Mann= 9 ,-1 , 0
  2992.1     .12       0  3131.9     .07       0  3207.9     .12       0
    3238    .035       0  3344.1     .05       0  4952.9     .05       0
  5007.8     .05       0  5107.8     .12       0  5146.1     .05       0
Bank Sta=4952.9,5007.8
XS Rating Curve= 0 ,0
Exp/Cntr=0.3,0.1

Type RM Length L Ch R = 1 ,11584   ,695,695,695
BEGIN DESCRIPTION:
Mapping XS a80bdf38
END DESCRIPTION:
XS GIS Cut Line= 4
      2499400.65     13498297.17      2500559.42     13496567.41
      2501012.85     13496147.56      2500861.97      13495518.9
#Sta/Elev= 30
  2855.8  179.34  3028.2   179.4    3202   178.7  3797.3  174.05  4237.4  165.64
  4279.4  166.82  4438.5  165.53  4453.5   163.4  4459.5  165.21  4474.5   165.5
  4669.6  164.68  4756.7   160.9  4870.8  160.67  4915.8  155.19  4957.8  155.03
  4979.7  148.03  4980.9  147.33  5034.7  148.03  5056.5  149.96  5092.2  149.91
  5113.2  156.35  5163.6  160.72  5247.6  169.38  5445.3  180.17  5533.1  184.41
  5617.9  186.46  5679.8   185.8  5781.9  183.43  5955.6  183.36  6202.3  181.59
#Mann= 12 ,-1 , 0
  2855.8     .07       0  3028.2     .12       0    3202     .05       0
  4979.7     .05       0  5034.7     .05       0  5163.6     .12       0
  5445.3     .07       0  5533.1     .12       0  5617.9     .07       0
  5679.8     .12       0  5781.9     .05       0  5955.6     .07       0
Bank Sta=4979.7,5034.7
XS Rating Curve= 0 ,0
Exp/Cntr=0.3,0.1

Type RM Length L Ch R = 1 ,10889   ,1743,1743,1743
BEGIN DESCRIPTION:
Mapping XS 174ace14
END DESCRIPTION:
XS GIS Cut Line= 3
       2499548.9     13498467.08      2501085.39     13496993.09
      2501460.08     13495900.23
#Sta/Elev= 30
  2510.3  179.64  2582.5  179.49    2861  178.98  3598.3  174.32  3640.8  172.77
  4107.5  171.88  4305.6  168.28  4372.2   165.8  4463.1  164.43  4479.1  164.16
  4607.6  162.33  4619.1  162.22  4827.8  162.48  4880.6  155.55  4910.7  154.15
  4922.9  155.13    4944  150.81  4966.3  150.54    4970  147.27  4971.2  146.57
    5025  147.27  5054.8  153.86  5070.9  159.17  5099.8  163.65  5237.2   171.8
    5331  174.93  5409.1  175.83  5527.4  177.86  5652.3  178.69  5794.8  182.47
#Mann= 14 ,-1 , 0
  2510.3     .05       0  2582.5     .12       0    2861     .05       0
  4372.2     .07       0  4463.1     .05       0  4479.1     .12       0
  4607.6     .05       0  4619.1     .12       0  4910.7     .05       0
    4970     .05       0    5025     .05       0  5099.8      .1       0
  5409.1     .12       0  5527.4     .05       0
Bank Sta=4970,5025
XS Rating Curve= 0 ,0
Exp/Cntr=0.3,0.1

Type RM Length L Ch R = 1 ,9146    ,651,651,651
BEGIN DESCRIPTION:
Mapping XS 2c807e50
END DESCRIPTION:
XS GIS Cut Line= 3
      2502188.41     13498977.36      2502759.41     13497255.95
      2502490.71     13496013.21
#Sta/Elev= 30
    3103  178.21  3294.2  174.26    3648  172.93  4005.4  167.87  4500.3  162.35
  4540.5  163.15  4603.9  159.93  4685.9  151.94  4730.6  150.24  4780.7  154.73
  4857.1  154.75  4938.1  157.21  4948.3  154.99  4957.3  149.04  4962.4  151.57
  4968.8  148.62    4979     148  4983.6   145.2  4984.9   144.5  5039.6   145.2
  5040.4  147.44  5055.8  149.21  5081.3  148.39    5112  151.45  5154.2  152.21
  5193.2  157.33  5419.5   164.9  5769.2  180.26    5927  182.92  6188.1  183.05
#Mann= 9 ,-1 , 0
    3103     .05       0  4005.4     .12       0  4500.3    .035       0
  4857.1      .1       0  4983.6     .05       0  5039.6      .1       0
  5419.5     .07       0  5769.2     .12       0    5927     .05       0
Bank Sta=4983.6,5039.6
XS Rating Curve= 0 ,0
Exp/Cntr=0.3,0.1

Type RM Length L Ch R = 1 ,8495    ,2102,2102,2102
BEGIN DESCRIPTION:
Mapping XS 98ea32c5
END DESCRIPTION:
XS GIS Cut Line= 4
      2503145.66     13499052.91      2503464.75     13498456.71
      2503238.03      13496332.3      2502843.38     13496122.38
#Sta/Elev= 30
  3185.9  175.11  3531.8  171.26  3924.2  171.81  4403.7   169.8  4551.4  166.75
  4650.8  161.84  4750.3  155.84  4799.1  154.85  4829.3  152.52  4859.5  156.13
  4889.6  152.08  4919.8  153.53    4960  150.12  4970.1   150.5  4972.1  144.36
  4973.4  143.56  5028.5  144.36  5060.6  145.04  5090.8  152.84  5128.9  158.16
  5151.1  157.91  5181.3  153.91  5220.1  158.77  5402.5  166.93  5432.7   171.1
    5475  173.24  5573.5  176.35  5774.6   176.1  6251.2     180  6445.6  180.35
#Mann= 9 ,-1 , 0
  3185.9     .05       0  4403.7     .12       0  4551.4     .07       0
  4650.8     .12       0  4750.3      .1       0  4972.1     .05       0
  5028.5      .1       0  5220.1     .12       0    5475     .07       0
Bank Sta=4972.1,5028.5
XS Rating Curve= 0 ,0
Exp/Cntr=0.3,0.1

Type RM Length L Ch R = 1 ,6393    ,428,428,428
BEGIN DESCRIPTION:
Mapping XS cc7f71fe
END DESCRIPTION:
XS GIS Cut Line= 3
      2505278.48     13499178.81      2505236.49     13497516.26
      2505261.68     13495853.63
#Sta/Elev= 30
  3295.5  183.96  3439.4  180.33  3762.6  166.53  3949.5   161.6  4169.2   160.2
  4365.5  160.06  4486.1  162.73  4589.7  162.33  4749.8  157.82  4839.8  157.95
  4879.8  154.95  4924.3  147.11  4969.8  144.51  4971.1  141.32  4972.4  140.52
  5028.6  141.32  5029.8  143.92  5049.8  148.08  5079.8  148.18  5119.9  151.27
  5315.5  149.17  5339.9  149.16  5409.9  155.66  5869.9  161.07    6000  164.02
    6200  172.91    6327  175.16  6451.7  177.64  6497.9  178.04  6621.4  180.29
#Mann= 12 ,-1 , 0
  3295.5     .05       0  3762.6     .12       0  4169.2     .07       0
  4365.5     .12       0  4486.1     .07       0  4924.3     .05       0
  4971.1     .05       0  5028.6     .05       0  5315.5     .12       0
    6327     .05       0  6451.7     .07       0  6497.9     .05       0
Bank Sta=4971.1,5028.6
XS Rating Curve= 0 ,0
Exp/Cntr=0.3,0.1

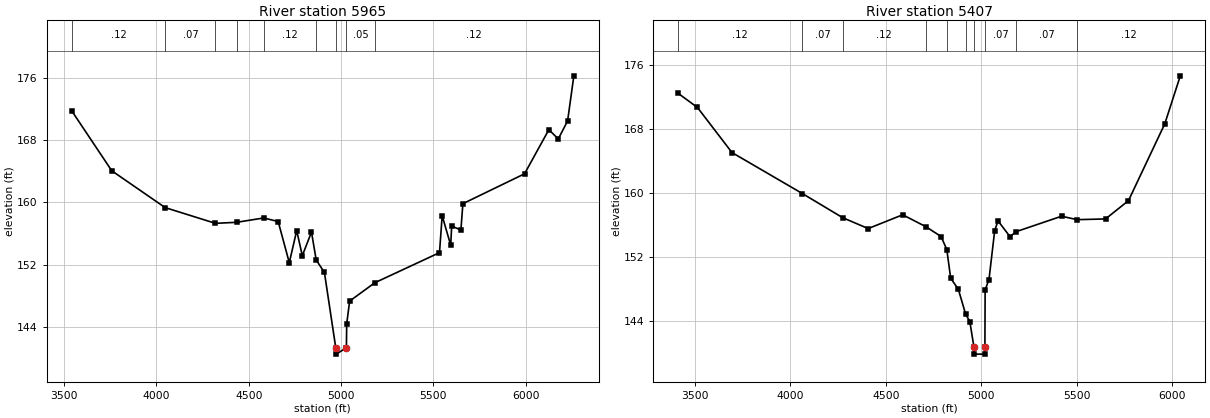
Type RM Length L Ch R = 1 ,5965    ,558,558,558
BEGIN DESCRIPTION:
Mapping XS 47bb8e3e
END DESCRIPTION:
XS GIS Cut Line= 3
      2505533.06     13498781.29      2505611.19     13497331.59
      2505819.51     13496081.63
#Sta/Elev= 30
  3541.7  171.76  3758.3  164.06  4047.7  159.32  4319.9   157.3  4434.1  157.43
  4581.3  157.99  4659.6  157.53  4719.7  152.24  4759.8  156.37  4790.2  153.14
  4839.9  156.18  4865.4  152.59    4910  150.98  4971.4  141.28  4972.8  140.48
  5028.9  141.28  5030.6  144.37  5046.5   147.3  5182.8  149.66  5533.1  153.53
  5547.6  158.29  5593.9  154.49    5599  156.95    5649  156.44  5659.8  159.83
  5993.7  163.67  6125.5  169.35  6176.2  168.15  6226.9  170.47  6260.7  176.27
#Mann= 9 ,-1 , 0
  3541.7     .12       0  4047.7     .07       0  4319.9     .12       0
  4434.1     .07       0  4581.3     .12       0  4865.4     .05       0
  4971.4     .05       0  5028.9     .05       0  5182.8     .12       0
Bank Sta=4971.4,5028.9
XS Rating Curve= 0 ,0
Exp/Cntr=0.3,0.1

Type RM Length L Ch R = 1 ,5407    ,353,353,353
BEGIN DESCRIPTION:
Mapping XS e11d43cb
END DESCRIPTION:
XS GIS Cut Line= 3
      2505967.09     13498755.22      2506114.66     13497218.75
      2506158.06     13496133.66
#Sta/Elev= 30
  3412.5   172.4  3513.2  170.64    3694  165.02  4062.5  159.91  4273.6   156.9
  4407.3  155.54  4588.1  157.26  4710.5  155.76    4789  154.55  4819.1  152.92
  4839.3  149.35  4879.4  147.97  4917.9  144.85  4939.7  143.94    4961  140.78
  4962.4  139.88  5017.3  139.88  5018.6  140.78  5019.8   147.9  5039.9  149.17
  5069.9  155.29  5087.3   156.5  5149.9  154.54  5183.9  155.17  5420.2  157.08
  5501.3  156.65  5650.3  156.74  5770.4  159.02  5960.6   168.6    6042  174.59
#Mann= 10 ,-1 , 0
  3412.5     .12       0  4062.5     .07       0  4273.6     .12       0
  4710.5     .07       0  4819.1     .12       0  4917.9     .07       0
    4961     .05       0  5018.6     .07       0  5183.9     .07       0
  5501.3     .12       0
Bank Sta=4961,5018.6
XS Rating Curve= 0 ,0
Exp/Cntr=0.3,0.1