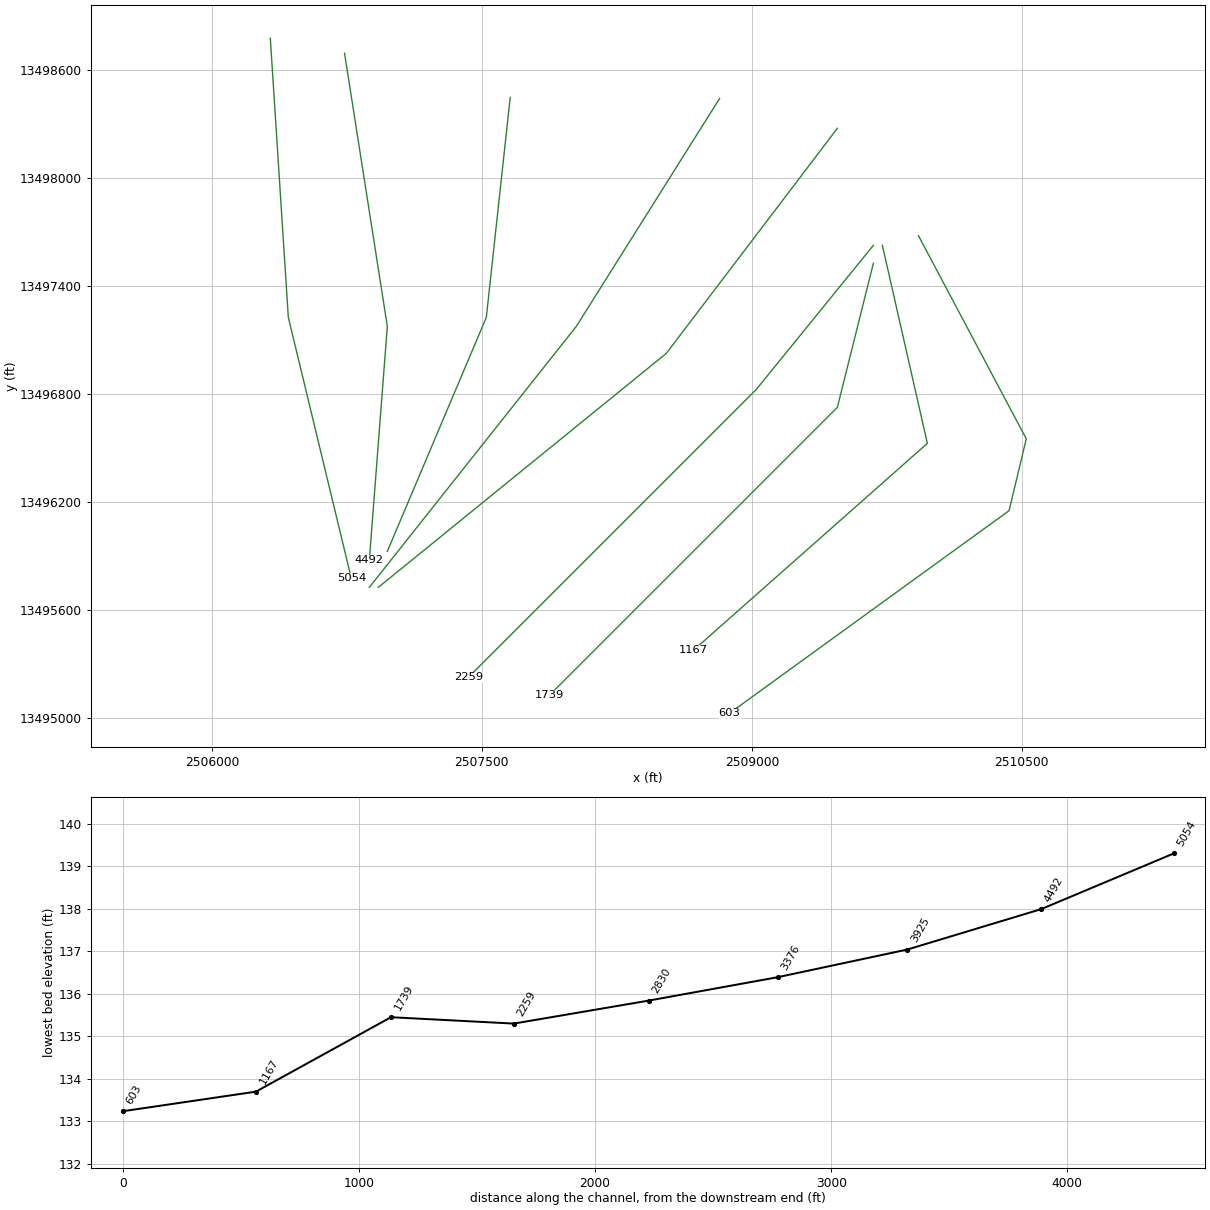
HEC-RAS study EIGHTEENMILE CREEK.prj: EIGHTEENMILE CREEK Base Level Engineering

--- EIGHTEENMILE CREEK.g01 (geometry) --- (continued)

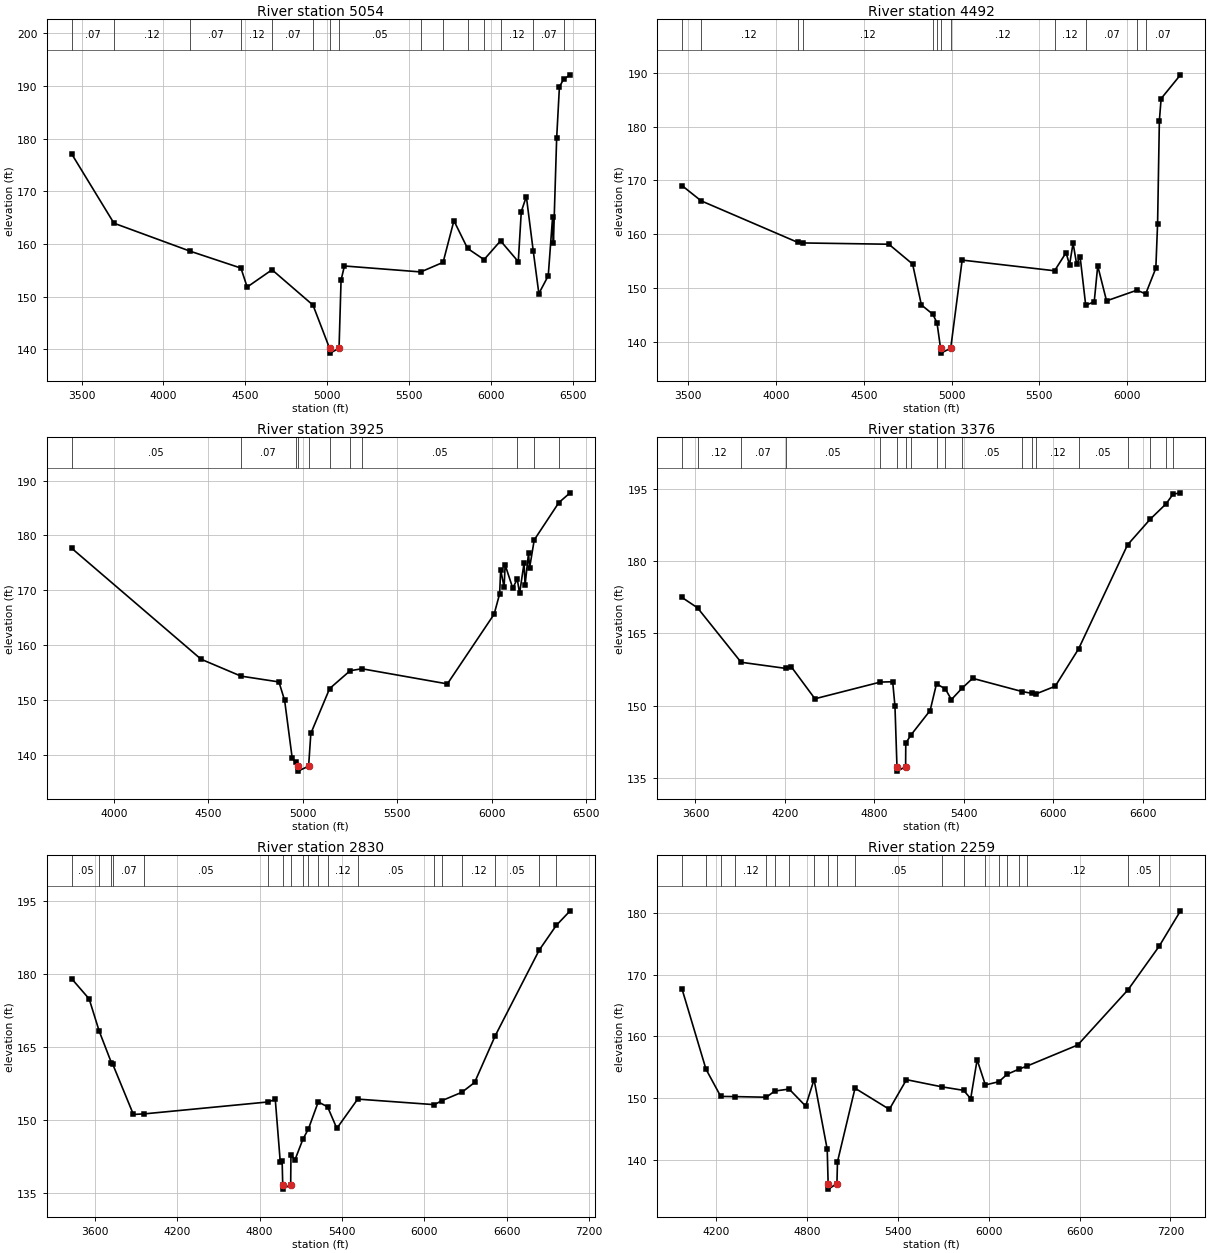
Type RM Length L Ch R = 1 ,5054    ,562,562,562
BEGIN DESCRIPTION:
EIGHTEENMILE CREEK 9.0
END DESCRIPTION:
XS GIS Cut Line= 3
        2506325.     13498774.96        2506425.       13497225.
      2506774.99     13495775.03
#Sta/Elev= 30
  3438.7  177.13  3697.3  163.96  4164.3  158.63    4473  155.44  4510.9  151.84
  4662.8  155.12  4913.1  148.41  5014.5   140.2  5015.9   139.3  5072.1   140.2
  5084.5  153.16    5105  155.84  5571.2  154.71  5707.6  156.53  5773.7  164.43
  5857.1  159.17  5957.8  157.05  6058.6  160.61  6166.8  156.66  6185.2  166.17
  6216.1  169.02  6258.1  158.72  6292.5   150.6  6349.8  153.98  6376.2  165.06
  6381.4  160.18  6401.2  180.08  6418.1  189.85  6443.7  191.27  6483.5  192.12
#Mann= 15 ,-1 , 0
  3438.7     .07       0  3697.3     .12       0  4164.3     .07       0
    4473     .12       0  4662.8     .07       0  4913.1     .05       0
  5014.5     .05       0  5072.1     .05       0  5571.2     .12       0
  5707.6     .07       0  5857.1     .12       0  5957.8     .07       0
  6058.6     .12       0  6258.1     .07       0  6443.7     .05       0
Bank Sta=5014.5,5072.1
XS Rating Curve= 0 ,0
Exp/Cntr=0.3,0.1

Type RM Length L Ch R = 1 ,4492    ,567,567,567
BEGIN DESCRIPTION:
EIGHTEENMILE CREEK 8.0
END DESCRIPTION:
XS GIS Cut Line= 3
      2506737.33     13498692.29        2506975.       13497175.
        2506875.     13495875.03
#Sta/Elev= 30
  3464.2  169.06  3573.2  166.23  4122.7  158.54  4150.9  158.42  4642.6  158.18
  4778.1   154.5  4827.9  146.93    4893   145.2  4916.9  143.62  4937.2  138.89
  4938.6  137.99    4995  138.89  5060.2  155.24  5586.6  153.26  5651.9   156.6
    5672  154.39    5692  158.38  5712.1  154.53  5732.1  155.85  5763.9  146.87
  5812.4  147.51  5832.4  154.17  5882.6  147.68  6055.8  149.66  6105.5  148.97
  6163.4  153.74  6173.4     162  6183.5  181.08  6193.5  185.18  6303.8  189.59
#Mann= 12 ,-1 , 0
  3464.2     .07       0  3573.2     .12       0  4122.7     .07       0
  4150.9     .12       0    4893     .05       0  4916.9     .12       0
  4937.2     .05       0    4995     .12       0  5586.6     .12       0
  5763.9     .07       0  6055.8     .05       0  6105.5     .07       0
Bank Sta=4937.2,4995
XS Rating Curve= 0 ,0
Exp/Cntr=0.3,0.1

Type RM Length L Ch R = 1 ,3925    ,549,549,549
BEGIN DESCRIPTION:
EIGHTEENMILE CREEK 7.0
END DESCRIPTION:
XS GIS Cut Line= 3
      2507657.65     13498446.68        2507525.       13497225.
      2506975.01     13495925.02
#Sta/Elev= 30
    3776  177.68  4461.7  157.44  4672.9  154.36  4874.1   153.3  4904.3  149.93
  4944.5  139.39  4962.6  138.64  4973.4  137.94  4974.7  137.04  5031.3  137.94
  5043.1  143.91  5142.7  152.09  5251.1  155.34  5313.4   155.7  5766.2  152.94
  6013.9  165.65  6043.1  169.37  6048.5  173.77  6066.7  170.54  6072.2  174.64
  6112.4   170.4  6136.4  172.05  6148.7  169.42  6172.4  174.99  6177.8  170.94
  6196.1  176.82  6201.5  174.05  6226.3  179.19  6356.9     186  6416.4  187.77
#Mann= 11 ,-1 , 0
    3776     .05       0  4672.9     .07       0  4962.6     .12       0
  4973.4     .05       0  5031.3     .12       0  5142.7      .1       0
  5251.1     .12       0  5313.4     .05       0  6136.4     .07       0
  6226.3    .035       0  6356.9     .07       0
Bank Sta=4973.4,5031.3
XS Rating Curve= 0 ,0
Exp/Cntr=0.3,0.1

Type RM Length L Ch R = 1 ,3376    ,546,546,546
BEGIN DESCRIPTION:
EIGHTEENMILE CREEK 6.0
END DESCRIPTION:
XS GIS Cut Line= 3
      2508820.67     13498440.55        2508025.       13497175.
      2506874.98     13495724.98
#Sta/Elev= 30
  3509.3   172.5    3614  170.33  3906.1  159.02  4204.5  157.75  4242.8  158.09
  4401.8  151.43  4840.8   154.9  4923.5  154.97  4938.8  149.88  4952.3  137.29
  4953.6  136.39  5010.2  137.29  5011.4  142.22  5048.1  143.98  5174.8  148.99
  5217.6  154.55  5277.3  153.46  5317.4  151.26  5388.1   153.6  5460.1  155.68
  5791.3  152.94  5856.6  152.56  5888.4  152.48  6014.4  154.04    6171   161.8
  6499.5  183.42  6652.3  188.78  6757.8  191.94    6805  193.96  6854.9  194.24
#Mann= 19 ,-1 , 0
  3509.3     .07       0    3614     .12       0  3906.1     .07       0
  4204.5     .05       0  4840.8      .1       0  4952.3     .05       0
  5010.2      .1       0  5048.1     .07       0  5217.6      .1       0
  5277.3     .12       0  5388.1     .05       0  5791.3     .07       0
  5856.6     .05       0  5888.4     .12       0    6171     .05       0
  6499.5    .035       0  6652.3     .05       0  6757.8     .07       0
    6805     .05       0
Bank Sta=4952.3,5010.2
XS Rating Curve= 0 ,0
Exp/Cntr=0.3,0.1

Type RM Length L Ch R = 1 ,2830    ,571,571,571
BEGIN DESCRIPTION:
EIGHTEENMILE CREEK 5.0
END DESCRIPTION:
XS GIS Cut Line= 3
      2509474.98     13498274.97        2508525.       13497025.
      2506925.04     13495725.03
#Sta/Elev= 30
    3430  179.05  3557.9  174.89  3630.6  168.31  3720.2  161.77  3728.9  161.54
  3880.1  151.17  3960.5  151.29  4859.4  153.73  4913.7  154.25  4949.8   141.5
  4963.6  141.69  4967.9  136.74  4969.3  135.84  5025.8  136.74    5028   142.9
  5056.7  141.81  5114.9  146.08    5155  148.19  5226.7  153.74  5294.8  152.73
    5362  148.31  5514.1  154.32    6073  153.18    6127     154  6272.7  155.72
  6365.5  157.73  6515.8  167.32  6836.5  184.92  6960.3  189.97  7061.5  192.97
#Mann= 19 ,-1 , 0
    3430     .05       0  3630.6     .07       0  3720.2     .05       0
  3728.9     .07       0  3960.5     .05       0  4859.4     .07       0
  4967.9     .05       0  5025.8     .07       0  5114.9     .05       0
    5155     .07       0  5226.7      .1       0  5294.8     .12       0
  5514.1     .05       0    6073     .07       0    6127     .05       0
  6272.7     .12       0  6515.8     .05       0  6836.5    .035       0
  6960.3     .07       0
Bank Sta=4967.9,5025.8
XS Rating Curve= 0 ,0
Exp/Cntr=0.3,0.1

Type RM Length L Ch R = 1 ,2259    ,520,520,520
BEGIN DESCRIPTION:
EIGHTEENMILE CREEK 4.0
END DESCRIPTION:
XS GIS Cut Line= 3
      2509674.97     13497624.97        2509025.       13496825.
      2507424.98     13495224.98
#Sta/Elev= 30
    3973  167.72  4131.7  154.71  4229.2   150.3  4325.6  150.27  4530.6  150.17
  4585.7  151.17  4681.2  151.49  4790.4  148.73  4845.8  153.03  4932.6  141.75
  4938.8   136.2  4940.2   135.3  4996.8   136.2  5000.5  139.73  5116.4  151.63
  5343.1  148.21  5456.3  153.01  5690.4  151.85  5833.9  151.28  5880.5  149.94
    5923  156.23  5977.4  152.16  6066.5  152.68  6120.9  153.88  6201.7  154.74
  6251.4   155.2  6587.7  158.62  6920.7  167.58  7125.4  174.59  7266.5  180.33
#Mann= 20 ,-1 , 0
    3973     .05       0  4131.7     .07       0  4229.2     .07       0
  4325.6     .12       0  4530.6     .07       0  4585.7     .12       0
  4681.2     .05       0  4845.8     .07       0  4938.8     .05       0
  4996.8     .07       0  5116.4     .05       0  5690.4     .07       0
  5833.9     .12       0  5977.4     .05       0  6066.5     .07       0
  6120.9     .12       0  6201.7     .07       0  6251.4     .12       0
  6920.7     .05       0  7125.4     .07       0
Bank Sta=4938.8,4996.8
XS Rating Curve= 0 ,0
Exp/Cntr=0.3,0.1

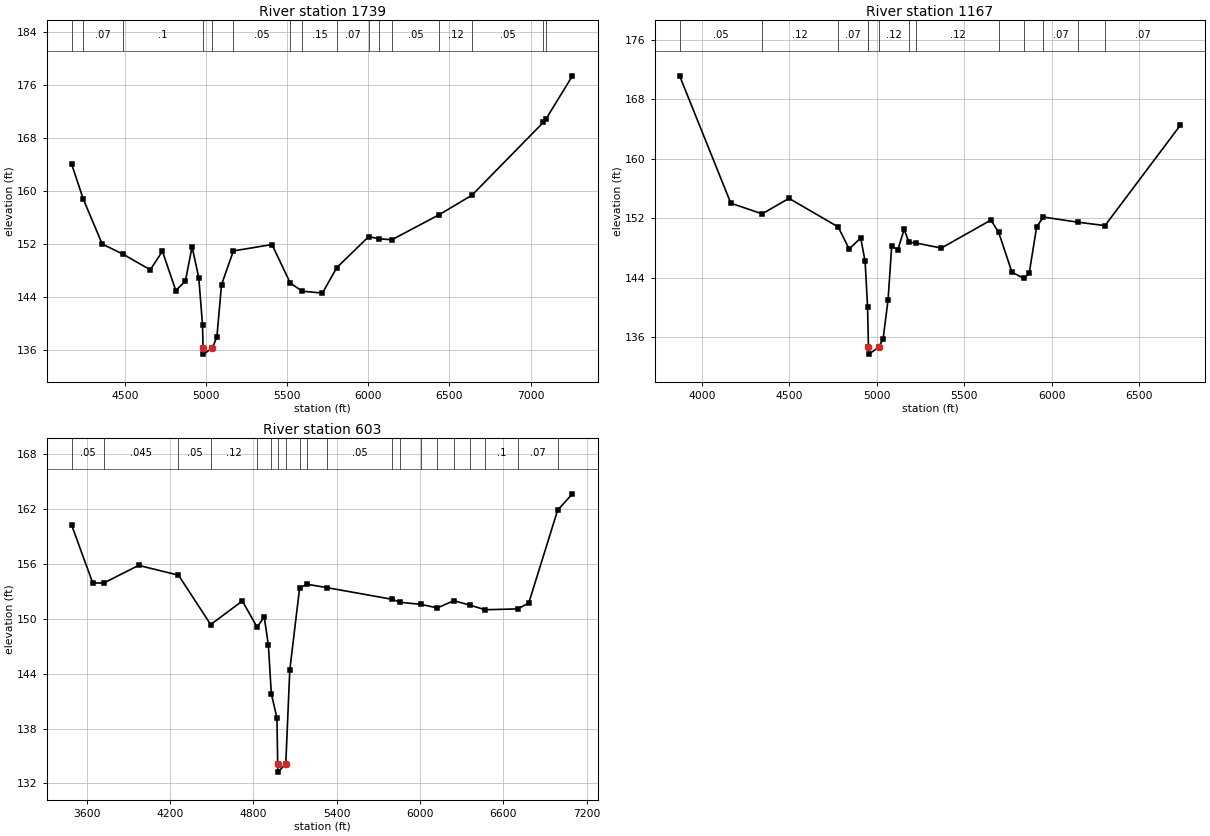
Type RM Length L Ch R = 1 ,1739    ,572,572,572
BEGIN DESCRIPTION:
EIGHTEENMILE CREEK 3.0
END DESCRIPTION:
XS GIS Cut Line= 3
      2509674.99     13497524.96        2509475.       13496725.
      2507875.02     13495125.02
#Sta/Elev= 30
  4170.9  164.01  4242.3  158.77    4359  152.02    4488  150.48  4655.3  148.14
  4730.1  150.94  4812.5  145.02  4871.8  146.44    4913   151.6  4954.3  146.94
  4977.4  139.85  4980.6  136.35    4982  135.45  5038.6  136.35  5066.2  138.09
  5094.5   145.9  5167.6  150.98  5405.6  151.94  5518.1  146.16  5591.6  144.92
  5716.7  144.64  5805.1  148.47  6002.4  153.14  6063.6  152.81  6144.5  152.66
  6436.5  156.43  6638.6  159.37  7078.9  170.34  7096.6   170.9  7258.2  177.33
#Mann= 16 ,-1 , 0
  4170.9     .05       0  4242.3     .07       0    4488      .1       0
  4980.6     .05       0  5038.6      .1       0  5167.6     .05       0
  5518.1      .1       0  5591.6     .15       0  5805.1     .07       0
  6002.4     .12       0  6063.6     .07       0  6144.5     .05       0
  6436.5     .12       0  6638.6     .05       0  7078.9     .07       0
  7096.6    .035       0
Bank Sta=4980.6,5038.6
XS Rating Curve= 0 ,0
Exp/Cntr=0.3,0.1

Type RM Length L Ch R = 1 ,1167    ,564,564,564
BEGIN DESCRIPTION:
EIGHTEENMILE CREEK 2.0
END DESCRIPTION:
XS GIS Cut Line= 3
        2509725.     13497624.98        2509975.       13496525.
      2508674.99     13495374.99
#Sta/Elev= 30
  3872.3  171.18  4165.1  154.03  4344.3  152.59  4497.8  154.68  4779.1  150.83
  4841.9  147.86    4908  149.34  4933.2  146.18  4947.1   140.1  4952.3   134.6
  4953.7   133.7  5010.4   134.6  5035.9  135.73  5064.3  140.99  5085.2  148.26
  5120.5  147.78  5156.3  150.49  5184.3  148.76  5226.3  148.66  5368.8  147.98
  5652.4  151.75  5696.6  150.12  5772.8  144.73  5841.2   143.9  5871.5  144.59
  5914.2  150.85  5952.7  152.16  6148.7  151.47  6304.9  151.01    6736  164.53
#Mann= 13 ,-1 , 0
  3872.3     .05       0  4344.3     .12       0  4779.1     .07       0
  4947.1     .12       0  4952.3     .05       0  5010.4     .12       0
  5184.3     .05       0  5226.3     .12       0  5696.6     .15       0
  5841.2    .035       0  5952.7     .07       0  6148.7      .1       0
  6304.9     .07       0
Bank Sta=4952.3,5010.4
XS Rating Curve= 0 ,0
Exp/Cntr=0.3,0.1

Type RM Length L Ch R = 1 ,603     ,0,0,0
BEGIN DESCRIPTION:
EIGHTEENMILE CREEK 1.0
END DESCRIPTION:
XS GIS Cut Line= 4
      2509925.43      13497678.8      2510524.38     13496550.34
      2510428.89     13496151.04      2508875.01     13495025.01
#Sta/Elev= 30
  3490.7  160.22  3642.2  153.92  3721.6  153.91  3972.9  155.84  4259.6  154.77
  4491.9  149.37  4719.8  151.95  4826.4  149.08  4877.4  150.22  4907.4  147.11
  4928.5  141.82  4969.1  139.15  4974.4  134.14  4975.8  133.24  5032.7  134.14
  5061.6  144.41  5132.6   153.4  5188.4  153.77  5331.2   153.4  5799.1  152.13
  5858.4   151.8  6005.3  151.58  6124.3  151.19  6243.3  151.98  6362.2  151.48
  6468.1  150.99  6702.4  151.08  6782.7  151.72  6991.2  161.89  7097.8  163.66
#Mann= 20 ,-1 , 0
  3490.7     .05       0  3721.6    .045       0  4259.6     .05       0
  4491.9     .12       0  4826.4     .05       0  4928.5     .07       0
  4974.4     .05       0  5032.7     .07       0  5132.6     .05       0
  5188.4    .035       0  5331.2     .05       0  5799.1     .05       0
  5858.4     .12       0  6005.3     .07       0  6124.3     .05       0
  6243.3      .1       0  6362.2     .15       0  6468.1      .1       0
  6702.4     .07       0  6991.2     .12       0
Bank Sta=4974.4,5032.7
XS Rating Curve= 0 ,0
Exp/Cntr=0.3,0.1

Chan Stop Cuts=-1
Use User Specified Reach Order=0
Composite Channel Slope=5