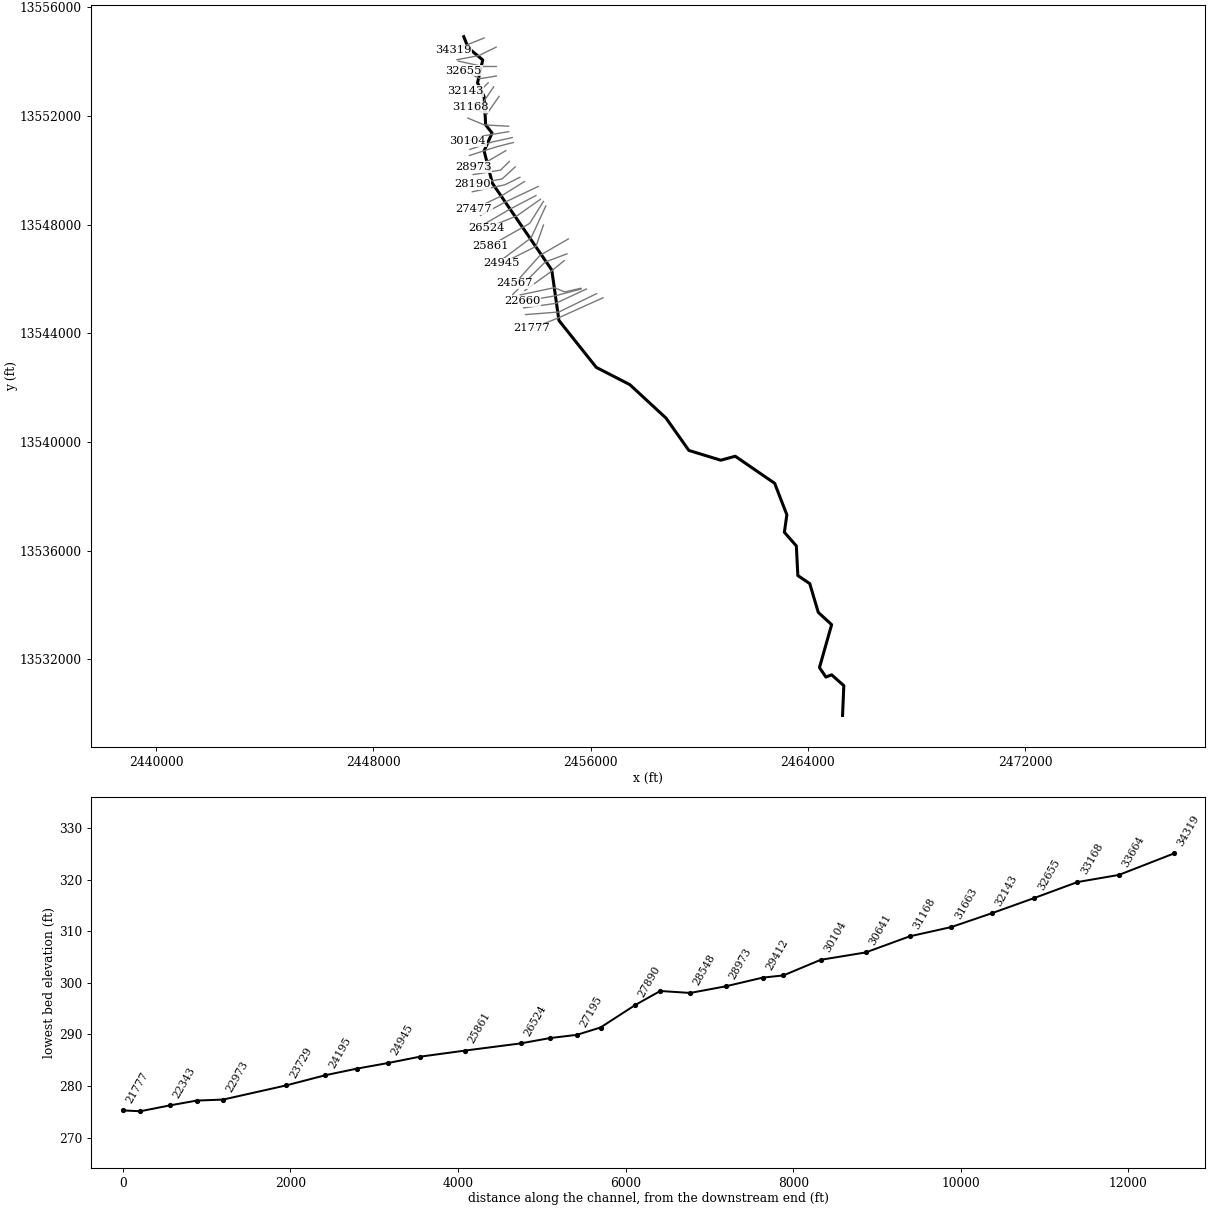
--- FIFTEENMILE CREEK.prj (project) ---

Proj Title=FIFTEENMILE CREEK Base Level Engineering
Current Plan=p01
Default Exp/Contr=0.3,0.1
English Units
Geom File=g01
Flow File=f01
Plan File=p01
Y Axis Title=Elevation
X Axis Title(PF)=Main Channel Distance
X Axis Title(XS)=Station
BEGIN DESCRIPTION:
FIFTEENMILE CREEK
END DESCRIPTION:
DSS Export Rating Curves= 0
DSS Export Rating Curve Sorted= 0
DSS Export Volume Flow Curves= 0
DXF OffsetX= 0
DXF OffsetY= 0
DXF ScaleX= 1
DXF ScaleY= 10

--- FIFTEENMILE CREEK.p01 (plan) ---

Plan Title=Multiple Run
Short Identifier=Multiple
Geom File=g01
Flow File=f01
Subcritical Flow
K Sum by GR= 0
Std Step Tol= 0.01
Critical Tol= 0.01
Num of Std Step Trials= 20
Max Error Tol= 0.3
Flow Tol Ratio= 0.001
Split Flow NTrial= 30
Split Flow Tol= 0.02
Split Flow Ratio= 0.02
Log Output Level= 0
Friction Slope Method= 1
Unsteady Friction Slope Method= 2
Unsteady Bridges Friction Slope Method= 1
Parabolic Critical Depth
Global Vel Dist=  1 , 1 , 1
Global Log Level= 0
CheckData=True
Encroach Param= -1, 0, 0, 0
BEGIN DESCRIPTION:
Multiple Run
END DESCRIPTION:

--- FIFTEENMILE CREEK.f01 (steady flow) ---

Flow Title=Multiple
Number of Profiles=7
Profile Names=10-year,25-year,50-year,1pct_min,100-year,1pct_plu,500-year
River Rch & RM= FIFTEENMILE CREE,Reach-1,34319
     537     861    1150     745    1487    2968    2462
River Rch & RM= FIFTEENMILE CREE,Reach-1,30641
    1105    1838    2520    1669    3329    6642    5756
River Rch & RM= FIFTEENMILE CREE,Reach-1,26524
    1264    2113    2904    1928    3847    7675    6684
River Rch & RM= FIFTEENMILE CREE,Reach-1,22973
    1426    2396    3304    2199    4387    8754    7665
River Rch & RM= FIFTEENMILE CREE,Reach-1,19827
    1606    2712    3755    2508    5003    9983    8802
River Rch & RM= FIFTEENMILE CREE,Reach-1,16068
    2356    4051    5675    3831    7645   15253   13747
River Rch & RM= FIFTEENMILE CREE,Reach-1,12997
    2402    4130    5786    3905    7791   15544   14000
River Rch & RM= FIFTEENMILE CREE,Reach-1,10483
    2858    4946    6957    4712    9402   18760   17022
River Rch & RM= FIFTEENMILE CREE,Reach-1,7508
    2939    5084    7153    4844    9665   19285   17493
River Rch & RM= FIFTEENMILE CREE,Reach-1,3638
    3138    5438    7657    5189   10353   20658   18763
Boundary for River Rch & Prof#=FIFTEENMILE CREE,Reach-1,1
Up Type=0
Dn Type=3
Dn Slope=0.003
Boundary for River Rch & Prof#=FIFTEENMILE CREE,Reach-1,2
Up Type=0
Dn Type=3
Dn Slope=0.003
Boundary for River Rch & Prof#=FIFTEENMILE CREE,Reach-1,3
Up Type=0
Dn Type=3
Dn Slope=0.003
Boundary for River Rch & Prof#=FIFTEENMILE CREE,Reach-1,4
Up Type=0
Dn Type=3
Dn Slope=0.003
Boundary for River Rch & Prof#=FIFTEENMILE CREE,Reach-1,5
Up Type=0
Dn Type=3
Dn Slope=0.003
Boundary for River Rch & Prof#=FIFTEENMILE CREE,Reach-1,6
Up Type=0
Dn Type=3
Dn Slope=0.003
Boundary for River Rch & Prof#=FIFTEENMILE CREE,Reach-1,7
Up Type=0
Dn Type=3
Dn Slope=0.003

--- FIFTEENMILE CREEK.g01 (geometry) ---

Geom Title=Existing Conditions

River Reach=FIFTEENMILE CREE,Reach-1
Reach XY= 30
      2451325.00     13554925.00      2451488.62     13554511.78
      2452024.45     13554064.36      2451832.30     13553225.08
      2452074.40     13552714.50      2452132.77     13551671.77
      2452367.47     13551374.99      2452074.54     13550714.81
      2452378.52     13549526.28      2454565.87     13546331.72
      2454829.99     13544472.45      2456204.52     13542744.80
      2457441.79     13542108.56      2458775.00     13540875.00
      2459615.20     13539685.48      2460790.27     13539325.37
      2461323.45     13539471.25      2462775.00     13538475.00
      2463223.81     13537314.52      2463132.84     13536671.77
      2463572.94     13536169.15      2463628.75     13535076.55
      2464066.98     13534781.34      2464380.73     13533722.45
      2464873.04     13533269.11      2464425.37     13531690.27
      2464661.62     13531338.52      2464873.28     13531421.66
      2465321.54     13531023.50      2465275.00     13529925.00

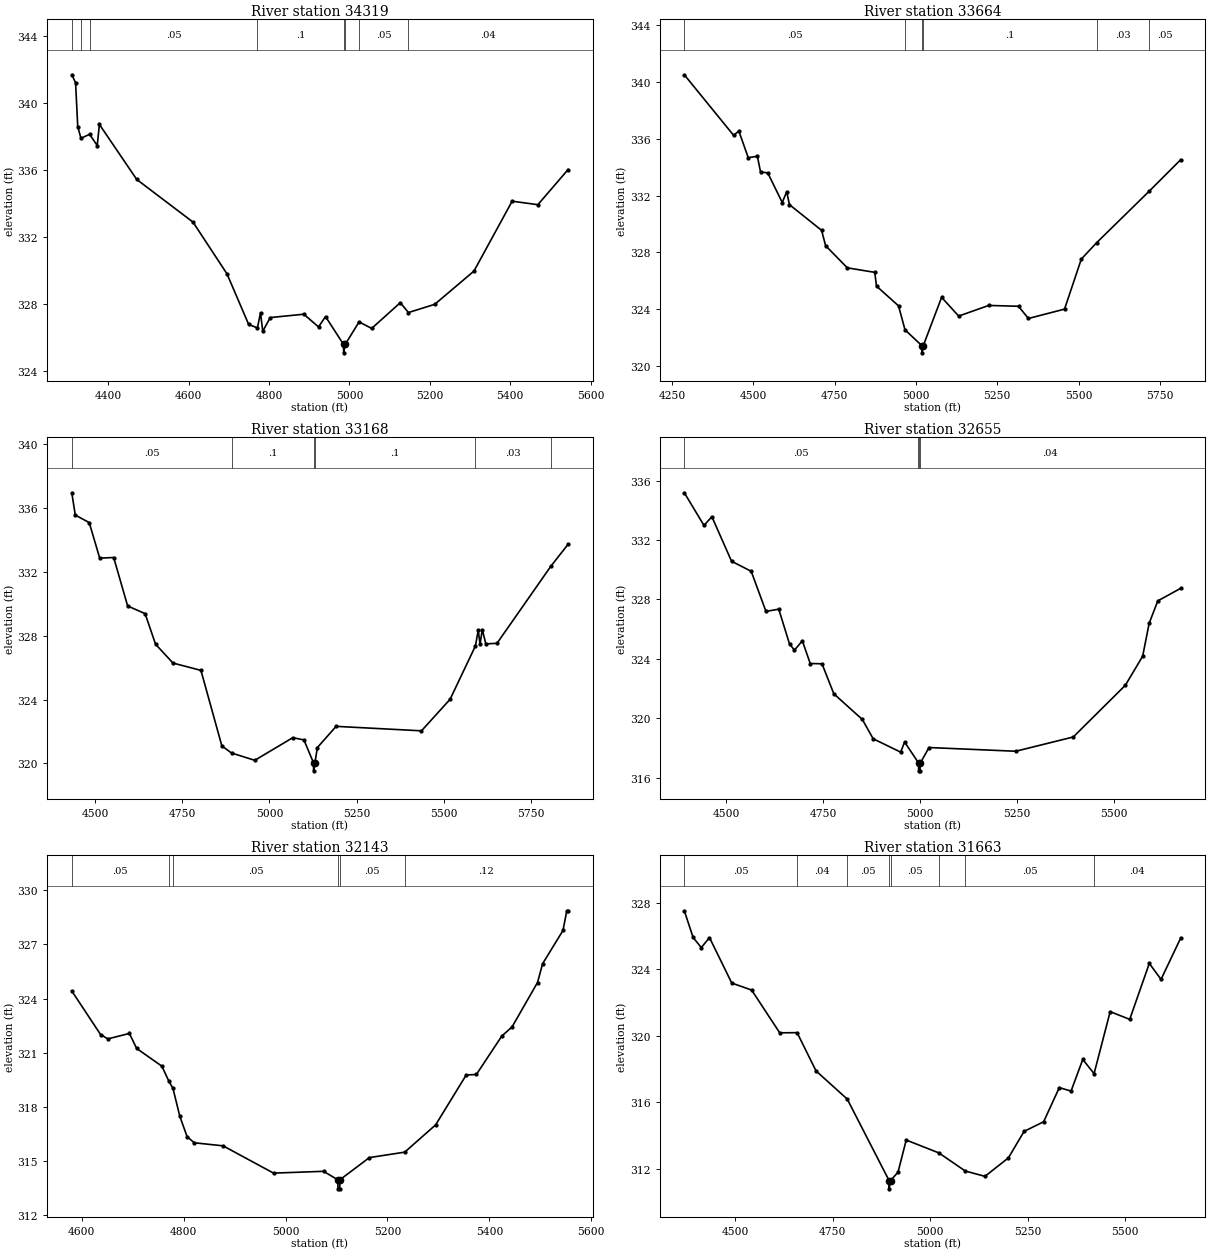
Type RM Length L Ch R = 1,34319,655,655,655
BEGIN DESCRIPTION:
FIFTEENMILE CREEK 194.0
END DESCRIPTION:
XS GIS Cut Line= 3
      2452075.01     13554875.01      2451497.05     13554643.58
      2450924.97     13554424.99
#Sta/Elev= 30
  4309.2  341.70  4318.6  341.23  4324.0  338.60  4332.0  337.90  4353.5  338.14
  4372.5  337.47  4377.9  338.73  4470.8  335.44  4610.8  332.89  4695.5  329.79
  4749.3  326.77  4771.1  326.56  4778.9  327.47  4784.3  326.36  4803.1  327.18
  4886.6  327.38  4923.2  326.62  4940.6  327.24  4985.5  325.57  4985.7  325.07
  4989.5  325.57  5024.1  326.92  5055.5  326.53  5126.7  328.07  5146.9  327.48
  5212.3  327.97  5310.0  329.96  5405.0  334.14  5469.0  333.93  5544.2  336.03
#Mann=8,-1,0
  4309.2    0.04       0  4332.0   0.013       0  4353.5    0.05       0
  4771.1     0.1       0  4985.5    0.05       0  4989.5     0.1       0
  5024.1    0.05       0  5146.9    0.04       0
Bank Sta=4985.5,4989.5
Exp/Cntr=0.3,0.1

Type RM Length L Ch R = 1,33664,496,496,496
BEGIN DESCRIPTION:
FIFTEENMILE CREEK 193.0
END DESCRIPTION:
XS GIS Cut Line= 3
      2452515.92     13554536.31      2451875.00     13554225.00
      2451074.97     13554074.99
#Sta/Elev= 30
  4287.5  340.51  4438.9  336.25  4455.3  336.54  4484.1  334.67  4512.2  334.77
  4522.0  333.66  4544.2  333.60  4588.7  331.51  4602.4  332.27  4610.9  331.36
  4709.7  329.55  4722.1  328.47  4788.8  326.91  4873.2  326.59  4878.7  325.62
  4946.4  324.23  4966.3  322.54  5018.4  321.42  5018.6  320.92  5022.4  321.42
  5078.9  324.83  5131.4  323.51  5223.9  324.26  5315.4  324.20  5345.9  323.34
  5457.0  324.00  5508.7  327.53  5555.8  328.68  5716.6  332.29  5814.0  334.52
#Mann=6,-1,0
  4287.5    0.05       0  4966.3     0.1       0  5018.4    0.05       0
  5022.4     0.1       0  5555.8    0.03       0  5716.6    0.05       0
Bank Sta=5018.4,5022.4
Exp/Cntr=0.3,0.1

Type RM Length L Ch R = 1,33168,513,513,513
BEGIN DESCRIPTION:
FIFTEENMILE CREEK 192.0
END DESCRIPTION:
XS GIS Cut Line= 3
      2452524.96     13553825.00      2452025.00     13553825.00
      2451125.01     13554025.00
#Sta/Elev= 30
  4433.6  336.97  4443.6  335.57  4483.6  335.10  4513.6  332.87  4553.6  332.91
  4593.6  329.87  4643.6  329.39  4673.6  327.47  4723.6  326.29  4803.6  325.83
  4863.6  321.09  4891.2  320.65  4957.9  320.19  5066.7  321.61  5098.7  321.47
  5126.2  320.03  5126.4  319.53  5130.2  320.03  5137.2  320.99  5190.9  322.32
  5435.5  322.04  5517.5  324.02  5590.2  327.37  5598.1  328.36  5603.3  327.47
  5609.7  328.39  5619.9  327.49  5651.9  327.53  5806.4  332.37  5855.5  333.74
#Mann=6,-1,0
  4433.6    0.05       0  4891.2     0.1       0  5126.2    0.05       0
  5130.2     0.1       0  5590.2    0.03       0  5806.4    0.04       0
Bank Sta=5126.2,5130.2
Exp/Cntr=0.3,0.1

Type RM Length L Ch R = 1,32655,512,512,512
BEGIN DESCRIPTION:
FIFTEENMILE CREEK 191.0
END DESCRIPTION:
XS GIS Cut Line= 3
      2452525.04     13553475.01      2451925.00     13553375.00
      2451325.04     13553674.98
#Sta/Elev= 30
  4392.0  335.18  4442.7  332.98  4463.0  333.57  4513.7  330.57  4564.4  329.89
  4602.4  327.19  4635.4  327.34  4663.2  324.99  4675.9  324.58  4696.2  325.21
  4716.5  323.68  4746.9  323.66  4777.3  321.64  4850.8  319.91  4878.7  318.61
  4949.6  317.71  4959.8  318.39  4995.2  317.00  4995.8  316.95  4996.0  316.45
  4999.5  316.45  4999.8  316.95  5022.7  318.02  5246.3  317.77  5394.4  318.73
  5528.6  322.21  5573.3  324.17  5590.1  326.39  5612.4  327.90  5671.1  328.74
#Mann=4,-1,0
  4392.0    0.05       0  4995.2    0.04       0  4995.8    0.04       0
  4999.8    0.04       0
Bank Sta=4995.8,4999.8
Exp/Cntr=0.3,0.1

Type RM Length L Ch R = 1,32143,480,480,480
BEGIN DESCRIPTION:
FIFTEENMILE CREEK 190.0
END DESCRIPTION:
XS GIS Cut Line= 3
      2452224.99     13553224.99      2451925.00     13552925.00
      2451375.04     13552925.00
#Sta/Elev= 30
  4580.3  324.42  4636.8  322.01  4651.0  321.77  4693.4  322.07  4707.6  321.24
  4757.1  320.26  4771.0  319.42  4778.9  319.03  4792.4  317.48  4806.6  316.36
  4820.7  316.02  4877.3  315.85  4976.3  314.34  5074.5  314.44  5102.5  313.97
  5102.8  313.47  5106.3  313.47  5106.5  313.97  5164.5  315.20  5233.8  315.50
  5294.5  317.01  5354.5  319.77  5374.5  319.80  5424.5  321.93  5444.5  322.43
  5494.5  324.89  5504.5  325.93  5544.5  327.77  5552.0  328.86  5554.5  328.86
#Mann=6,-1,0
  4580.3    0.05       0  4771.0    0.04       0  4778.9    0.05       0
  5102.5    0.05       0  5106.5    0.05       0  5233.8    0.12       0
Bank Sta=5102.5,5106.5
Exp/Cntr=0.3,0.1

Type RM Length L Ch R = 1,31663,495,495,495
BEGIN DESCRIPTION:
FIFTEENMILE CREEK 189.0
END DESCRIPTION:
XS GIS Cut Line= 3
      2452424.98     13553074.98      2452025.00     13552475.00
      2451475.05     13552425.00
#Sta/Elev= 30
  4368.9  327.51  4391.4  325.91  4412.4  325.30  4433.5  325.90  4490.6  323.17
  4541.6  322.75  4613.7  320.18  4658.3  320.19  4706.9  317.89  4786.9  316.20
  4894.2  311.31  4894.4  310.81  4898.2  311.31  4917.2  311.81  4938.2  313.74
  5021.8  312.97  5089.8  311.88  5140.2  311.56  5200.4  312.67  5240.6  314.26
  5290.8  314.84  5331.0  316.89  5361.1  316.68  5391.2  318.58  5420.2  317.73
  5461.5  321.45  5511.7  320.99  5561.9  324.35  5592.0  323.39  5642.2  325.86
#Mann=8,-1,0
  4368.9    0.05       0  4658.3    0.04       0  4786.9    0.05       0
  4894.2    0.05       0  4898.2    0.05       0  5021.8    0.04       0
  5089.8    0.05       0  5420.2    0.04       0
Bank Sta=4894.2,4898.2
Exp/Cntr=0.3,0.1

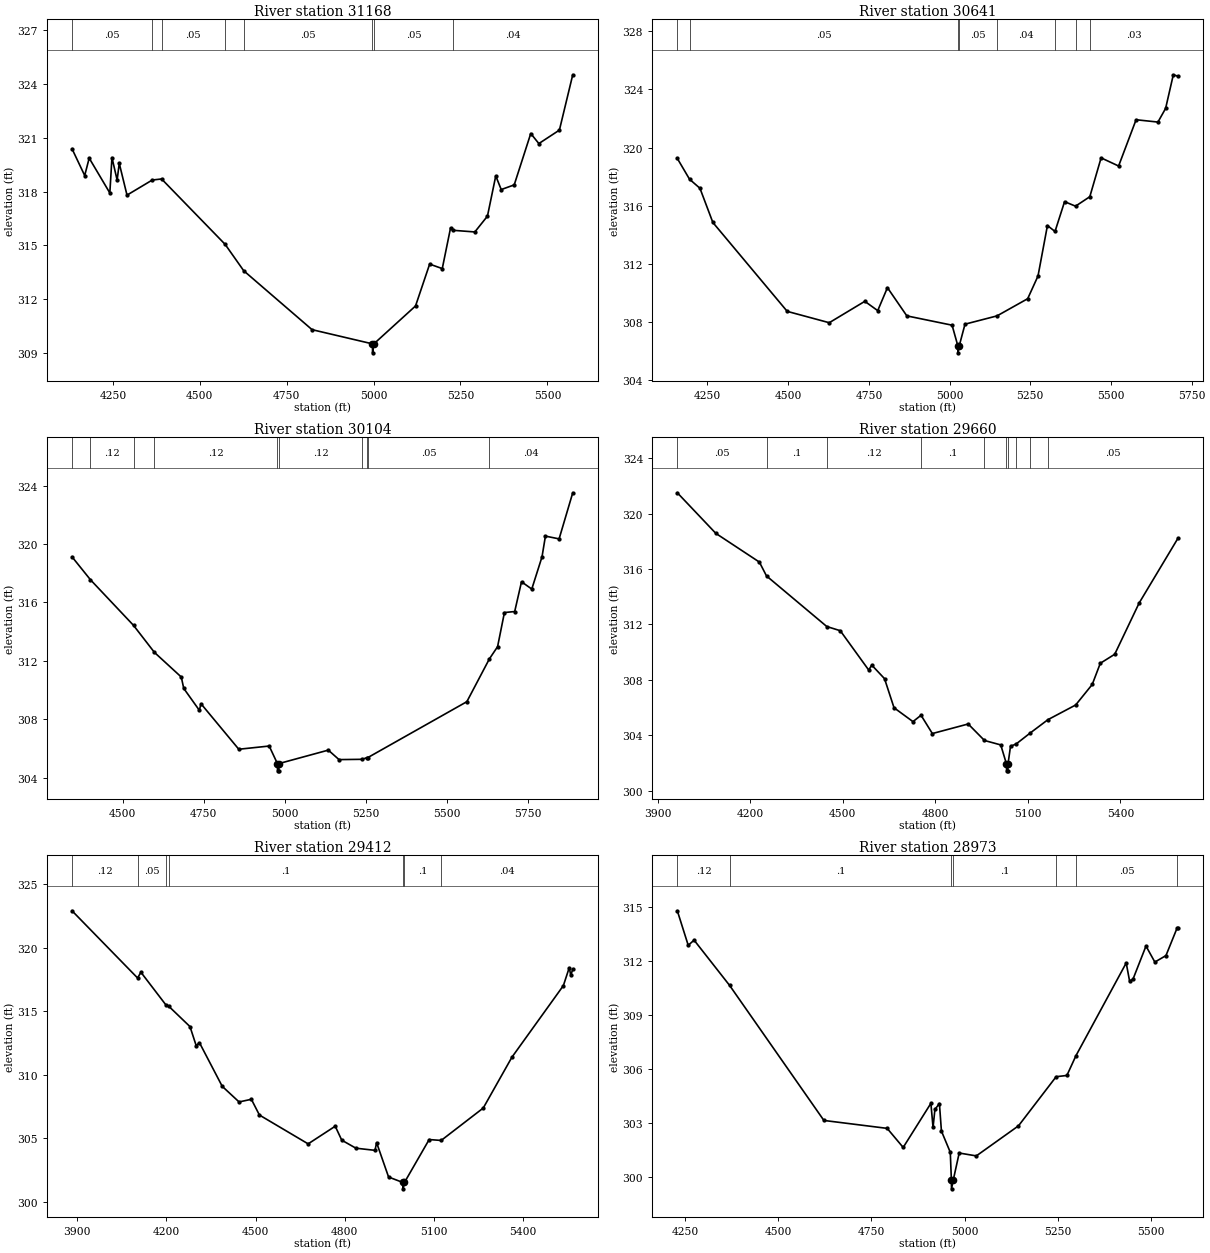
Type RM Length L Ch R = 1,31168,527,527,527
BEGIN DESCRIPTION:
FIFTEENMILE CREEK 188.0
END DESCRIPTION:
XS GIS Cut Line= 3
      2452625.02     13552725.03      2452175.00     13552075.00
      2451575.01     13552325.00
#Sta/Elev= 30
  4132.4  320.38  4168.9  318.89  4181.8  319.86  4241.2  317.92  4247.3  319.89
  4262.2  318.64  4268.3  319.57  4290.6  317.80  4363.2  318.64  4390.1  318.70
  4572.9  315.06  4626.4  313.59  4823.0  310.31  4996.8  309.52  4997.1  309.02
  5000.8  309.52  5120.7  311.63  5161.3  313.96  5197.6  313.71  5221.5  315.98
  5229.8  315.84  5291.3  315.75  5327.6  316.63  5351.5  318.87  5367.2  318.11
  5404.6  318.37  5452.2  321.23  5475.5  320.67  5534.6  321.42  5573.0  324.50
#Mann=8,-1,0
  4132.4    0.05       0  4363.2    0.12       0  4390.1    0.05       0
  4572.9    0.12       0  4626.4    0.05       0  4996.8    0.05       0
  5000.8    0.05       0  5229.8    0.04       0
Bank Sta=4996.8,5000.8
Exp/Cntr=0.3,0.1

Type RM Length L Ch R = 1,30641,537,537,537
BEGIN DESCRIPTION:
FIFTEENMILE CREEK 187.0
END DESCRIPTION:
XS GIS Cut Line= 3
      2452974.96     13551625.00      2452075.00     13551675.00
      2451474.96     13551925.02
#Sta/Elev= 30
  4156.5  319.25  4194.4  317.82  4226.6  317.20  4266.6  314.85  4497.0  308.74
  4627.2  307.96  4737.4  309.43  4777.4  308.79  4807.5  310.37  4867.6  308.43
  5007.8  307.79  5025.4  306.39  5025.8  305.89  5030.2  306.39  5047.8  307.86
  5147.1  308.43  5242.0  309.61  5274.0  311.17  5303.2  314.64  5326.7  314.23
  5356.3  316.28  5390.3  315.97  5434.5  316.62  5469.5  319.29  5523.7  318.73
  5577.9  321.91  5645.6  321.75  5669.4  322.69  5693.2  325.00  5707.9  324.90
#Mann=8,-1,0
  4156.5    0.12       0  4194.4    0.05       0  5025.4    0.05       0
  5030.2    0.05       0  5147.1    0.04       0  5326.7    0.03       0
  5390.3    0.04       0  5434.5    0.03       0
Bank Sta=5025.4,5030.2
Exp/Cntr=0.3,0.1

Type RM Length L Ch R = 1,30104,444,444,444
BEGIN DESCRIPTION:
FIFTEENMILE CREEK 186.0
END DESCRIPTION:
XS GIS Cut Line= 3
      2452974.98     13551425.00      2452075.00     13551275.00
      2451475.04     13551075.01
#Sta/Elev= 30
  4343.6  319.13  4400.4  317.56  4533.4  314.43  4597.8  312.58  4680.7  310.89
  4688.3  310.11  4736.4  308.61  4741.5  309.06  4858.1  305.94  4951.9  306.16
  4977.2  304.96  4977.6  304.46  4981.8  304.46  4982.2  304.96  5134.3  305.88
  5167.3  305.23  5237.9  305.25  5254.7  305.37  5256.3  305.37  5561.7  309.20
  5631.1  312.13  5656.5  312.97  5677.6  315.31  5709.3  315.38  5730.3  317.42
  5762.0  316.92  5793.6  319.13  5804.1  320.55  5846.3  320.36  5888.4  323.52
#Mann=10,-1,0
  4343.6    0.05       0  4400.4    0.12       0  4533.4     0.1       0
  4597.8    0.12       0  4977.2    0.05       0  4982.2    0.12       0
  5237.9    0.05       0  5254.7    0.12       0  5256.3    0.05       0
  5631.1    0.04       0
Bank Sta=4977.2,4982.2
Exp/Cntr=0.3,0.1

Type RM Length L Ch R = 1,29660,248,248,248
BEGIN DESCRIPTION:
Mapping XS 770adbd7
END DESCRIPTION:
XS GIS Cut Line= 3
      2453110.54     13551207.31      2452346.63     13551038.03
      2451550.55     13550769.79
#Sta/Elev= 30
  3964.1  321.50  4089.0  318.57  4230.0  316.50  4253.1  315.50  4448.5  311.85
  4492.1  311.55  4584.3  308.71  4594.1  309.07  4635.5  308.09  4666.3  305.99
  4727.7  304.99  4753.8  305.45  4790.5  304.13  4906.6  304.82  4959.4  303.63
  5012.1  303.31  5030.6  301.94  5031.0  301.44  5035.3  301.44  5035.7  301.94
  5043.7  303.21  5062.1  303.38  5108.2  304.18  5164.9  305.13  5254.8  306.19
  5308.5  307.67  5334.7  309.20  5381.4  309.85  5460.6  313.55  5586.6  318.23
#Mann=10,-1,0
  3964.1    0.05       0  4253.1     0.1       0  4448.5    0.12       0
  4753.8     0.1       0  4959.4    0.12       0  5030.6    0.05       0
  5035.7    0.12       0  5062.1    0.05       0  5108.2    0.12       0
  5164.9    0.05       0
Bank Sta=5030.6,5035.7
Exp/Cntr=0.3,0.1

Type RM Length L Ch R = 1,29412,439,439,439
BEGIN DESCRIPTION:
Mapping XS 4f71f3f7
END DESCRIPTION:
XS GIS Cut Line= 3
      2453149.57     13551025.01      2452537.60     13550868.76
      2451534.99     13550547.58
#Sta/Elev= 30
  3882.2  322.90  4102.7  317.61  4114.0  318.06  4199.3  315.45  4207.8  315.38
  4279.1  313.78  4299.8  312.29  4311.0  312.51  4387.5  309.08  4444.2  307.85
  4485.5  308.06  4512.6  306.82  4676.5  304.55  4767.6  305.94  4789.6  304.84
  4837.2  304.21  4901.5  304.04  4906.7  304.65  4947.1  301.94  4995.3  301.51
  4995.7  301.01  5000.4  301.51  5083.6  304.89  5124.0  304.82  5265.5  307.37
  5361.9  311.37  5535.1  317.01  5554.8  318.42  5560.0  317.82  5566.6  318.30
#Mann=7,-1,0
  3882.2    0.12       0  4102.7    0.05       0  4199.3    0.12       0
  4207.8     0.1       0  4995.3    0.05       0  5000.4     0.1       0
  5124.0    0.04       0
Bank Sta=4995.3,5000.4
Exp/Cntr=0.3,0.1

Type RM Length L Ch R = 1,28973,425,425,425
BEGIN DESCRIPTION:
FIFTEENMILE CREEK 184.0
END DESCRIPTION:
XS GIS Cut Line= 3
      2452874.96     13550724.98      2452275.00     13550375.00
      2451674.98     13550124.99
#Sta/Elev= 30
  4228.7  314.78  4258.0  312.86  4273.7  313.15  4369.2  310.63  4622.3  303.13
  4792.2  302.69  4835.2  301.63  4909.6  304.08  4915.4  302.74  4920.4  303.74
  4932.5  304.07  4937.9  302.54  4961.7  301.36  4964.6  299.83  4965.0  299.33
  4969.8  299.83  4985.6  301.32  5031.6  301.16  5144.8  302.83  5245.9  305.56
  5274.8  305.63  5299.2  306.73  5434.1  311.88  5443.3  310.86  5452.5  310.99
  5487.2  312.82  5511.0  311.93  5540.8  312.29  5570.7  313.82  5573.3  313.82
#Mann=7,-1,0
  4228.7    0.12       0  4369.2     0.1       0  4964.6    0.05       0
  4969.8     0.1       0  5245.9    0.12       0  5299.2    0.05       0
  5570.7    0.04       0
Bank Sta=4964.6,4969.8
Exp/Cntr=0.3,0.1

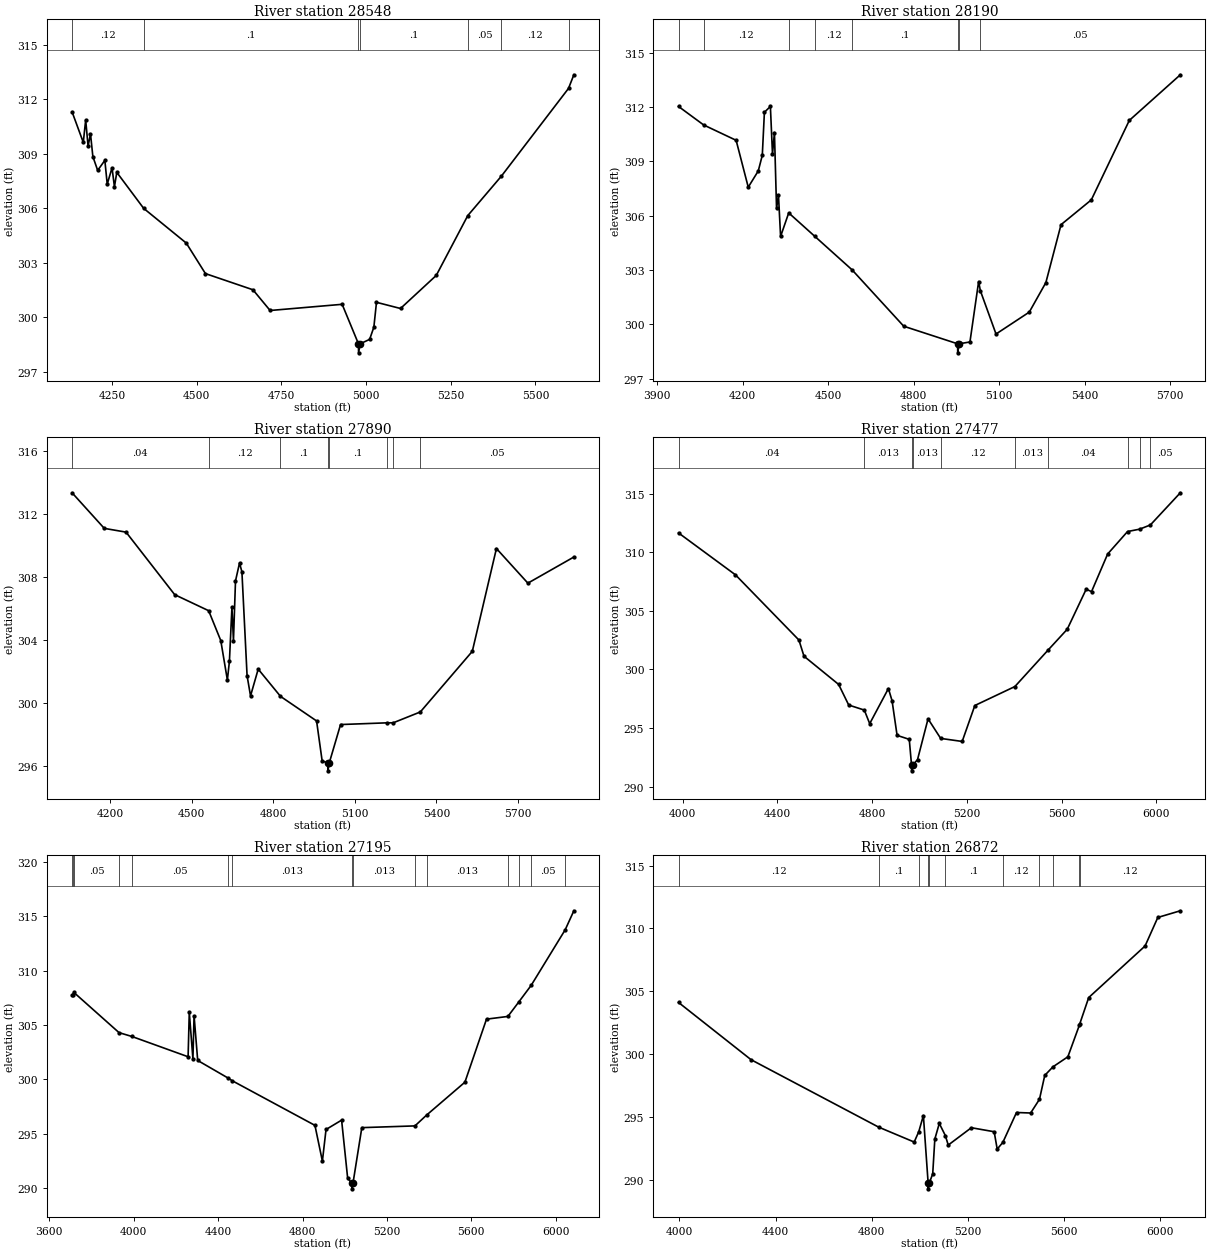
Type RM Length L Ch R = 1,28548,358,358,358
BEGIN DESCRIPTION:
Mapping XS d1500ca6
END DESCRIPTION:
XS GIS Cut Line= 3
      2453006.33     13550330.55      2452680.83     13550009.39
      2451669.76     13549844.49
#Sta/Elev= 30
  4131.8  311.30  4164.9  309.62  4172.0  310.85  4179.1  309.41  4186.2  310.09
  4193.2  308.84  4207.4  308.08  4228.6  308.63  4235.6  307.32  4249.8  308.22
  4256.9  307.18  4263.9  307.97  4343.2  305.99  4469.0  304.08  4525.6  302.40
  4665.9  301.51  4716.6  300.37  4929.3  300.71  4977.4  298.54  4977.8  298.04
  4982.6  298.54  5010.4  298.78  5022.9  299.45  5030.7  300.82  5101.6  300.48
  5207.2  302.30  5300.2  305.59  5399.4  307.76  5597.7  312.59  5613.5  313.34
#Mann=7,-1,0
  4131.8    0.12       0  4343.2     0.1       0  4977.4    0.05       0
  4982.6     0.1       0  5300.2    0.05       0  5399.4    0.12       0
  5597.7    0.04       0
Bank Sta=4977.4,4982.6
Exp/Cntr=0.3,0.1

Type RM Length L Ch R = 1,28190,300,300,300
BEGIN DESCRIPTION:
Mapping XS 39aabec3
END DESCRIPTION:
XS GIS Cut Line= 3
      2453218.99     13550126.55      2452737.25     13549683.87
      2451648.92     13549484.41
#Sta/Elev= 30
  3975.5  312.03  4063.5  311.01  4177.6  310.16  4220.1  307.57  4255.3  308.47
  4269.4  309.33  4276.8  311.71  4297.8  312.03  4305.2  309.39  4312.0  310.59
  4319.4  306.40  4326.2  307.12  4333.6  304.85  4362.1  306.15  4454.0  304.85
  4584.1  303.01  4765.7  299.89  4954.7  298.92  4955.1  298.42  4960.0  298.92
  4998.0  299.02  5028.5  302.36  5034.6  301.85  5089.5  299.46  5206.2  300.67
  5264.4  302.30  5317.6  305.50  5423.9  306.87  5557.2  311.26  5736.2  313.78
#Mann=8,-1,0
  3975.5    0.05       0  4063.5    0.12       0  4362.1    0.04       0
  4454.0    0.12       0  4584.1     0.1       0  4954.7    0.05       0
  4960.0     0.1       0  5034.6    0.05       0
Bank Sta=4954.7,4960
Exp/Cntr=0.3,0.1

Type RM Length L Ch R = 1,27890,413,413,413
BEGIN DESCRIPTION:
Mapping XS 34b25621
END DESCRIPTION:
XS GIS Cut Line= 3
      2453392.60     13549744.61      2452837.08     13549466.85
      2451639.62     13549210.88
#Sta/Elev= 30
  4059.9  313.35  4178.3  311.09  4258.5  310.85  4437.3  306.88  4562.3  305.86
  4606.9  303.96  4631.1  301.46  4638.6  302.64  4647.9  306.07  4653.5  303.96
  4661.0  307.75  4675.8  308.89  4684.6  308.33  4703.6  301.73  4716.3  300.45
  4744.5  302.15  4826.5  300.42  4959.2  298.86  4979.7  296.32  5000.3  296.19
  5000.7  295.69  5005.8  296.19  5047.4  298.63  5219.5  298.74  5240.9  298.74
  5340.8  299.43  5532.0  303.28  5620.7  309.81  5736.4  307.61  5905.5  309.27
#Mann=8,-1,0
  4059.9    0.04       0  4562.3    0.12       0  4826.5     0.1       0
  5000.3    0.05       0  5005.8     0.1       0  5219.5   0.013       0
  5240.9     0.1       0  5340.8    0.05       0
Bank Sta=5000.3,5005.8
Exp/Cntr=0.3,0.1

Type RM Length L Ch R = 1,27477,282,282,282
BEGIN DESCRIPTION:
Mapping XS c0f390a4
END DESCRIPTION:
XS GIS Cut Line= 3
      2453561.93     13549588.40      2452711.21     13549058.87
      2451704.29     13548577.11
#Sta/Elev= 30
  3982.8  311.66  4223.2  308.08  4491.1  302.51  4512.4  301.13  4658.7  298.72
  4701.2  296.96  4767.1  296.53  4789.8  295.37  4868.8  298.37  4884.2  297.33
  4905.4  294.37  4956.8  294.03  4966.4  291.84  4966.8  291.34  4972.0  291.84
  4991.7  292.30  5036.1  295.78  5089.4  294.11  5180.2  293.85  5233.6  296.92
  5402.7  298.54  5544.4  301.69  5623.6  303.43  5703.6  306.85  5726.3  306.65
  5794.3  309.86  5878.3  311.78  5928.9  311.98  5974.6  312.34  6101.1  315.09
#Mann=10,-1,0
  3982.8    0.04       0  4767.1   0.013       0  4966.4    0.03       0
  4972.0   0.013       0  5089.4    0.12       0  5402.7   0.013       0
  5544.4    0.04       0  5878.3    0.05       0  5928.9   0.013       0
  5974.6    0.05       0
Bank Sta=4966.4,4972
Exp/Cntr=0.3,0.1

Type RM Length L Ch R = 1,27195,323,323,323
BEGIN DESCRIPTION:
Mapping XS ba77b503
END DESCRIPTION:
XS GIS Cut Line= 3
      2454065.36     13549406.08      2452845.76     13548828.83
      2451940.78     13548339.54
#Sta/Elev= 30
  3707.7  307.71  3711.6  307.76  3715.6  308.00  3930.3  304.29  3990.7  303.94
  4257.6  302.07  4263.2  306.16  4280.4  301.89  4285.9  305.84  4303.1  301.73
  4447.3  300.11  4467.1  299.86  4858.7  295.76  4894.0  292.47  4911.3  295.38
  4985.1  296.24  5013.6  290.93  5033.2  290.42  5033.7  289.92  5038.9  290.42
  5080.9  295.55  5332.7  295.71  5388.2  296.71  5569.4  299.73  5671.8  305.53
  5773.1  305.78  5825.9  307.14  5883.2  308.63  6044.7  313.75  6085.8  315.50
#Mann=15,-1,0
  3707.7    0.05       0  3711.6   0.013       0  3715.6    0.05       0
  3930.3   0.013       0  3990.7    0.05       0  4447.3   0.075       0
  4467.1   0.013       0  5033.2    0.03       0  5038.9   0.013       0
  5332.7    0.05       0  5388.2   0.013       0  5773.1    0.05       0
  5825.9   0.013       0  5883.2    0.05       0  6044.7   0.013       0
Bank Sta=5033.2,5038.9
Exp/Cntr=0.3,0.1

Type RM Length L Ch R = 1,26872,348,348,348
BEGIN DESCRIPTION:
Mapping XS 62483e50
END DESCRIPTION:
XS GIS Cut Line= 3
      2453982.92     13549071.89      2453036.73     13548577.10
      2452155.63     13548064.93
#Sta/Elev= 30
  3996.1  304.11  4297.6  299.56  4828.0  294.20  4976.2  293.01  4995.3  293.84
  5014.4  295.12  5034.0  289.79  5034.4  289.29  5039.7  289.79  5053.2  290.48
  5062.0  293.25  5080.6  294.49  5105.6  293.53  5117.8  292.77  5213.9  294.15
  5308.8  293.83  5321.4  292.45  5344.8  292.98  5401.7  295.36  5460.5  295.32
  5497.2  296.41  5519.2  298.31  5553.2  298.99  5615.3  299.79  5662.9  302.29
  5664.8  302.41  5702.0  304.50  5936.4  308.60  5989.4  310.87  6083.0  311.40
#Mann=11,-1,0
  3996.1    0.12       0  4828.0     0.1       0  4995.3    0.12       0
  5034.0    0.05       0  5039.7    0.12       0  5105.6     0.1       0
  5344.8    0.12       0  5497.2     0.1       0  5553.2    0.12       0
  5662.9     0.1       0  5664.8    0.12       0
Bank Sta=5034,5039.7
Exp/Cntr=0.3,0.1

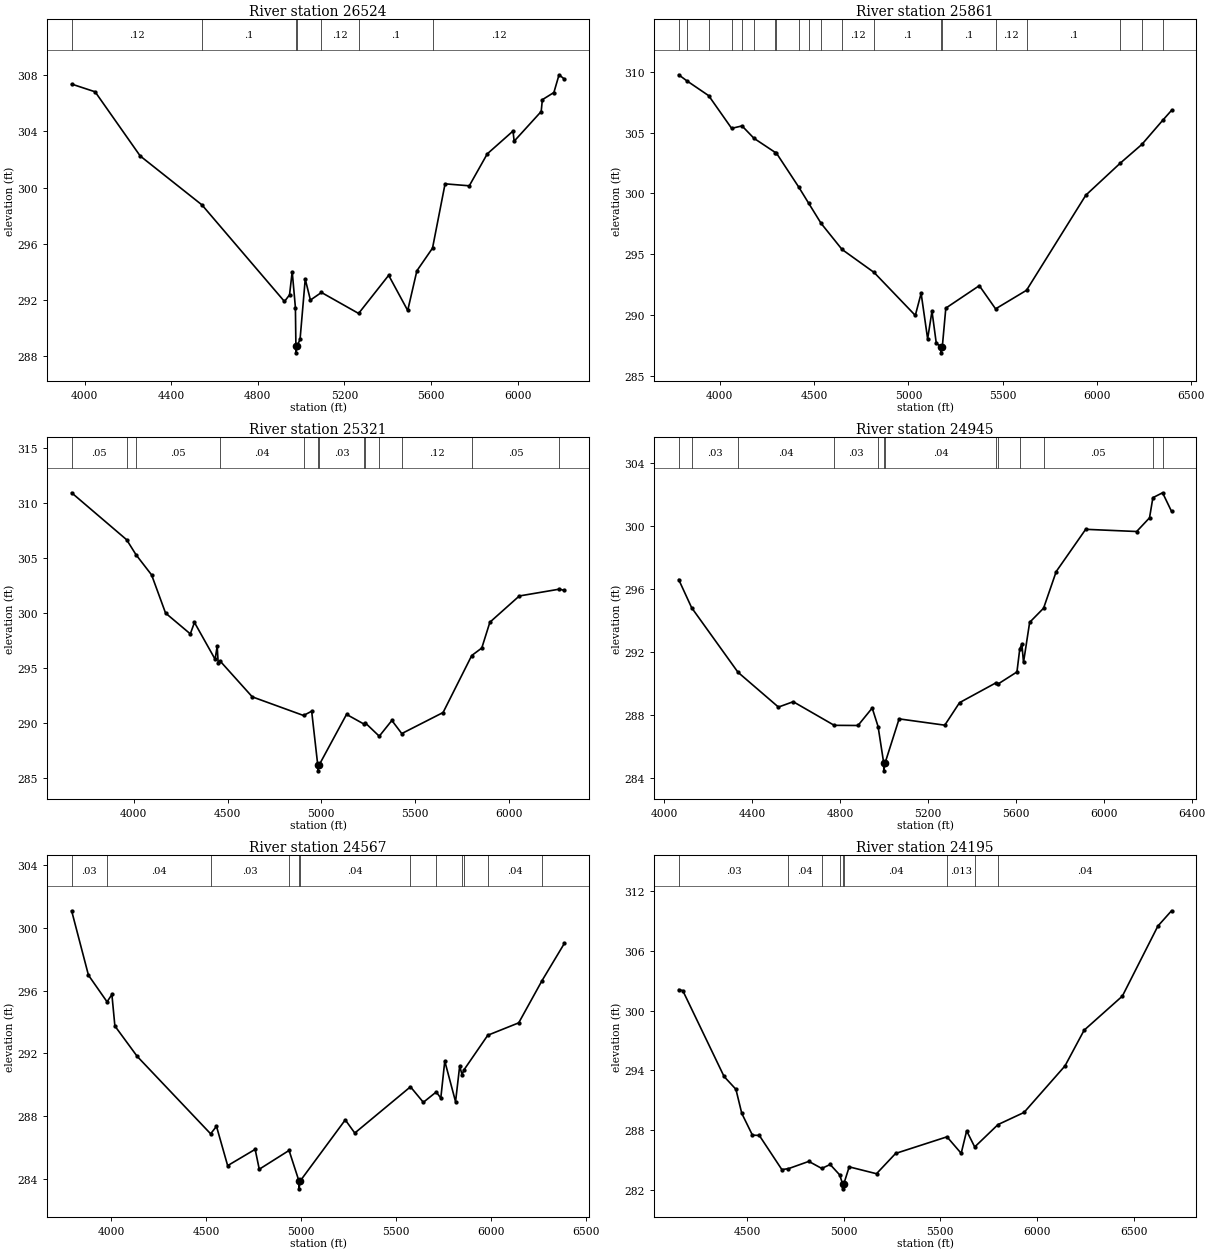
Type RM Length L Ch R = 1,26524,663,663,663
BEGIN DESCRIPTION:
Mapping XS a71a5ab5
END DESCRIPTION:
XS GIS Cut Line= 3
      2454147.88     13548933.03      2453297.15     13548334.04
      2452155.65     13547860.95
#Sta/Elev= 30
  3940.2  307.36  4048.7  306.81  4256.9  302.25  4542.3  298.77  4923.2  291.91
  4946.6  292.38  4958.9  294.03  4973.7  291.48  4976.0  288.76  4976.5  288.26
  4981.9  288.76  4995.2  289.22  5019.1  293.50  5043.0  292.01  5094.0  292.55
  5265.6  291.06  5404.4  293.77  5492.3  291.27  5534.7  294.09  5606.9  295.70
  5664.9  300.27  5776.7  300.13  5859.8  302.40  5978.6  304.02  5984.0  303.30
  6108.8  305.41  6114.2  306.25  6167.4  306.76  6191.3  308.02  6216.3  307.71
#Mann=7,-1,0
  3940.2    0.12       0  4542.3     0.1       0  4976.0    0.05       0
  4981.9     0.1       0  5094.0    0.12       0  5265.6     0.1       0
  5606.9    0.12       0
Bank Sta=4976,4981.9
Exp/Cntr=0.3,0.1

Type RM Length L Ch R = 1,25861,540,540,540
BEGIN DESCRIPTION:
Mapping XS 54dd7e47
END DESCRIPTION:
XS GIS Cut Line= 3
      2454260.71     13548854.91      2453752.25     13548046.14
      2452309.60     13547230.26
#Sta/Elev= 30
  3781.8  309.76  3825.3  309.26  3940.9  308.04  4062.5  305.35  4117.7  305.55
  4181.0  304.53  4294.4  303.36  4299.6  303.32  4418.1  300.52  4471.1  299.18
  4536.7  297.53  4647.9  295.38  4817.5  293.49  5036.2  289.95  5067.1  291.77
  5101.6  288.02  5124.6  290.30  5147.5  287.65  5173.1  287.37  5173.6  286.87
  5179.4  287.37  5197.9  290.55  5375.5  292.40  5461.8  290.49  5625.8  292.02
  5940.2  299.85  6122.4  302.48  6237.5  304.03  6348.7  306.03  6394.5  306.83
#Mann=20,-1,0
  3781.8    0.12       0  3825.3    0.05       0  3940.9    0.12       0
  4062.5   0.013       0  4117.7    0.12       0  4181.0   0.013       0
  4294.4    0.12       0  4299.6    0.05       0  4418.1   0.013       0
  4471.1    0.12       0  4536.7    0.05       0  4647.9    0.12       0
  4817.5     0.1       0  5173.1    0.05       0  5179.4     0.1       0
  5461.8    0.12       0  5625.8     0.1       0  6122.4    0.05       0
  6237.5    0.12       0  6348.7    0.05       0
Bank Sta=5173.1,5179.4
Exp/Cntr=0.3,0.1

Type RM Length L Ch R = 1,25321,376,376,376
BEGIN DESCRIPTION:
Mapping XS 51e5d83f
END DESCRIPTION:
XS GIS Cut Line= 3
      2454347.48     13548689.91      2453804.96     13547513.73
      2452736.16     13546716.58
#Sta/Elev= 30
  3668.6  310.90  3962.1  306.64  4012.5  305.27  4095.2  303.45  4169.6  299.99
  4301.7  298.10  4323.7  299.14  4433.9  295.80  4444.9  296.98  4450.4  295.43
  4461.0  295.63  4632.1  292.39  4905.5  290.70  4948.9  291.09  4981.5  286.18
  4982.0  285.68  4987.8  286.18  5134.8  290.80  5229.0  289.91  5233.7  290.05
  5309.4  288.82  5376.6  290.25  5429.5  289.06  5649.8  290.97  5802.7  296.14
  5856.2  296.82  5899.4  299.16  6056.3  301.54  6270.4  302.16  6297.2  302.04
#Mann=13,-1,0
  3668.6    0.05       0  3962.1    0.04       0  4012.5    0.05       0
  4461.0    0.04       0  4905.5    0.03       0  4981.5    0.03       0
  4987.8    0.03       0  5229.0   0.013       0  5233.7    0.03       0
  5309.4   0.013       0  5429.5    0.12       0  5802.7    0.05       0
  6270.4    0.12       0
Bank Sta=4981.5,4987.8
Exp/Cntr=0.3,0.1

Type RM Length L Ch R = 1,24945,378,378,378
BEGIN DESCRIPTION:
Mapping XS 0061cb71
END DESCRIPTION:
XS GIS Cut Line= 3
      2454260.30     13547986.72      2453984.65     13547197.61
      2452725.36     13546570.67
#Sta/Elev= 30
  4065.5  296.62  4124.5  294.83  4335.4  290.73  4519.4  288.52  4586.8  288.86
  4773.3  287.36  4881.4  287.35  4946.1  288.46  4972.9  287.28  4998.4  284.97
  4998.9  284.47  5004.7  284.97  5068.5  287.77  5276.3  287.37  5343.5  288.80
  5509.2  290.06  5519.3  289.99  5604.7  290.75  5617.5  292.21  5627.1  292.52
  5634.6  291.36  5662.5  293.90  5725.9  294.80  5783.5  297.13  5917.5  299.81
  6149.5  299.67  6208.0  300.54  6223.3  301.82  6267.4  302.13  6308.1  300.95
#Mann=13,-1,0
  4065.5    0.05       0  4124.5    0.03       0  4335.4    0.04       0
  4773.3    0.03       0  4972.9    0.04       0  4998.4    0.04       0
  5004.7    0.04       0  5509.2   0.013       0  5519.3    0.04       0
  5617.5   0.013       0  5725.9    0.05       0  6223.3   0.013       0
  6267.4    0.05       0
Bank Sta=4998.4,5004.7
Exp/Cntr=0.3,0.1

Type RM Length L Ch R = 1,24567,372,372,372
BEGIN DESCRIPTION:
Mapping XS 7237c4ed
END DESCRIPTION:
XS GIS Cut Line= 3
      2455176.47     13547474.65      2454134.82     13546871.37
      2453206.02     13545834.06
#Sta/Elev= 30
  3791.6  301.10  3880.3  296.99  3978.3  295.29  4003.7  295.76  4019.5  293.75
  4137.1  291.81  4523.9  286.87  4554.7  287.35  4613.5  284.84  4758.4  285.88
  4780.0  284.61  4937.0  285.81  4989.1  283.86  4989.6  283.36  4995.5  283.86
  5233.1  287.76  5283.2  286.92  5576.5  289.87  5644.3  288.88  5712.3  289.54
  5736.3  289.15  5757.2  291.51  5814.0  288.92  5835.7  291.19  5848.1  290.65
  5858.9  290.96  5983.8  293.16  6146.7  293.95  6269.8  296.65  6387.7  299.03
#Mann=12,-1,0
  3791.6    0.03       0  3978.3    0.04       0  4523.9    0.03       0
  4937.0    0.04       0  4989.1    0.04       0  4995.5    0.04       0
  5576.5    0.05       0  5712.3   0.013       0  5848.1    0.04       0
  5858.9    0.05       0  5983.8    0.04       0  6269.8    0.05       0
Bank Sta=4989.1,4995.5
Exp/Cntr=0.3,0.1

Type RM Length L Ch R = 1,24195,466,466,466
BEGIN DESCRIPTION:
FIFTEENMILE CREEK 174.0
END DESCRIPTION:
XS GIS Cut Line= 3
      2455124.97     13546924.99      2454325.00     13546625.00
      2453125.02     13545425.02
#Sta/Elev= 30
  4145.3  302.13  4166.6  302.03  4380.2  293.40  4441.6  292.11  4471.9  289.69
  4527.1  287.50  4562.7  287.47  4679.3  284.04  4713.6  284.13  4819.0  284.86
  4886.1  284.15  4929.4  284.55  4978.9  283.50  4993.8  282.60  4994.3  282.10
  5000.2  282.60  5028.0  284.31  5169.4  283.62  5268.4  285.66  5534.3  287.33
  5607.8  285.67  5636.1  287.93  5677.8  286.31  5798.3  288.56  5933.1  289.78
  6145.2  294.46  6244.2  298.05  6442.2  301.48  6626.0  308.52  6696.7  310.06
#Mann=9,-1,0
  4145.3    0.03       0  4713.6    0.04       0  4886.1    0.05       0
  4978.9    0.04       0  4993.8    0.04       0  5000.2    0.04       0
  5534.3   0.013       0  5677.8    0.05       0  5798.3    0.04       0
Bank Sta=4993.8,5000.2
Exp/Cntr=0.3,0.1

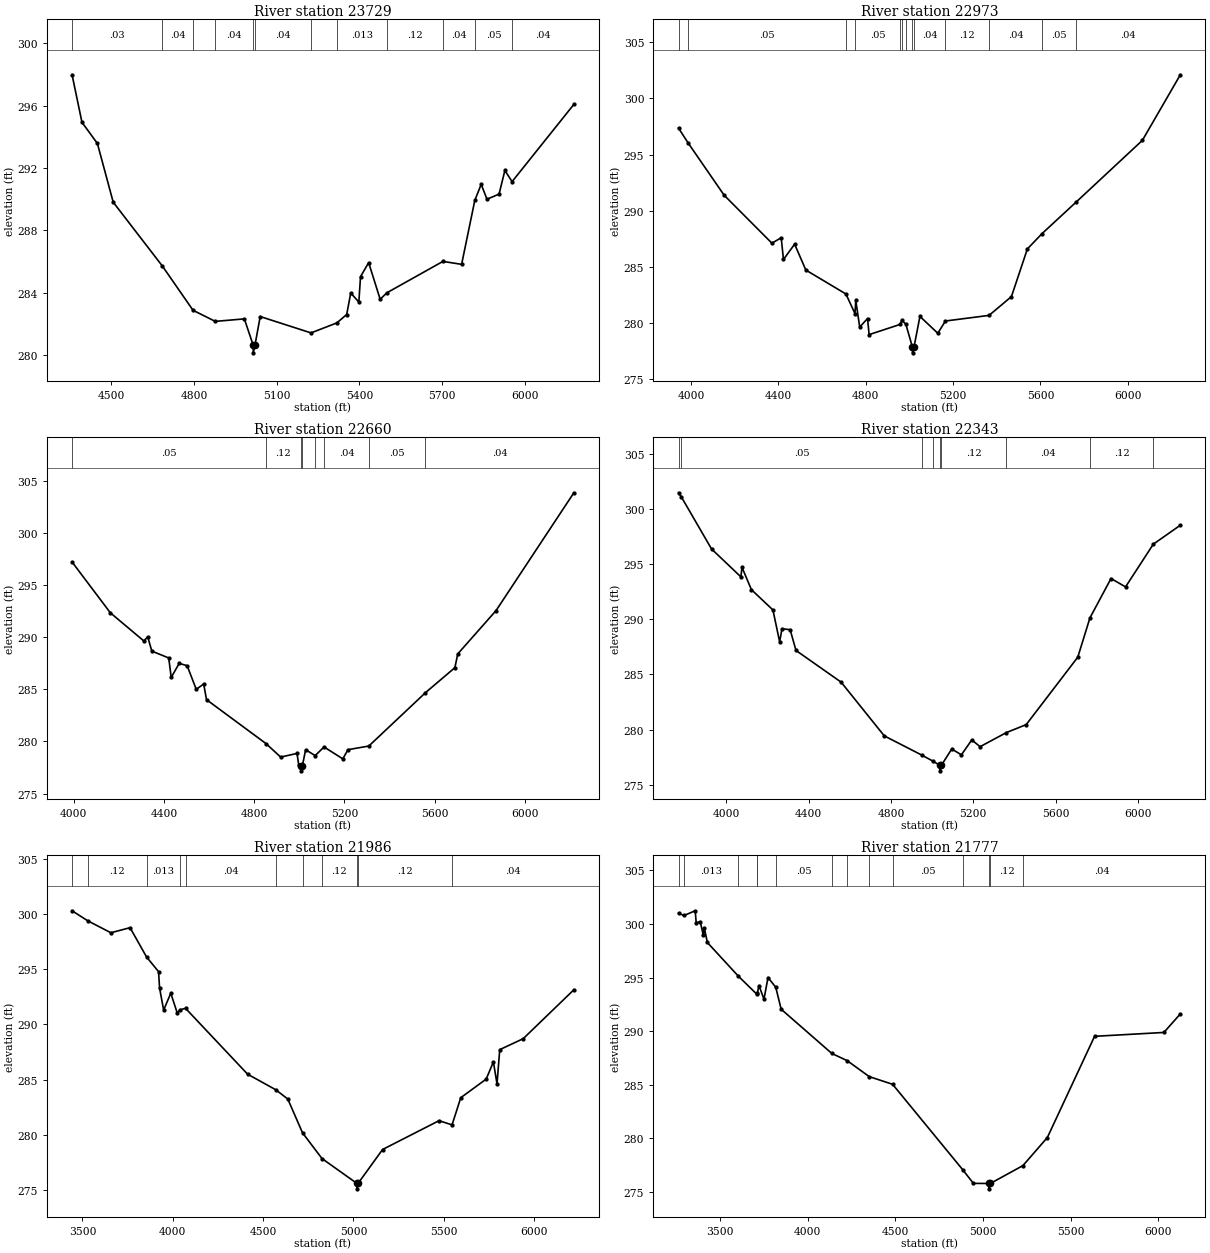
Type RM Length L Ch R = 1,23729,756,756,756
BEGIN DESCRIPTION:
FIFTEENMILE CREEK 173.0
END DESCRIPTION:
XS GIS Cut Line= 3
      2455024.98     13546674.98      2454475.00     13546225.00
      2453574.99     13545574.99
#Sta/Elev= 30
  4357.5  297.98  4393.4  294.93  4449.4  293.57  4506.8  289.80  4684.8  285.71
  4796.5  282.86  4877.1  282.15  4982.7  282.31  5014.5  280.63  5015.0  280.13
  5021.3  280.63  5040.1  282.46  5224.5  281.41  5318.2  282.05  5354.0  282.59
  5368.7  283.97  5398.1  283.39  5404.2  285.02  5433.7  285.92  5475.4  283.57
  5500.3  283.99  5703.3  286.00  5771.0  285.81  5818.8  289.91  5842.1  290.95
  5863.0  289.99  5906.9  290.32  5928.0  291.84  5954.1  291.12  6178.3  296.08
#Mann=12,-1,0
  4357.5    0.03       0  4684.8    0.04       0  4796.5    0.03       0
  4877.1    0.04       0  5014.5    0.04       0  5021.3    0.04       0
  5224.5    0.05       0  5318.2   0.013       0  5500.3    0.12       0
  5703.3    0.04       0  5818.8    0.05       0  5954.1    0.04       0
Bank Sta=5014.5,5021.3
Exp/Cntr=0.3,0.1

Type RM Length L Ch R = 1,22973,313,313,313
BEGIN DESCRIPTION:
FIFTEENMILE CREEK 172.0
END DESCRIPTION:
XS GIS Cut Line= 5
      2455633.04     13545657.27      2455049.37     13545522.16
      2454654.77     13545679.16      2454557.55     13545657.28
      2453408.16     13545414.45
#Sta/Elev= 30
  3942.4  297.35  3986.6  296.02  4151.4  291.38  4370.0  287.12  4412.6  287.60
  4423.0  285.67  4474.1  287.03  4525.5  284.73  4709.1  282.60  4750.5  280.86
  4754.1  282.03  4772.2  279.66  4808.0  280.42  4815.3  278.99  4957.8  279.90
  4964.7  280.26  4983.5  279.92  5013.7  277.87  5014.2  277.37  5020.7  277.87
  5048.0  280.61  5129.8  279.11  5164.8  280.20  5364.6  280.70  5467.1  282.37
  5540.1  286.61  5607.3  287.97  5764.3  290.79  6066.8  296.26  6240.6  302.09
#Mann=13,-1,0
  3942.4    0.12       0  3986.6    0.05       0  4709.1   0.013       0
  4750.5    0.05       0  4957.8   0.013       0  4964.7    0.12       0
  4983.5    0.04       0  5013.7    0.04       0  5020.7    0.04       0
  5164.8    0.12       0  5364.6    0.04       0  5607.3    0.05       0
  5764.3    0.04       0
Bank Sta=5013.7,5020.7
Exp/Cntr=0.3,0.1

Type RM Length L Ch R = 1,22660,317,317,317
BEGIN DESCRIPTION:
FIFTEENMILE CREEK 171.0
END DESCRIPTION:
XS GIS Cut Line= 3
      2455649.28     13545630.26      2454675.00     13545375.00
      2453475.02     13545175.00
#Sta/Elev= 30
  3992.8  297.22  4162.6  292.34  4311.0  289.64  4328.0  290.04  4346.2  288.67
  4421.1  288.01  4432.2  286.14  4467.4  287.49  4502.7  287.27  4543.1  285.00
  4576.1  285.51  4588.6  284.01  4851.9  279.80  4917.3  278.50  4989.6  278.85
  4997.4  277.72  5006.6  277.68  5007.1  277.18  5013.6  277.68  5027.8  279.21
  5070.1  278.64  5109.4  279.47  5192.6  278.33  5215.4  279.21  5307.9  279.56
  5558.9  284.68  5689.3  287.08  5702.0  288.40  5871.8  292.56  6216.5  303.86
#Mann=8,-1,0
  3992.8    0.05       0  4851.9    0.12       0  5006.6    0.05       0
  5013.6    0.12       0  5070.1    0.05       0  5109.4    0.04       0
  5307.9    0.05       0  5558.9    0.04       0
Bank Sta=5006.6,5013.6
Exp/Cntr=0.3,0.1

Type RM Length L Ch R = 1,22343,357,357,357
BEGIN DESCRIPTION:
Mapping XS c735de31
END DESCRIPTION:
XS GIS Cut Line= 3
      2455840.54     13545630.04      2454707.74     13545100.53
      2453531.49     13544935.60
#Sta/Elev= 30
  3767.9  301.46  3781.4  301.09  3928.2  296.37  4070.8  293.84  4076.3  294.70
  4122.0  292.68  4226.6  290.84  4259.1  287.96  4270.8  289.14  4310.3  289.05
  4338.6  287.17  4557.8  284.30  4767.5  279.43  4949.4  277.69  5004.9  277.13
  5037.6  276.76  5038.1  276.26  5045.0  276.76  5095.5  278.24  5142.3  277.71
  5192.8  279.06  5233.2  278.45  5361.2  279.73  5457.3  280.45  5707.8  286.56
  5766.9  290.12  5869.3  293.69  5940.0  292.93  6074.7  296.80  6206.1  298.52
#Mann=9,-1,0
  3767.9    0.12       0  3781.4    0.05       0  4949.4    0.04       0
  5004.9    0.12       0  5037.6    0.04       0  5045.0    0.12       0
  5361.2    0.04       0  5766.9    0.12       0  6074.7    0.04       0
Bank Sta=5037.6,5045
Exp/Cntr=0.3,0.1

Type RM Length L Ch R = 1,21986,209,209,209
BEGIN DESCRIPTION:
Mapping XS a75e9615
END DESCRIPTION:
XS GIS Cut Line= 3
      2456218.16     13545460.78      2454829.26     13544783.69
      2453601.01     13544688.21
#Sta/Elev= 30
  3442.6  300.28  3529.7  299.37  3657.5  298.29  3763.5  298.75  3854.8  296.10
  3921.3  294.77  3926.8  293.29  3949.4  291.29  3988.9  292.82  4024.6  291.03
  4040.6  291.32  4070.6  291.45  4414.0  285.49  4569.8  284.08  4636.5  283.24
  4718.0  280.18  4825.9  277.85  5018.4  275.61  5018.9  275.11  5025.9  275.61
  5161.0  278.67  5473.5  281.28  5545.6  280.90  5593.8  283.36  5734.3  285.04
  5774.4  286.60  5794.4  284.61  5809.5  287.71  5939.2  288.70  6219.7  293.13
#Mann=11,-1,0
  3442.6    0.05       0  3529.7    0.12       0  3854.8   0.013       0
  4040.6    0.05       0  4070.6    0.04       0  4569.8    0.05       0
  4718.0    0.04       0  4825.9    0.12       0  5018.4    0.05       0
  5025.9    0.12       0  5545.6    0.04       0
Bank Sta=5018.4,5025.9
Exp/Cntr=0.3,0.1

Type RM Length L Ch R = 1,21777,324,324,324
BEGIN DESCRIPTION:
Mapping XS 74bcc3ee
END DESCRIPTION:
XS GIS Cut Line= 3
      2456456.87     13545308.87      2454820.58     13544571.02
      2453831.04     13544176.07
#Sta/Elev= 30
  3264.7  301.00  3296.2  300.79  3359.6  301.23  3365.5  300.10  3388.2  300.22
  3405.9  298.96  3411.4  299.65  3429.0  298.27  3605.9  295.12  3712.4  293.42
  3713.8  293.52  3723.1  294.25  3751.7  292.98  3774.8  295.00  3818.9  294.09
  3849.7  292.04  4138.4  287.91  4225.8  287.24  4351.4  285.75  4484.9  285.03
  4883.9  277.07  4945.5  275.78  5034.3  275.77  5034.8  275.27  5041.8  275.77
  5227.9  277.44  5367.1  280.06  5636.3  289.51  6031.4  289.87  6125.1  291.60
#Mann=14,-1,0
  3264.7    0.05       0  3296.2   0.013       0  3605.9    0.12       0
  3712.4    0.05       0  3713.8   0.013       0  3818.9    0.05       0
  4138.4    0.04       0  4225.8    0.05       0  4351.4    0.04       0
  4484.9    0.05       0  4883.9    0.12       0  5034.3    0.05       0
  5041.8    0.12       0  5227.9    0.04       0
Bank Sta=5034.3,5041.8
Exp/Cntr=0.3,0.1