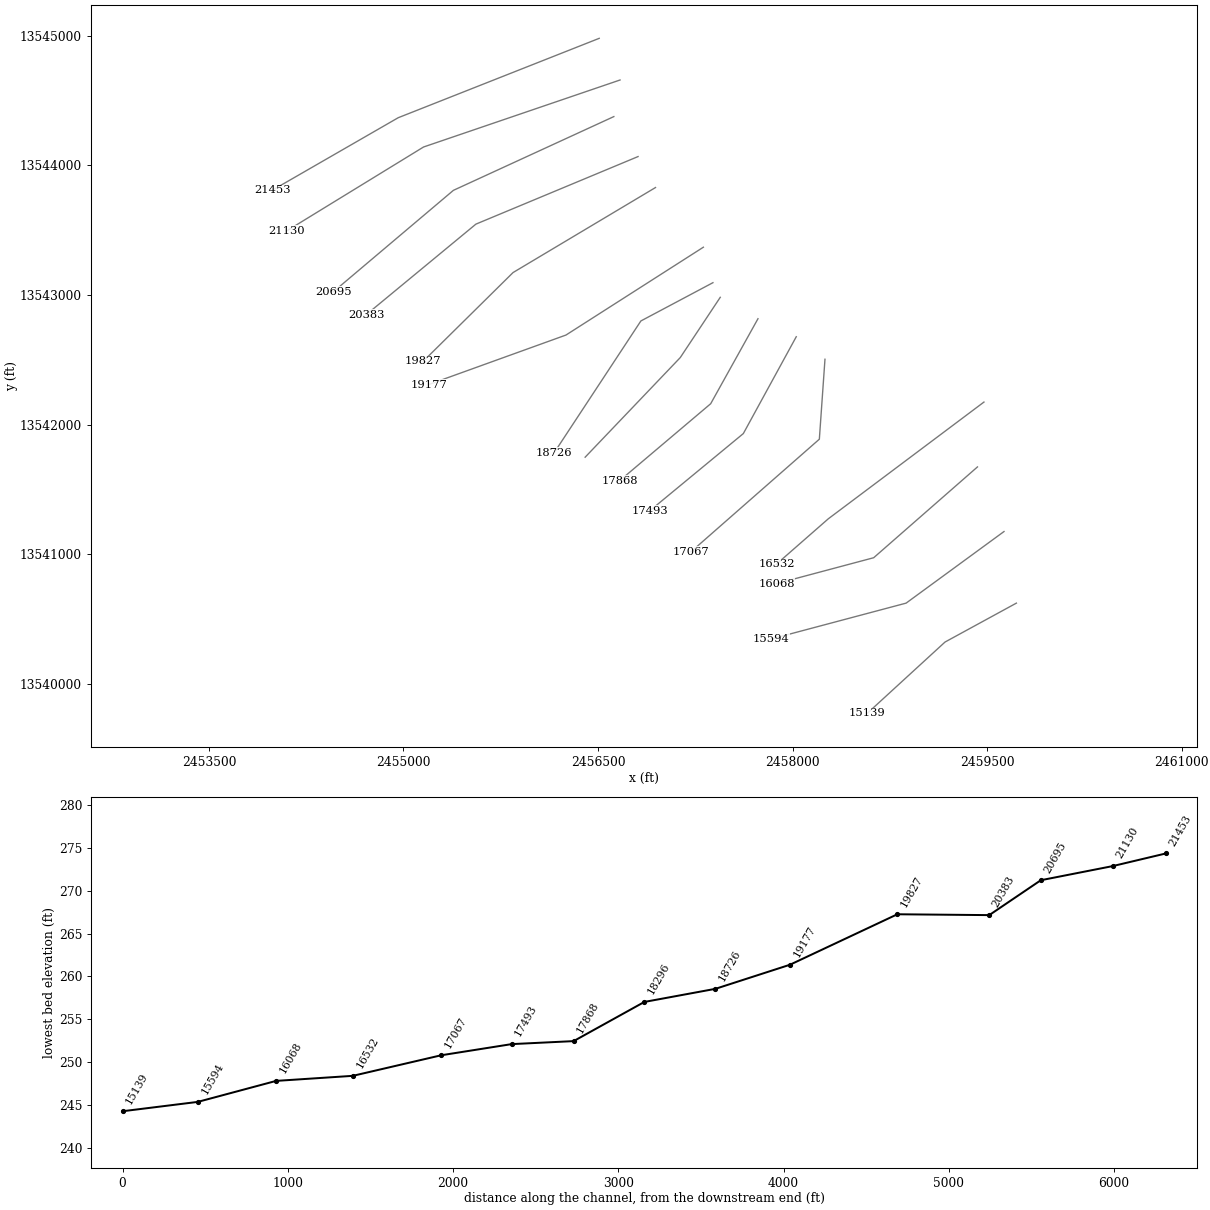
HEC-RAS study FIFTEENMILE CREEK.prj: FIFTEENMILE CREEK Base Level Engineering

--- FIFTEENMILE CREEK.g01 (geometry) --- (continued)

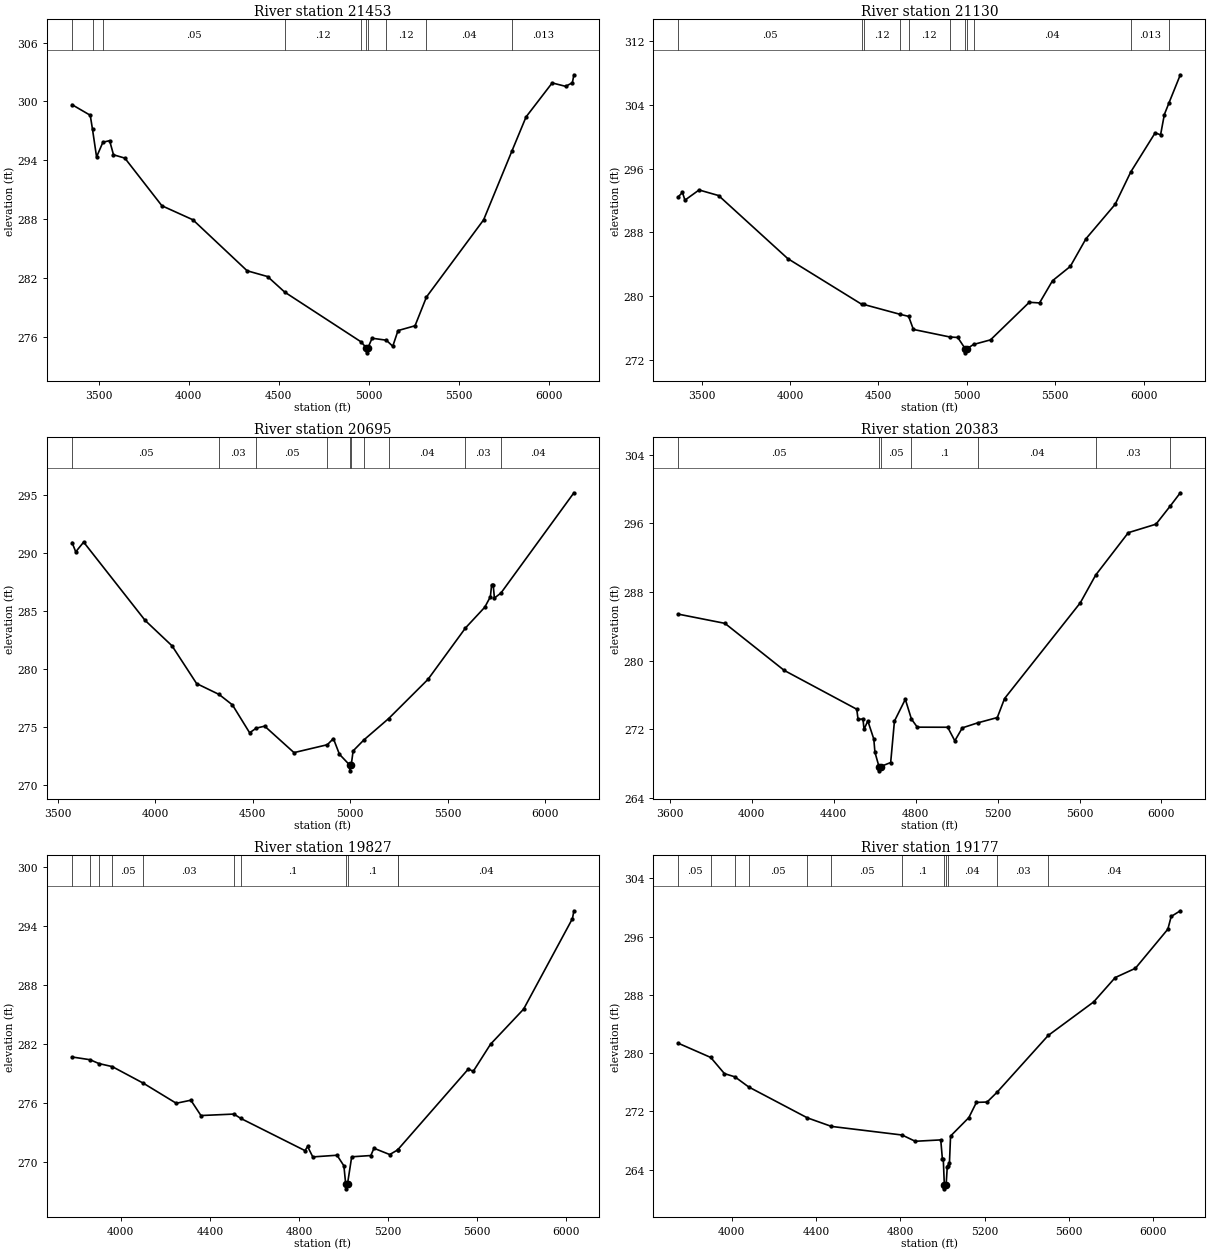
Type RM Length L Ch R = 1,21453,323,323,323
BEGIN DESCRIPTION:
Mapping XS 602904c9
END DESCRIPTION:
XS GIS Cut Line= 3
      2456508.95     13544979.00      2454959.47     13544367.03
      2453988.61     13543807.91
#Sta/Elev= 30
  3352.6  299.67  3453.5  298.59  3466.1  297.15  3488.6  294.34  3523.8  295.84
  3561.1  296.00  3582.6  294.56  3645.6  294.22  3851.4  289.36  4023.5  287.93
  4324.5  282.73  4438.1  282.14  4533.5  280.55  4956.3  275.49  4987.2  274.86
  4987.7  274.36  4995.0  274.86  5018.3  275.85  5097.1  275.65  5133.1  275.03
  5162.2  276.63  5256.7  277.12  5320.4  280.06  5637.4  287.92  5795.3  294.97
  5873.1  298.42  6018.2  301.89  6092.9  301.54  6130.2  301.91  6138.9  302.72
#Mann=10,-1,0
  3352.6    0.05       0  3466.1   0.013       0  3523.8    0.05       0
  4533.5    0.12       0  4956.3     0.1       0  4987.2    0.05       0
  4995.0     0.1       0  5097.1    0.12       0  5320.4    0.04       0
  5795.3   0.013       0
Bank Sta=4987.2,4995
Exp/Cntr=0.3,0.1

Type RM Length L Ch R = 1,21130,435,435,435
BEGIN DESCRIPTION:
Mapping XS 0b7afa97
END DESCRIPTION:
XS GIS Cut Line= 3
      2456669.56     13544657.83      2455154.79     13544141.33
      2454100.08     13543494.62
#Sta/Elev= 30
  3369.7  292.51  3392.2  293.03  3406.2  292.06  3486.2  293.34  3596.4  292.64
  3987.6  284.72  4406.4  278.97  4416.9  278.96  4622.7  277.72  4671.1  277.46
  4697.9  275.82  4904.5  274.87  4948.8  274.81  4991.5  273.38  4992.0  272.88
  4999.4  273.38  5038.0  273.93  5134.1  274.51  5353.2  279.23  5411.2  279.15
  5484.7  281.94  5585.3  283.74  5673.7  287.21  5838.6  291.53  5927.3  295.61
  6064.9  300.51  6095.7  300.27  6117.0  302.82  6143.2  304.28  6207.3  307.81
#Mann=11,-1,0
  3369.7    0.05       0  4406.4    0.03       0  4416.9    0.12       0
  4622.7    0.05       0  4671.1    0.12       0  4904.5     0.1       0
  4991.5    0.05       0  4999.4     0.1       0  5038.0    0.04       0
  5927.3   0.013       0  6143.2    0.04       0
Bank Sta=4991.5,4999.4
Exp/Cntr=0.3,0.1

Type RM Length L Ch R = 1,20695,312,312,312
BEGIN DESCRIPTION:
Mapping XS 89e456e3
END DESCRIPTION:
XS GIS Cut Line= 3
      2456621.79     13544375.70      2455384.82     13543807.13
      2454460.31     13543025.85
#Sta/Elev= 30
  3574.2  290.90  3593.0  290.10  3633.5  290.94  3948.7  284.19  4086.6  282.00
  4212.4  278.75  4327.9  277.81  4396.1  276.91  4484.1  274.51  4518.2  274.91
  4561.2  275.08  4711.5  272.80  4882.3  273.48  4913.4  274.01  4944.3  272.66
  4996.8  271.73  4997.3  271.23  5004.8  271.73  5014.5  272.95  5069.4  273.89
  5196.9  275.74  5398.0  279.11  5590.2  283.54  5689.2  285.33  5717.8  286.23
  5724.4  287.27  5732.1  287.28  5738.6  286.12  5772.0  286.55  6146.0  295.19
#Mann=10,-1,0
  3574.2    0.05       0  4327.9    0.03       0  4518.2    0.05       0
  4882.3     0.1       0  4996.8    0.05       0  5004.8     0.1       0
  5069.4    0.05       0  5196.9    0.04       0  5590.2    0.03       0
  5772.0    0.04       0
Bank Sta=4996.8,5004.8
Exp/Cntr=0.3,0.1

Type RM Length L Ch R = 1,20383,556,556,556
BEGIN DESCRIPTION:
Mapping XS c665bce0
END DESCRIPTION:
XS GIS Cut Line= 3
      2456808.48     13544067.57      2455558.43     13543546.71
      2454713.36     13542848.99
#Sta/Elev= 30
  3642.0  285.42  3868.8  284.35  4158.0  278.87  4512.4  274.34  4518.8  273.15
  4542.6  273.21  4548.0  272.00  4566.4  272.98  4595.7  270.86  4601.1  269.33
  4620.9  267.66  4621.4  267.16  4629.0  267.66  4678.0  268.13  4696.4  272.96
  4749.5  275.50  4779.4  273.19  4808.0  272.25  4956.4  272.24  4991.1  270.66
  5027.8  272.17  5102.6  272.75  5198.5  273.37  5234.1  275.59  5603.6  286.74
  5678.9  289.98  5838.2  294.92  5973.3  295.91  6043.7  298.05  6092.1  299.57
#Mann=7,-1,0
  3642.0    0.05       0  4620.9    0.05       0  4629.0    0.05       0
  4779.4     0.1       0  5102.6    0.04       0  5678.9    0.03       0
  6043.7    0.04       0
Bank Sta=4620.9,4629
Exp/Cntr=0.3,0.1

Type RM Length L Ch R = 1,19827,650,650,650
BEGIN DESCRIPTION:
Mapping XS b1559564
END DESCRIPTION:
XS GIS Cut Line= 3
      2456942.98     13543828.83      2455844.89     13543173.45
      2455151.64     13542488.86
#Sta/Elev= 30
  3781.2  280.68  3862.0  280.40  3901.9  280.01  3961.6  279.70  4101.2  278.01
  4248.9  275.97  4314.5  276.28  4359.8  274.72  4508.0  274.87  4537.6  274.44
  4826.9  271.15  4838.6  271.57  4861.9  270.51  4970.8  270.68  5001.6  269.60
  5009.6  267.76  5010.1  267.26  5017.8  267.76  5036.6  270.52  5122.5  270.65
  5136.6  271.39  5207.3  270.75  5242.9  271.22  5243.1  271.23  5560.9  279.47
  5582.1  279.21  5659.9  281.98  5808.4  285.55  6027.6  294.76  6034.3  295.56
#Mann=11,-1,0
  3781.2    0.03       0  3862.0    0.05       0  3901.9    0.03       0
  3961.6    0.05       0  4101.2    0.03       0  4508.0    0.05       0
  4537.6     0.1       0  5009.6    0.05       0  5017.8     0.1       0
  5242.9    0.05       0  5243.1    0.04       0
Bank Sta=5009.6,5017.8
Exp/Cntr=0.3,0.1

Type RM Length L Ch R = 1,19177,451,451,451
BEGIN DESCRIPTION:
Mapping XS 150c5d2b
END DESCRIPTION:
XS GIS Cut Line= 3
      2457311.93     13543368.78      2456252.88     13542691.68
      2455194.23     13542309.87
#Sta/Elev= 30
  3746.8  281.35  3899.9  279.41  3965.0  277.19  4014.6  276.75  4080.1  275.36
  4358.4  271.12  4473.1  269.94  4808.4  268.76  4870.7  267.90  4991.9  268.09
  4999.6  265.49  5003.8  265.49  5009.0  261.87  5009.5  261.37  5017.3  261.87
  5022.8  264.38  5024.9  264.50  5033.2  264.97  5038.5  268.62  5125.2  271.15
  5161.2  273.24  5212.0  273.29  5259.1  274.63  5502.0  282.43  5717.6  287.03
  5820.1  290.38  5915.8  291.65  6069.9  297.02  6085.9  298.77  6129.2  299.55
#Mann=12,-1,0
  3746.8    0.05       0  3899.9   0.013       0  4014.6    0.12       0
  4080.1    0.05       0  4358.4    0.12       0  4473.1    0.05       0
  4808.4     0.1       0  5009.0    0.05       0  5017.3     0.1       0
  5024.9    0.04       0  5259.1    0.03       0  5502.0    0.04       0
Bank Sta=5009,5017.3
Exp/Cntr=0.3,0.1

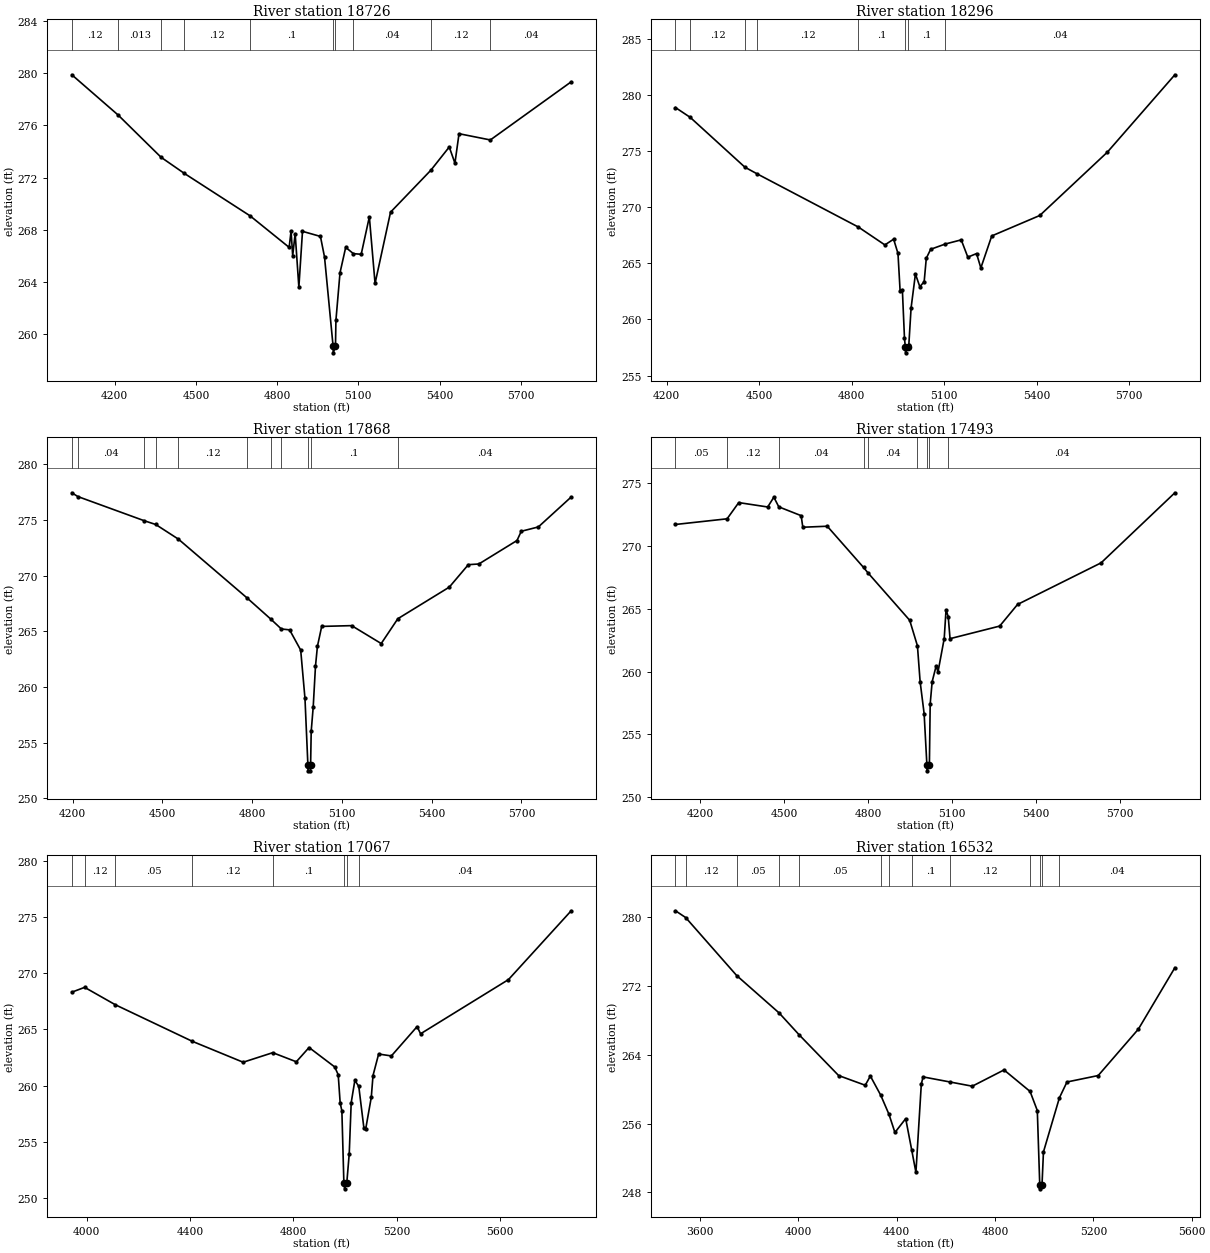
Type RM Length L Ch R = 1,18726,430,430,430
BEGIN DESCRIPTION:
Mapping XS 6b931ad9
END DESCRIPTION:
XS GIS Cut Line= 3
      2457385.67     13543095.32      2456830.13     13542800.19
      2456161.73     13541784.56
#Sta/Elev= 30
  4041.5  279.89  4212.7  276.80  4371.3  273.56  4456.8  272.33  4700.0  269.07
  4844.4  266.65  4851.5  267.90  4857.5  266.01  4866.6  267.71  4880.3  263.60
  4893.7  267.88  4960.0  267.49  4975.1  265.91  5006.8  259.06  5007.3  258.56
  5015.6  259.06  5017.2  261.05  5032.3  264.70  5053.3  266.65  5081.7  266.17
  5110.6  266.12  5140.7  268.99  5161.8  263.88  5219.0  269.35  5368.0  272.57
  5435.9  274.35  5456.9  273.11  5472.0  275.37  5587.7  274.89  5886.4  279.35
#Mann=10,-1,0
  4041.5    0.12       0  4212.7   0.013       0  4371.3    0.05       0
  4456.8    0.12       0  4700.0     0.1       0  5006.8    0.05       0
  5015.6     0.1       0  5081.7    0.04       0  5368.0    0.12       0
  5587.7    0.04       0
Bank Sta=5006.8,5015.6
Exp/Cntr=0.3,0.1

Type RM Length L Ch R = 1,18296,428,428,428
BEGIN DESCRIPTION:
Mapping XS 8959f43a
END DESCRIPTION:
XS GIS Cut Line= 3
      2457442.13     13542982.50      2457133.95     13542518.07
      2456400.55     13541749.95
#Sta/Elev= 30
  4229.0  278.87  4276.6  278.00  4454.1  273.56  4492.9  272.98  4822.1  268.23
  4908.0  266.64  4936.4  267.15  4950.5  265.88  4957.4  262.54  4964.7  262.66
  4971.6  258.32  4974.4  257.53  4974.9  257.03  4983.3  257.53  4985.7  257.75
  4993.0  261.03  5007.1  264.05  5021.3  262.92  5035.4  263.36  5042.3  265.45
  5056.5  266.25  5103.9  266.72  5155.6  267.09  5177.0  265.55  5205.3  265.87
  5219.2  264.59  5254.6  267.44  5410.3  269.26  5629.5  274.90  5848.4  281.79
#Mann=8,-1,0
  4229.0    0.04       0  4276.6    0.12       0  4454.1   0.013       0
  4492.9    0.12       0  4822.1     0.1       0  4974.4    0.05       0
  4983.3     0.1       0  5103.9    0.04       0
Bank Sta=4974.4,4983.3
Exp/Cntr=0.3,0.1

Type RM Length L Ch R = 1,17868,375,375,375
BEGIN DESCRIPTION:
Mapping XS e322fae4
END DESCRIPTION:
XS GIS Cut Line= 3
      2457732.93     13542817.58      2457368.33     13542162.16
      2456666.69     13541568.80
#Sta/Elev= 30
  4197.5  277.45  4217.7  277.11  4439.3  274.94  4477.9  274.60  4553.9  273.28
  4783.1  268.00  4862.7  266.09  4897.7  265.21  4925.3  265.13  4962.4  263.31
  4976.7  258.97  4986.5  252.96  4987.0  252.46  4995.0  252.46  4995.5  252.96
  4997.5  256.01  5004.2  258.19  5011.8  261.86  5018.3  263.65  5032.6  265.44
  5132.7  265.51  5231.5  263.90  5287.0  266.13  5459.0  268.97  5522.7  270.99
  5557.8  271.05  5685.3  273.16  5699.6  273.99  5756.7  274.38  5866.4  277.07
#Mann=11,-1,0
  4197.5    0.05       0  4217.7    0.04       0  4439.3    0.12       0
  4477.9    0.04       0  4553.9    0.12       0  4783.1    0.04       0
  4862.7   0.013       0  4897.7     0.1       0  4986.5    0.05       0
  4995.5     0.1       0  5287.0    0.04       0
Bank Sta=4986.5,4995.5
Exp/Cntr=0.3,0.1

Type RM Length L Ch R = 1,17493,426,426,426
BEGIN DESCRIPTION:
Mapping XS f7023651
END DESCRIPTION:
XS GIS Cut Line= 3
      2458028.04     13542678.65      2457620.06     13541932.13
      2456901.27     13541338.91
#Sta/Elev= 30
  4112.1  271.70  4296.3  272.15  4337.9  273.44  4441.3  273.09  4463.2  273.87
  4480.9  273.10  4560.7  272.40  4566.6  271.48  4653.9  271.56  4783.5  268.28
  4799.7  267.84  4948.2  264.08  4975.8  262.05  4985.4  259.20  4999.7  256.66
  5009.5  252.61  5010.0  252.11  5018.5  252.61  5021.3  257.43  5028.4  259.20
  5042.7  260.46  5049.2  259.97  5071.4  262.63  5077.9  264.92  5085.8  264.36
  5092.2  262.62  5269.4  263.62  5333.2  265.34  5631.6  268.65  5894.8  274.22
#Mann=9,-1,0
  4112.1    0.05       0  4296.3    0.12       0  4480.9    0.04       0
  4783.5    0.05       0  4799.7    0.04       0  4975.8     0.1       0
  5009.5    0.05       0  5018.5     0.1       0  5085.8    0.04       0
Bank Sta=5009.5,5018.5
Exp/Cntr=0.3,0.1

Type RM Length L Ch R = 1,17067,535,535,535
BEGIN DESCRIPTION:
Mapping XS 946c2d72
END DESCRIPTION:
XS GIS Cut Line= 3
      2458249.41     13542505.08      2458206.00     13541888.73
      2457216.44     13541020.70
#Sta/Elev= 30
  3942.0  268.30  3991.6  268.73  4110.7  267.18  4408.7  263.93  4605.6  262.07
  4720.3  262.92  4811.5  262.11  4860.9  263.38  4960.3  261.65  4973.8  260.96
  4981.4  258.44  4988.0  257.75  4995.6  251.45  4997.7  251.31  4998.2  250.81
  5006.9  251.31  5016.5  253.93  5024.1  258.47  5038.3  260.46  5053.5  259.92
  5073.4  256.20  5080.1  256.11  5101.9  258.95  5108.6  260.89  5130.4  262.80
  5179.7  262.63  5279.4  265.24  5292.8  264.60  5633.3  269.42  5876.2  275.54
#Mann=8,-1,0
  3942.0    0.05       0  3991.6    0.12       0  4110.7    0.05       0
  4408.7    0.12       0  4720.3     0.1       0  4997.7    0.05       0
  5006.9     0.1       0  5053.5    0.04       0
Bank Sta=4997.7,5006.9
Exp/Cntr=0.3,0.1

Type RM Length L Ch R = 1,16532,464,464,464
BEGIN DESCRIPTION:
FIFTEENMILE CREEK 158.0
END DESCRIPTION:
XS GIS Cut Line= 3
      2459475.02     13542175.01      2458275.00     13541275.00
      2457875.02     13540925.02
#Sta/Elev= 30
  3500.2  280.73  3541.7  279.94  3749.2  273.20  3921.9  268.85  4003.3  266.31
  4163.8  261.58  4272.1  260.45  4292.9  261.52  4335.2  259.29  4368.7  257.07
  4392.9  254.96  4436.7  256.57  4461.3  252.90  4478.3  250.32  4500.2  260.59
  4507.5  261.42  4615.3  260.84  4707.5  260.34  4836.7  262.23  4942.7  259.73
  4972.1  257.51  4982.0  248.91  4982.5  248.41  4991.3  248.91  4997.1  252.70
  5062.0  258.99  5092.8  260.83  5219.9  261.58  5383.2  266.97  5531.7  274.11
#Mann=13,-1,0
  3500.2    0.05       0  3541.7    0.12       0  3749.2    0.05       0
  3921.9    0.12       0  4003.3    0.05       0  4335.2     0.1       0
  4368.7    0.12       0  4461.3     0.1       0  4615.3    0.12       0
  4942.7     0.1       0  4982.0    0.05       0  4991.3     0.1       0
  5062.0    0.04       0
Bank Sta=4982,4991.3
Exp/Cntr=0.3,0.1

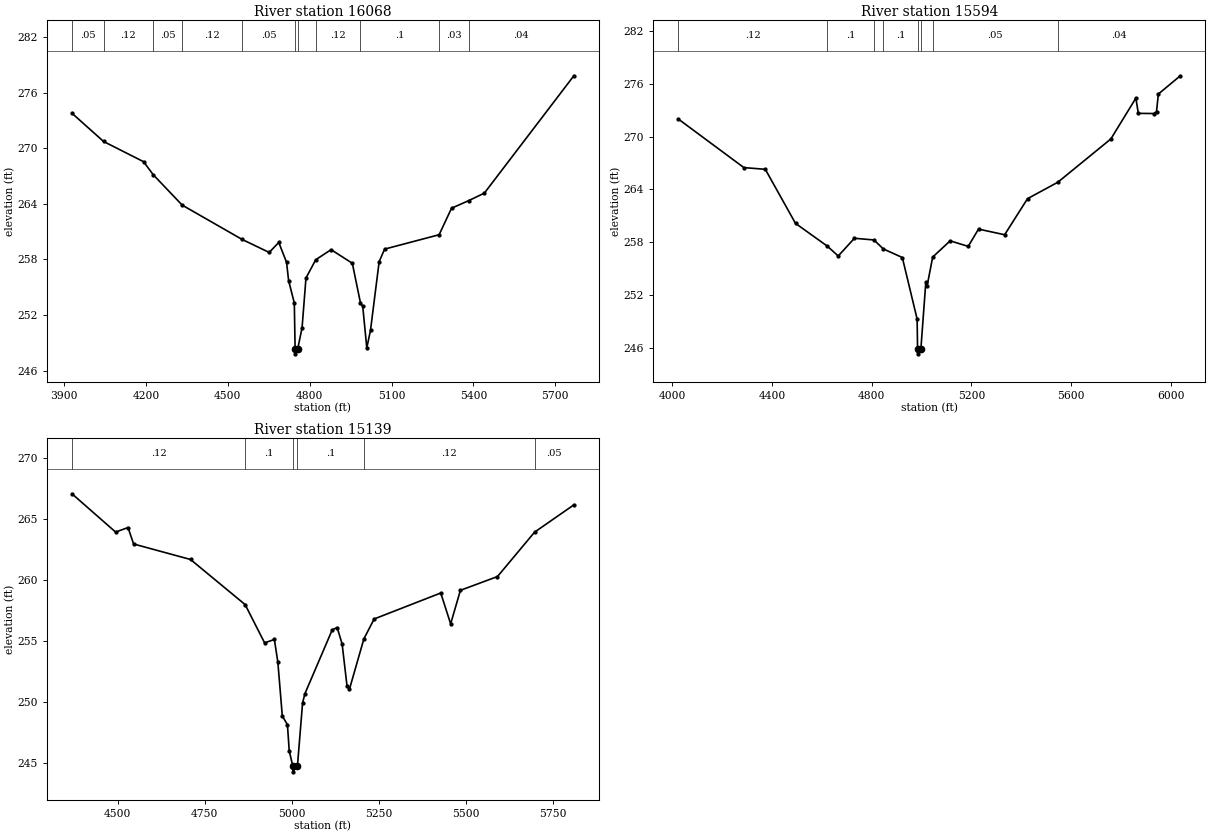
Type RM Length L Ch R = 1,16068,474,474,474
BEGIN DESCRIPTION:
FIFTEENMILE CREEK 157.0
END DESCRIPTION:
XS GIS Cut Line= 3
      2459425.03     13541675.02      2458625.00     13540975.00
      2457874.96     13540774.99
#Sta/Elev= 30
  3928.7  273.78  4044.6  270.73  4191.2  268.55  4226.1  267.16  4332.5  263.87
  4551.9  260.17  4651.5  258.76  4686.6  259.84  4715.1  257.70  4722.7  255.72
  4743.6  253.30  4746.5  248.32  4747.0  247.82  4755.8  248.32  4772.0  250.63
  4786.3  256.00  4822.0  257.97  4878.3  259.06  4956.2  257.59  4986.1  253.30
  4994.3  252.95  5009.2  248.46  5022.8  250.36  5054.5  257.77  5074.5  259.12
  5274.3  260.67  5319.7  263.53  5382.7  264.35  5440.0  265.16  5768.0  277.82
#Mann=11,-1,0
  3928.7    0.05       0  4044.6    0.12       0  4226.1    0.05       0
  4332.5    0.12       0  4551.9    0.05       0  4746.5    0.05       0
  4755.8    0.05       0  4822.0    0.12       0  4986.1     0.1       0
  5274.3    0.03       0  5382.7    0.04       0
Bank Sta=4746.5,4755.8
Exp/Cntr=0.3,0.1

Type RM Length L Ch R = 1,15594,455,455,455
BEGIN DESCRIPTION:
FIFTEENMILE CREEK 156.0
END DESCRIPTION:
XS GIS Cut Line= 3
      2459629.60     13541176.92      2458875.00     13540625.00
      2457832.70     13540347.92
#Sta/Elev= 30
  4024.7  271.98  4287.4  266.48  4373.2  266.29  4494.4  260.16  4622.4  257.57
  4665.8  256.46  4730.7  258.47  4809.0  258.28  4846.8  257.26  4922.9  256.29
  4982.3  249.31  4984.1  245.87  4984.6  245.37  4997.2  245.87  5017.2  253.52
  5022.4  253.08  5044.7  256.34  5114.8  258.18  5187.2  257.55  5228.6  259.51
  5333.3  258.87  5425.2  262.96  5546.6  264.82  5759.5  269.73  5859.8  274.36
  5869.6  272.63  5932.2  272.61  5942.6  272.84  5950.0  274.82  6038.1  276.89
#Mann=8,-1,0
  4024.7    0.12       0  4622.4     0.1       0  4809.0    0.12       0
  4846.8     0.1       0  4984.1    0.05       0  4997.2     0.1       0
  5044.7    0.05       0  5546.6    0.04       0
Bank Sta=4984.1,4997.2
Exp/Cntr=0.3,0.1

Type RM Length L Ch R = 1,15139,474,474,474
BEGIN DESCRIPTION:
FIFTEENMILE CREEK 155.0
END DESCRIPTION:
XS GIS Cut Line= 3
      2459724.99     13540624.99      2459175.00     13540325.00
      2458575.02     13539775.02
#Sta/Elev= 30
  4369.0  267.09  4494.3  263.95  4529.9  264.32  4546.0  262.97  4709.3  261.70
  4866.0  258.00  4921.9  254.86  4949.9  255.14  4959.9  253.28  4972.7  248.86
  4987.4  248.15  4992.6  245.99  5002.6  244.78  5003.1  244.28  5016.2  244.78
  5030.9  249.94  5037.7  250.70  5116.0  255.93  5130.2  256.12  5144.4  254.76
  5158.3  251.35  5165.4  251.06  5206.8  255.19  5236.3  256.82  5427.4  258.95
  5455.8  256.42  5483.8  259.17  5590.2  260.30  5696.6  263.94  5809.4  266.18
#Mann=6,-1,0
  4369.0    0.12       0  4866.0     0.1       0  5002.6    0.05       0
  5016.2     0.1       0  5206.8    0.12       0  5696.6    0.05       0
Bank Sta=5002.6,5016.2
Exp/Cntr=0.3,0.1