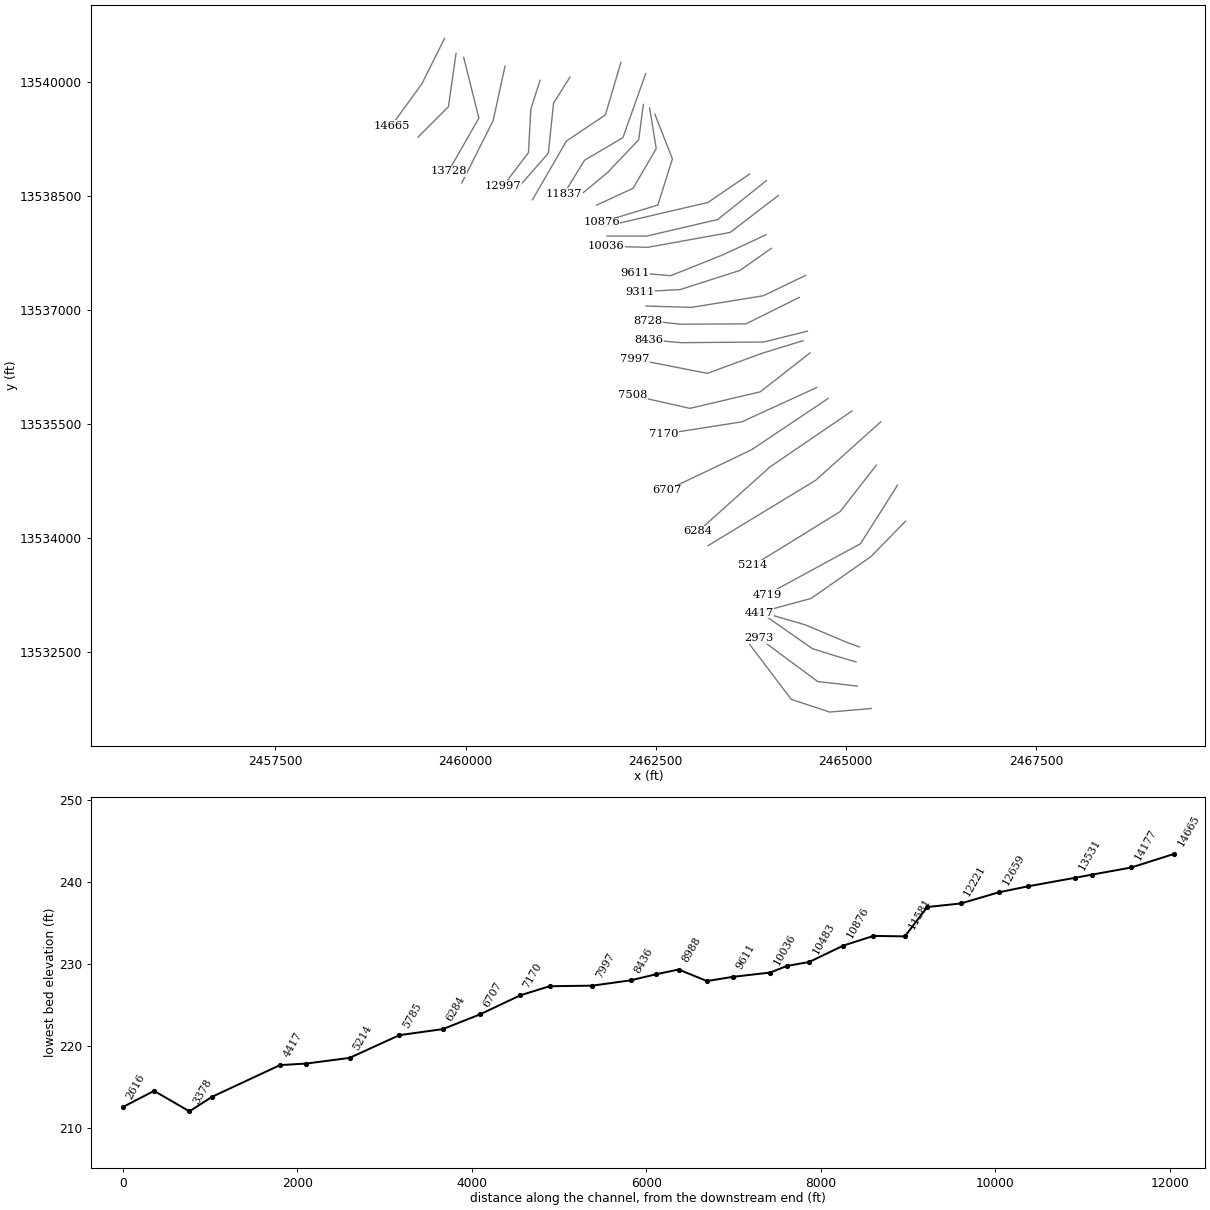
HEC-RAS study FIFTEENMILE CREEK.prj: FIFTEENMILE CREEK Base Level Engineering

--- FIFTEENMILE CREEK.g01 (geometry) --- (continued)

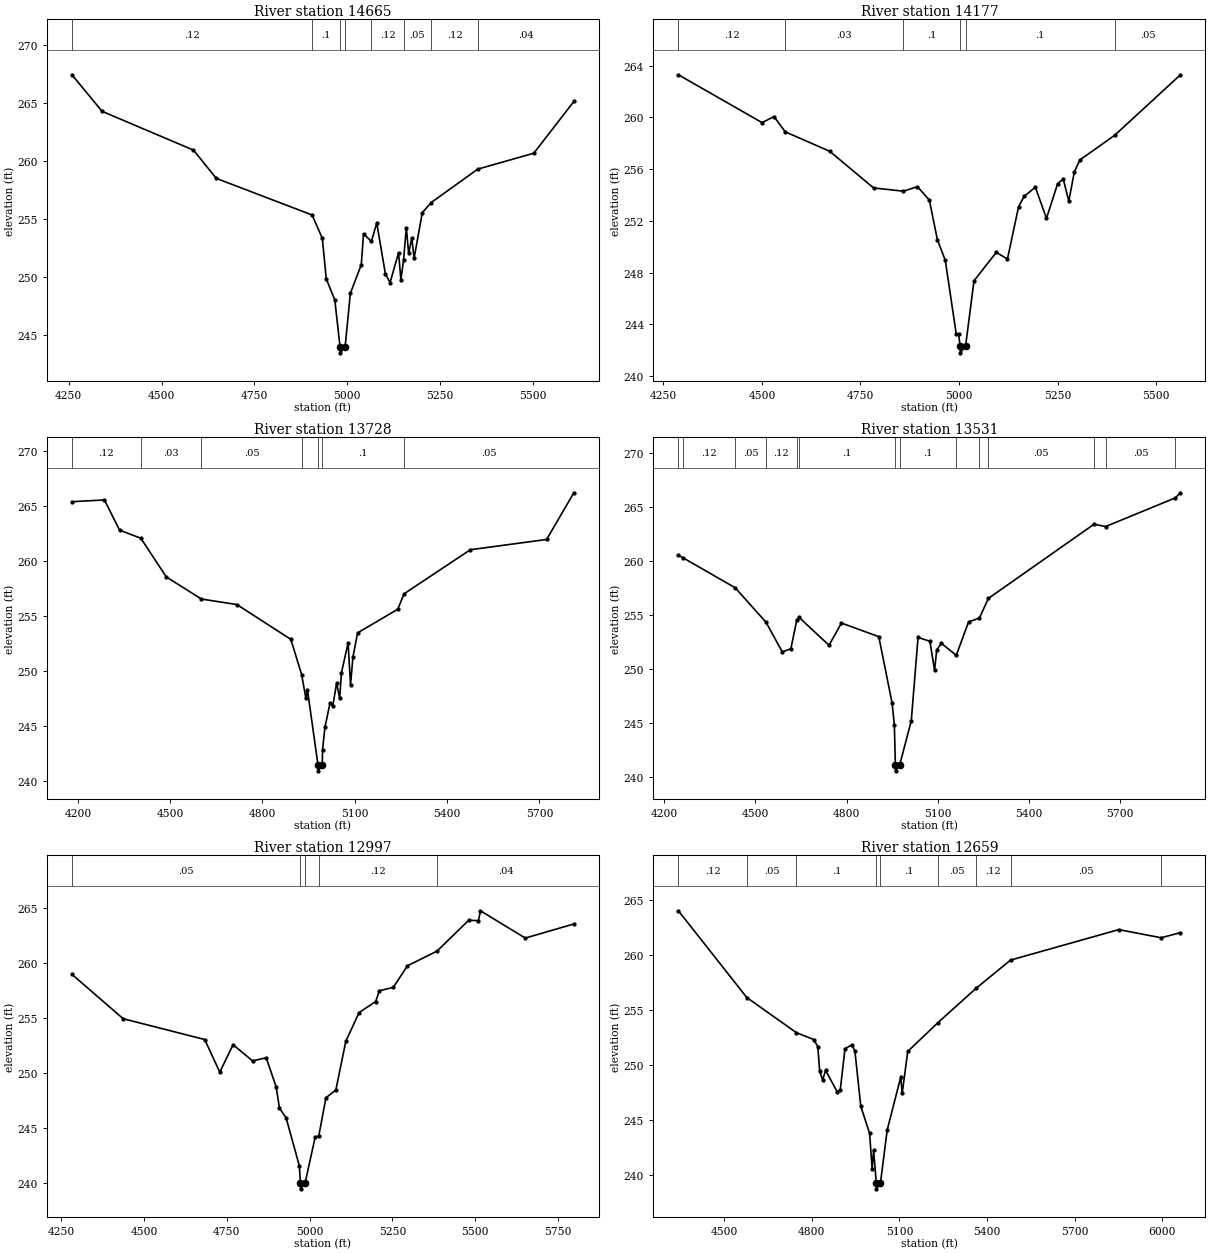
Type RM Length L Ch R = 1,14665,488,488,488
BEGIN DESCRIPTION:
FIFTEENMILE CREEK 154.0
END DESCRIPTION:
XS GIS Cut Line= 3
      2459725.02     13540575.03      2459425.00     13539975.00
      2459025.02     13539425.02
#Sta/Elev= 30
  4258.9  267.40  4340.0  264.25  4586.0  260.91  4647.5  258.47  4905.2  255.32
  4932.8  253.31  4943.3  249.83  4966.5  247.98  4980.5  243.94  4981.0  243.44
  4994.1  243.94  5008.2  248.56  5037.6  251.03  5043.7  253.70  5064.9  253.04
  5079.3  254.63  5102.5  250.25  5115.2  249.49  5138.0  252.07  5144.2  249.73
  5151.4  251.42  5158.9  254.24  5165.1  252.01  5173.6  253.33  5179.8  251.59
  5201.8  255.51  5225.7  256.39  5351.2  259.27  5502.0  260.64  5609.8  265.10
#Mann=8,-1,0
  4258.9    0.12       0  4905.2     0.1       0  4980.5    0.05       0
  4994.1     0.1       0  5064.9    0.12       0  5151.4    0.05       0
  5225.7    0.12       0  5351.2    0.04       0
Bank Sta=4980.5,4994.1
Exp/Cntr=0.3,0.1

Type RM Length L Ch R = 1,14177,449,449,449
BEGIN DESCRIPTION:
FIFTEENMILE CREEK 153.0
END DESCRIPTION:
XS GIS Cut Line= 3
      2459875.01     13540375.04      2459775.00     13539675.00
      2459375.03     13539275.03
#Sta/Elev= 30
  4288.3  263.29  4500.5  259.59  4530.8  260.06  4559.1  258.88  4672.2  257.37
  4783.3  254.54  4859.0  254.29  4894.4  254.64  4924.7  253.60  4944.9  250.55
  4965.1  248.94  4992.9  243.23  4999.0  243.23  5002.7  242.29  5003.2  241.79
  5016.4  242.29  5037.9  247.36  5094.4  249.56  5122.7  249.04  5151.0  253.10
  5165.2  253.89  5193.4  254.60  5221.7  252.19  5250.0  254.87  5264.2  255.23
  5278.3  253.52  5292.4  255.79  5306.6  256.71  5394.2  258.60  5561.1  263.28
#Mann=6,-1,0
  4288.3    0.12       0  4559.1    0.03       0  4859.0     0.1       0
  5002.7    0.05       0  5016.4     0.1       0  5394.2    0.05       0
Bank Sta=5002.7,5016.4
Exp/Cntr=0.3,0.1

Type RM Length L Ch R = 1,13728,197,197,197
BEGIN DESCRIPTION:
FIFTEENMILE CREEK 152.0
END DESCRIPTION:
XS GIS Cut Line= 3
      2459975.01     13540324.96      2460175.00     13539525.00
      2459775.00     13538825.00
#Sta/Elev= 30
  4180.9  265.36  4286.5  265.52  4335.5  262.78  4404.7  262.04  4487.5  258.53
  4601.7  256.52  4716.9  256.02  4892.1  252.86  4927.2  249.66  4941.1  247.49
  4946.2  248.26  4980.5  241.42  4981.0  240.92  4994.3  241.42  4995.2  242.85
  5002.9  244.87  5019.2  247.05  5028.5  246.82  5040.8  248.88  5050.8  247.52
  5056.6  249.84  5078.2  252.54  5086.1  248.75  5094.0  251.28  5109.1  253.45
  5239.4  255.59  5260.2  257.00  5475.5  261.00  5723.2  261.93  5811.7  266.17
#Mann=7,-1,0
  4180.9    0.12       0  4404.7    0.03       0  4601.7    0.05       0
  4927.2     0.1       0  4980.5    0.05       0  4994.3     0.1       0
  5260.2    0.05       0
Bank Sta=4980.5,4994.3
Exp/Cntr=0.3,0.1

Type RM Length L Ch R = 1,13531,534,534,534
BEGIN DESCRIPTION:
Mapping XS 739142c9
END DESCRIPTION:
XS GIS Cut Line= 3
      2460519.37     13540209.05      2460363.12     13539492.89
      2459950.80     13538672.60
#Sta/Elev= 30
  4246.6  260.54  4261.5  260.30  4433.2  257.52  4534.7  254.32  4588.5  251.56
  4616.5  251.86  4636.2  254.55  4643.9  254.76  4742.0  252.18  4783.0  254.24
  4905.8  252.98  4949.6  246.81  4957.0  244.76  4960.3  241.03  4960.8  240.53
  4974.1  241.03  5012.6  245.17  5034.9  252.91  5074.0  252.55  5089.2  249.85
  5096.3  251.75  5111.6  252.36  5160.7  251.25  5201.1  254.35  5236.6  254.70
  5266.3  256.53  5613.7  263.41  5652.1  263.20  5881.6  265.86  5897.7  266.33
#Mann=14,-1,0
  4246.6     0.1       0  4261.5    0.12       0  4433.2    0.05       0
  4534.7    0.12       0  4636.2    0.05       0  4643.9     0.1       0
  4960.3    0.05       0  4974.1     0.1       0  5160.7    0.05       0
  5236.6     0.1       0  5266.3    0.05       0  5613.7    0.12       0
  5652.1    0.05       0  5881.6    0.04       0
Bank Sta=4960.3,4974.1
Exp/Cntr=0.3,0.1

Type RM Length L Ch R = 1,12997,338,338,338
BEGIN DESCRIPTION:
Mapping XS b293c91c
END DESCRIPTION:
XS GIS Cut Line= 4
      2460979.44     13540022.41      2460857.91     13539640.46
      2460827.53     13539071.89      2460497.70     13538637.90
#Sta/Elev= 30
  4282.6  258.99  4437.3  254.96  4683.4  253.07  4728.9  250.10  4769.0  252.60
  4827.9  251.13  4869.1  251.41  4899.2  248.76  4909.2  246.82  4929.2  245.95
  4969.3  241.57  4972.3  240.00  4972.8  239.50  4986.3  240.00  5016.7  244.17
  5028.0  244.34  5049.4  247.77  5079.4  248.49  5109.5  252.92  5149.5  255.52
  5199.6  256.52  5210.6  257.50  5252.8  257.81  5295.6  259.77  5384.5  261.10
  5480.7  263.91  5509.8  263.87  5516.0  264.77  5651.2  262.29  5797.9  263.57
#Mann=5,-1,0
  4282.6    0.05       0  4972.3    0.05       0  4986.3    0.05       0
  5028.0    0.12       0  5384.5    0.04       0
Bank Sta=4972.3,4986.3
Exp/Cntr=0.3,0.1

Type RM Length L Ch R = 1,12659,438,438,438
BEGIN DESCRIPTION:
Mapping XS 4dad5125
END DESCRIPTION:
XS GIS Cut Line= 4
      2461374.40     13540065.81      2461157.39     13539722.93
      2461087.95     13539063.21      2460659.12     13538573.74
#Sta/Elev= 30
  4342.7  264.02  4577.0  256.14  4746.8  252.95  4806.7  252.32  4820.4  251.68
  4826.8  249.43  4836.9  248.66  4847.0  249.52  4887.2  247.56  4897.2  247.72
  4913.5  251.50  4937.5  251.84  4947.5  251.28  4967.6  246.27  4997.8  243.80
  5006.5  240.60  5011.5  242.26  5020.9  239.26  5021.4  238.76  5034.9  239.26
  5058.1  244.10  5104.5  248.90  5109.5  247.43  5128.5  251.24  5232.5  253.87
  5362.9  256.98  5480.7  259.54  5851.8  262.31  5996.8  261.57  6062.6  262.03
#Mann=9,-1,0
  4342.7    0.12       0  4577.0    0.05       0  4746.8     0.1       0
  5020.9    0.05       0  5034.9     0.1       0  5232.5    0.05       0
  5362.9    0.12       0  5480.7    0.05       0  5996.8    0.04       0
Bank Sta=5020.9,5034.9
Exp/Cntr=0.3,0.1

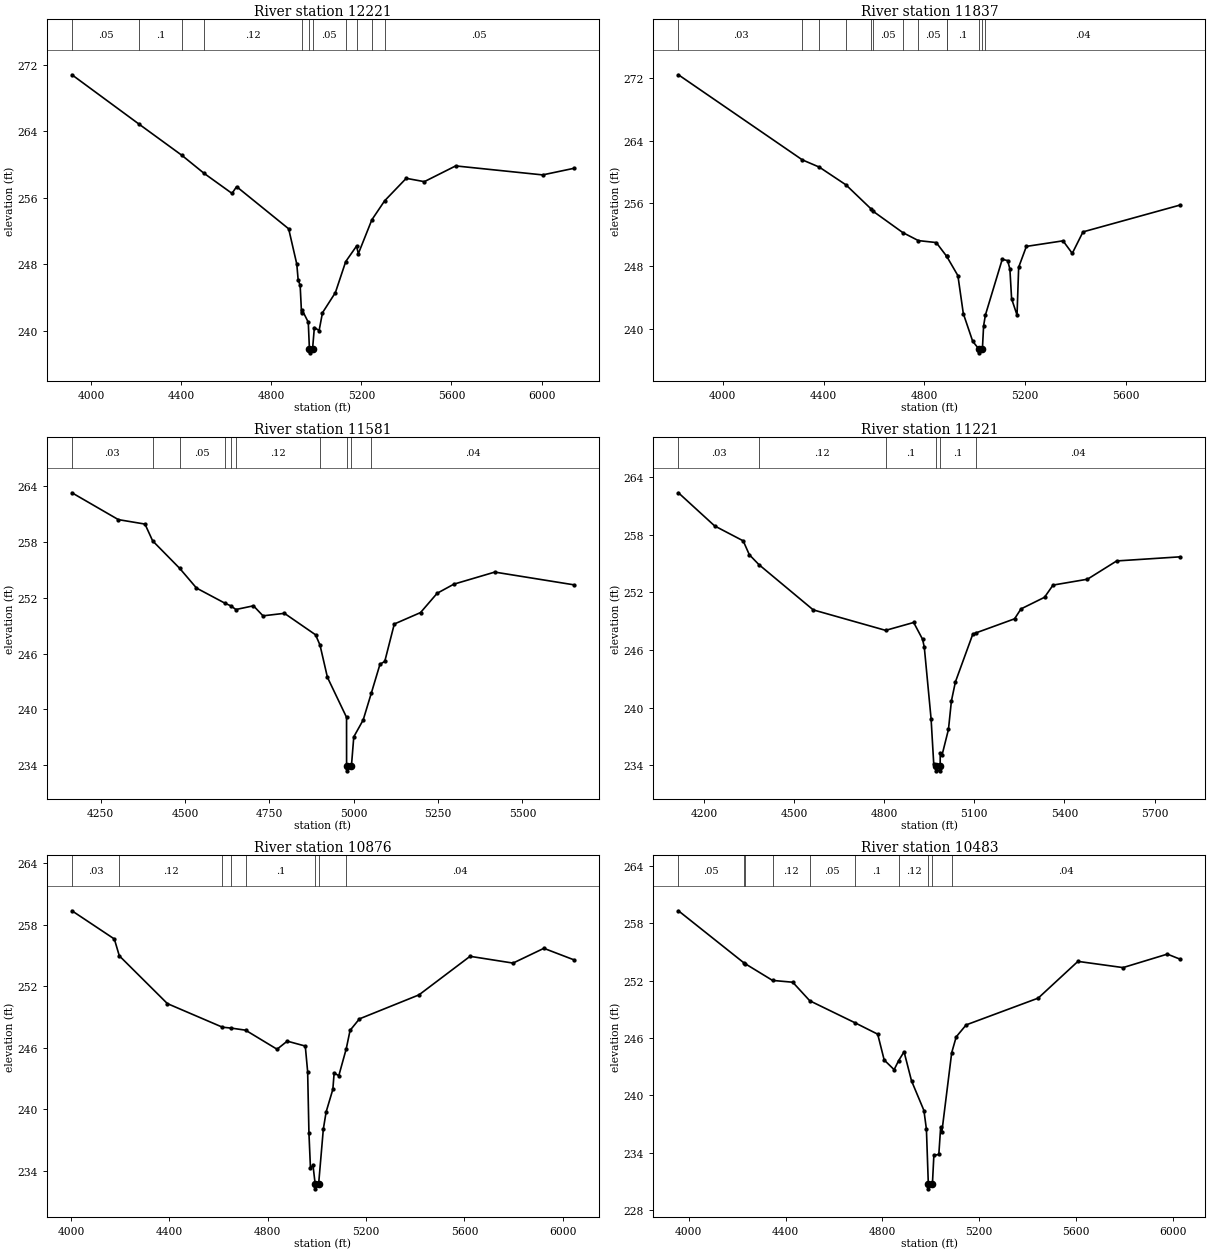
Type RM Length L Ch R = 1,12221,384,384,384
BEGIN DESCRIPTION:
Mapping XS 8bfe69b1
END DESCRIPTION:
XS GIS Cut Line= 4
      2462042.82     13540256.81      2461838.81     13539566.68
      2461326.66     13539223.80      2460879.80     13538451.56
#Sta/Elev= 30
  3915.3  270.77  4213.9  264.83  4403.4  261.10  4501.8  258.94  4625.9  256.53
  4646.3  257.34  4877.4  252.28  4913.5  248.04  4919.5  246.16  4928.4  245.49
  4934.5  242.18  4937.2  242.53  4964.5  241.06  4969.5  237.89  4970.0  237.39
  4983.6  237.89  4991.5  240.43  5012.6  240.07  5027.5  242.20  5084.8  244.62
  5130.6  248.34  5178.8  250.21  5186.7  249.29  5246.7  253.36  5303.4  255.64
  5399.3  258.34  5479.7  257.94  5618.9  259.83  6005.0  258.75  6143.5  259.54
#Mann=11,-1,0
  3915.3    0.05       0  4213.9     0.1       0  4403.4    0.05       0
  4501.8    0.12       0  4937.2    0.05       0  4969.5    0.05       0
  4983.6    0.05       0  5130.6     0.1       0  5178.8   0.013       0
  5246.7     0.1       0  5303.4    0.05       0
Bank Sta=4969.5,4983.6
Exp/Cntr=0.3,0.1

Type RM Length L Ch R = 1,11837,256,256,256
BEGIN DESCRIPTION:
Mapping XS 95056f54
END DESCRIPTION:
XS GIS Cut Line= 4
      2462368.33     13540109.21      2462068.85     13539267.20
      2461565.38     13538972.06      2461296.26     13538533.66
#Sta/Elev= 30
  3824.2  272.41  4316.0  261.56  4383.2  260.64  4488.9  258.38  4587.7  255.34
  4594.6  255.06  4714.2  252.30  4776.3  251.27  4847.4  251.02  4888.4  249.28
  4888.7  249.27  4933.3  246.80  4954.8  241.96  4992.0  238.43  5016.2  237.46
  5016.7  236.96  5030.5  237.46  5035.3  240.41  5042.6  241.80  5109.2  248.88
  5130.7  248.72  5139.6  247.64  5146.4  243.85  5167.9  241.78  5174.4  247.87
  5205.0  250.53  5350.4  251.24  5387.1  249.64  5429.7  252.38  5815.9  255.81
#Mann=13,-1,0
  3824.2    0.03       0  4316.0    0.05       0  4383.2    0.03       0
  4488.9    0.12       0  4587.7   0.013       0  4594.6    0.05       0
  4714.2    0.12       0  4776.3    0.05       0  4888.4   0.013       0
  4888.7     0.1       0  5016.2    0.05       0  5030.5     0.1       0
  5042.6    0.04       0
Bank Sta=5016.2,5030.5
Exp/Cntr=0.3,0.1

Type RM Length L Ch R = 1,11581,360,360,360
BEGIN DESCRIPTION:
Mapping XS 51a74c0a
END DESCRIPTION:
XS GIS Cut Line= 4
      2462337.95     13539705.57      2462277.18     13539241.16
      2461869.20     13538811.47      2461540.84     13538539.28
#Sta/Elev= 30
  4165.0  263.31  4302.5  260.42  4381.4  259.94  4404.2  258.13  4484.6  255.16
  4534.1  253.05  4618.4  251.42  4636.1  251.13  4650.8  250.74  4702.9  251.14
  4731.2  250.06  4794.7  250.33  4886.9  248.02  4900.1  246.91  4922.1  243.44
  4978.8  239.13  4978.9  233.87  4979.4  233.37  4993.2  233.87  5000.2  237.03
  5028.1  238.85  5052.6  241.79  5077.9  244.85  5092.0  245.15  5120.3  249.18
  5198.0  250.41  5247.3  252.49  5296.8  253.47  5418.0  254.77  5652.4  253.40
#Mann=10,-1,0
  4165.0    0.03       0  4404.2    0.12       0  4484.6    0.05       0
  4618.4    0.12       0  4636.1    0.05       0  4650.8    0.12       0
  4900.1     0.1       0  4978.9    0.05       0  4993.2     0.1       0
  5052.6    0.04       0
Bank Sta=4978.9,4993.2
Exp/Cntr=0.3,0.1

Type RM Length L Ch R = 1,11221,345,345,345
BEGIN DESCRIPTION:
Mapping XS 685c5634
END DESCRIPTION:
XS GIS Cut Line= 4
      2462420.41     13539657.81      2462507.22     13539123.97
      2462203.40     13538603.14      2461725.94     13538381.77
#Sta/Elev= 30
  4115.4  262.35  4236.1  258.90  4331.0  257.35  4351.3  255.91  4383.2  254.88
  4564.0  250.17  4804.9  248.04  4898.2  248.86  4927.9  247.11  4933.6  246.28
  4956.1  238.86  4965.1  234.09  4972.1  233.93  4972.6  233.43  4985.9  233.43
  4986.4  233.93  4986.6  235.29  4992.4  235.04  5014.0  237.74  5023.8  240.70
  5037.1  242.68  5095.0  247.65  5106.5  247.79  5233.9  249.24  5255.3  250.27
  5333.6  251.48  5362.0  252.75  5476.5  253.36  5573.7  255.26  5785.5  255.69
#Mann=6,-1,0
  4115.4    0.03       0  4383.2    0.12       0  4804.9     0.1       0
  4972.1    0.05       0  4986.4     0.1       0  5106.5    0.04       0
Bank Sta=4972.1,4986.4
Exp/Cntr=0.3,0.1

Type RM Length L Ch R = 1,10876,393,393,393
BEGIN DESCRIPTION:
Mapping XS dcf5696c
END DESCRIPTION:
XS GIS Cut Line= 4
      2462489.85     13539575.37      2462719.89     13538989.42
      2462528.92     13538381.78      2461788.33     13538156.58
#Sta/Elev= 30
  4004.2  259.36  4176.5  256.61  4196.7  254.97  4392.2  250.31  4616.0  248.01
  4652.0  247.92  4709.9  247.72  4838.1  245.86  4879.4  246.65  4952.8  246.17
  4962.4  243.68  4967.7  237.68  4973.8  234.31  4984.2  234.53  4992.9  232.75
  4993.4  232.25  5007.2  232.75  5026.2  238.08  5037.7  239.76  5064.9  241.95
  5070.1  243.54  5089.1  243.28  5119.3  245.90  5134.9  247.70  5172.9  248.82
  5415.0  251.16  5622.7  254.92  5797.4  254.26  5922.8  255.70  6044.7  254.58
#Mann=8,-1,0
  4004.2    0.03       0  4196.7    0.12       0  4616.0    0.05       0
  4652.0    0.12       0  4709.9     0.1       0  4992.9    0.05       0
  5007.2     0.1       0  5119.3    0.04       0
Bank Sta=4992.9,5007.2
Exp/Cntr=0.3,0.1

Type RM Length L Ch R = 1,10483,254,254,254
BEGIN DESCRIPTION:
Mapping XS 0ba5bd18
END DESCRIPTION:
XS GIS Cut Line= 3
      2463735.54     13538789.78      2463188.64     13538416.51
      2461812.77     13538095.32
#Sta/Elev= 30
  3956.9  259.31  4228.9  253.84  4232.0  253.79  4346.0  252.03  4429.6  251.84
  4500.0  249.90  4685.4  247.62  4780.8  246.41  4807.6  243.71  4848.7  242.70
  4867.3  243.64  4889.8  244.57  4920.6  241.53  4971.9  238.43  4982.2  236.47
  4990.1  230.74  4990.6  230.24  5007.0  230.74  5013.0  233.74  5033.5  233.84
  5041.1  236.69  5046.2  236.22  5086.7  244.47  5105.4  246.13  5146.5  247.38
  5444.4  250.18  5608.6  254.02  5795.0  253.37  5978.3  254.78  6031.9  254.24
#Mann=10,-1,0
  3956.9    0.05       0  4228.9    0.12       0  4232.0    0.05       0
  4346.0    0.12       0  4500.0    0.05       0  4685.4     0.1       0
  4867.3    0.12       0  4990.1    0.05       0  5007.0    0.12       0
  5086.7    0.04       0
Bank Sta=4990.1,5007
Exp/Cntr=0.3,0.1

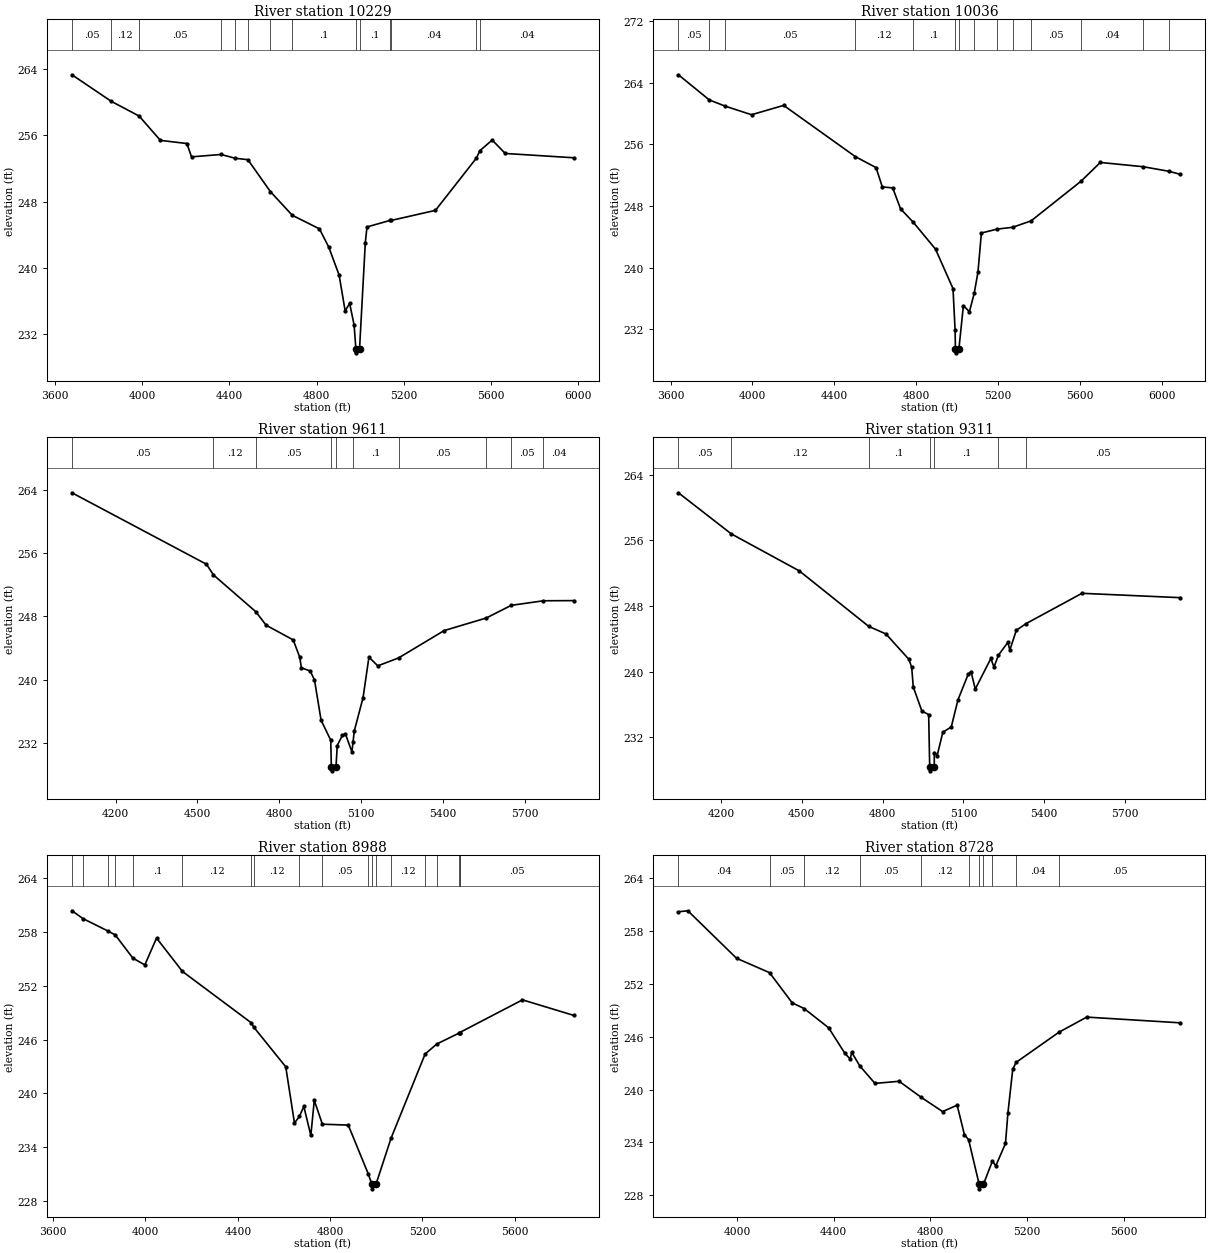
Type RM Length L Ch R = 1,10229,193,193,193
BEGIN DESCRIPTION:
Mapping XS 8abaefea
END DESCRIPTION:
XS GIS Cut Line= 4
      2463956.87     13538702.97      2463314.51     13538190.81
      2462381.35     13537973.80      2461860.55     13537973.80
#Sta/Elev= 30
  3679.1  263.33  3859.0  260.13  3986.8  258.35  4084.6  255.41  4205.9  255.03
  4227.1  253.42  4362.5  253.71  4427.3  253.25  4485.4  253.08  4588.5  249.23
  4688.8  246.37  4813.3  244.73  4855.9  242.54  4903.6  239.15  4931.3  234.82
  4951.9  235.73  4972.4  233.11  4980.4  230.26  4980.9  229.76  4997.3  230.26
  5023.7  243.08  5031.4  244.96  5138.9  245.76  5141.5  245.74  5345.1  246.96
  5533.1  253.28  5548.6  254.16  5605.1  255.45  5665.1  253.83  5979.5  253.31
#Mann=14,-1,0
  3679.1    0.05       0  3859.0    0.12       0  3986.8    0.05       0
  4362.5    0.12       0  4427.3    0.05       0  4485.4    0.12       0
  4588.5    0.05       0  4688.8     0.1       0  4980.4    0.04       0
  4997.3     0.1       0  5138.9     0.1       0  5141.5    0.04       0
  5533.1    0.05       0  5548.6    0.04       0
Bank Sta=4980.4,4997.3
Exp/Cntr=0.3,0.1

Type RM Length L Ch R = 1,10036,425,425,425
BEGIN DESCRIPTION:
Mapping XS 7bb7e095
END DESCRIPTION:
XS GIS Cut Line= 4
      2464113.14     13538507.67      2463479.44     13538021.54
      2462398.71     13537826.23      2461843.19     13537839.25
#Sta/Elev= 30
  3638.2  265.01  3789.2  261.75  3865.9  260.95  3995.4  259.83  4152.6  261.04
  4502.6  254.40  4604.0  252.97  4634.5  250.47  4685.3  250.34  4723.8  247.62
  4785.3  245.90  4894.5  242.40  4980.0  237.28  4990.1  231.97  4991.9  229.45
  4992.4  228.95  5008.8  229.45  5030.8  235.08  5060.1  234.28  5083.5  236.65
  5101.9  239.40  5118.7  244.49  5196.5  245.00  5271.2  245.23  5361.9  246.07
  5605.2  251.20  5700.0  253.64  5908.7  253.09  6033.7  252.50  6090.8  252.10
#Mann=14,-1,0
  3638.2    0.05       0  3789.2    0.12       0  3865.9    0.05       0
  4502.6    0.12       0  4785.3     0.1       0  4991.9    0.05       0
  5008.8     0.1       0  5083.5    0.04       0  5196.5     0.1       0
  5271.2    0.04       0  5361.9    0.05       0  5605.2    0.04       0
  5908.7    0.05       0  6033.7    0.04       0
Bank Sta=4991.9,5008.8
Exp/Cntr=0.3,0.1

Type RM Length L Ch R = 1,9611,300,300,300
BEGIN DESCRIPTION:
Mapping XS fc7b6ebc
END DESCRIPTION:
XS GIS Cut Line= 4
      2463952.57     13537991.18      2463370.93     13537722.06
      2462698.19     13537452.96      2462225.14     13537492.02
#Sta/Elev= 30
  4040.3  263.68  4533.5  254.62  4559.0  253.27  4714.1  248.61  4752.2  246.89
  4851.4  245.03  4875.6  242.82  4881.4  241.49  4913.7  241.09  4929.5  239.95
  4953.7  234.85  4989.1  232.31  4991.4  228.93  4991.9  228.43  5008.4  228.93
  5012.9  231.64  5031.8  232.93  5043.0  233.11  5066.8  230.82  5070.8  232.07
  5075.3  233.47  5107.6  237.71  5129.1  242.84  5161.5  241.74  5237.7  242.74
  5404.8  246.21  5559.8  247.81  5650.8  249.41  5769.0  249.99  5880.4  250.01
#Mann=10,-1,0
  4040.3    0.05       0  4559.0    0.12       0  4714.1    0.05       0
  4991.4    0.05       0  5008.4    0.05       0  5070.8     0.1       0
  5237.7    0.05       0  5559.8    0.12       0  5650.8    0.05       0
  5769.0    0.04       0
Bank Sta=4991.4,5008.4
Exp/Cntr=0.3,0.1

Type RM Length L Ch R = 1,9311,323,323,323
BEGIN DESCRIPTION:
Mapping XS 8ed2acd0
END DESCRIPTION:
XS GIS Cut Line= 4
      2464021.98     13537813.21      2463609.65     13537522.41
      2462824.06     13537270.67      2462290.22     13537240.29
#Sta/Elev= 30
  4041.5  261.79  4237.5  256.79  4490.6  252.27  4748.3  245.51  4812.2  244.59
  4897.5  241.50  4908.0  240.52  4913.8  238.13  4946.0  235.18  4971.0  234.77
  4974.8  228.41  4975.3  227.91  4991.8  228.41  4992.0  230.14  5002.5  229.76
  5023.5  232.61  5055.0  233.26  5079.8  236.56  5118.0  239.69  5128.5  239.99
  5144.0  237.87  5202.0  241.60  5213.6  240.55  5230.0  242.00  5265.0  243.56
  5272.6  242.63  5296.5  245.03  5332.3  245.84  5540.3  249.54  5905.7  249.01
#Mann=7,-1,0
  4041.5    0.05       0  4237.5    0.12       0  4748.3     0.1       0
  4974.8    0.05       0  4991.8     0.1       0  5230.0    0.12       0
  5332.3    0.05       0
Bank Sta=4974.8,4991.8
Exp/Cntr=0.3,0.1

Type RM Length L Ch R = 1,8988,260,260,260
BEGIN DESCRIPTION:
Mapping XS 2307910b
END DESCRIPTION:
XS GIS Cut Line= 4
      2464473.40     13537457.32      2463913.47     13537188.21
      2462971.63     13537036.30      2462372.64     13537053.66
#Sta/Elev= 30
  3681.4  260.38  3729.7  259.50  3837.4  258.12  3869.1  257.68  3945.0  255.10
  3997.1  254.33  4047.9  257.33  4160.3  253.60  4459.2  247.85  4468.9  247.39
  4607.7  242.95  4645.5  236.66  4667.2  237.43  4686.0  238.52  4716.4  235.28
  4731.3  239.20  4766.4  236.54  4878.5  236.44  4964.7  231.02  4981.2  229.82
  4981.7  229.32  4998.5  229.82  5063.8  234.97  5211.5  244.38  5262.1  245.50
  5359.7  246.73  5360.5  246.76  5360.7  246.77  5633.4  250.43  5855.9  248.69
#Mann=19,-1,0
  3681.4    0.05       0  3729.7    0.12       0  3837.4     0.1       0
  3869.1    0.05       0  3945.0     0.1       0  4160.3    0.12       0
  4459.2    0.05       0  4468.9    0.12       0  4667.2     0.1       0
  4766.4    0.05       0  4964.7    0.04       0  4981.2    0.04       0
  4998.5    0.04       0  5063.8    0.12       0  5211.5    0.05       0
  5262.1    0.04       0  5359.7    0.05       0  5360.5    0.12       0
  5360.7    0.05       0
Bank Sta=4981.2,4998.5
Exp/Cntr=0.3,0.1

Type RM Length L Ch R = 1,8728,292,292,292
BEGIN DESCRIPTION:
Mapping XS 27381033
END DESCRIPTION:
XS GIS Cut Line= 4
      2464386.56     13537166.51      2463687.77     13536819.28
      2462824.06     13536814.94      2462394.33     13536862.69
#Sta/Elev= 30
  3757.4  260.17  3796.4  260.28  3998.0  254.89  4134.4  253.26  4228.1  249.84
  4277.6  249.19  4378.8  247.01  4446.0  244.11  4468.4  243.45  4474.0  244.24
  4508.1  242.67  4570.5  240.70  4670.5  240.94  4761.4  239.13  4850.5  237.50
  4910.5  238.23  4940.5  234.90  4958.0  234.30  5001.8  229.24  5002.3  228.74
  5019.1  229.24  5056.3  231.88  5070.5  231.35  5110.5  233.89  5120.5  237.33
  5140.5  242.30  5154.7  243.09  5331.4  246.50  5446.5  248.22  5833.8  247.57
#Mann=11,-1,0
  3757.4    0.04       0  4134.4    0.05       0  4277.6    0.12       0
  4508.1    0.05       0  4761.4    0.12       0  4958.0    0.04       0
  5001.8    0.04       0  5019.1    0.04       0  5056.3    0.05       0
  5154.7    0.04       0  5331.4    0.05       0
Bank Sta=5001.8,5019.1
Exp/Cntr=0.3,0.1

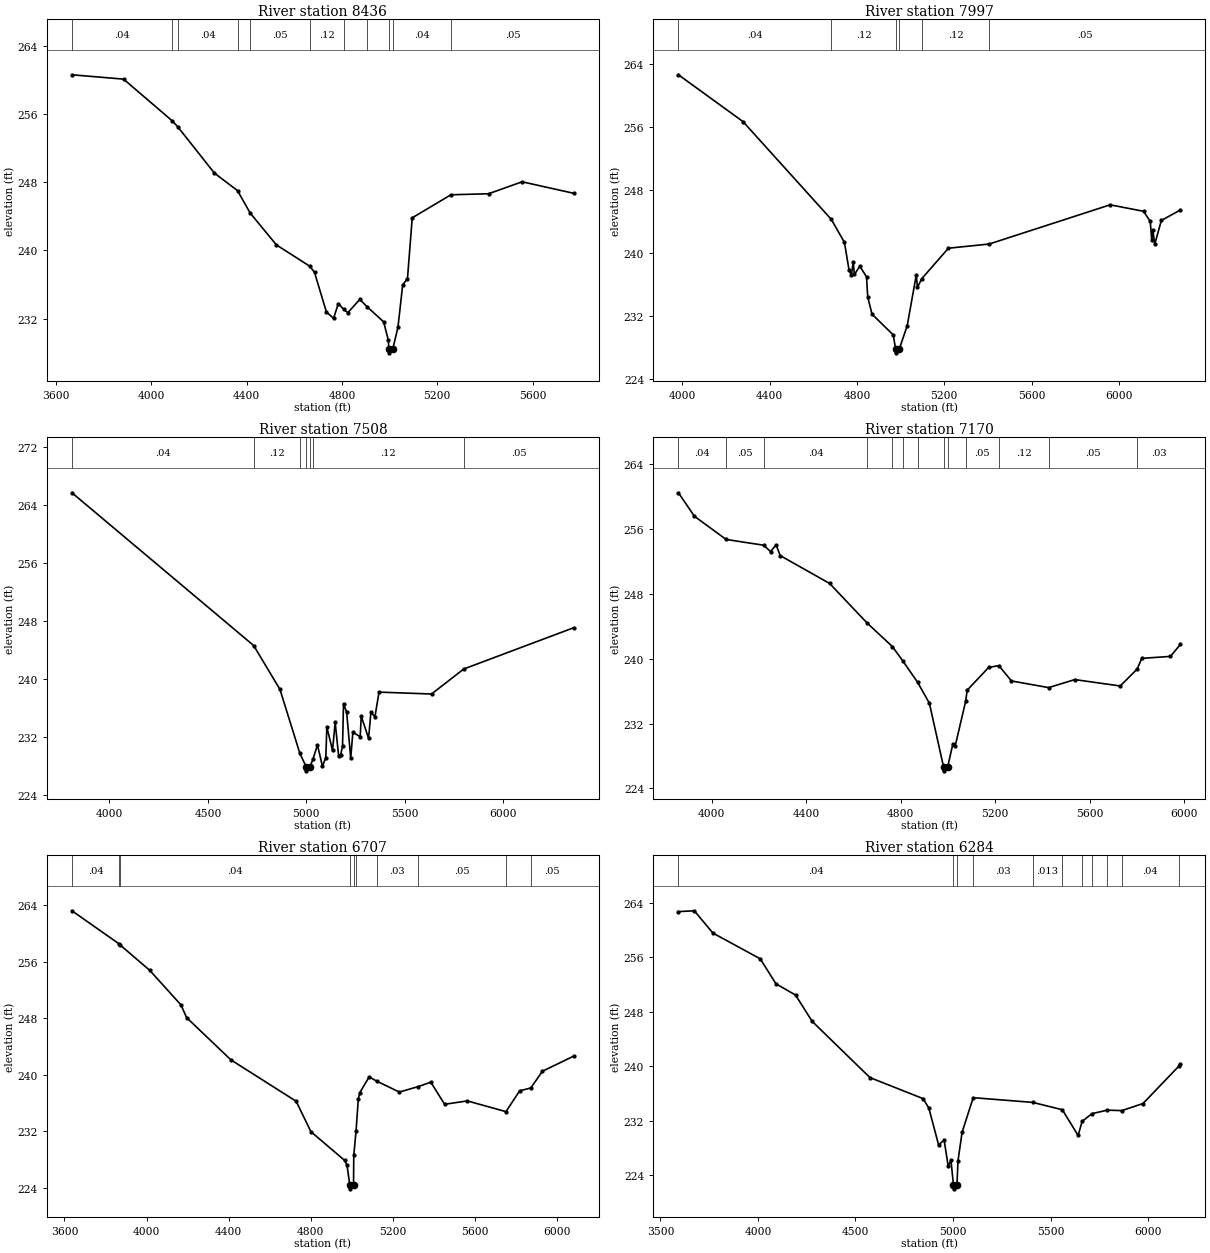
Type RM Length L Ch R = 1,8436,439,439,439
BEGIN DESCRIPTION:
Mapping XS 56bbb4fb
END DESCRIPTION:
XS GIS Cut Line= 4
      2464495.09     13536723.80      2463922.15     13536580.57
      2462832.74     13536571.89      2462408.74     13536610.83
#Sta/Elev= 30
  3667.4  260.58  3884.0  260.07  4089.1  255.16  4111.2  254.49  4265.1  249.06
  4362.0  247.01  4415.4  244.37  4525.1  240.65  4665.7  238.14  4685.1  237.43
  4735.1  232.78  4765.1  232.04  4785.1  233.78  4807.5  233.09  4825.1  232.71
  4875.1  234.26  4905.8  233.40  4975.1  231.63  4995.1  229.45  4996.5  228.50
  4997.0  228.00  5013.8  228.50  5035.1  230.98  5055.1  235.97  5075.1  236.69
  5095.1  243.82  5257.5  246.52  5415.4  246.64  5556.0  248.04  5773.2  246.69
#Mann=11,-1,0
  3667.4    0.04       0  4089.1    0.12       0  4111.2    0.04       0
  4362.0    0.12       0  4415.4    0.05       0  4665.7    0.12       0
  4807.5    0.05       0  4905.8    0.04       0  4996.5    0.04       0
  5013.8    0.04       0  5257.5    0.05       0
Bank Sta=4996.5,5013.8
Exp/Cntr=0.3,0.1

Type RM Length L Ch R = 1,7997,489,489,489
BEGIN DESCRIPTION:
Mapping XS ee367a84
END DESCRIPTION:
XS GIS Cut Line= 4
      2464438.61     13536597.92      2463900.45     13536433.00
      2463179.96     13536168.24      2462229.76     13536354.81
#Sta/Elev= 30
  3982.6  262.59  4278.3  256.66  4682.9  244.26  4743.0  241.35  4764.3  237.82
  4775.0  237.23  4783.2  238.86  4788.5  237.28  4813.7  238.32  4844.2  236.98
  4849.6  234.43  4869.3  232.26  4966.8  229.61  4977.2  227.85  4977.7  227.35
  4994.6  227.85  5030.7  230.81  5072.0  237.22  5077.3  235.65  5097.6  236.76
  5219.1  240.61  5406.0  241.14  5960.1  246.11  6113.0  245.29  6143.6  244.01
  6150.7  241.64  6155.7  242.86  6164.0  241.09  6194.5  244.13  6281.4  245.45
#Mann=6,-1,0
  3982.6    0.04       0  4682.9    0.12       0  4977.2    0.05       0
  4994.6    0.12       0  5097.6    0.12       0  5406.0    0.05       0
Bank Sta=4977.2,4994.6
Exp/Cntr=0.3,0.1

Type RM Length L Ch R = 1,7508,338,338,338
BEGIN DESCRIPTION:
Mapping XS d429b5d9
END DESCRIPTION:
XS GIS Cut Line= 4
      2464529.76     13536437.32      2463874.40     13535925.19
      2462949.92     13535708.17      2462199.50     13535877.34
#Sta/Elev= 30
  3809.2  265.64  4732.6  244.57  4866.3  238.51  4967.3  229.70  5000.5  227.78
  5001.0  227.28  5018.2  227.78  5033.6  228.87  5056.9  230.84  5082.0  227.92
  5099.3  229.09  5104.4  233.33  5133.4  230.10  5146.9  233.95  5164.2  229.39
  5174.5  229.52  5184.2  230.64  5189.3  236.55  5205.3  235.34  5225.8  229.02
  5236.8  232.60  5274.1  231.98  5279.3  234.82  5316.6  231.77  5328.5  235.34
  5349.1  234.75  5369.6  238.14  5636.6  237.88  5800.3  241.33  6359.8  247.03
#Mann=7,-1,0
  3809.2    0.04       0  4732.6    0.12       0  4967.3    0.05       0
  5000.5    0.05       0  5018.2    0.05       0  5033.6    0.12       0
  5800.3    0.05       0
Bank Sta=5000.5,5018.2
Exp/Cntr=0.3,0.1

Type RM Length L Ch R = 1,7170,463,463,463
BEGIN DESCRIPTION:
Mapping XS 32eb3312
END DESCRIPTION:
XS GIS Cut Line= 3
      2464616.62     13535981.62      2463631.35     13535530.22
      2462603.85     13535369.81
#Sta/Elev= 30
  3859.2  260.47  3927.0  257.57  4061.1  254.71  4219.9  254.00  4249.3  253.21
  4272.4  254.05  4289.9  252.72  4499.0  249.28  4657.6  244.40  4764.4  241.50
  4809.2  239.70  4871.2  237.09  4921.0  234.51  4981.0  226.66  4981.5  226.16
  4998.7  226.66  5020.2  229.45  5030.3  229.22  5074.5  234.74  5081.0  236.11
  5172.0  238.92  5215.1  239.14  5268.4  237.25  5425.8  236.43  5536.4  237.42
  5728.7  236.63  5800.6  238.73  5819.8  240.04  5941.2  240.28  5982.9  241.75
#Mann=13,-1,0
  3859.2    0.04       0  4061.1    0.05       0  4219.9    0.04       0
  4657.6    0.05       0  4764.4    0.04       0  4809.2    0.05       0
  4871.2     0.1       0  4981.0    0.05       0  4998.7     0.1       0
  5074.5    0.05       0  5215.1    0.12       0  5425.8    0.05       0
  5800.6    0.03       0
Bank Sta=4981,4998.7
Exp/Cntr=0.3,0.1

Type RM Length L Ch R = 1,6707,423,423,423
BEGIN DESCRIPTION:
Mapping XS 08fac940
END DESCRIPTION:
XS GIS Cut Line= 3
      2464768.49     13535838.37      2463757.22     13535161.30
      2462646.14     13534631.80
#Sta/Elev= 30
  3636.4  263.20  3866.5  258.51  3870.9  258.37  4015.3  254.78  4168.4  249.86
  4195.4  248.08  4411.6  242.09  4729.8  236.23  4801.9  231.92  4966.6  227.85
  4978.0  227.14  4991.8  224.33  4992.3  223.83  5009.6  224.33  5010.9  228.57
  5021.9  231.99  5033.1  236.58  5040.5  237.46  5085.9  239.68  5122.2  239.09
  5233.2  237.53  5324.3  238.30  5386.5  238.93  5454.0  235.80  5564.8  236.28
  5753.1  234.76  5819.6  237.70  5874.5  238.12  5930.8  240.48  6084.2  242.63
#Mann=10,-1,0
  3636.4    0.04       0  3866.5    0.05       0  3870.9    0.04       0
  4991.8    0.04       0  5009.6    0.04       0  5021.9    0.12       0
  5122.2    0.03       0  5324.3    0.05       0  5753.1   0.013       0
  5874.5    0.05       0
Bank Sta=4991.8,5009.6
Exp/Cntr=0.3,0.1

Type RM Length L Ch R = 1,6284,499,499,499
BEGIN DESCRIPTION:
Mapping XS 50758e61
END DESCRIPTION:
XS GIS Cut Line= 3
      2465080.99     13535673.44      2464000.27     13534935.60
      2463059.64     13534090.33
#Sta/Elev= 30
  3592.2  262.73  3673.7  262.85  3769.0  259.58  4011.7  255.80  4092.4  252.13
  4192.8  250.48  4277.9  246.62  4574.0  238.37  4846.6  235.28  4876.1  233.89
  4926.1  228.49  4954.5  229.20  4975.4  225.35  4989.6  226.24  5002.4  222.54
  5002.9  222.04  5020.2  222.54  5025.5  226.13  5046.4  230.32  5103.5  235.42
  5408.2  234.73  5560.5  233.65  5641.4  229.87  5662.2  231.95  5712.8  233.08
  5791.1  233.59  5865.1  233.52  5974.0  234.56  6156.9  240.02  6165.4  240.38
#Mann=11,-1,0
  3592.2    0.04       0  5002.4    0.04       0  5020.2    0.04       0
  5103.5    0.03       0  5408.2   0.013       0  5560.5    0.05       0
  5662.2    0.12       0  5712.8    0.04       0  5791.1    0.12       0
  5865.1    0.04       0  6156.9    0.05       0
Bank Sta=5002.4,5020.2
Exp/Cntr=0.3,0.1

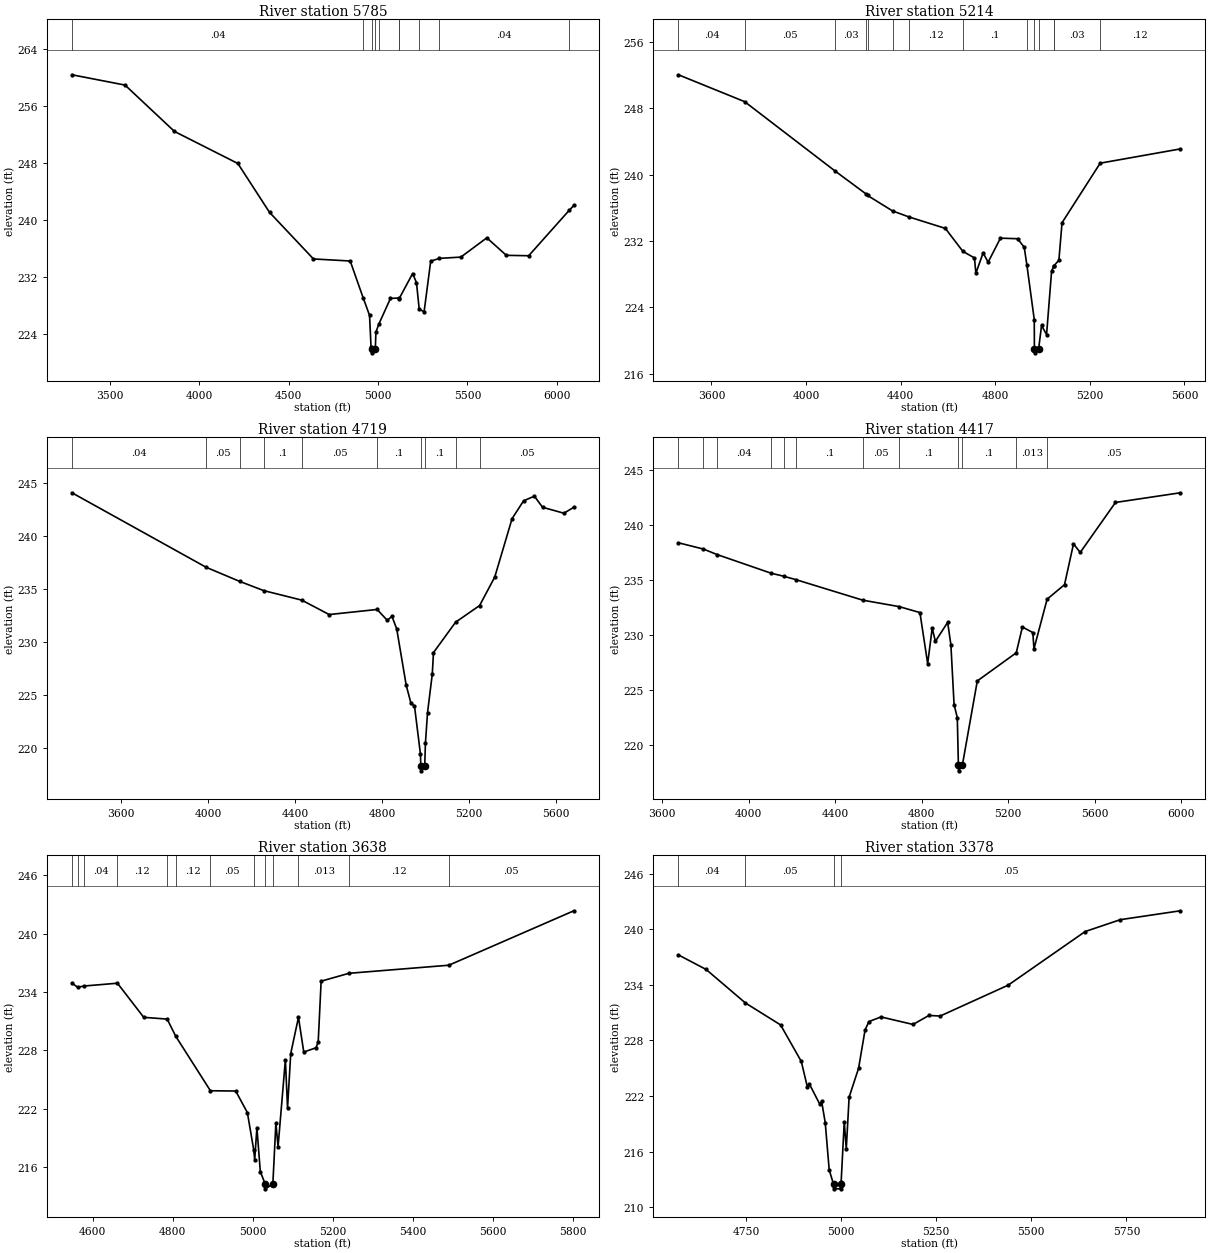
Type RM Length L Ch R = 1,5785,571,571,571
BEGIN DESCRIPTION:
Mapping XS b0ecf87d
END DESCRIPTION:
XS GIS Cut Line= 3
      2465458.61     13535530.23      2464603.57     13534761.99
      2463189.35     13533903.05
#Sta/Elev= 30
  3290.1  260.42  3586.8  258.97  3862.7  252.45  4217.0  247.94  4394.1  241.06
  4639.3  234.51  4844.7  234.22  4916.8  229.06  4952.7  226.58  4961.0  222.18
  4967.2  221.80  4967.7  221.30  4985.0  221.80  4988.2  224.19  5004.2  225.32
  5069.7  228.96  5116.1  229.01  5117.3  228.89  5193.6  232.46  5214.9  231.18
  5230.3  227.43  5257.6  227.08  5294.4  234.20  5343.4  234.59  5463.0  234.77
  5607.9  237.48  5716.9  235.02  5841.9  234.96  6067.5  241.33  6094.2  242.04
#Mann=10,-1,0
  3290.1    0.04       0  4916.8     0.1       0  4967.2    0.05       0
  4985.0     0.1       0  5004.2    0.03       0  5116.1   0.013       0
  5117.3    0.03       0  5230.3    0.12       0  5343.4    0.04       0
  6067.5    0.05       0
Bank Sta=4967.2,4985
Exp/Cntr=0.3,0.1

Type RM Length L Ch R = 1,5214,495,495,495
BEGIN DESCRIPTION:
Mapping XS 12cc238a
END DESCRIPTION:
XS GIS Cut Line= 3
      2465402.15     13534961.61      2464924.75     13534349.66
      2463779.49     13533642.55
#Sta/Elev= 30
  3460.4  252.05  3740.3  248.81  4123.9  240.42  4252.3  237.71  4260.0  237.50
  4365.9  235.63  4434.9  234.91  4588.8  233.53  4663.3  230.75  4712.0  229.97
  4718.1  228.12  4748.7  230.57  4769.9  229.45  4822.0  232.35  4894.4  232.28
  4922.5  231.25  4933.7  229.12  4965.0  222.52  4965.5  219.02  4966.0  218.52
  4983.5  219.02  4995.8  221.82  5017.0  220.73  5038.3  228.39  5046.9  228.95
  5047.3  228.98  5069.1  229.70  5082.4  234.21  5243.7  241.39  5582.5  243.11
#Mann=14,-1,0
  3460.4    0.04       0  3740.3    0.05       0  4123.9    0.03       0
  4252.3    0.05       0  4260.0    0.03       0  4365.9    0.05       0
  4434.9    0.12       0  4663.3     0.1       0  4933.7    0.03       0
  4965.5    0.03       0  4983.5    0.03       0  5046.9   0.013       0
  5047.3    0.03       0  5243.7    0.12       0
Bank Sta=4965.5,4983.5
Exp/Cntr=0.3,0.1

Type RM Length L Ch R = 1,4719,302,302,302
BEGIN DESCRIPTION:
Mapping XS d094d96a
END DESCRIPTION:
XS GIS Cut Line= 3
      2465679.97     13534696.90      2465193.85     13533928.66
      2463965.56     13533260.26
#Sta/Elev= 30
  3373.9  244.09  3991.2  237.05  4145.2  235.72  4255.7  234.85  4430.7  233.95
  4556.4  232.59  4776.9  233.07  4823.3  232.05  4845.2  232.42  4867.0  231.23
  4910.7  225.91  4932.6  224.20  4948.7  223.96  4976.2  219.39  4977.7  218.33
  4978.2  217.83  4995.8  218.33  4999.0  220.43  5008.6  223.32  5030.4  226.94
  5036.1  229.00  5137.8  231.87  5248.1  233.44  5317.7  236.13  5397.4  241.65
  5450.2  243.33  5499.9  243.77  5537.6  242.72  5635.5  242.16  5681.4  242.72
#Mann=10,-1,0
  3373.9    0.04       0  3991.2    0.05       0  4145.2    0.04       0
  4255.7     0.1       0  4430.7    0.05       0  4776.9     0.1       0
  4977.7    0.05       0  4995.8     0.1       0  5137.8   0.013       0
  5248.1    0.05       0
Bank Sta=4977.7,4995.8
Exp/Cntr=0.3,0.1

Type RM Length L Ch R = 1,4417,779,779,779
BEGIN DESCRIPTION:
Mapping XS ec461559
END DESCRIPTION:
XS GIS Cut Line= 4
      2465784.15     13534223.82      2465332.74     13533759.39
      2464542.81     13533208.17      2463858.51     13533021.94
#Sta/Elev= 30
  3675.7  238.39  3791.2  237.82  3854.3  237.32  4104.5  235.62  4163.6  235.34
  4219.9  235.03  4527.6  233.17  4696.6  232.58  4792.1  232.04  4827.9  227.40
  4848.8  230.62  4863.6  229.42  4920.3  231.15  4935.2  229.12  4950.0  223.66
  4964.8  222.49  4970.0  218.14  4970.5  217.64  4988.1  218.14  5057.3  225.82
  5237.4  228.38  5265.8  230.73  5314.0  230.22  5319.2  228.74  5380.1  233.26
  5460.5  234.58  5502.0  238.29  5533.1  237.51  5696.1  242.06  5995.8  242.94
#Mann=12,-1,0
  3675.7    0.04       0  3791.2    0.05       0  3854.3    0.04       0
  4104.5    0.05       0  4163.6    0.04       0  4219.9     0.1       0
  4527.6    0.05       0  4696.6     0.1       0  4970.0    0.05       0
  4988.1     0.1       0  5237.4   0.013       0  5380.1    0.05       0
Bank Sta=4970,4988.1
Exp/Cntr=0.3,0.1

Type RM Length L Ch R = 1,3638,260,260,260
BEGIN DESCRIPTION:
Mapping XS 457c634a
END DESCRIPTION:
XS GIS Cut Line= 4
      2465181.93     13532570.76      2465024.58     13532626.57
      2464469.02     13532860.95      2464004.65     13532995.49
#Sta/Elev= 30
  4548.0  234.92  4562.5  234.50  4577.7  234.63  4661.6  234.92  4727.3  231.41
  4785.8  231.23  4807.5  229.44  4893.8  223.86  4957.0  223.83  4986.1  221.61
  5001.8  217.81  5004.4  216.78  5009.9  220.06  5018.4  215.54  5030.6  214.27
  5031.1  213.77  5049.7  214.27  5057.3  220.55  5062.7  218.08  5081.0  227.04
  5086.4  222.09  5094.4  227.69  5113.7  231.41  5126.9  227.84  5157.6  228.28
  5163.0  228.91  5170.3  235.13  5240.0  235.94  5489.2  236.77  5801.4  242.37
#Mann=13,-1,0
  4548.0    0.04       0  4562.5    0.12       0  4577.7    0.04       0
  4661.6    0.12       0  4785.8   0.013       0  4807.5    0.12       0
  4893.8    0.05       0  5001.8   0.013       0  5030.6    0.05       0
  5049.7   0.013       0  5113.7   0.013       0  5240.0    0.12       0
  5489.2    0.05       0
Bank Sta=5030.6,5049.7
Exp/Cntr=0.3,0.1

Type RM Length L Ch R = 1,3378,405,405,405
BEGIN DESCRIPTION:
Mapping XS 28cab855
END DESCRIPTION:
XS GIS Cut Line= 4
      2465135.01     13532373.91      2464863.99     13532452.96
      2464560.17     13532548.45      2463970.48     13532960.36
#Sta/Elev= 30
  4571.7  237.22  4644.6  235.65  4747.8  232.04  4840.4  229.67  4894.9  225.73
  4910.7  223.00  4916.0  223.31  4943.1  221.15  4948.4  221.42  4957.8  219.14
  4968.3  214.03  4979.7  212.49  4980.2  211.99  4998.3  211.99  4998.8  212.49
  4999.7  212.72  5007.9  219.22  5013.2  216.29  5020.7  221.88  5045.6  225.00
  5062.6  229.12  5072.7  230.03  5104.5  230.53  5188.8  229.72  5230.6  230.69
  5260.3  230.63  5439.1  233.96  5641.5  239.74  5733.9  241.02  5891.8  241.98
#Mann=4,-1,0
  4571.7    0.04       0  4747.8    0.05       0  4979.7    0.05       0
  4998.8    0.05       0
Bank Sta=4979.7,4998.8
Exp/Cntr=0.3,0.1

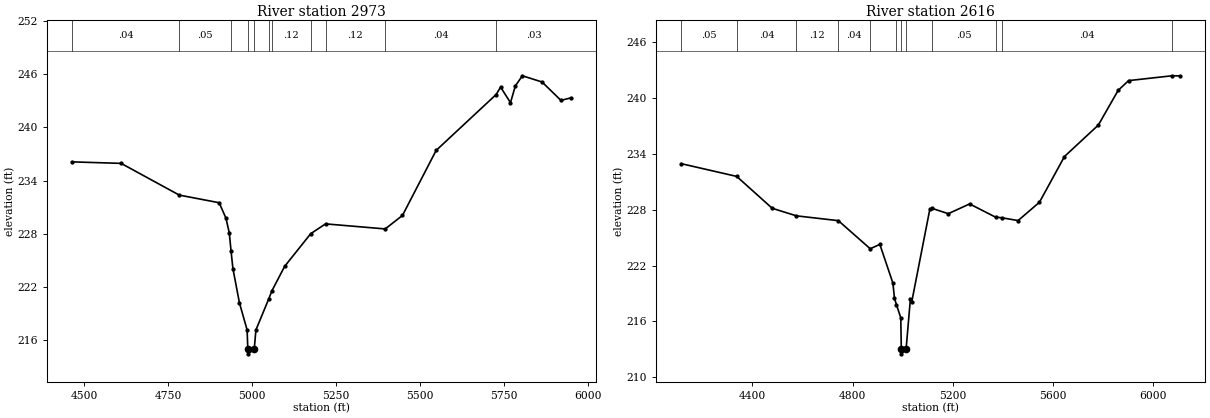
Type RM Length L Ch R = 1,2973,357,357,357
BEGIN DESCRIPTION:
Mapping XS d32df0a7
END DESCRIPTION:
XS GIS Cut Line= 3
      2465150.90     13532056.15      2464632.22     13532115.29
      2463856.14     13532688.23
#Sta/Elev= 30
  4462.7  236.10  4609.5  235.93  4782.6  232.36  4901.4  231.50  4921.6  229.77
  4931.6  228.10  4936.8  226.09  4942.4  224.09  4961.8  220.23  4984.7  217.18
  4986.8  214.99  4987.3  214.49  5005.9  214.99  5010.9  217.18  5049.3  220.69
  5058.6  221.59  5096.5  224.34  5174.2  228.02  5218.4  229.12  5395.9  228.55
  5447.3  230.07  5547.6  237.39  5726.2  243.68  5739.6  244.51  5768.9  242.76
  5783.5  244.66  5804.4  245.79  5862.9  245.09  5919.2  243.02  5949.4  243.31
#Mann=11,-1,0
  4462.7    0.04       0  4782.6    0.05       0  4936.8     0.1       0
  4986.8    0.05       0  5005.9     0.1       0  5049.3    0.05       0
  5058.6    0.12       0  5174.2    0.05       0  5218.4    0.12       0
  5395.9    0.04       0  5726.2    0.03       0
Bank Sta=4986.8,5005.9
Exp/Cntr=0.3,0.1

Type RM Length L Ch R = 1,2616,0,0,0
BEGIN DESCRIPTION:
Mapping XS 99fc32da
END DESCRIPTION:
XS GIS Cut Line= 4
      2465333.13     13531761.02      2464788.47     13531714.25
      2464283.26     13531880.91      2463731.20     13532610.04
#Sta/Elev= 30
  4115.4  232.97  4337.0  231.60  4478.9  228.17  4575.3  227.36  4742.9  226.84
  4870.1  223.82  4908.5  224.29  4960.6  220.13  4966.8  218.54  4974.6  217.81
  4992.1  216.40  4994.2  213.02  4994.7  212.52  5013.3  213.02  5030.3  218.37
  5035.5  218.06  5108.0  228.06  5118.5  228.15  5181.7  227.59  5266.9  228.64
  5370.3  227.22  5395.8  227.15  5460.4  226.85  5545.7  228.82  5645.6  233.74
  5780.8  237.12  5859.9  240.85  5901.6  241.90  6074.7  242.42  6108.6  242.41
#Mann=12,-1,0
  4115.4    0.05       0  4337.0    0.04       0  4575.3    0.12       0
  4742.9    0.04       0  4870.1    0.05       0  4974.6     0.1       0
  4994.2    0.05       0  5013.3     0.1       0  5118.5    0.05       0
  5370.3    0.12       0  5395.8    0.04       0  6074.7    0.03       0
Bank Sta=4994.2,5013.3
Exp/Cntr=0.3,0.1

Chan Stop Cuts=-1