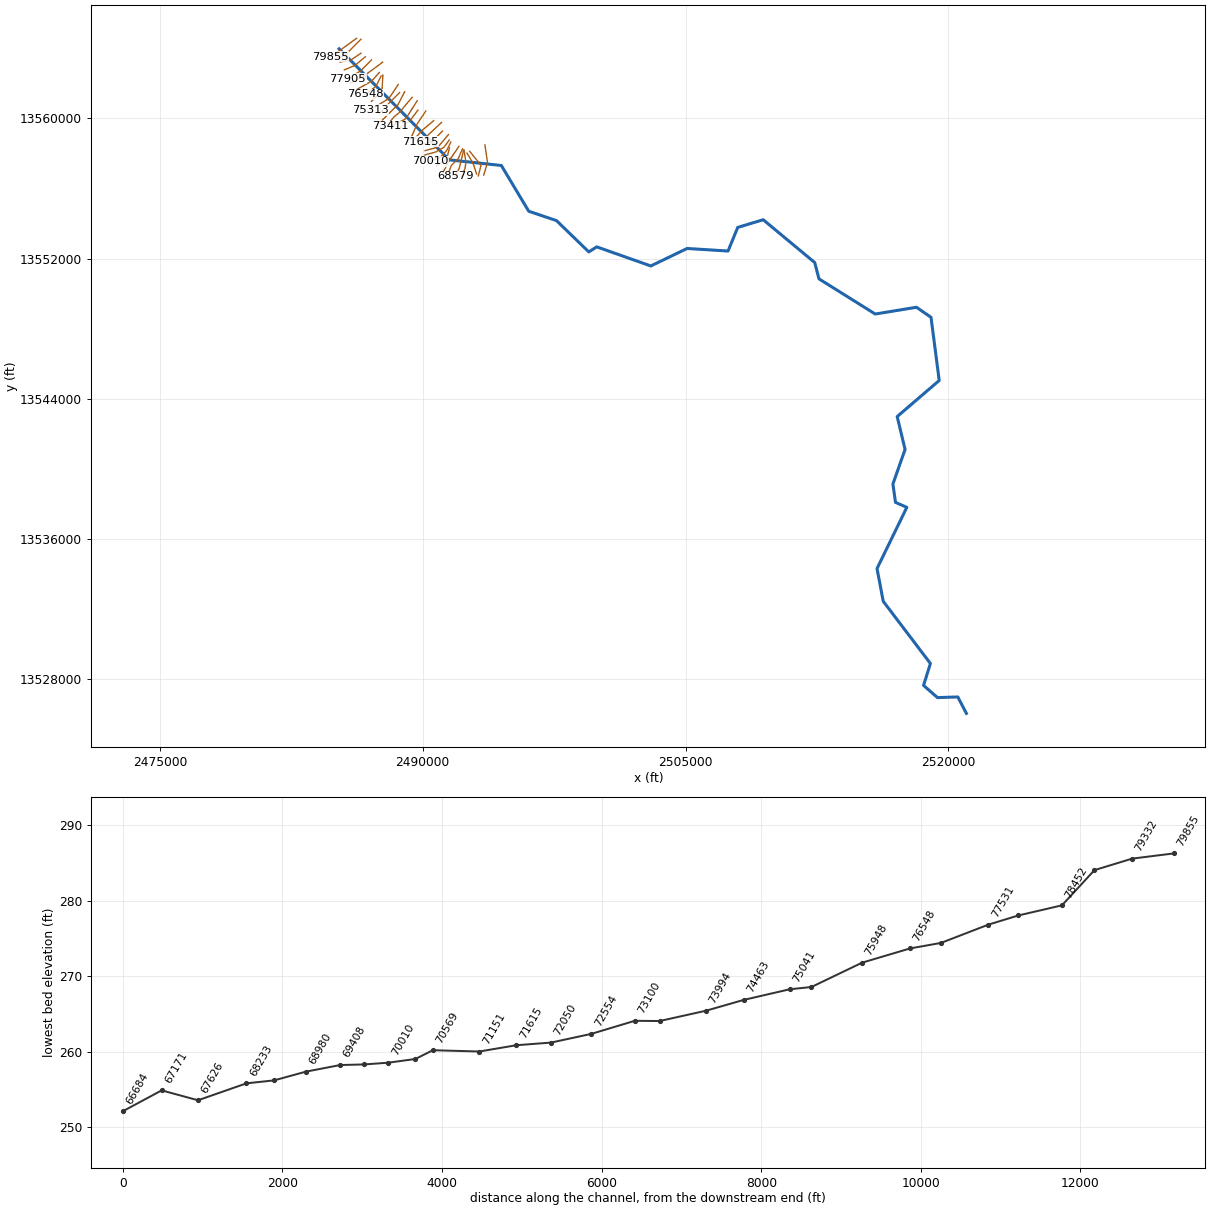
--- FIVEMILE CREEK.prj (project) ---

Proj Title=FIVEMILE CREEK Base Level Engineering
Current Plan=p01
Default Exp/Contr=0.3,0.1
English Units
Geom File=g01
Flow File=f01
Plan File=p01
Y Axis Title=Elevation
X Axis Title(PF)=Main Channel Distance
X Axis Title(XS)=Station
BEGIN DESCRIPTION:
FIVEMILE CREEK
END DESCRIPTION:
DSS Export Rating Curves= 0
DSS Export Rating Curve Sorted= 0
DSS Export Volume Flow Curves= 0
DXF OffsetX= 0
DXF OffsetY= 0
DXF ScaleX= 1
DXF ScaleY= 10

--- FIVEMILE CREEK.p01 (plan) ---

Plan Title=Multiple Run
Short Identifier=Multiple
Geom File=g01
Flow File=f01
Subcritical Flow
K Sum by GR= 0
Std Step Tol= 0.01
Critical Tol= 0.01
Num of Std Step Trials= 20
Max Error Tol= 0.3
Flow Tol Ratio= 0.001
Split Flow NTrial= 30
Split Flow Tol= 0.02
Split Flow Ratio= 0.02
Log Output Level= 0
Friction Slope Method= 1
Unsteady Friction Slope Method= 2
Unsteady Bridges Friction Slope Method= 1
Parabolic Critical Depth
Global Vel Dist=  1 , 1 , 1
Global Log Level= 0
CheckData=True
Encroach Param= -1, 0, 0, 0
BEGIN DESCRIPTION:
Multiple Run
END DESCRIPTION:

--- FIVEMILE CREEK.f01 (steady flow) ---

Flow Title=Multiple
Number of Profiles=7
Profile Names=10-year,25-year,50-year,1pct_min,100-year,1pct_plu,500-year
River Rch & RM= FIVEMILE CREEK,Reach-1,79855
     598     956    1276     825    1645    3283    2710
River Rch & RM= FIVEMILE CREEK,Reach-1,76936
     793    1289    1739    1136    2266    4521    3809
River Rch & RM= FIVEMILE CREEK,Reach-1,75948
     899    1466    1984    1298    2589    5167    4372
River Rch & RM= FIVEMILE CREEK,Reach-1,73411
    1023    1676    2273    1490    2973    5932    5039
River Rch & RM= FIVEMILE CREEK,Reach-1,70350
    1067    1748    2371    1553    3099    6184    5250
River Rch & RM= FIVEMILE CREEK,Reach-1,67171
    1246    2050    2788    1830    3651    7284    6206
River Rch & RM= FIVEMILE CREEK,Reach-1,61729
    2321    3932    5455    3645    7274   14513   12826
River Rch & RM= FIVEMILE CREEK,Reach-1,58992
    2826    4823    6722    4509    8996   17950   15962
River Rch & RM= FIVEMILE CREEK,Reach-1,57266
    2612    4441    6176    4136    8252   16465   14611
River Rch & RM= FIVEMILE CREEK,Reach-1,54062
    3016    5154    7189    4824    9625   19205   17095
River Rch & RM= FIVEMILE CREEK,Reach-1,53426
    2807    4783    6660    4465    8908   17775   15808
River Rch & RM= FIVEMILE CREEK,Reach-1,51014
    3183    5442    7592    5094   10165   20281   18052
River Rch & RM= FIVEMILE CREEK,Reach-1,50106
    3275    5603    7822    5252   10478   20907   18627
River Rch & RM= FIVEMILE CREEK,Reach-1,48630
    2947    5022    6993    4687    9351   18658   16584
River Rch & RM= FIVEMILE CREEK,Reach-1,44868
    3696    6340    8868    5967   11905   23754   21276
River Rch & RM= FIVEMILE CREEK,Reach-1,39964
    4178    7193   10083    6792   13552   27040   24252
River Rch & RM= FIVEMILE CREEK,Reach-1,39544
    4165    7159   10024    6744   13457   26850   24024
River Rch & RM= FIVEMILE CREEK,Reach-1,35975
    4215    7243   10140    6821   13610   27156   24288
River Rch & RM= FIVEMILE CREEK,Reach-1,35664
    4974    8556   11991    8072   16105   32135   28764
River Rch & RM= FIVEMILE CREEK,Reach-1,26679
    5130    8828   12375    8331   16623   33168   29697
River Rch & RM= FIVEMILE CREEK,Reach-1,22926
    5224    8989   12600    8482   16924   33768   30227
River Rch & RM= FIVEMILE CREEK,Reach-1,21135
    5385    9275   13009    8762   17483   34884   31260
River Rch & RM= FIVEMILE CREEK,Reach-1,18702
    5388    9274   13002    8754   17466   34849   31199
River Rch & RM= FIVEMILE CREEK,Reach-1,14892
    5724    9865   13842    9326   18608   37129   33288
River Rch & RM= FIVEMILE CREEK,Reach-1,9807
    5770    9944   13953    9400   18756   37423   33546
River Rch & RM= FIVEMILE CREEK,Reach-1,6922
    5847   10084   14156    9541   19037   37984   34080
River Rch & RM= FIVEMILE CREEK,Reach-1,1704
    7155   12408   17487   11829   23601   47091   42544
Boundary for River Rch & Prof#=FIVEMILE CREEK,Reach-1,1
Up Type=0
Dn Type=3
Dn Slope=0.005
Boundary for River Rch & Prof#=FIVEMILE CREEK,Reach-1,2
Up Type=0
Dn Type=3
Dn Slope=0.005
Boundary for River Rch & Prof#=FIVEMILE CREEK,Reach-1,3
Up Type=0
Dn Type=3
Dn Slope=0.005
Boundary for River Rch & Prof#=FIVEMILE CREEK,Reach-1,4
Up Type=0
Dn Type=3
Dn Slope=0.005
Boundary for River Rch & Prof#=FIVEMILE CREEK,Reach-1,5
Up Type=0
Dn Type=3
Dn Slope=0.005
Boundary for River Rch & Prof#=FIVEMILE CREEK,Reach-1,6
Up Type=0
Dn Type=3
Dn Slope=0.005
Boundary for River Rch & Prof#=FIVEMILE CREEK,Reach-1,7
Up Type=0
Dn Type=3
Dn Slope=0.005

--- FIVEMILE CREEK.g01 (geometry) ---

Geom Title=Existing Conditions

River Reach=FIVEMILE CREEK,Reach-1
Reach XY= 30
      2485225.00     13563975.00      2491515.18     13557635.46
      2494485.00     13557313.76      2496051.47     13554697.86
      2497631.06     13554167.52      2499476.19     13552378.45
      2499928.30     13552666.92      2503015.41     13551576.21
      2505085.50     13552573.78      2507423.50     13552428.61
      2507975.00     13553775.00      2509428.41     13554217.19
      2512369.59     13551769.82      2512611.67     13550838.39
      2515822.57     13548830.52      2518175.10     13549217.67
      2519005.57     13548645.09      2519473.80     13545034.59
      2517075.00     13542975.00      2517525.38     13541097.72
      2516832.28     13539124.91      2516980.06     13538072.70
      2517625.13     13537790.42      2515925.07     13534295.03
      2516280.83     13532422.69      2518971.33     13528873.42
      2518580.45     13527622.54      2519375.00     13526925.00
      2520535.00     13526963.76      2521025.00     13526025.00

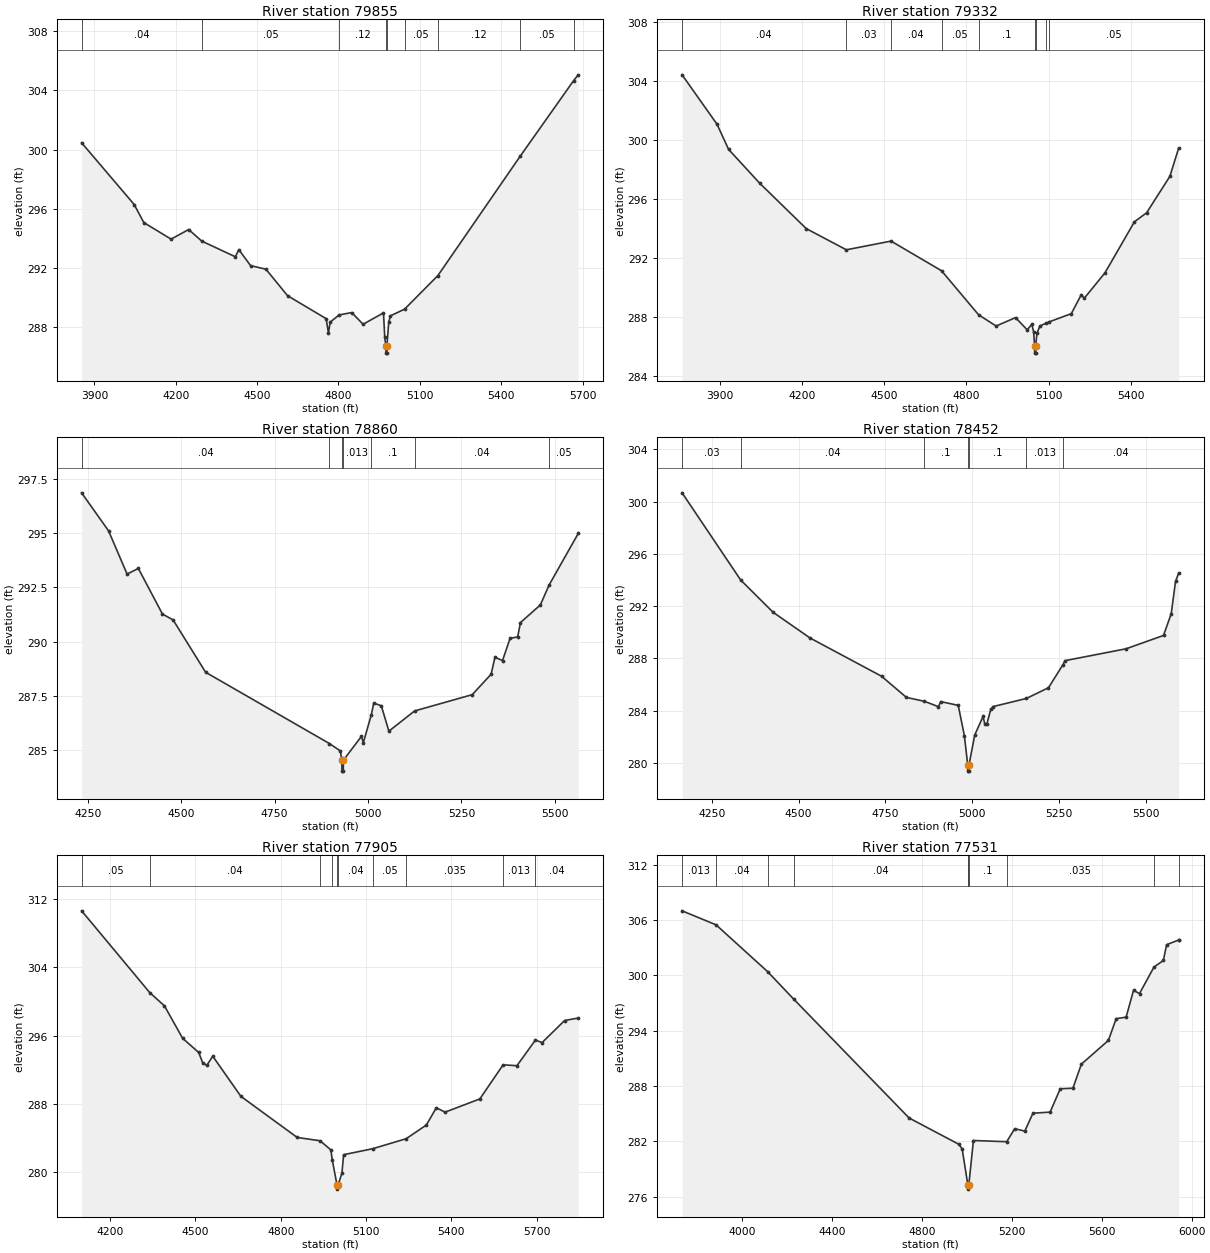
Type RM Length L Ch R = 1,79855,523,523,523
BEGIN DESCRIPTION:
FIVEMILE CREEK 134.0
END DESCRIPTION:
XS GIS Cut Line= 3
      2486224.97     13564574.98      2485325.00     13563925.00
      2484725.04     13563525.03
#Sta/Elev= 30
  3853.0  300.46  4046.8  296.29  4082.3  295.07  4182.9  293.95  4247.7  294.60
  4295.8  293.82  4419.7  292.76  4432.7  293.24  4476.1  292.16  4532.6  291.92
  4612.3  290.13  4754.6  288.58  4763.2  287.60  4769.3  288.34  4802.4  288.83
  4849.0  288.99  4890.8  288.20  4966.1  288.97  4970.6  287.36  4974.7  286.75
  4974.9  286.25  4978.4  286.25  4978.7  286.75  4985.7  288.38  4991.7  288.77
  5043.8  289.22  5166.7  291.49  5469.7  299.54  5666.8  304.65  5684.2  305.05
#Mann=9,-1,0
  3853.0    0.04       0  4295.8    0.05       0  4802.4    0.12       0
  4974.7    0.05       0  4978.7    0.12       0  5043.8    0.05       0
  5166.7    0.12       0  5469.7    0.05       0  5666.8    0.12       0
Bank Sta=4974.7,4978.7
Exp/Cntr=0.3,0.1

Type RM Length L Ch R = 1,79332,472,472,472
BEGIN DESCRIPTION:
FIVEMILE CREEK 133.0
END DESCRIPTION:
XS GIS Cut Line= 3
      2486475.01     13564525.01      2485575.00     13563625.00
      2485075.02     13563425.01
#Sta/Elev= 30
  3762.8  304.44  3890.1  301.09  3932.5  299.38  4045.7  297.09  4215.4  294.01
  4361.9  292.57  4524.9  293.16  4709.0  291.15  4844.2  288.16  4908.3  287.40
  4979.0  287.97  5021.5  287.14  5038.3  287.52  5045.0  287.00  5048.4  286.06
  5048.7  285.56  5052.2  285.56  5052.4  286.06  5057.1  286.91  5067.9  287.40
  5091.0  287.60  5101.4  287.68  5182.4  288.24  5218.7  289.52  5229.5  289.28
  5304.9  291.00  5412.6  294.47  5457.0  295.08  5541.8  297.55  5574.1  299.48
#Mann=9,-1,0
  3762.8    0.04       0  4361.9    0.03       0  4524.9    0.04       0
  4709.0    0.05       0  4844.2     0.1       0  5048.4    0.05       0
  5052.4     0.1       0  5091.0    0.04       0  5101.4    0.05       0
Bank Sta=5048.4,5052.4
Exp/Cntr=0.3,0.1

Type RM Length L Ch R = 1,78860,408,408,408
BEGIN DESCRIPTION:
FIVEMILE CREEK 132.0
END DESCRIPTION:
XS GIS Cut Line= 3
      2486475.03     13563725.02      2485875.00     13563325.00
      2485275.02     13563225.00
#Sta/Elev= 30
  4233.2  296.85  4305.3  295.10  4354.9  293.11  4385.0  293.37  4449.6  291.27
  4478.1  291.00  4565.2  288.59  4896.5  285.31  4925.8  284.97  4929.8  284.54
  4930.1  284.04  4933.6  284.04  4933.8  284.54  4982.2  285.64  4987.3  285.35
  5008.8  286.64  5015.2  287.17  5035.4  287.05  5055.7  285.88  5124.5  286.81
  5278.8  287.56  5329.4  288.50  5339.6  289.28  5359.9  289.13  5380.1  290.15
  5400.4  290.22  5408.0  290.88  5461.2  291.69  5484.7  292.61  5562.6  294.98
#Mann=7,-1,0
  4233.2    0.04       0  4896.5   0.013       0  4929.8    0.03       0
  4933.8   0.013       0  5008.8     0.1       0  5124.5    0.04       0
  5484.7    0.05       0
Bank Sta=4929.8,4933.8
Exp/Cntr=0.3,0.1

Type RM Length L Ch R = 1,78452,547,547,547
BEGIN DESCRIPTION:
FIVEMILE CREEK 131.0
END DESCRIPTION:
XS GIS Cut Line= 3
      2486725.01     13563525.01      2486125.00     13563025.00
      2485525.04     13562775.02
#Sta/Elev= 30
  4164.4  300.67  4333.2  294.00  4426.7  291.53  4533.4  289.56  4739.1  286.64
  4810.7  285.02  4862.7  284.72  4903.1  284.31  4909.6  284.70  4960.1  284.41
  4977.9  282.08  4987.3  279.88  4987.6  279.38  4991.1  279.38  4991.3  279.88
  5007.7  282.15  5031.6  283.56  5037.0  282.95  5042.9  283.02  5053.8  284.10
  5060.8  284.32  5156.5  284.94  5220.1  285.76  5261.8  287.52  5267.7  287.83
  5443.8  288.74  5551.6  289.76  5573.8  291.42  5586.2  293.89  5595.4  294.54
#Mann=7,-1,0
  4164.4    0.03       0  4333.2    0.04       0  4862.7     0.1       0
  4987.3    0.05       0  4991.3     0.1       0  5156.5   0.013       0
  5261.8    0.04       0
Bank Sta=4987.3,4991.3
Exp/Cntr=0.3,0.1

Type RM Length L Ch R = 1,77905,374,374,374
BEGIN DESCRIPTION:
Mapping XS 07b9b953
END DESCRIPTION:
XS GIS Cut Line= 3
      2487074.97     13563347.17      2486460.42     13562722.20
      2485720.83     13562263.86
#Sta/Elev= 30
  4099.7  310.62  4339.2  301.05  4391.1  299.49  4454.7  295.71  4511.3  294.04
  4525.4  292.85  4539.6  292.52  4560.9  293.60  4659.9  288.90  4857.9  284.09
  4938.6  283.70  4976.2  282.63  4981.4  281.43  4997.8  278.54  4998.0  278.04
  5001.8  278.54  5015.2  279.91  5021.1  282.07  5123.2  282.77  5240.9  283.94
  5312.0  285.54  5347.3  287.57  5377.9  287.05  5500.2  288.60  5582.0  292.59
  5630.7  292.49  5695.7  295.49  5719.3  295.20  5798.4  297.78  5846.3  298.07
#Mann=10,-1,0
  4099.7    0.05       0  4339.2    0.04       0  4938.6     0.1       0
  4981.4    0.04       0  4997.8    0.04       0  5001.8    0.04       0
  5123.2    0.05       0  5240.9   0.035       0  5582.0   0.013       0
  5695.7    0.04       0
Bank Sta=4997.8,5001.8
Exp/Cntr=0.3,0.1

Type RM Length L Ch R = 1,77531,595,595,595
BEGIN DESCRIPTION:
Mapping XS 83eeb145
END DESCRIPTION:
XS GIS Cut Line= 3
      2487710.44     13563211.80      2486658.34     13562435.74
      2485857.15     13562019.54
#Sta/Elev= 30
  3732.3  307.00  3883.5  305.48  4112.9  300.41  4228.5  297.44  4742.7  284.54
  4964.1  281.69  4978.7  281.19  5002.7  277.49  5004.5  277.33  5004.8  276.83
  5008.5  277.33  5028.8  282.10  5177.0  281.97  5212.5  283.38  5257.5  283.12
  5293.8  285.06  5370.2  285.18  5415.3  287.71  5471.6  287.77  5509.4  290.38
  5629.4  292.95  5664.2  295.31  5708.4  295.47  5741.4  298.38  5768.0  298.03
  5832.3  300.90  5874.1  301.62  5888.6  303.33  5941.6  303.83  5942.5  303.83
#Mann=10,-1,0
  3732.3   0.013       0  3883.5    0.04       0  4112.9    0.05       0
  4228.5    0.04       0  5002.7     0.1       0  5004.5    0.04       0
  5008.5     0.1       0  5177.0   0.035       0  5832.3   0.013       0
  5941.6    0.04       0
Bank Sta=5004.5,5008.5
Exp/Cntr=0.3,0.1

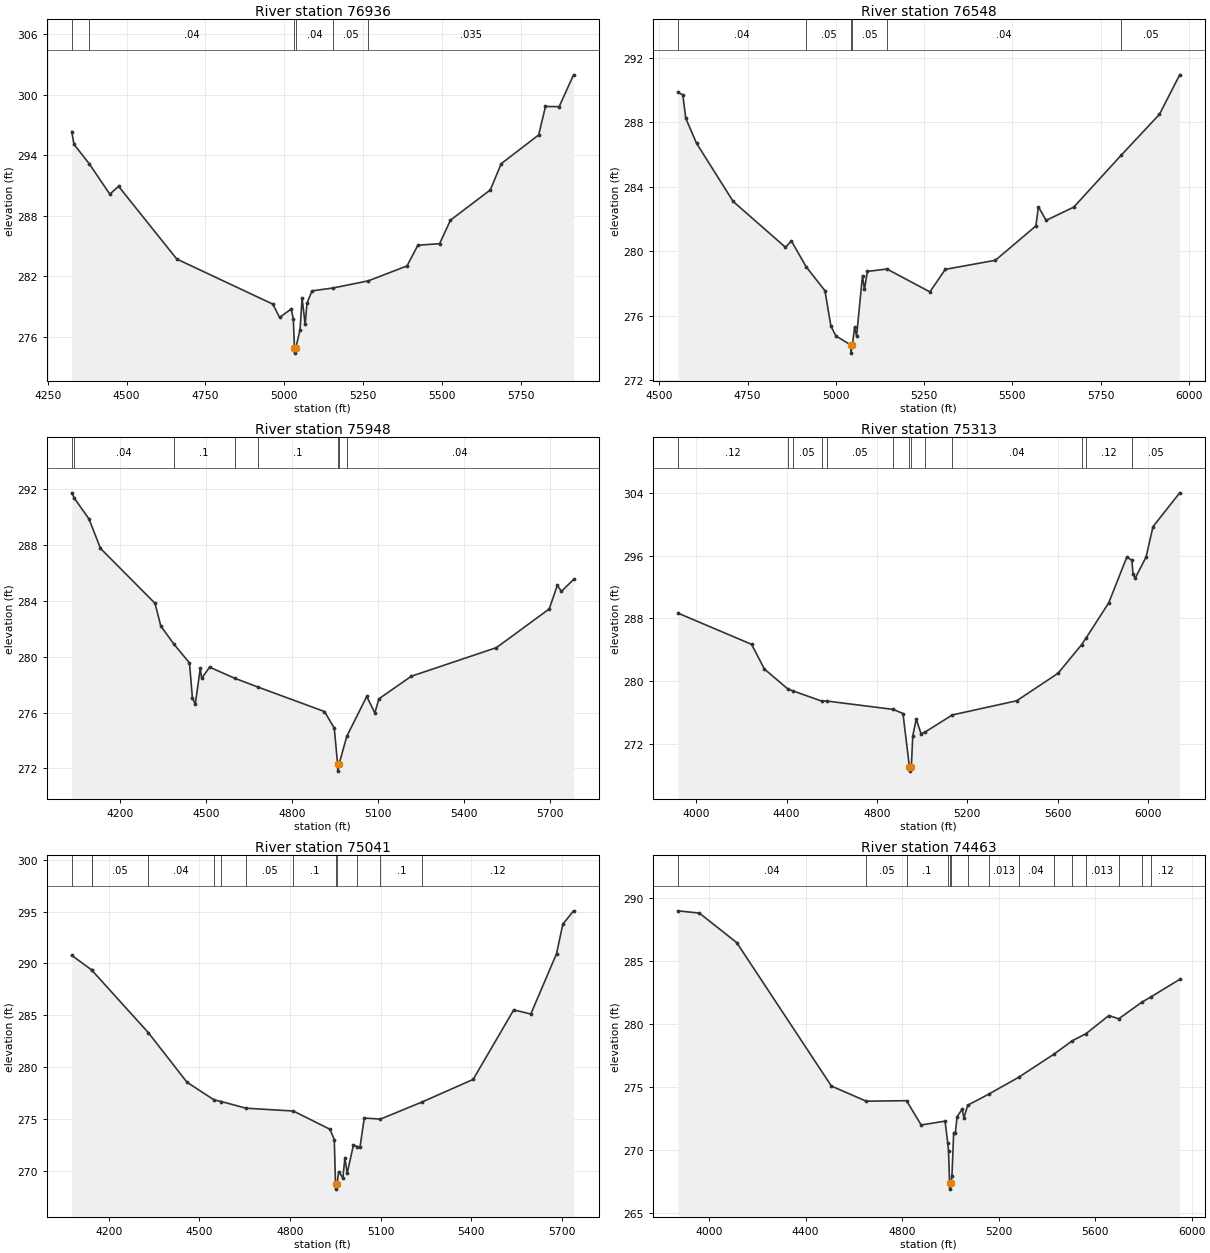
Type RM Length L Ch R = 1,76936,388,388,388
BEGIN DESCRIPTION:
FIVEMILE CREEK 128.0
END DESCRIPTION:
XS GIS Cut Line= 3
      2487525.01     13562625.01      2487075.00     13562125.00
      2486274.98     13561674.99
#Sta/Elev= 30
  4326.4  296.34  4333.5  295.07  4381.4  293.17  4447.1  290.14  4474.8  290.92
  4659.4  283.72  4963.6  279.26  4985.3  277.94  5022.0  278.78  5028.7  277.81
  5032.4  274.91  5032.7  274.41  5036.5  274.91  5050.1  276.74  5056.5  279.86
  5066.3  277.25  5072.1  279.35  5088.0  280.57  5155.1  280.86  5266.2  281.56
  5389.2  283.04  5423.6  285.09  5492.5  285.24  5526.9  287.57  5653.1  290.56
  5687.8  293.16  5806.4  296.00  5828.1  298.82  5871.4  298.80  5917.0  301.95
#Mann=6,-1,0
  4326.4    0.05       0  4381.4    0.04       0  5032.4    0.04       0
  5036.5    0.04       0  5155.1    0.05       0  5266.2   0.035       0
Bank Sta=5032.4,5036.5
Exp/Cntr=0.3,0.1

Type RM Length L Ch R = 1,76548,600,600,600
BEGIN DESCRIPTION:
FIVEMILE CREEK 127.0
END DESCRIPTION:
XS GIS Cut Line= 3
      2487624.99     13562424.97      2487325.00     13561825.00
      2486724.99     13561374.99
#Sta/Elev= 30
  4552.8  289.86  4566.7  289.71  4575.1  288.25  4605.9  286.69  4709.3  283.09
  4857.4  280.25  4874.2  280.64  4915.6  279.05  4969.2  277.55  4986.0  275.36
  5000.0  274.75  5042.7  274.18  5042.9  273.68  5046.8  274.18  5053.1  275.30
  5058.7  274.74  5075.5  278.49  5081.0  277.64  5089.4  278.75  5144.7  278.90
  5266.3  277.48  5310.0  278.88  5451.7  279.44  5566.3  281.57  5573.6  282.76
  5595.5  281.92  5673.6  282.74  5808.3  285.97  5916.3  288.50  5973.6  290.95
#Mann=6,-1,0
  4552.8    0.04       0  4915.6    0.05       0  5042.7    0.05       0
  5046.8    0.05       0  5144.7    0.04       0  5808.3    0.05       0
Bank Sta=5042.7,5046.8
Exp/Cntr=0.3,0.1

Type RM Length L Ch R = 1,75948,635,635,635
BEGIN DESCRIPTION:
FIVEMILE CREEK 126.0
END DESCRIPTION:
XS GIS Cut Line= 3
      2487725.00     13562475.01      2487675.00     13561575.00
      2487075.02     13560975.02
#Sta/Elev= 30
  4032.9  291.74  4041.7  291.36  4093.0  289.87  4133.1  287.76  4323.4  283.82
  4343.4  282.20  4388.0  280.93  4443.5  279.55  4453.6  277.06  4463.6  276.59
  4481.1  279.16  4486.1  278.45  4513.7  279.25  4600.5  278.46  4682.8  277.82
  4914.3  276.07  4948.4  274.88  4960.0  272.30  4960.4  271.80  4965.1  272.30
  4992.1  274.30  5061.6  277.15  5089.9  275.97  5104.0  276.98  5217.1  278.60
  5514.1  280.65  5698.0  283.42  5726.3  285.11  5740.4  284.68  5782.8  285.53
#Mann=8,-1,0
  4032.9    0.05       0  4041.7    0.04       0  4388.0     0.1       0
  4600.5    0.05       0  4682.8     0.1       0  4960.0    0.04       0
  4965.1     0.1       0  4992.1    0.04       0
Bank Sta=4960,4965.1
Exp/Cntr=0.3,0.1

Type RM Length L Ch R = 1,75313,272,272,272
BEGIN DESCRIPTION:
Mapping XS f7f86eb4
END DESCRIPTION:
XS GIS Cut Line= 4
      2488601.06     13561940.97      2488059.38     13561128.45
      2487783.34     13560966.99      2486998.42     13560478.37
#Sta/Elev= 30
  3919.2  288.68  4245.2  284.71  4302.3  281.56  4407.1  279.00  4427.0  278.80
  4555.5  277.49  4577.2  277.50  4872.1  276.43  4915.3  275.91  4944.1  269.08
  4944.5  268.58  4949.3  269.08  4952.5  269.18  4958.7  273.07  4974.0  275.18
  4995.5  273.33  5013.6  273.56  5134.1  275.73  5418.8  277.53  5601.8  281.03
  5705.9  284.66  5724.8  285.47  5826.1  289.99  5906.3  295.82  5928.6  295.40
  5933.4  293.65  5942.9  293.12  5991.3  295.81  6022.0  299.68  6140.1  303.98
#Mann=13,-1,0
  3919.2    0.12       0  4407.1    0.04       0  4427.0    0.05       0
  4555.5    0.04       0  4577.2    0.05       0  4872.1     0.1       0
  4944.1    0.05       0  4949.3     0.1       0  5013.6    0.05       0
  5134.1    0.04       0  5705.9    0.05       0  5724.8    0.12       0
  5928.6    0.05       0
Bank Sta=4944.1,4949.3
Exp/Cntr=0.3,0.1

Type RM Length L Ch R = 1,75041,578,578,578
BEGIN DESCRIPTION:
FIVEMILE CREEK 124.0
END DESCRIPTION:
XS GIS Cut Line= 3
      2488675.00     13561475.00      2488075.00     13560875.00
      2487524.98     13560274.98
#Sta/Elev= 30
  4076.8  290.78  4142.3  289.39  4142.6  289.38  4330.3  283.35  4458.6  278.57
  4548.3  276.87  4572.7  276.71  4653.8  276.07  4810.8  275.80  4932.4  274.04
  4946.6  273.05  4950.7  268.78  4951.1  268.28  4956.1  268.78  4960.8  269.97
  4975.0  269.36  4981.8  271.30  4989.2  269.80  5010.1  272.53  5023.0  272.38
  5031.7  272.29  5045.9  275.12  5099.6  275.02  5237.7  276.67  5406.6  278.84
  5541.0  285.53  5597.8  285.14  5682.9  290.94  5703.8  293.78  5739.3  295.07
#Mann=13,-1,0
  4076.8    0.05       0  4142.3   0.013       0  4142.6    0.05       0
  4330.3    0.04       0  4548.3    0.05       0  4572.7    0.04       0
  4653.8    0.05       0  4810.8     0.1       0  4950.7    0.05       0
  4956.1     0.1       0  5023.0    0.05       0  5099.6     0.1       0
  5237.7    0.12       0
Bank Sta=4950.7,4956.1
Exp/Cntr=0.3,0.1

Type RM Length L Ch R = 1,74463,469,469,469
BEGIN DESCRIPTION:
Mapping XS dec21703
END DESCRIPTION:
XS GIS Cut Line= 4
      2488970.84     13561529.50      2488575.01     13560769.07
      2488304.17     13560513.87      2487699.97     13559914.88
#Sta/Elev= 30
  3870.3  288.96  3959.3  288.78  4114.1  286.44  4506.7  275.05  4651.2  273.85
  4818.2  273.89  4878.8  271.96  4977.9  272.27  4989.1  270.51  4992.1  269.93
  4996.6  267.37  4997.0  266.87  5002.2  267.37  5006.3  267.91  5013.6  271.36
  5020.4  271.33  5027.7  272.62  5048.8  273.22  5056.0  272.52  5071.8  273.53
  5158.8  274.41  5283.2  275.75  5428.2  277.57  5504.9  278.64  5562.9  279.22
  5657.0  280.65  5697.6  280.39  5793.1  281.70  5832.3  282.14  5950.5  283.52
#Mann=15,-1,0
  3870.3    0.04       0  4651.2    0.05       0  4818.2     0.1       0
  4989.1   0.013       0  4996.6    0.03       0  5002.2   0.013       0
  5071.8    0.05       0  5158.8   0.013       0  5283.2    0.04       0
  5428.2   0.013       0  5504.9    0.04       0  5562.9   0.013       0
  5697.6    0.12       0  5793.1   0.013       0  5832.3    0.12       0
Bank Sta=4996.6,5002.2
Exp/Cntr=0.3,0.1

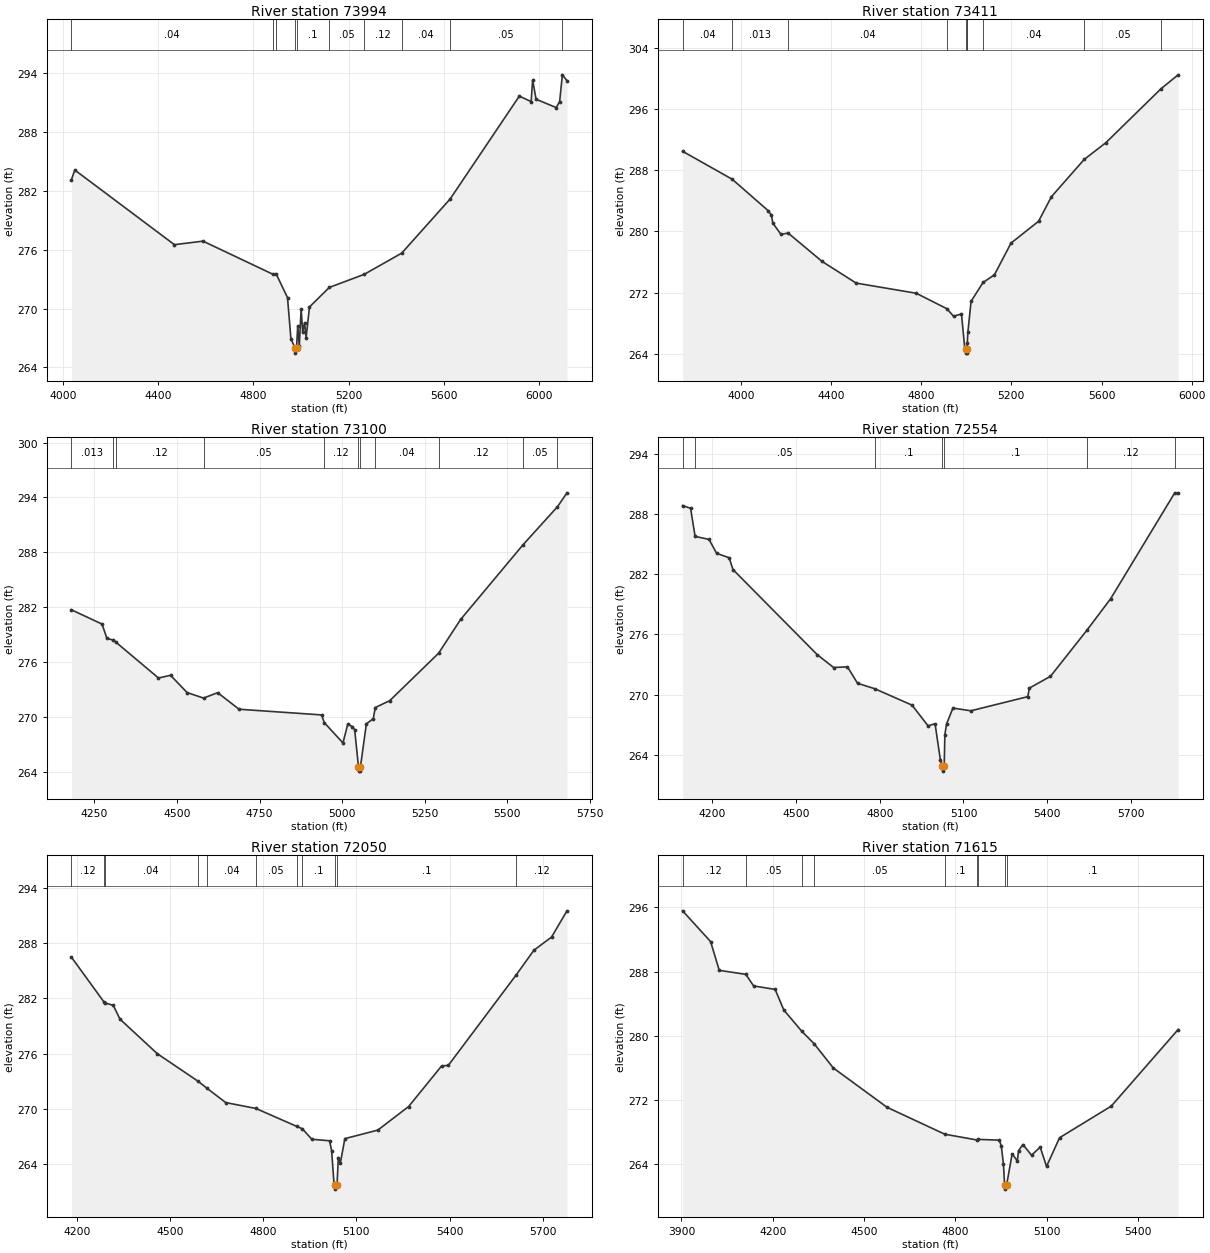
Type RM Length L Ch R = 1,73994,583,583,583
BEGIN DESCRIPTION:
Mapping XS 95dac7dc
END DESCRIPTION:
XS GIS Cut Line= 4
      2489392.74     13561206.61      2488663.55     13560336.78
      2488356.26     13560086.78      2488007.43     13559659.86
#Sta/Elev= 30
  4035.0  283.14  4049.2  284.12  4467.7  276.51  4587.9  276.87  4880.1  273.51
  4894.9  273.55  4943.0  271.11  4957.4  266.89  4975.4  265.95  4975.8  265.45
  4981.0  265.95  4986.0  268.23  4992.5  266.19  5000.3  269.93  5006.8  267.61
  5014.6  268.53  5021.1  267.01  5035.4  270.16  5118.7  272.15  5265.1  273.48
  5423.1  275.65  5626.5  281.17  5917.2  291.66  5966.8  291.10  5973.2  293.30
  5987.6  291.34  6072.3  290.49  6086.7  291.11  6098.1  293.83  6117.5  293.23
#Mann=10,-1,0
  4035.0    0.04       0  4880.1    0.05       0  4894.9     0.1       0
  4975.4    0.05       0  4981.0     0.1       0  5118.7    0.05       0
  5265.1    0.12       0  5423.1    0.04       0  5626.5    0.05       0
  6098.1    0.12       0
Bank Sta=4975.4,4981
Exp/Cntr=0.3,0.1

Type RM Length L Ch R = 1,73411,311,311,311
BEGIN DESCRIPTION:
Mapping XS 08553c8d
END DESCRIPTION:
XS GIS Cut Line= 4
      2489684.38     13561008.65      2489090.63     13560076.37
      2488965.63     13559940.95      2488149.05     13559540.46
#Sta/Elev= 30
  3741.0  290.48  3961.3  286.82  4120.1  282.73  4135.4  282.12  4141.3  281.09
  4177.7  279.61  4209.2  279.79  4359.7  276.08  4511.2  273.24  4777.9  271.91
  4913.1  269.90  4943.4  268.91  4978.7  269.20  4992.9  264.79  4996.6  264.58
  4997.1  264.08  5002.2  264.08  5002.7  264.58  5004.2  265.35  5007.0  266.80
  5021.2  270.86  5074.4  273.32  5124.8  274.32  5198.4  278.47  5320.9  281.33
  5377.8  284.54  5523.1  289.41  5619.6  291.61  5864.5  298.67  5940.1  300.48
#Mann=10,-1,0
  3741.0    0.04       0  3961.3   0.013       0  4209.2    0.04       0
  4913.1     0.1       0  4996.6    0.05       0  5002.7     0.1       0
  5004.2    0.12       0  5074.4    0.04       0  5523.1    0.05       0
  5864.5    0.12       0
Bank Sta=4996.6,5002.7
Exp/Cntr=0.3,0.1

Type RM Length L Ch R = 1,73100,546,546,546
BEGIN DESCRIPTION:
FIVEMILE CREEK 120.0
END DESCRIPTION:
XS GIS Cut Line= 3
      2489724.99     13560474.98      2489275.00     13559875.00
      2488674.98     13559424.99
#Sta/Elev= 30
  4180.7  281.73  4273.4  280.17  4288.0  278.61  4307.6  278.42  4314.5  278.22
  4444.2  274.28  4480.7  274.58  4530.7  272.69  4580.7  272.09  4623.4  272.68
  4688.0  270.87  4938.0  270.25  4945.9  269.41  5002.6  267.19  5017.1  269.24
  5030.7  268.98  5038.0  268.64  5049.5  264.61  5050.0  264.11  5055.1  264.11
  5055.6  264.61  5073.4  269.27  5094.2  269.84  5100.6  271.06  5144.2  271.81
  5292.1  276.99  5358.8  280.68  5547.7  288.84  5651.9  292.99  5680.7  294.51
#Mann=11,-1,0
  4180.7   0.013       0  4307.6    0.05       0  4314.5    0.12       0
  4580.7    0.05       0  4945.9    0.12       0  5049.5    0.05       0
  5055.6    0.12       0  5100.6    0.04       0  5292.1    0.12       0
  5547.7    0.05       0  5651.9    0.04       0
Bank Sta=5049.5,5055.6
Exp/Cntr=0.3,0.1

Type RM Length L Ch R = 1,72554,504,504,504
BEGIN DESCRIPTION:
FIVEMILE CREEK 119.0
END DESCRIPTION:
XS GIS Cut Line= 3
      2490175.00     13560425.01      2489675.00     13559675.00
      2489325.00     13558875.01
#Sta/Elev= 30
  4094.1  288.83  4122.7  288.56  4138.9  285.76  4188.8  285.46  4215.8  284.08
  4260.9  283.63  4274.4  282.46  4576.3  273.98  4634.9  272.70  4684.5  272.77
  4720.6  271.13  4782.0  270.59  4915.9  268.95  4973.0  266.89  4998.2  267.10
  5017.3  263.50  5024.8  262.88  5025.3  262.38  5031.0  262.88  5033.3  266.00
  5039.2  267.06  5062.2  268.66  5126.5  268.39  5330.4  269.80  5335.8  270.65
  5411.4  271.82  5543.6  276.47  5627.4  279.57  5856.6  290.10  5868.7  290.09
#Mann=7,-1,0
  4094.1   0.013       0  4138.9    0.05       0  4782.0     0.1       0
  5024.8    0.05       0  5031.0     0.1       0  5543.6    0.12       0
  5856.6    0.05       0
Bank Sta=5024.8,5031
Exp/Cntr=0.3,0.1

Type RM Length L Ch R = 1,72050,435,435,435
BEGIN DESCRIPTION:
FIVEMILE CREEK 118.0
END DESCRIPTION:
XS GIS Cut Line= 3
      2490625.00     13559875.00      2490025.00     13559375.00
      2489474.98     13558774.98
#Sta/Elev= 30
  4183.1  286.50  4288.4  281.59  4290.0  281.53  4317.8  281.25  4339.3  279.75
  4459.7  275.98  4590.0  273.00  4619.3  272.22  4679.7  270.66  4776.7  270.02
  4908.0  268.07  4926.0  267.81  4957.0  266.66  5013.8  266.50  5020.6  265.41
  5028.0  261.89  5031.5  261.73  5032.0  261.23  5038.0  261.73  5042.1  264.67
  5048.9  264.11  5063.1  266.73  5169.2  267.66  5268.4  270.23  5374.5  274.65
  5396.1  274.71  5615.1  284.59  5671.7  287.26  5728.4  288.69  5778.1  291.55
#Mann=11,-1,0
  4183.1    0.12       0  4288.4    0.05       0  4290.0    0.04       0
  4590.0    0.05       0  4619.3    0.04       0  4776.7    0.05       0
  4908.0    0.04       0  4926.0     0.1       0  5031.5    0.05       0
  5038.0     0.1       0  5615.1    0.12       0
Bank Sta=5031.5,5038
Exp/Cntr=0.3,0.1

Type RM Length L Ch R = 1,71615,464,464,464
BEGIN DESCRIPTION:
FIVEMILE CREEK 117.0
END DESCRIPTION:
XS GIS Cut Line= 3
      2491075.01     13559775.01      2490275.00     13559025.00
      2489875.01     13558675.00
#Sta/Elev= 30
  3904.0  295.58  3996.1  291.74  4024.4  288.16  4111.7  287.66  4137.3  286.22
  4208.1  285.78  4236.4  283.22  4295.5  280.57  4336.1  279.01  4399.1  275.99
  4575.9  271.08  4765.3  267.73  4870.9  267.01  4875.8  267.08  4944.2  266.99
  4951.0  266.29  4958.3  263.96  4961.9  261.38  4962.4  260.88  4968.5  261.38
  4986.7  265.28  5003.9  264.39  5007.7  265.67  5022.0  266.44  5050.4  265.11
  5078.9  266.12  5099.8  263.71  5142.5  267.29  5312.4  271.23  5532.1  280.78
#Mann=9,-1,0
  3904.0    0.12       0  4111.7    0.05       0  4295.5    0.12       0
  4336.1    0.05       0  4765.3     0.1       0  4870.9    0.05       0
  4875.8     0.1       0  4961.9    0.05       0  4968.5     0.1       0
Bank Sta=4961.9,4968.5
Exp/Cntr=0.3,0.1

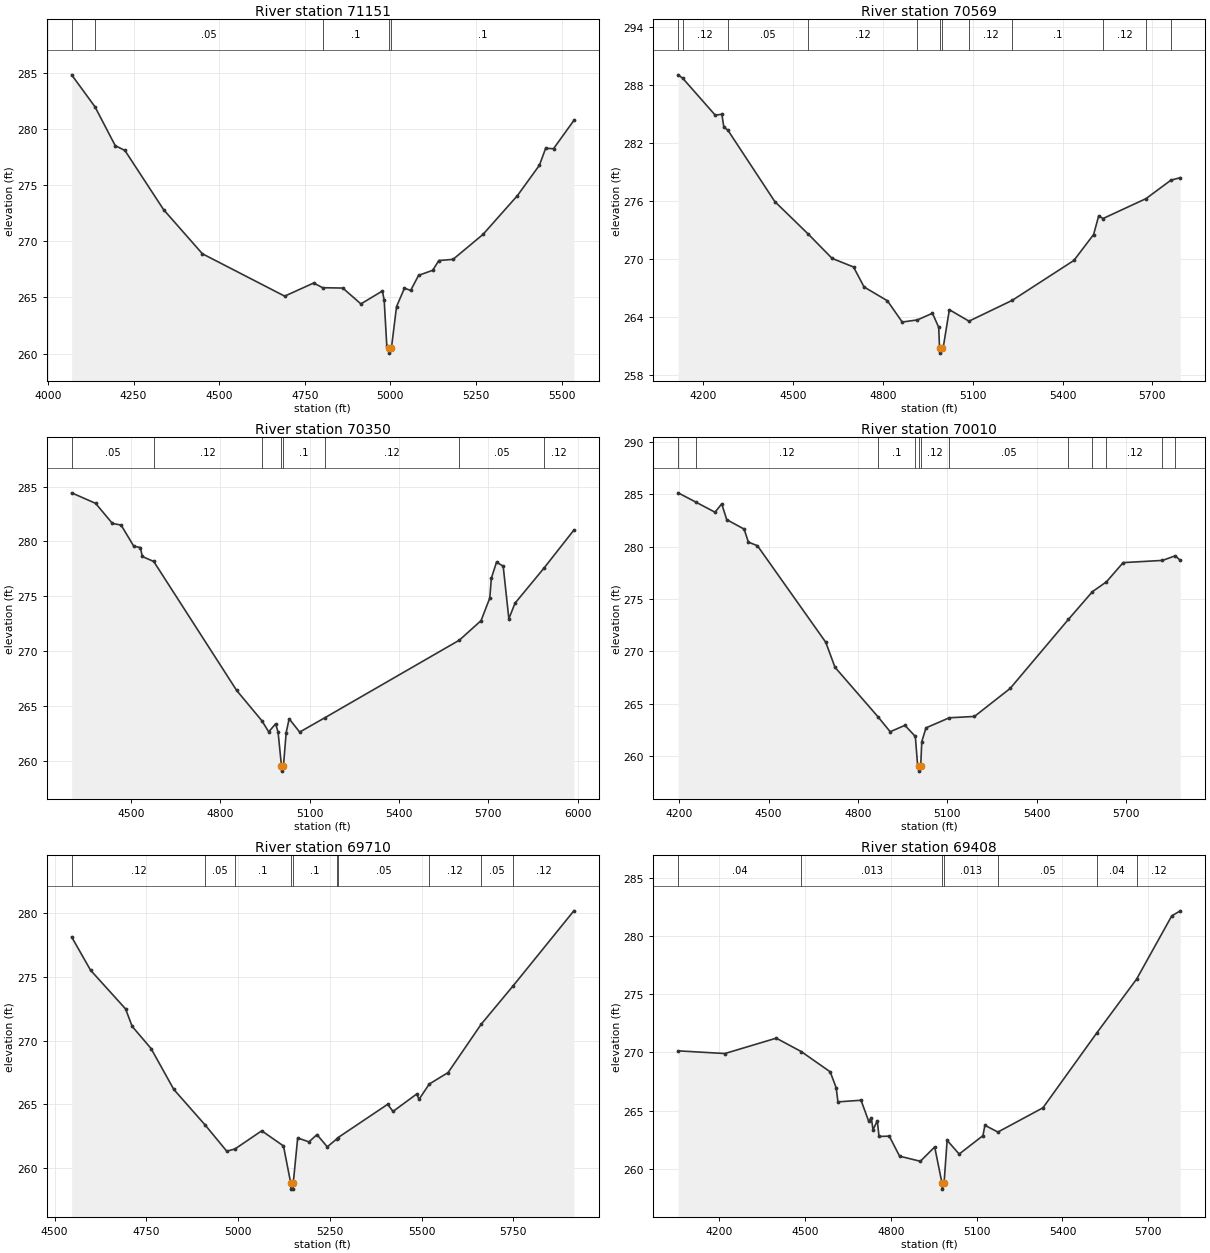
Type RM Length L Ch R = 1,71151,582,582,582
BEGIN DESCRIPTION:
FIVEMILE CREEK 116.0
END DESCRIPTION:
XS GIS Cut Line= 3
      2491125.02     13559275.02      2490525.00     13558675.00
      2489925.02     13558525.00
#Sta/Elev= 30
  4069.0  284.81  4137.3  281.96  4196.3  278.51  4224.6  278.08  4337.7  272.81
  4450.9  268.89  4691.3  265.12  4776.1  266.29  4802.1  265.87  4861.0  265.84
  4914.0  264.43  4976.8  265.58  4982.0  264.75  4989.7  260.65  4996.7  260.55
  4997.2  260.05  5003.3  260.55  5018.1  264.19  5041.2  265.83  5059.3  265.63
  5082.5  266.97  5123.7  267.42  5141.7  268.29  5183.0  268.39  5270.6  270.61
  5371.1  274.06  5435.5  276.77  5453.6  278.27  5476.7  278.24  5536.0  280.75
#Mann=5,-1,0
  4069.0    0.12       0  4137.3    0.05       0  4802.1     0.1       0
  4996.7    0.05       0  5003.3     0.1       0
Bank Sta=4996.7,5003.3
Exp/Cntr=0.3,0.1

Type RM Length L Ch R = 1,70569,219,219,219
BEGIN DESCRIPTION:
Mapping XS 3fa23fd0
END DESCRIPTION:
XS GIS Cut Line= 4
      2491465.65     13559079.86      2490940.46     13558450.50
      2490784.21     13558337.65      2490141.80     13558164.03
#Sta/Elev= 30
  4115.3  289.04  4130.9  288.68  4239.4  284.86  4261.5  284.96  4268.0  283.64
  4281.5  283.31  4438.5  275.91  4550.4  272.54  4629.8  270.03  4701.4  269.14
  4736.6  267.07  4814.6  265.64  4864.1  263.44  4914.9  263.66  4965.1  264.35
  4986.0  262.89  4988.8  260.72  4989.3  260.22  4995.6  260.72  5000.7  260.74
  5021.6  264.72  5087.1  263.53  5231.8  265.69  5437.7  269.82  5503.5  272.50
  5520.6  274.44  5535.1  274.16  5678.6  276.22  5761.8  278.13  5793.2  278.39
#Mann=12,-1,0
  4115.3    0.05       0  4130.9    0.12       0  4281.5    0.05       0
  4550.4    0.12       0  4914.9     0.1       0  4988.8    0.05       0
  4995.6     0.1       0  5087.1    0.12       0  5231.8     0.1       0
  5535.1    0.12       0  5678.6    0.05       0  5761.8    0.12       0
Bank Sta=4988.8,4995.6
Exp/Cntr=0.3,0.1

Type RM Length L Ch R = 1,70350,340,340,340
BEGIN DESCRIPTION:
Mapping XS 374f7727
END DESCRIPTION:
XS GIS Cut Line= 4
      2491509.00     13558762.96      2491209.55     13558355.01
      2490745.14     13558085.91      2490124.51     13557916.65
#Sta/Elev= 30
  4300.8  284.43  4381.3  283.47  4437.6  281.64  4466.9  281.49  4509.2  279.57
  4531.7  279.44  4537.9  278.63  4576.5  278.17  4854.7  266.42  4939.6  263.65
  4962.4  262.64  4985.5  263.37  4993.8  262.64  5005.2  259.56  5005.7  259.06
  5012.0  259.56  5021.1  262.58  5031.1  263.83  5066.4  262.62  5149.8  263.91
  5602.5  271.00  5675.4  272.78  5704.7  274.84  5709.9  276.64  5727.3  278.11
  5749.7  277.74  5768.7  272.95  5789.4  274.37  5886.4  277.56  5986.9  281.03
#Mann=8,-1,0
  4300.8    0.05       0  4576.5    0.12       0  4939.6     0.1       0
  5005.2    0.05       0  5012.0     0.1       0  5149.8    0.12       0
  5602.5    0.05       0  5886.4    0.12       0
Bank Sta=5005.2,5012
Exp/Cntr=0.3,0.1

Type RM Length L Ch R = 1,70010,300,300,300
BEGIN DESCRIPTION:
Mapping XS 7d8df69c
END DESCRIPTION:
XS GIS Cut Line= 4
      2491600.20     13558645.84      2491352.78     13558151.02
      2490970.84     13557751.71      2490423.92     13557560.73
#Sta/Elev= 30
  4196.5  285.13  4257.0  284.23  4320.4  283.28  4342.8  284.08  4359.6  282.57
  4418.0  281.67  4432.2  280.43  4462.7  280.08  4691.9  270.87  4722.9  268.48
  4867.1  263.76  4908.1  262.33  4957.5  262.94  4992.5  261.88  5000.0  259.19
  5003.6  259.07  5004.1  258.57  5010.6  259.07  5014.1  261.39  5028.3  262.70
  5106.3  263.66  5190.9  263.79  5310.6  266.46  5506.4  273.06  5586.8  275.70
  5633.6  276.63  5689.8  278.47  5821.8  278.68  5864.8  279.12  5881.6  278.68
#Mann=12,-1,0
  4196.5    0.05       0  4257.0    0.12       0  4867.1     0.1       0
  4992.5    0.12       0  5003.6    0.05       0  5010.6    0.12       0
  5106.3    0.05       0  5506.4    0.12       0  5586.8    0.05       0
  5633.6    0.12       0  5821.8    0.05       0  5864.8    0.12       0
Bank Sta=5003.6,5010.6
Exp/Cntr=0.3,0.1

Type RM Length L Ch R = 1,69710,302,302,302
BEGIN DESCRIPTION:
FIVEMILE CREEK 113.0
END DESCRIPTION:
XS GIS Cut Line= 3
      2491524.99     13558324.97      2491375.00     13557725.00
      2490775.02     13557275.02
#Sta/Elev= 30
  4546.4  278.14  4597.9  275.53  4693.3  272.49  4711.3  271.12  4762.8  269.38
  4824.7  266.17  4910.9  263.35  4969.0  261.32  4991.3  261.49  5064.3  262.92
  5123.6  261.73  5143.2  258.84  5143.7  258.34  5149.8  258.34  5150.3  258.84
  5162.3  262.36  5193.0  262.05  5214.8  262.62  5243.0  261.66  5268.4  262.27
  5272.5  262.39  5407.5  265.00  5422.1  264.44  5486.7  265.81  5493.0  265.39
  5520.8  266.59  5572.1  267.49  5662.4  271.29  5749.9  274.32  5914.8  280.19
#Mann=10,-1,0
  4546.4    0.12       0  4910.9    0.05       0  4991.3     0.1       0
  5143.2    0.05       0  5150.3     0.1       0  5268.4    0.12       0
  5272.5    0.05       0  5520.8    0.12       0  5662.4    0.05       0
  5749.9    0.12       0
Bank Sta=5143.2,5150.3
Exp/Cntr=0.3,0.1

Type RM Length L Ch R = 1,69408,428,428,428
BEGIN DESCRIPTION:
Mapping XS 2e1698ce
END DESCRIPTION:
XS GIS Cut Line= 4
      2492062.58     13558404.28      2491552.44     13557656.23
      2491520.59     13557620.46      2491152.70     13556908.53
#Sta/Elev= 30
  4057.0  270.13  4220.4  269.90  4400.0  271.22  4487.1  270.07  4588.4  268.33
  4609.3  266.96  4615.4  265.75  4696.1  265.89  4723.1  264.07  4732.0  264.38
  4738.0  263.36  4753.0  264.13  4759.0  262.78  4794.9  262.81  4830.8  261.09
  4903.4  260.65  4953.5  261.88  4979.1  258.76  4979.6  258.26  4986.2  258.76
  4996.9  262.45  5039.0  261.27  5122.0  262.85  5129.0  263.74  5174.3  263.16
  5331.7  265.24  5520.2  271.68  5659.0  276.29  5781.9  281.72  5811.7  282.15
#Mann=7,-1,0
  4057.0    0.04       0  4487.1   0.013       0  4979.1    0.03       0
  4986.2   0.013       0  5174.3    0.05       0  5520.2    0.04       0
  5659.0    0.12       0
Bank Sta=4979.1,4986.2
Exp/Cntr=0.3,0.1

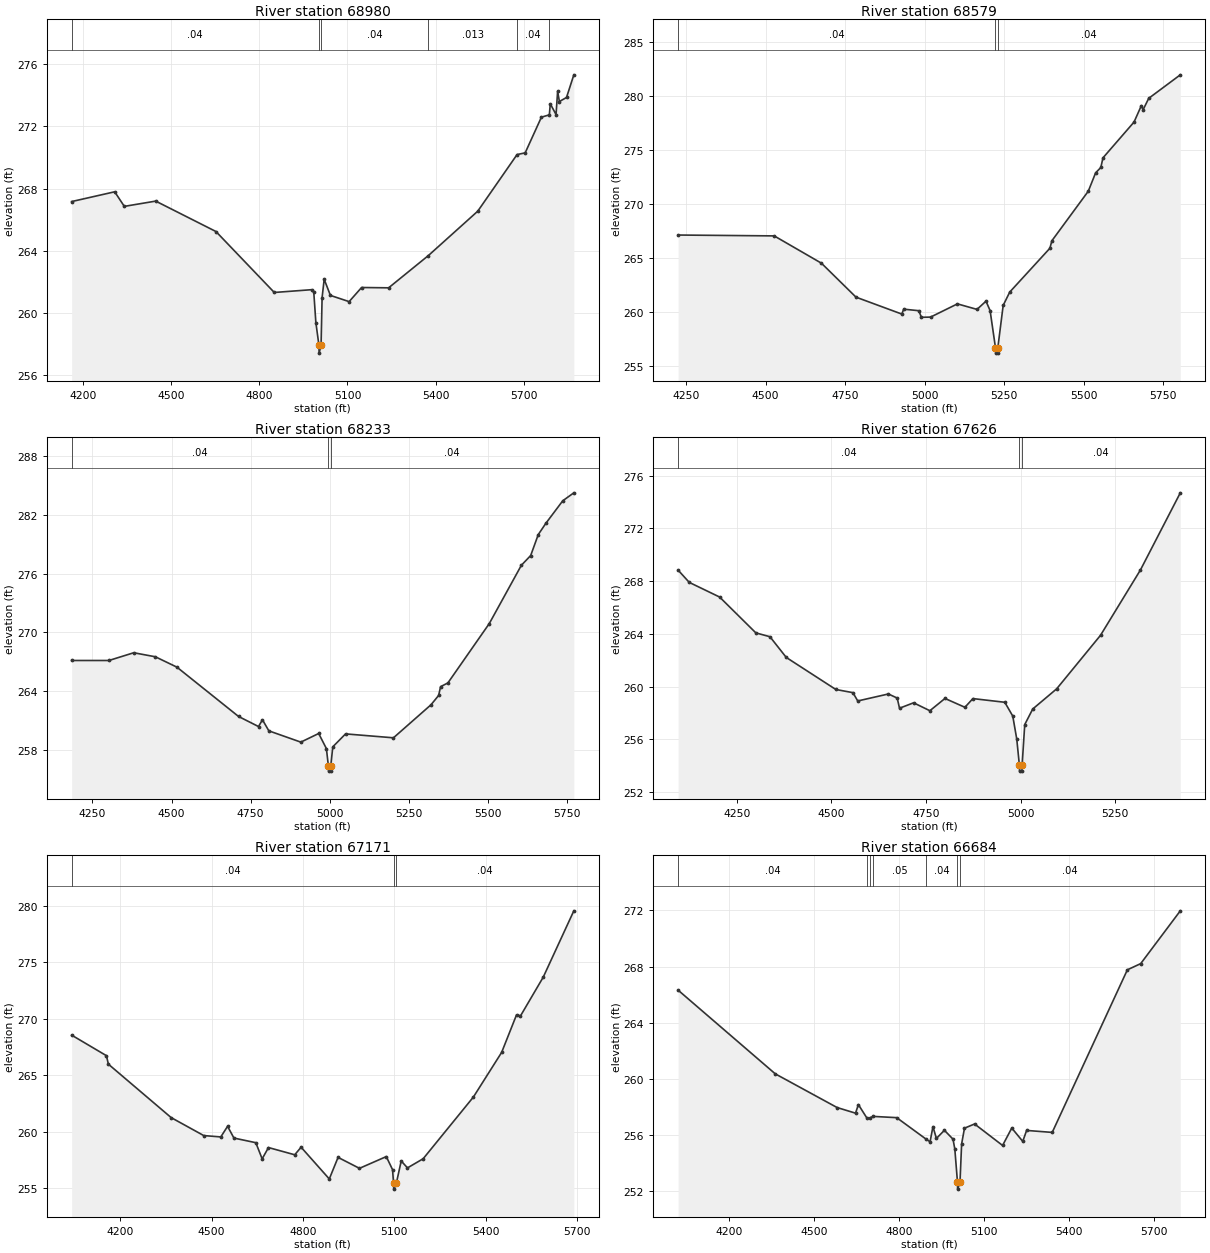
Type RM Length L Ch R = 1,68980,401,401,401
BEGIN DESCRIPTION:
Mapping XS 7d76f467
END DESCRIPTION:
XS GIS Cut Line= 4
      2492264.25     13558259.54      2492025.53     13557703.97
      2491634.90     13557317.68      2491440.40     13556799.01
#Sta/Elev= 30
  4162.0  267.16  4308.4  267.79  4341.1  266.85  4447.9  267.19  4652.7  265.23
  4851.2  261.30  4978.4  261.48  4985.5  261.32  4992.6  259.36  5003.1  257.89
  5003.6  257.39  5010.3  257.89  5013.8  260.97  5020.9  262.15  5042.1  261.11
  5105.7  260.71  5148.1  261.62  5240.1  261.60  5375.3  263.68  5543.2  266.54
  5676.9  270.19  5704.5  270.30  5759.7  272.60  5786.7  272.75  5789.9  273.46
  5809.5  272.77  5814.9  274.27  5820.9  273.61  5845.1  273.87  5870.0  275.33
#Mann=6,-1,0
  4162.0    0.04       0  5003.1    0.04       0  5010.3    0.04       0
  5375.3   0.013       0  5676.9    0.04       0  5786.7   0.013       0
Bank Sta=5003.1,5010.3
Exp/Cntr=0.3,0.1

Type RM Length L Ch R = 1,68579,346,346,346
BEGIN DESCRIPTION:
Mapping XS 78a793c7
END DESCRIPTION:
XS GIS Cut Line= 3
      2492333.69     13558198.79      2492094.97     13557191.82
      2491869.66     13556697.86
#Sta/Elev= 30
  4225.3  267.14  4527.2  267.06  4675.5  264.54  4784.2  261.40  4928.0  259.84
  4934.1  260.29  4981.4  260.15  4989.7  259.54  5018.5  259.56  5102.8  260.78
  5164.4  260.27  5192.6  261.03  5205.5  260.16  5222.4  256.73  5222.9  256.23
  5229.3  256.23  5229.8  256.73  5246.6  260.64  5267.2  261.87  5393.4  265.92
  5399.6  266.61  5514.0  271.19  5537.1  272.89  5553.4  273.38  5560.1  274.27
  5657.8  277.58  5680.8  279.10  5686.3  278.72  5703.9  279.77  5803.1  281.94
#Mann=3,-1,0
  4225.3    0.04       0  5222.4    0.04       0  5229.8    0.04       0
Bank Sta=5222.4,5229.8
Exp/Cntr=0.3,0.1

Type RM Length L Ch R = 1,68233,607,607,607
BEGIN DESCRIPTION:
Mapping XS 4f6ff9b6
END DESCRIPTION:
XS GIS Cut Line= 4
      2492359.72     13558181.44      2492463.89     13557504.32
      2492411.81     13557144.07      2492207.81     13556644.93
#Sta/Elev= 30
  4184.2  267.13  4302.0  267.13  4380.6  267.92  4448.9  267.51  4517.2  266.45
  4712.0  261.42  4775.2  260.39  4787.7  261.08  4807.9  259.95  4909.0  258.80
  4965.5  259.68  4989.9  258.14  4996.3  256.34  4996.8  255.84  5003.2  255.84
  5003.7  256.34  5010.1  258.32  5050.5  259.64  5202.0  259.24  5320.7  262.61
  5344.8  263.56  5351.1  264.46  5374.2  264.84  5505.1  270.90  5606.6  276.85
  5636.0  277.84  5660.0  279.98  5684.0  281.13  5737.5  283.43  5772.5  284.24
#Mann=3,-1,0
  4184.2    0.04       0  4996.3    0.04       0  5003.7    0.04       0
Bank Sta=4996.3,5003.7
Exp/Cntr=0.3,0.1

Type RM Length L Ch R = 1,67626,455,455,455
BEGIN DESCRIPTION:
FIVEMILE CREEK 110.0
END DESCRIPTION:
XS GIS Cut Line= 3
      2492524.98     13558025.04      2492875.00     13557425.00
      2493074.99     13556825.02
#Sta/Elev= 30
  4094.9  268.84  4124.3  267.91  4204.5  266.80  4300.4  264.08  4337.6  263.79
  4380.7  262.22  4511.7  259.79  4556.8  259.55  4569.6  258.92  4650.6  259.45
  4673.8  259.14  4680.0  258.37  4717.2  258.78  4760.2  258.18  4800.1  259.11
  4852.8  258.44  4873.9  259.10  4958.2  258.82  4979.3  257.77  4989.8  256.03
  4996.6  254.10  4997.1  253.60  5003.6  253.60  5004.1  254.10  5010.9  257.13
  5032.0  258.31  5095.3  259.84  5211.2  263.90  5316.6  268.85  5422.0  274.70
#Mann=3,-1,0
  4094.9    0.04       0  4996.6    0.04       0  5004.1    0.04       0
Bank Sta=4996.6,5004.1
Exp/Cntr=0.3,0.1

Type RM Length L Ch R = 1,67171,487,487,487
BEGIN DESCRIPTION:
FIVEMILE CREEK 109.0
END DESCRIPTION:
XS GIS Cut Line= 3
      2492675.03     13558124.96      2493325.00     13557325.00
      2493175.00     13556725.00
#Sta/Elev= 30
  4040.5  268.54  4154.7  266.72  4161.1  265.97  4367.3  261.24  4474.3  259.65
  4530.3  259.53  4552.6  260.47  4573.4  259.43  4645.3  259.02  4666.1  257.59
  4686.9  258.59  4773.1  257.95  4794.0  258.62  4886.6  255.81  4915.4  257.72
  4985.7  256.75  5073.8  257.79  5094.4  256.63  5097.7  255.41  5098.2  254.91
  5106.6  255.41  5122.8  257.40  5143.4  256.79  5194.9  257.60  5359.8  263.06
  5452.6  267.01  5501.6  270.34  5514.5  270.24  5589.2  273.67  5689.7  279.54
#Mann=3,-1,0
  4040.5    0.04       0  5097.7    0.04       0  5106.6    0.04       0
Bank Sta=5097.7,5106.6
Exp/Cntr=0.3,0.1

Type RM Length L Ch R = 1,66684,356,356,356
BEGIN DESCRIPTION:
Mapping XS 0e51f5bd
END DESCRIPTION:
XS GIS Cut Line= 3
      2493548.97     13558493.89      2493696.53     13557482.62
      2493479.51     13556766.45
#Sta/Elev= 30
  4020.9  266.32  4363.4  260.36  4581.4  257.96  4646.3  257.56  4656.4  258.17
  4687.4  257.18  4695.6  257.21  4708.0  257.33  4791.4  257.24  4894.4  255.72
  4909.1  255.52  4919.2  256.60  4931.4  255.76  4959.6  256.34  4989.9  255.71
  4996.3  255.01  5005.7  252.65  5006.2  252.15  5014.6  252.65  5020.3  255.37
  5030.4  256.49  5066.0  256.79  5164.7  255.26  5197.1  256.50  5235.8  255.55
  5249.4  256.33  5339.7  256.19  5604.6  267.77  5651.6  268.21  5791.2  271.97
#Mann=7,-1,0
  4020.9    0.04       0  4687.4    0.05       0  4695.6    0.04       0
  4708.0    0.05       0  4894.4    0.04       0  5005.7    0.04       0
  5014.6    0.04       0
Bank Sta=5005.7,5014.6
Exp/Cntr=0.3,0.1