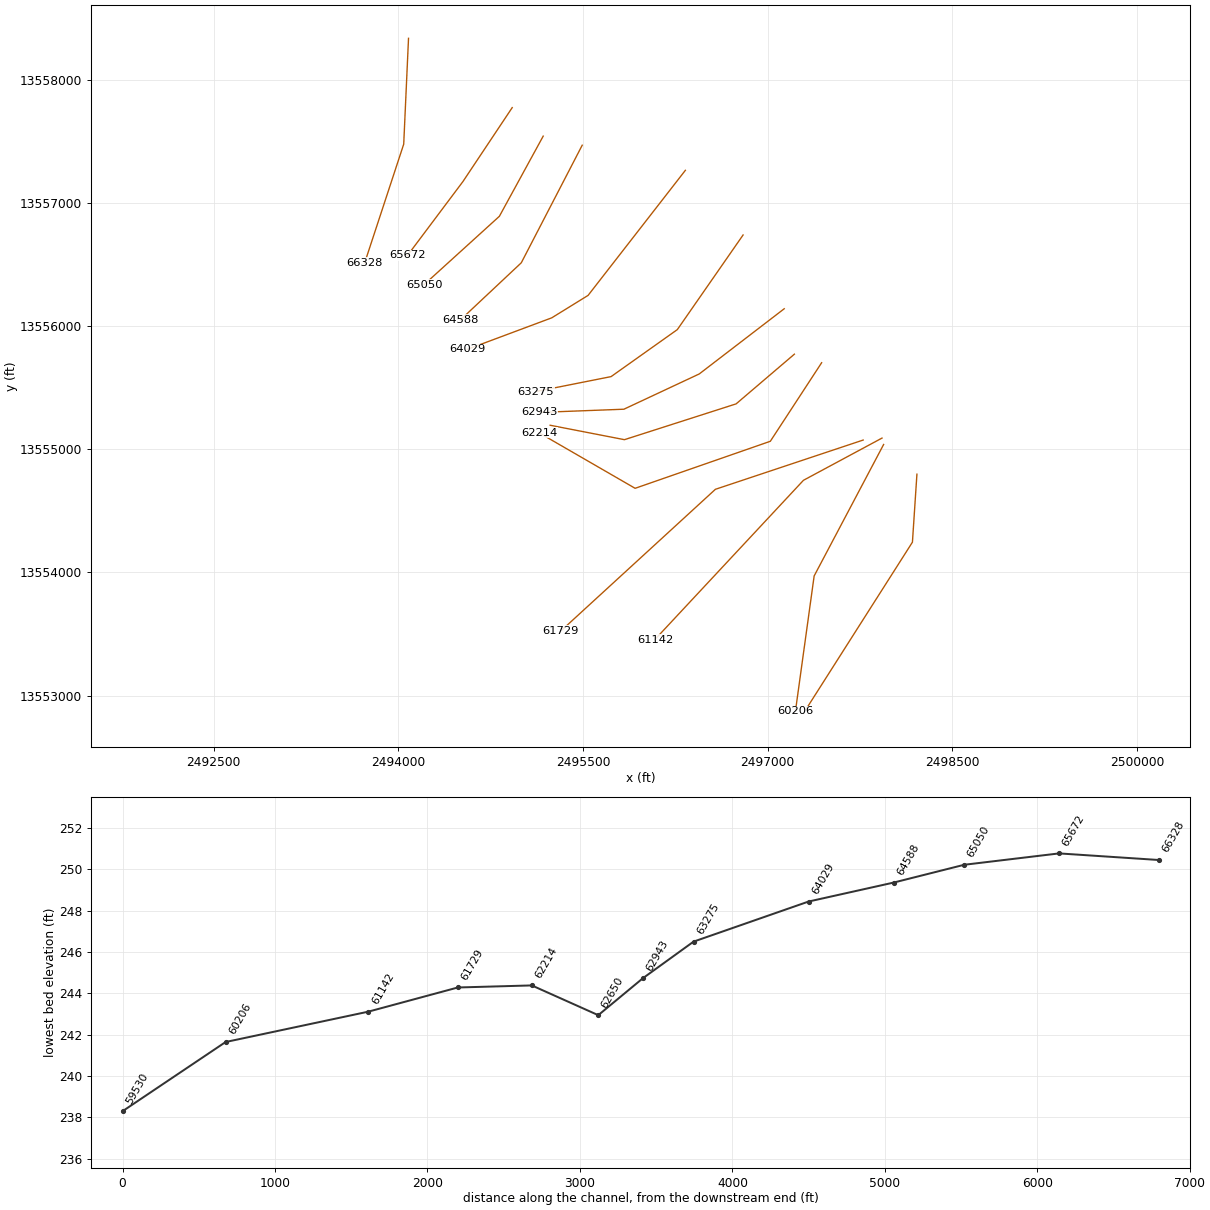
HEC-RAS study FIVEMILE CREEK.prj: FIVEMILE CREEK Base Level Engineering

--- FIVEMILE CREEK.g01 (geometry) --- (continued)

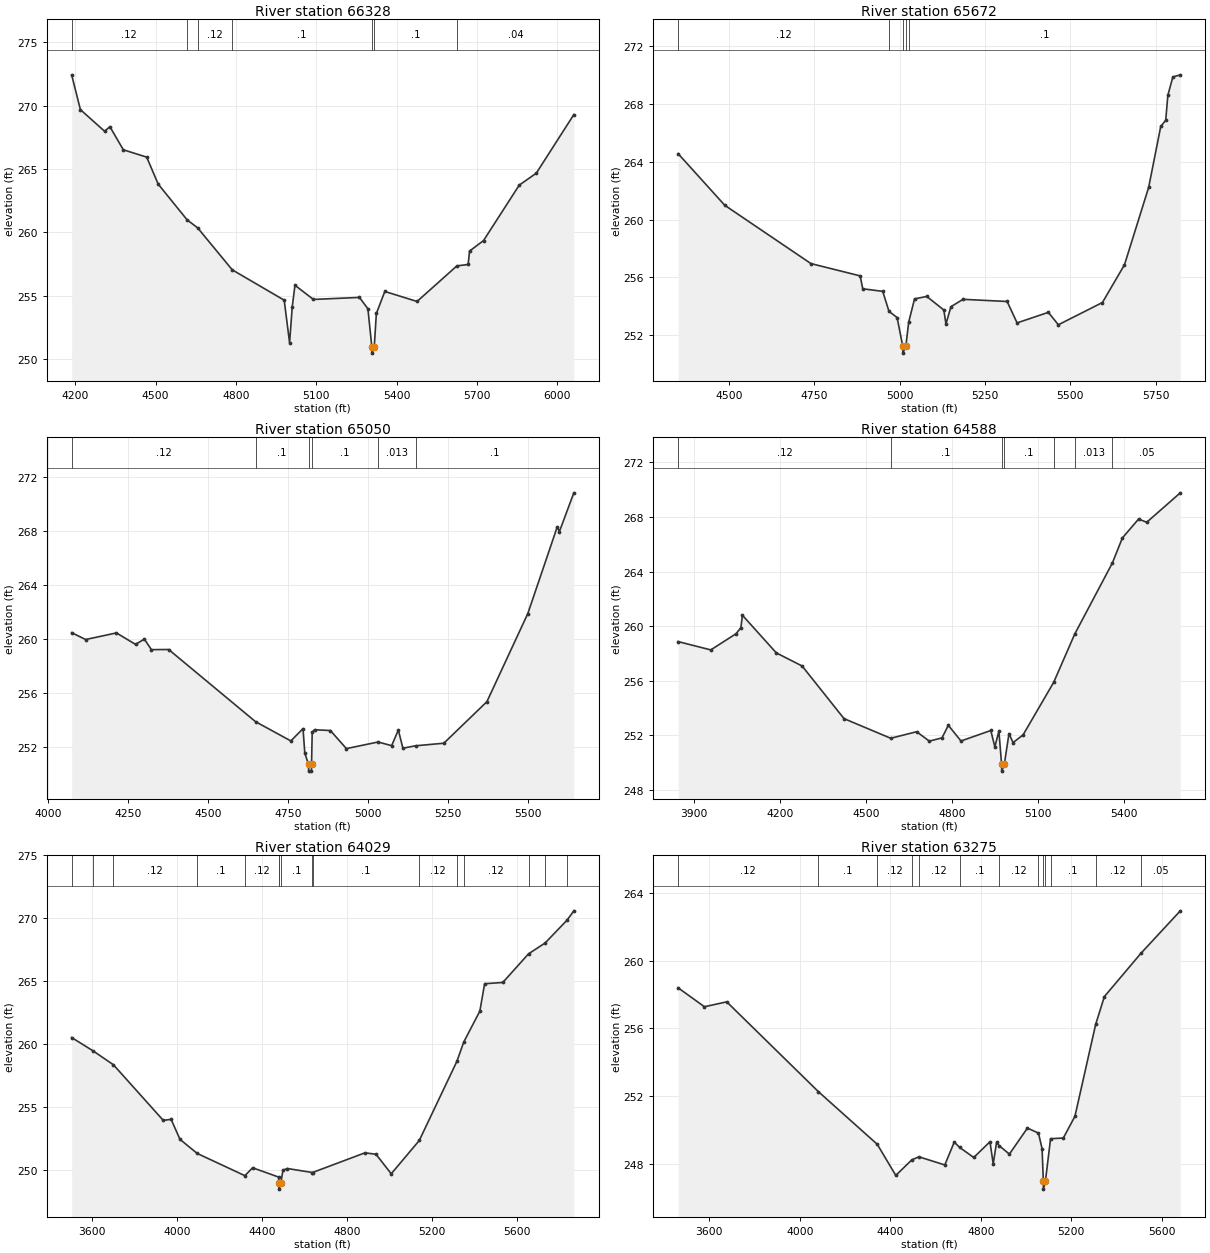
Type RM Length L Ch R = 1,66328,656,656,656
BEGIN DESCRIPTION:
Mapping XS 6a81ffd8
END DESCRIPTION:
XS GIS Cut Line= 3
      2494082.82     13558337.69      2494043.76     13557478.27
      2493726.92     13556514.73
#Sta/Elev= 30
  4186.7  272.43  4219.4  269.68  4309.5  267.98  4329.5  268.33  4379.6  266.51
  4466.9  265.93  4509.7  263.80  4617.6  260.98  4657.2  260.34  4786.1  257.03
  4980.2  254.63  5000.2  251.27  5010.2  254.12  5020.3  255.81  5089.2  254.69
  5261.0  254.85  5292.6  253.95  5307.2  250.95  5307.7  250.45  5316.3  250.95
  5324.1  253.58  5355.7  255.32  5476.0  254.53  5624.7  257.34  5666.8  257.45
  5672.0  258.51  5724.2  259.34  5857.5  263.72  5921.1  264.66  6061.3  269.29
#Mann=7,-1,0
  4186.7    0.12       0  4617.6   0.013       0  4657.2    0.12       0
  4786.1     0.1       0  5307.2    0.05       0  5316.3     0.1       0
  5624.7    0.04       0
Bank Sta=5307.2,5316.3
Exp/Cntr=0.3,0.1

Type RM Length L Ch R = 1,65672,622,622,622
BEGIN DESCRIPTION:
FIVEMILE CREEK 106.0
END DESCRIPTION:
XS GIS Cut Line= 3
      2494925.00     13557775.00      2494525.00     13557175.00
      2494075.00     13556575.00
#Sta/Elev= 30
  4350.9  264.56  4487.6  260.99  4740.0  256.96  4884.2  256.11  4891.7  255.22
  4950.3  255.04  4968.6  253.66  4992.4  253.23  5008.8  251.27  5009.3  250.77
  5018.1  251.27  5026.4  252.92  5043.5  254.52  5079.3  254.69  5129.3  253.75
  5135.5  252.78  5150.1  253.98  5185.5  254.49  5314.7  254.34  5343.9  252.86
  5435.5  253.59  5464.7  252.73  5593.9  254.27  5658.5  256.88  5729.3  262.23
  5764.7  266.44  5779.3  266.87  5785.5  268.59  5800.1  269.86  5822.0  270.01
#Mann=5,-1,0
  4350.9    0.12       0  4968.6   0.013       0  5008.8    0.03       0
  5018.1   0.013       0  5026.4     0.1       0
Bank Sta=5008.8,5018.1
Exp/Cntr=0.3,0.1

Type RM Length L Ch R = 1,65050,462,462,462
BEGIN DESCRIPTION:
Mapping XS 7aed8ed6
END DESCRIPTION:
XS GIS Cut Line= 3
      2495176.56     13557543.36      2494820.67     13556892.34
      2494209.34     13556337.37
#Sta/Elev= 30
  4074.4  260.49  4118.1  259.98  4214.1  260.47  4273.8  259.62  4301.4  260.01
  4323.3  259.23  4377.2  259.24  4648.3  253.89  4758.6  252.46  4796.6  253.37
  4802.2  251.56  4813.8  250.72  4814.3  250.22  4822.7  250.22  4823.2  250.72
  4825.3  253.11  4832.7  253.29  4882.1  253.23  4932.0  251.89  5030.9  252.38
  5073.3  252.11  5094.2  253.27  5108.4  251.92  5147.9  252.10  5236.2  252.29
  5370.6  255.37  5498.4  261.91  5590.3  268.34  5597.0  267.99  5642.0  270.86
#Mann=6,-1,0
  4074.4    0.12       0  4648.3     0.1       0  4813.8    0.05       0
  4823.2     0.1       0  5030.9   0.013       0  5147.9     0.1       0
Bank Sta=4813.8,4823.2
Exp/Cntr=0.3,0.1

Type RM Length L Ch R = 1,64588,559,559,559
BEGIN DESCRIPTION:
Mapping XS 4ac8391c
END DESCRIPTION:
XS GIS Cut Line= 3
      2495493.39     13557469.56      2494998.62     13556514.73
      2494503.83     13556050.32
#Sta/Elev= 30
  3843.9  258.86  3958.0  258.25  4046.5  259.44  4063.0  259.88  4068.6  260.79
  4186.9  258.03  4277.0  257.07  4423.4  253.21  4586.4  251.77  4677.0  252.25
  4721.3  251.56  4765.6  251.80  4787.7  252.72  4831.9  251.57  4936.0  252.34
  4950.1  251.14  4964.3  252.29  4973.7  249.86  4974.2  249.36  4983.2  249.86
  4999.5  252.11  5013.7  251.45  5048.8  252.02  5155.6  255.87  5229.1  259.41
  5360.5  264.62  5395.6  266.46  5452.3  267.85  5480.6  267.61  5597.9  269.77
#Mann=7,-1,0
  3843.9    0.12       0  4586.4     0.1       0  4973.7    0.05       0
  4983.2     0.1       0  5155.6    0.05       0  5229.1   0.013       0
  5360.5    0.05       0
Bank Sta=4973.7,4983.2
Exp/Cntr=0.3,0.1

Type RM Length L Ch R = 1,64029,754,754,754
BEGIN DESCRIPTION:
Mapping XS c2e99c0a
END DESCRIPTION:
XS GIS Cut Line= 4
      2496331.07     13557265.59      2495541.15     13556249.98
      2495246.01     13556067.68      2494560.21     13555811.59
#Sta/Elev= 30
  3502.3  260.50  3604.0  259.43  3699.3  258.33  3933.8  253.91  3970.9  253.99
  4012.6  252.40  4093.7  251.28  4318.3  249.51  4354.6  250.14  4477.0  249.40
  4478.4  248.94  4478.9  248.44  4487.9  248.94  4497.6  249.94  4518.4  250.08
  4636.7  249.76  4636.9  249.76  4884.2  251.33  4936.2  251.21  5007.7  249.66
  5139.8  252.31  5317.1  258.61  5349.6  260.15  5425.1  262.60  5447.7  264.78
  5533.3  264.88  5654.5  267.16  5732.6  268.02  5836.5  269.85  5867.9  270.58
#Mann=16,-1,0
  3502.3    0.12       0  3604.0    0.05       0  3699.3    0.12       0
  4093.7     0.1       0  4318.3    0.12       0  4477.0     0.1       0
  4478.4    0.05       0  4487.9     0.1       0  4636.7    0.12       0
  4636.9     0.1       0  5139.8    0.12       0  5317.1    0.05       0
  5349.6    0.12       0  5654.5    0.05       0  5732.6   0.013       0
  5836.5    0.12       0
Bank Sta=4478.4,4487.9
Exp/Cntr=0.3,0.1

Type RM Length L Ch R = 1,63275,332,332,332
BEGIN DESCRIPTION:
Mapping XS 2bdf101e
END DESCRIPTION:
XS GIS Cut Line= 4
      2496799.86     13556740.47      2496265.98     13555972.20
      2495727.78     13555590.25      2495115.84     13555468.73
#Sta/Elev= 30
  3462.4  258.40  3578.7  257.28  3677.3  257.57  4082.5  252.26  4342.5  249.15
  4424.4  247.31  4495.2  248.23  4526.7  248.41  4641.0  247.93  4682.8  249.28
  4706.2  248.97  4768.9  248.37  4840.6  249.30  4855.0  247.99  4869.8  249.27
  4881.3  249.07  4926.4  248.57  5006.3  250.11  5055.0  249.81  5070.9  248.89
  5076.4  247.00  5076.9  246.50  5085.9  247.00  5108.4  249.48  5164.8  249.52
  5216.0  250.80  5307.8  256.24  5346.2  257.88  5507.2  260.43  5681.8  262.95
#Mann=13,-1,0
  3462.4    0.12       0  4082.5     0.1       0  4342.5    0.12       0
  4495.2     0.1       0  4526.7    0.12       0  4706.2     0.1       0
  4881.3    0.12       0  5055.0    0.05       0  5076.4    0.05       0
  5085.9    0.05       0  5108.4     0.1       0  5307.8    0.12       0
  5507.2    0.05       0
Bank Sta=5076.4,5085.9
Exp/Cntr=0.3,0.1

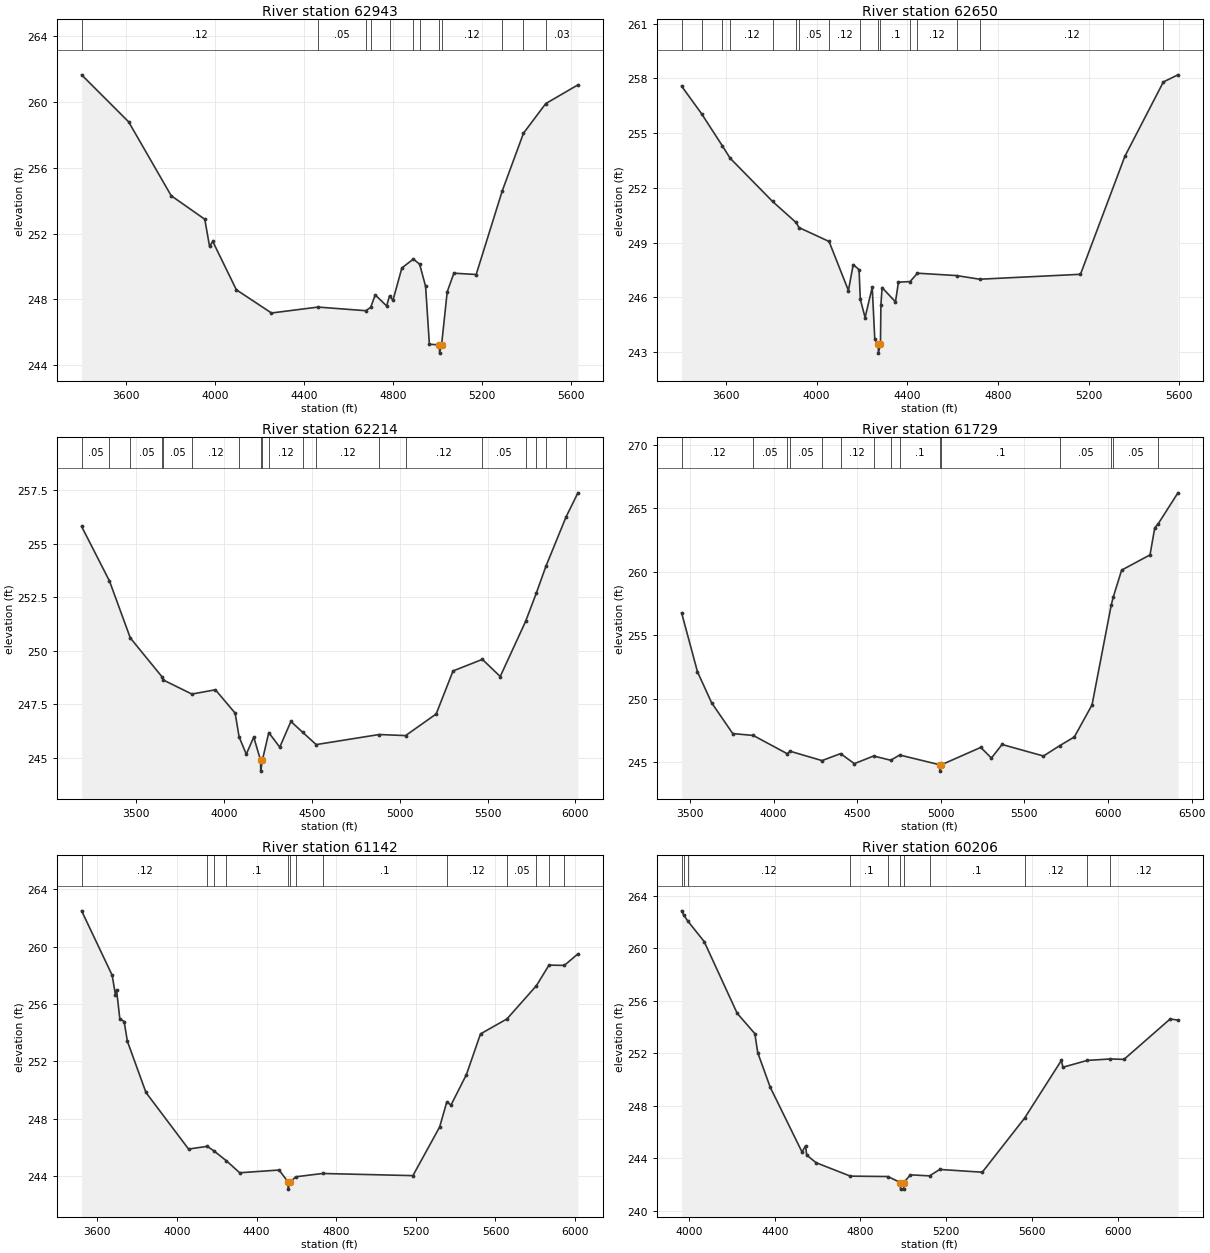
Type RM Length L Ch R = 1,62943,293,293,293
BEGIN DESCRIPTION:
Mapping XS 8c535435
END DESCRIPTION:
XS GIS Cut Line= 4
      2497134.03     13556141.46      2496443.93     13555611.96
      2495831.95     13555325.50      2495148.08     13555299.53
#Sta/Elev= 30
  3401.8  261.65  3613.2  258.79  3804.3  254.30  3955.2  252.87  3976.6  251.23
  3991.1  251.52  4097.1  248.58  4254.9  247.17  4463.9  247.53  4678.3  247.31
  4700.5  247.51  4721.0  248.27  4772.2  247.60  4785.4  248.21  4800.6  247.94
  4840.7  249.91  4892.6  250.45  4920.7  250.13  4947.3  248.79  4964.3  245.27
  5009.5  245.23  5010.0  244.73  5019.1  245.23  5044.4  248.46  5074.4  249.59
  5174.5  249.51  5291.6  254.59  5387.1  258.10  5487.0  259.90  5631.7  261.04
#Mann=12,-1,0
  3401.8    0.12       0  4463.9    0.05       0  4678.3    0.12       0
  4700.5    0.05       0  4785.4     0.1       0  4892.6    0.05       0
  4920.7    0.12       0  5009.5    0.05       0  5019.1    0.12       0
  5291.6    0.03       0  5387.1    0.12       0  5487.0    0.03       0
Bank Sta=5009.5,5019.1
Exp/Cntr=0.3,0.1

Type RM Length L Ch R = 1,62650,436,436,436
BEGIN DESCRIPTION:
Mapping XS 2455d7db
END DESCRIPTION:
XS GIS Cut Line= 4
      2497216.49     13555772.54      2496743.41     13555368.90
      2495836.29     13555078.10      2495233.04     13555195.28
#Sta/Elev= 30
  3405.0  257.57  3492.9  256.06  3584.0  254.31  3619.1  253.62  3806.2  251.25
  3909.6  250.10  3922.7  249.82  4055.2  249.06  4140.7  246.37  4161.7  247.79
  4187.5  247.52  4193.1  245.89  4214.2  244.89  4245.7  246.55  4257.0  243.69
  4272.4  243.44  4272.9  242.94  4282.0  243.44  4283.9  245.58  4289.2  246.53
  4348.2  245.75  4361.3  246.83  4412.7  246.86  4445.0  247.32  4617.4  247.19
  4719.7  246.99  5164.1  247.26  5359.7  253.72  5529.7  257.80  5594.0  258.19
#Mann=16,-1,0
  3405.0    0.05       0  3492.9    0.12       0  3584.0    0.05       0
  3619.1    0.12       0  3806.2    0.05       0  3909.6    0.12       0
  3922.7    0.05       0  4055.2    0.12       0  4193.1     0.1       0
  4272.4    0.05       0  4282.0     0.1       0  4412.7    0.05       0
  4445.0    0.12       0  4617.4    0.05       0  4719.7    0.12       0
  5529.7    0.03       0
Bank Sta=4272.4,4282
Exp/Cntr=0.3,0.1

Type RM Length L Ch R = 1,62214,485,485,485
BEGIN DESCRIPTION:
Mapping XS daf0b137
END DESCRIPTION:
XS GIS Cut Line= 4
      2497437.87     13555703.13      2497021.19     13555065.08
      2495923.10     13554683.14      2495141.81     13555134.55
#Sta/Elev= 30
  3187.9  255.81  3346.7  253.26  3465.4  250.60  3647.5  248.77  3652.3  248.64
  3816.0  247.98  3950.0  248.18  4062.4  247.09  4085.0  245.98  4125.9  245.17
  4168.3  245.97  4207.6  244.88  4208.1  244.38  4217.2  244.88  4254.0  246.18
  4316.5  245.50  4380.0  246.70  4446.3  246.20  4524.1  245.62  4882.4  246.09
  5033.3  246.04  5207.4  247.05  5303.6  249.06  5470.6  249.60  5572.3  248.80
  5716.6  251.37  5777.6  252.69  5832.1  253.94  5947.5  256.26  6014.9  257.38
#Mann=19,-1,0
  3187.9    0.05       0  3346.7    0.12       0  3465.4    0.05       0
  3647.5    0.12       0  3652.3    0.05       0  3816.0    0.12       0
  4085.0     0.1       0  4207.6    0.05       0  4217.2     0.1       0
  4254.0    0.12       0  4446.3    0.05       0  4524.1    0.12       0
  4882.4    0.05       0  5033.3    0.12       0  5470.6    0.05       0
  5716.6    0.12       0  5777.6    0.05       0  5832.1    0.03       0
  5947.5    0.05       0
Bank Sta=4207.6,4217.2
Exp/Cntr=0.3,0.1

Type RM Length L Ch R = 1,61729,587,587,587
BEGIN DESCRIPTION:
FIVEMILE CREEK 99.0
END DESCRIPTION:
XS GIS Cut Line= 3
      2497774.97     13555074.99      2496575.00     13554675.00
      2495319.89     13553524.37
#Sta/Elev= 30
  3450.5  256.75  3545.3  252.11  3629.7  249.67  3756.2  247.24  3879.2  247.09
  4082.2  245.65  4098.4  245.85  4290.0  245.11  4400.7  245.66  4483.5  244.87
  4598.1  245.47  4700.8  245.14  4754.3  245.55  4993.9  244.78  4994.4  244.28
  5003.5  244.78  5239.2  246.15  5302.7  245.31  5366.6  246.38  5614.1  245.47
  5710.2  246.28  5798.5  246.97  5904.5  249.50  6019.2  257.37  6031.1  257.99
  6081.5  260.12  6251.1  261.32  6279.4  263.45  6300.0  263.77  6418.1  266.21
#Mann=15,-1,0
  3450.5    0.12       0  3879.2    0.05       0  4082.2    0.12       0
  4098.4    0.05       0  4290.0     0.1       0  4400.7    0.12       0
  4598.1    0.05       0  4700.8    0.12       0  4754.3     0.1       0
  4993.9    0.05       0  5003.5     0.1       0  5710.2    0.05       0
  6019.2    0.12       0  6031.1    0.05       0  6300.0    0.12       0
Bank Sta=4993.9,5003.5
Exp/Cntr=0.3,0.1

Type RM Length L Ch R = 1,61142,936,936,936
BEGIN DESCRIPTION:
Mapping XS ae65a6b8
END DESCRIPTION:
XS GIS Cut Line= 3
      2497928.31     13555091.12      2497290.28     13554748.24
      2496083.65     13553454.80
#Sta/Elev= 30
  3520.9  262.49  3674.5  258.00  3690.8  256.64  3696.4  257.00  3712.7  254.99
  3734.6  254.78  3750.8  253.41  3844.2  249.84  4058.2  245.90  4152.0  246.09
  4185.0  245.78  4246.7  245.10  4315.1  244.25  4512.9  244.44  4557.9  243.61
  4558.4  243.11  4567.6  243.61  4597.2  243.97  4731.6  244.20  5185.2  244.05
  5319.5  247.44  5355.5  249.19  5376.2  248.96  5453.8  251.08  5524.7  253.92
  5657.3  254.96  5805.7  257.28  5868.7  258.71  5945.6  258.69  6014.1  259.49
#Mann=13,-1,0
  3520.9    0.12       0  4152.0    0.05       0  4185.0    0.12       0
  4246.7     0.1       0  4557.9    0.05       0  4567.6     0.1       0
  4597.2    0.12       0  4731.6     0.1       0  5355.5    0.12       0
  5657.3    0.05       0  5805.7    0.12       0  5868.7    0.05       0
  5945.6    0.12       0
Bank Sta=4557.9,4567.6
Exp/Cntr=0.3,0.1

Type RM Length L Ch R = 1,60206,676,676,676
BEGIN DESCRIPTION:
Mapping XS 7a98462e
END DESCRIPTION:
XS GIS Cut Line= 3
      2497941.31     13555039.00      2497377.09     13553971.33
      2497225.18     13552873.28
#Sta/Elev= 30
  3965.5  262.85  3974.9  262.54  3995.3  262.05  4070.7  260.51  4224.8  255.04
  4307.2  253.49  4320.7  252.04  4378.9  249.41  4527.3  244.47  4543.7  244.94
  4549.3  244.23  4593.4  243.65  4753.1  242.63  4928.0  242.60  4986.7  242.14
  4987.2  241.64  5002.0  241.64  5002.5  242.14  5033.0  242.73  5122.6  242.65
  5170.0  243.14  5368.5  242.93  5566.3  247.06  5737.7  251.45  5744.8  250.93
  5858.5  251.45  5965.9  251.56  6030.0  251.53  6245.5  254.61  6281.6  254.52
#Mann=11,-1,0
  3965.5    0.12       0  3974.9    0.03       0  3995.3    0.12       0
  4753.1     0.1       0  4928.0    0.12       0  4986.7    0.05       0
  5002.5    0.12       0  5122.6     0.1       0  5566.3    0.12       0
  5858.5    0.05       0  5965.9    0.12       0
Bank Sta=4986.7,5002.5
Exp/Cntr=0.3,0.1

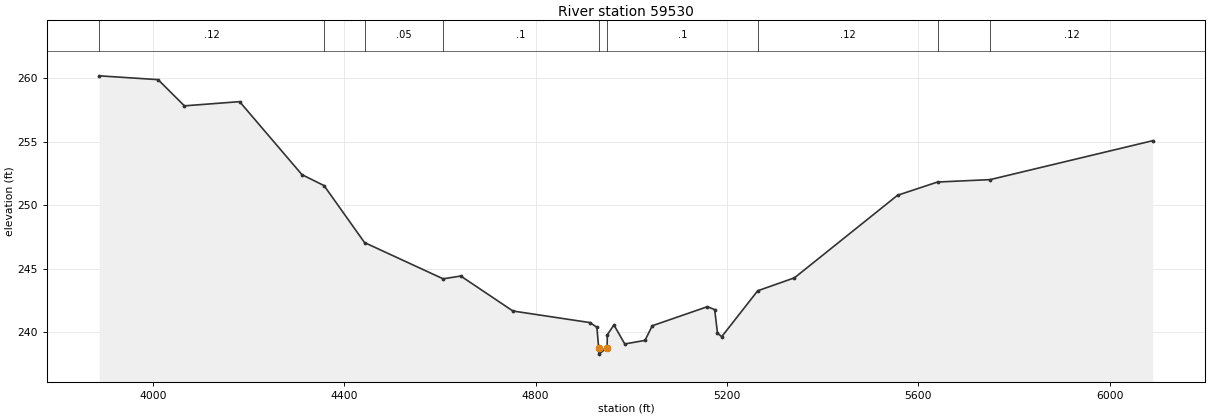
Type RM Length L Ch R = 1,59530,538,538,538
BEGIN DESCRIPTION:
Mapping XS 05af5ae5
END DESCRIPTION:
XS GIS Cut Line= 3
      2498211.73     13554797.74      2498175.27     13554245.64
      2497289.95     13552855.16
#Sta/Elev= 30
  3888.1  260.17  4011.1  259.87  4066.1  257.81  4181.5  258.14  4311.8  252.40
  4358.0  251.54  4442.6  247.06  4606.9  244.21  4643.7  244.43  4752.7  241.68
  4913.6  240.77  4928.2  240.40  4931.8  238.79  4932.3  238.29  4949.5  238.79
  4950.0  239.82  4963.8  240.58  4986.4  239.09  5028.7  239.37  5043.9  240.52
  5159.1  242.02  5174.3  241.79  5180.2  239.94  5189.0  239.66  5264.2  243.27
  5341.1  244.29  5556.5  250.78  5640.0  251.82  5750.0  252.01  6089.8  255.07
#Mann=9,-1,0
  3888.1    0.12       0  4358.0   0.035       0  4442.6    0.05       0
  4606.9     0.1       0  4931.8    0.05       0  4949.5     0.1       0
  5264.2    0.12       0  5640.0    0.05       0  5750.0    0.12       0
Bank Sta=4931.8,4949.5
Exp/Cntr=0.3,0.1