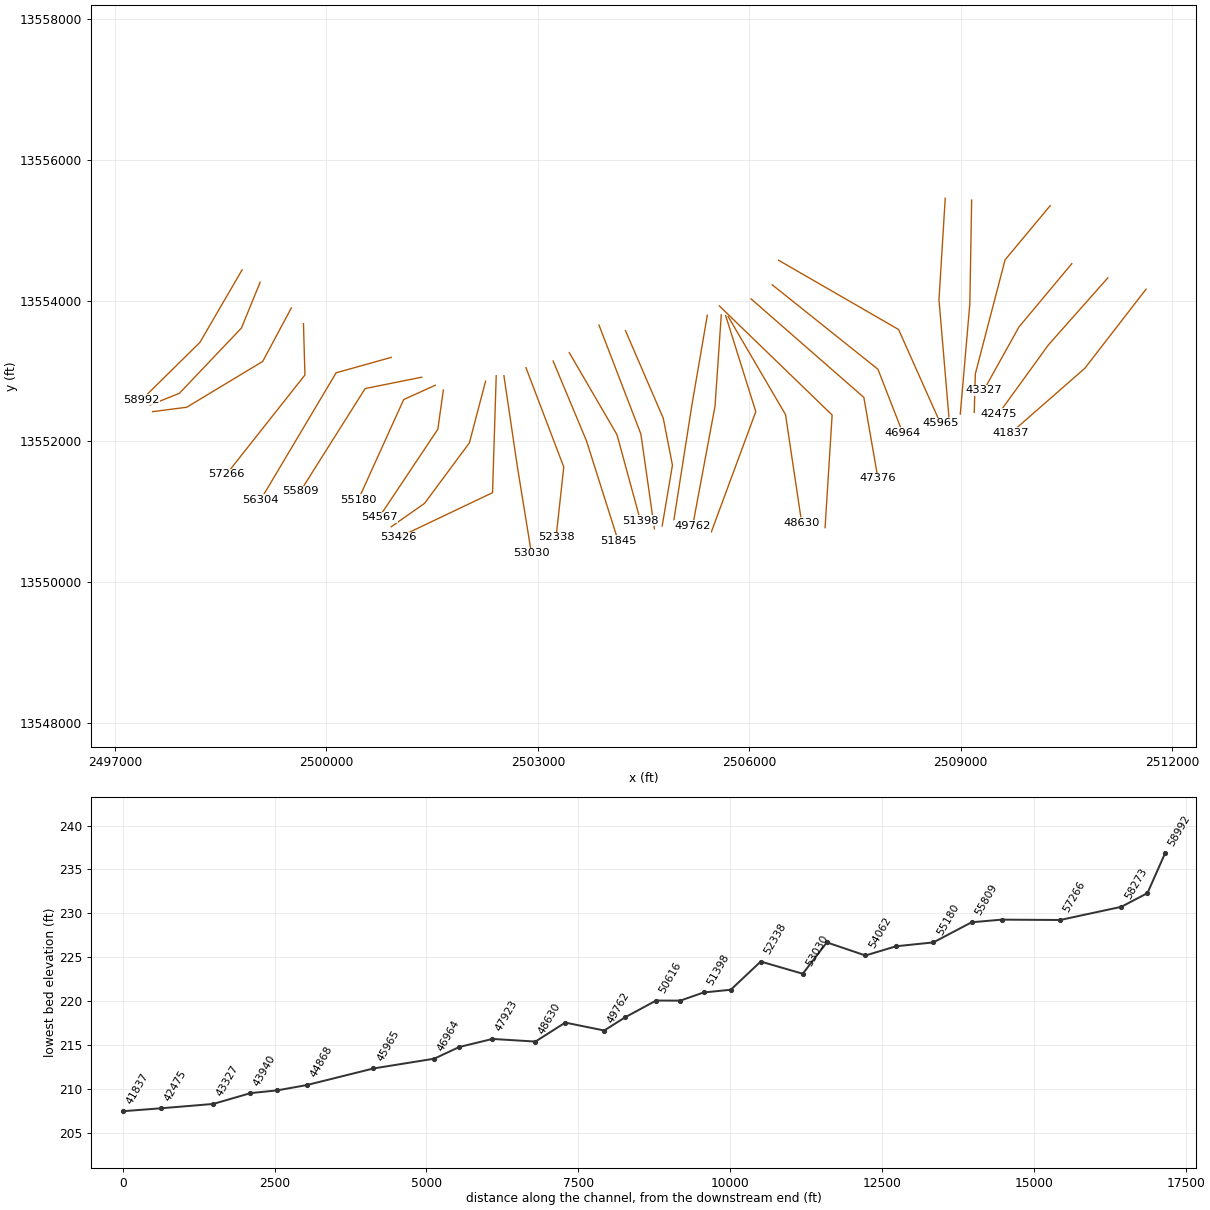
HEC-RAS study FIVEMILE CREEK.prj: FIVEMILE CREEK Base Level Engineering

--- FIVEMILE CREEK.g01 (geometry) --- (continued)

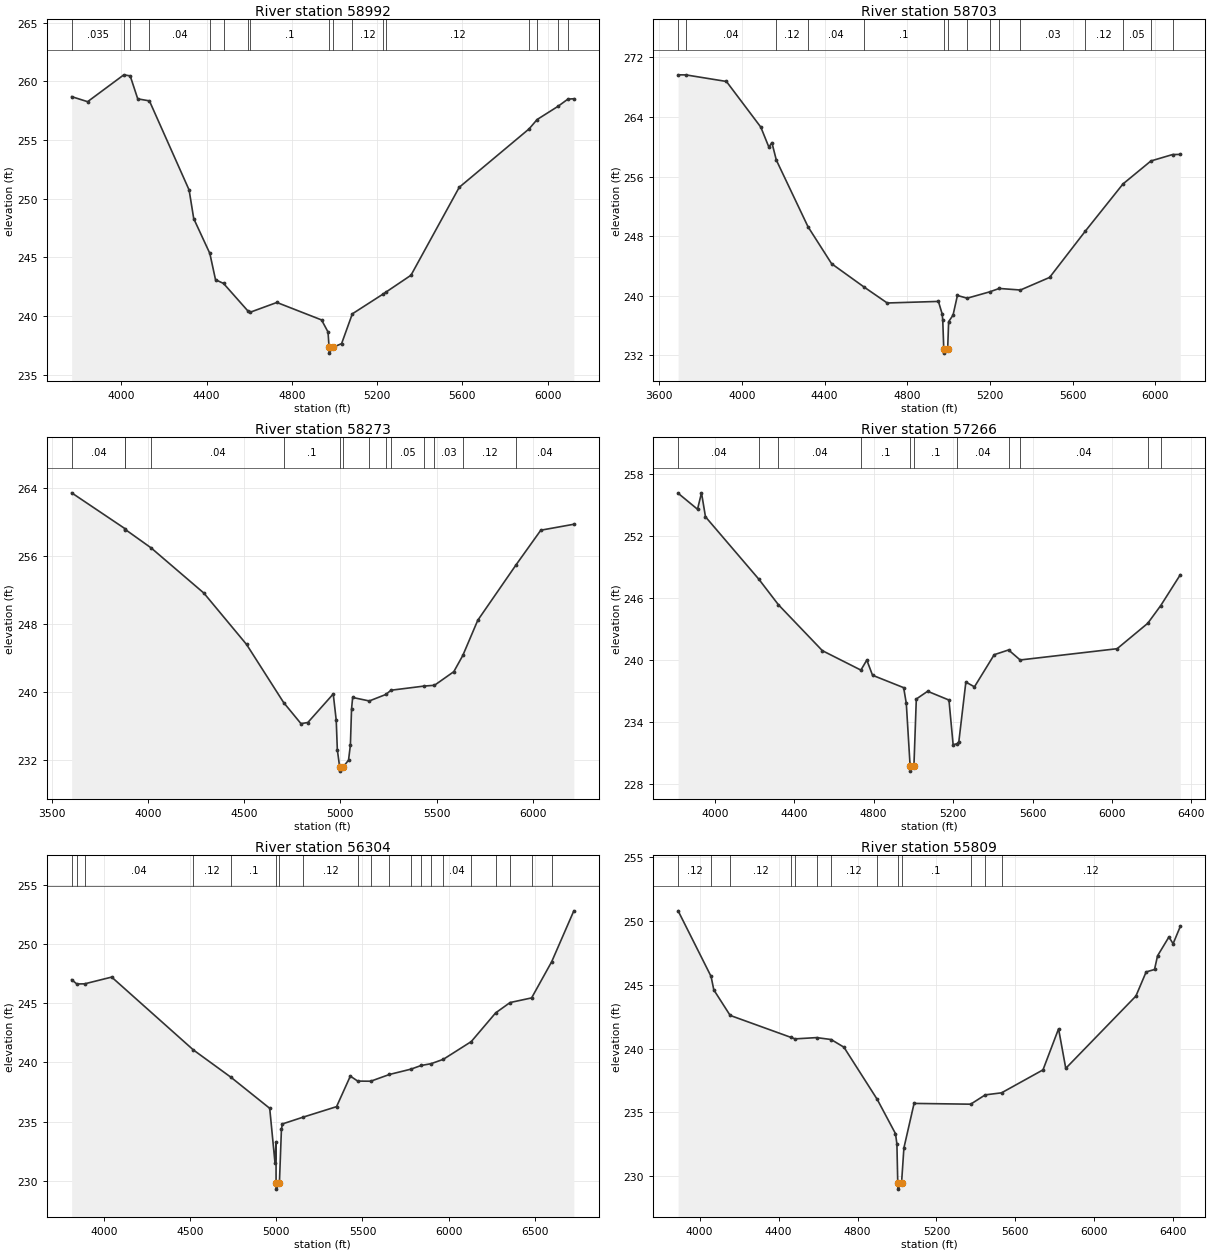
Type RM Length L Ch R = 1,58992,289,289,289
BEGIN DESCRIPTION:
Mapping XS 970ad118
END DESCRIPTION:
XS GIS Cut Line= 3
      2498805.48     13554438.35      2498206.52     13553407.09
      2497379.51     13552590.50
#Sta/Elev= 30
  3767.6  258.70  3842.4  258.27  4012.3  260.56  4042.1  260.47  4077.5  258.51
  4132.2  258.34  4318.4  250.74  4340.0  248.30  4415.6  245.33  4442.2  243.09
  4479.9  242.77  4595.8  240.39  4602.3  240.30  4729.9  241.15  4939.5  239.66
  4969.8  238.63  4974.6  237.33  4975.1  236.83  4993.3  237.33  5033.4  237.64
  5083.7  240.18  5228.2  241.87  5240.3  242.02  5358.7  243.47  5585.0  250.97
  5912.5  255.95  5950.3  256.75  6047.0  257.86  6094.7  258.49  6122.4  258.52
#Mann=17,-1,0
  3767.6   0.035       0  4012.3    0.04       0  4042.1    0.05       0
  4132.2    0.04       0  4415.6    0.12       0  4479.9    0.04       0
  4595.8    0.12       0  4602.3     0.1       0  4974.6    0.05       0
  4993.3     0.1       0  5083.7    0.12       0  5228.2   0.013       0
  5240.3    0.12       0  5912.5    0.05       0  5950.3    0.12       0
  6047.0    0.05       0  6094.7    0.04       0
Bank Sta=4974.6,4993.3
Exp/Cntr=0.3,0.1

Type RM Length L Ch R = 1,58703,430,430,430
BEGIN DESCRIPTION:
Mapping XS f0628e69
END DESCRIPTION:
XS GIS Cut Line= 4
      2499060.68     13554261.26      2498795.06     13553610.22
      2497914.85     13552683.14      2497500.02     13552517.21
#Sta/Elev= 30
  3691.9  269.66  3729.9  269.65  3925.5  268.77  4091.8  262.64  4130.7  259.96
  4145.3  260.56  4166.8  258.22  4320.0  249.27  4434.1  244.31  4591.1  241.18
  4703.0  239.04  4950.6  239.25  4968.8  237.56  4971.6  236.69  4976.5  232.81
  4977.0  232.31  4995.2  232.81  5000.0  236.53  5021.4  237.42  5042.4  240.05
  5089.6  239.68  5197.8  240.53  5244.7  240.99  5347.0  240.78  5488.2  242.47
  5660.8  248.68  5843.2  255.02  5978.1  258.10  6082.8  258.96  6120.2  258.98
#Mann=15,-1,0
  3691.9   0.035       0  3729.9    0.04       0  4166.8    0.12       0
  4320.0    0.04       0  4591.1     0.1       0  4976.5    0.05       0
  4995.2     0.1       0  5089.6    0.12       0  5197.8   0.013       0
  5244.7    0.05       0  5347.0    0.03       0  5660.8    0.12       0
  5843.2    0.05       0  5978.1    0.12       0  6082.8    0.05       0
Bank Sta=4976.5,4995.2
Exp/Cntr=0.3,0.1

Type RM Length L Ch R = 1,58273,1007,1007,1007
BEGIN DESCRIPTION:
Mapping XS d92bc1e7
END DESCRIPTION:
XS GIS Cut Line= 4
      2499503.38     13553896.65      2499097.14     13553136.26
      2498019.02     13552485.22      2497534.68     13552422.72
#Sta/Elev= 30
  3603.3  263.43  3881.3  259.21  3883.0  259.11  4015.9  256.97  4290.3  251.66
  4512.5  245.62  4705.1  238.80  4795.0  236.33  4830.8  236.46  4962.8  239.81
  4978.3  236.73  4984.1  233.24  4996.1  231.25  4996.6  230.75  5014.8  231.25
  5042.3  232.04  5052.0  233.82  5057.9  238.04  5063.7  239.40  5150.1  238.99
  5236.0  239.75  5263.1  240.25  5436.0  240.74  5489.0  240.83  5589.4  242.43
  5636.1  244.33  5713.8  248.46  5913.7  255.00  6041.5  259.04  6213.2  259.74
#Mann=14,-1,0
  3603.3    0.04       0  3881.3   0.013       0  3883.0    0.12       0
  4015.9    0.04       0  4705.1     0.1       0  4996.1    0.05       0
  5014.8     0.1       0  5150.1   0.013       0  5236.0    0.12       0
  5263.1    0.05       0  5436.0    0.12       0  5489.0    0.03       0
  5636.1    0.12       0  5913.7    0.04       0
Bank Sta=4996.1,5014.8
Exp/Cntr=0.3,0.1

Type RM Length L Ch R = 1,57266,962,962,962
BEGIN DESCRIPTION:
Mapping XS 4dbb539c
END DESCRIPTION:
XS GIS Cut Line= 3
      2499675.27     13553672.69      2499696.10     13552943.55
      2498581.52     13551532.10
#Sta/Elev= 30
  3815.9  256.15  3913.6  254.60  3933.6  256.19  3953.6  253.87  4222.6  247.82
  4321.1  245.35  4542.1  240.91  4736.0  239.03  4765.7  240.00  4794.6  238.53
  4951.2  237.33  4964.5  235.81  4983.7  229.75  4984.2  229.25  5002.9  229.75
  5014.9  236.23  5071.9  236.98  5179.3  236.13  5200.2  231.81  5220.3  231.90
  5229.0  232.10  5264.3  237.87  5307.6  237.41  5407.0  240.52  5479.4  240.98
  5537.6  240.01  6025.7  241.10  6179.9  243.56  6245.4  245.28  6343.8  248.26
#Mann=11,-1,0
  3815.9    0.04       0  4222.6   0.013       0  4321.1    0.04       0
  4736.0     0.1       0  4983.7    0.05       0  5002.9     0.1       0
  5220.3    0.04       0  5479.4   0.013       0  5537.6    0.04       0
  6179.9    0.05       0  6245.4    0.12       0
Bank Sta=4983.7,5002.9
Exp/Cntr=0.3,0.1

Type RM Length L Ch R = 1,56304,495,495,495
BEGIN DESCRIPTION:
Mapping XS bbb6c661
END DESCRIPTION:
XS GIS Cut Line= 3
      2500920.08     13553193.56      2500138.81     13552974.80
      2499066.65     13551168.79
#Sta/Elev= 30
  3814.0  246.99  3844.0  246.63  3889.2  246.64  4046.1  247.21  4520.0  241.05
  4737.0  238.75  4962.3  236.12  4993.3  231.47  4999.1  233.29  4999.2  229.79
  4999.7  229.29  5018.5  229.79  5030.3  234.36  5036.1  234.80  5157.5  235.38
  5349.9  236.26  5429.7  238.84  5472.6  238.42  5548.0  238.41  5656.5  238.98
  5781.2  239.43  5840.4  239.74  5897.7  239.89  5968.7  240.26  6130.9  241.76
  6272.6  244.19  6356.2  245.06  6480.7  245.45  6597.2  248.51  6725.6  252.81
#Mann=20,-1,0
  3814.0    0.04       0  3844.0    0.05       0  3889.2    0.04       0
  4520.0    0.12       0  4737.0     0.1       0  4999.2    0.05       0
  5018.5     0.1       0  5157.5    0.12       0  5472.6    0.04       0
  5548.0    0.12       0  5656.5    0.04       0  5781.2    0.12       0
  5840.4    0.04       0  5897.7   0.013       0  5968.7    0.04       0
  6130.9    0.12       0  6272.6    0.05       0  6356.2    0.12       0
  6480.7    0.05       0  6597.2    0.05       0
Bank Sta=4999.2,5018.5
Exp/Cntr=0.3,0.1

Type RM Length L Ch R = 1,55809,629,629,629
BEGIN DESCRIPTION:
Mapping XS 7f80dac7
END DESCRIPTION:
XS GIS Cut Line= 3
      2501352.36     13552912.31      2500550.27     13552750.84
      2499630.03     13551289.90
#Sta/Elev= 30
  3890.8  250.81  4057.7  245.67  4071.7  244.61  4154.5  242.61  4462.2  240.89
  4483.3  240.77  4592.8  240.87  4666.1  240.72  4730.9  240.12  4900.0  236.02
  4992.3  233.34  4999.5  232.53  5003.8  229.49  5004.3  228.99  5023.1  229.49
  5035.0  232.22  5086.5  235.71  5373.3  235.65  5447.1  236.38  5529.7  236.54
  5739.8  238.34  5818.7  241.56  5855.2  238.46  6210.7  244.13  6262.5  246.02
  6304.9  246.21  6320.2  247.28  6377.9  248.76  6399.1  248.23  6435.6  249.59
#Mann=13,-1,0
  3890.8    0.12       0  4057.7    0.05       0  4154.5    0.12       0
  4462.2     0.1       0  4483.3    0.12       0  4592.8    0.04       0
  4666.1    0.12       0  4900.0     0.1       0  5003.8    0.05       0
  5023.1     0.1       0  5373.3    0.12       0  5447.1     0.1       0
  5529.7    0.12       0
Bank Sta=5003.8,5023.1
Exp/Cntr=0.3,0.1

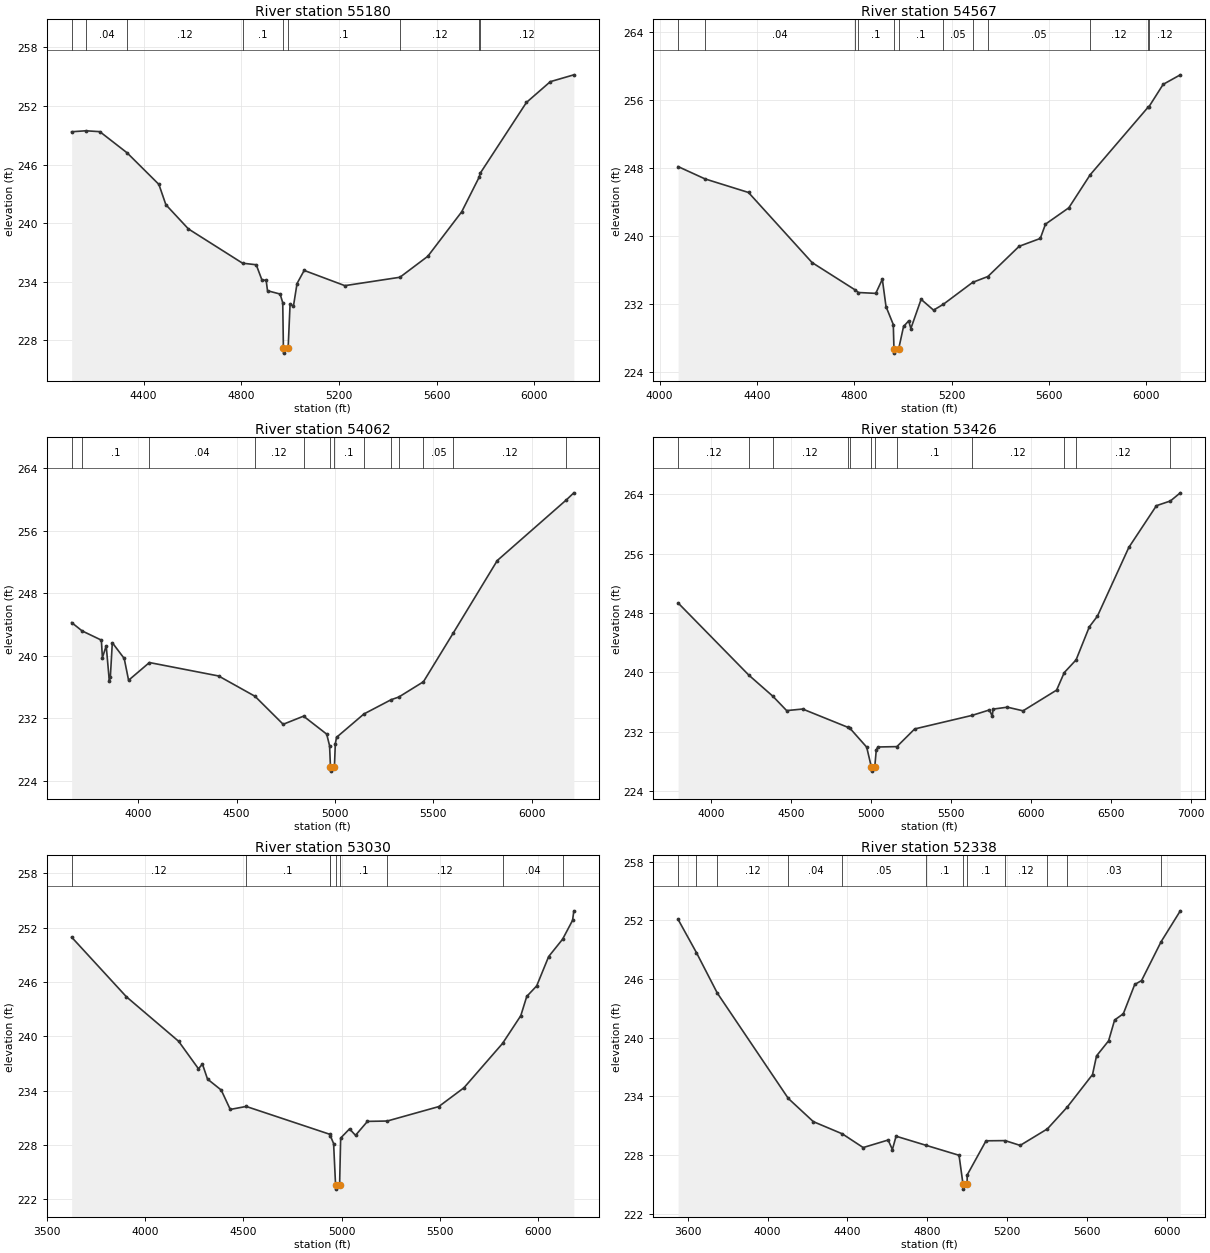
Type RM Length L Ch R = 1,55180,613,613,613
BEGIN DESCRIPTION:
Mapping XS 7a54edd7
END DESCRIPTION:
XS GIS Cut Line= 3
      2501545.05     13552797.72      2501097.14     13552594.59
      2500451.86     13551168.73
#Sta/Elev= 30
  4105.3  249.37  4163.7  249.47  4220.7  249.38  4332.5  247.21  4462.6  243.98
  4491.2  241.90  4583.5  239.42  4805.3  235.91  4861.3  235.75  4884.4  234.21
  4902.0  234.15  4907.5  233.09  4959.2  232.75  4969.9  231.86  4972.6  227.20
  4973.1  226.70  4992.0  227.20  4999.9  231.71  5013.8  231.52  5028.5  233.83
  5057.7  235.17  5224.3  233.61  5449.9  234.47  5564.2  236.62  5702.8  241.17
  5774.2  244.71  5778.7  245.12  5968.0  252.37  6065.9  254.50  6162.2  255.20
#Mann=9,-1,0
  4105.3    0.05       0  4163.7    0.04       0  4332.5    0.12       0
  4805.3     0.1       0  4972.6    0.05       0  4992.0     0.1       0
  5449.9    0.12       0  5774.2    0.03       0  5778.7    0.12       0
Bank Sta=4972.6,4992
Exp/Cntr=0.3,0.1

Type RM Length L Ch R = 1,54567,505,505,505
BEGIN DESCRIPTION:
Mapping XS 37348b86
END DESCRIPTION:
XS GIS Cut Line= 3
      2501659.64     13552729.98      2501581.52     13552172.72
      2500749.09     13550924.07
#Sta/Elev= 30
  4076.4  248.17  4187.4  246.72  4365.6  245.13  4626.7  236.90  4803.5  233.69
  4817.3  233.38  4888.5  233.28  4915.5  234.94  4930.6  231.73  4960.6  229.61
  4963.2  226.76  4963.7  226.26  4982.6  226.76  5002.7  229.39  5023.7  230.05
  5032.7  229.15  5074.8  232.58  5125.9  231.31  5165.8  231.99  5286.5  234.57
  5349.2  235.26  5477.7  238.81  5564.5  239.73  5585.8  241.41  5681.7  243.33
  5769.5  247.21  6007.8  255.16  6010.9  255.20  6069.3  257.83  6139.8  258.95
#Mann=12,-1,0
  4076.4    0.05       0  4187.4    0.04       0  4803.5    0.12       0
  4817.3     0.1       0  4963.2    0.05       0  4982.6     0.1       0
  5165.8    0.05       0  5286.5    0.12       0  5349.2    0.05       0
  5769.5    0.12       0  6007.8    0.05       0  6010.9    0.12       0
Bank Sta=4963.2,4982.6
Exp/Cntr=0.3,0.1

Type RM Length L Ch R = 1,54062,636,636,636
BEGIN DESCRIPTION:
Mapping XS e9529744
END DESCRIPTION:
XS GIS Cut Line= 4
      2502258.59     13552854.99      2502029.43     13551980.01
      2501394.02     13551120.64      2500920.06     13550787.30
#Sta/Elev= 30
  3661.9  244.24  3715.2  243.17  3813.0  241.99  3818.2  239.75  3837.6  241.26
  3853.4  236.76  3858.6  237.27  3868.6  241.66  3929.1  239.64  3951.3  236.85
  4057.2  239.12  4408.8  237.40  4593.8  234.80  4737.1  231.21  4840.7  232.25
  4958.3  229.95  4973.0  228.46  4977.6  225.71  4978.1  225.21  4997.5  225.71
  5002.2  228.72  5008.4  229.54  5147.4  232.53  5285.9  234.36  5324.7  234.70
  5450.1  236.66  5602.8  242.95  5825.5  252.19  6176.3  259.95  6214.6  260.86
#Mann=13,-1,0
  3661.9    0.12       0  3715.2     0.1       0  4057.2    0.04       0
  4593.8    0.12       0  4840.7     0.1       0  4977.6    0.05       0
  4997.5     0.1       0  5147.4    0.12       0  5285.9    0.05       0
  5324.7    0.12       0  5450.1    0.05       0  5602.8    0.12       0
  6176.3    0.05       0
Bank Sta=4977.6,4997.5
Exp/Cntr=0.3,0.1

Type RM Length L Ch R = 1,53426,396,396,396
BEGIN DESCRIPTION:
Mapping XS 4ec6e3c5
END DESCRIPTION:
XS GIS Cut Line= 3
      2502409.64     13552933.18      2502357.56     13551271.68
      2501024.24     13550636.27
#Sta/Elev= 30
  3791.6  249.34  4233.9  239.62  4383.5  236.79  4470.1  234.85  4570.2  235.06
  4852.9  232.60  4864.1  232.51  4970.4  229.93  5000.2  227.20  5000.7  226.70
  5020.6  227.20  5030.4  229.57  5040.4  229.95  5159.2  230.00  5270.5  232.38
  5630.1  234.21  5738.0  234.94  5755.2  234.08  5760.7  235.05  5850.0  235.31
  5947.8  234.82  6157.7  237.61  6205.2  239.96  6279.4  241.68  6362.0  246.12
  6412.9  247.57  6608.8  256.81  6781.6  262.44  6868.6  263.07  6930.9  264.17
#Mann=12,-1,0
  3791.6    0.12       0  4233.9     0.1       0  4383.5    0.12       0
  4852.9     0.1       0  4864.1    0.12       0  5000.2    0.05       0
  5020.6    0.12       0  5159.2     0.1       0  5630.1    0.12       0
  6205.2    0.05       0  6279.4    0.12       0  6868.6    0.05       0
Bank Sta=5000.2,5020.6
Exp/Cntr=0.3,0.1

Type RM Length L Ch R = 1,53030,692,692,692
BEGIN DESCRIPTION:
Mapping XS a512c808
END DESCRIPTION:
XS GIS Cut Line= 3
      2502519.01     13552933.18      2502706.52     13551662.30
      2502909.40     13550408.55
#Sta/Elev= 30
  3626.5  250.95  3905.0  244.37  4170.5  239.46  4271.6  236.42  4291.8  236.94
  4317.7  235.28  4387.4  234.07  4433.3  231.93  4514.6  232.26  4939.1  229.19
  4942.5  229.03  4959.1  228.16  4969.0  223.63  4969.5  223.13  4989.6  223.63
  4995.0  228.77  5040.1  229.78  5070.5  229.07  5131.3  230.61  5231.9  230.65
  5493.6  232.24  5622.1  234.32  5818.6  239.22  5911.3  242.28  5941.7  244.41
  5992.2  245.57  6053.1  248.81  6124.1  250.73  6174.7  252.81  6181.2  253.86
#Mann=9,-1,0
  3626.5    0.12       0  4514.6     0.1       0  4939.1    0.12       0
  4942.5     0.1       0  4969.0    0.05       0  4989.6     0.1       0
  5231.9    0.12       0  5818.6    0.04       0  6124.1    0.05       0
Bank Sta=4969,4989.6
Exp/Cntr=0.3,0.1

Type RM Length L Ch R = 1,52338,493,493,493
BEGIN DESCRIPTION:
Mapping XS d8f4398e
END DESCRIPTION:
XS GIS Cut Line= 3
      2502831.50     13553047.76      2503367.97     13551636.26
      2503258.80     13550638.13
#Sta/Elev= 30
  3552.4  252.09  3644.3  248.69  3748.6  244.56  4104.0  233.79  4229.3  231.42
  4374.5  230.17  4478.9  228.77  4603.8  229.54  4625.1  228.57  4643.6  229.93
  4791.8  229.01  4958.8  227.98  4978.7  225.02  4979.2  224.52  4999.3  225.02
  4999.6  225.97  5093.9  229.46  5189.3  229.48  5264.9  228.99  5401.2  230.68
  5500.6  232.91  5627.0  236.23  5647.1  238.14  5707.5  239.68  5737.7  241.81
  5781.3  242.45  5838.3  245.44  5872.5  245.84  5970.3  249.81  6066.5  252.97
#Mann=12,-1,0
  3552.4    0.05       0  3644.3    0.04       0  3748.6    0.12       0
  4104.0    0.04       0  4374.5    0.05       0  4791.8     0.1       0
  4978.7    0.05       0  4999.3     0.1       0  5189.3    0.12       0
  5401.2   0.013       0  5500.6    0.03       0  5970.3    0.12       0
Bank Sta=4978.7,4999.3
Exp/Cntr=0.3,0.1

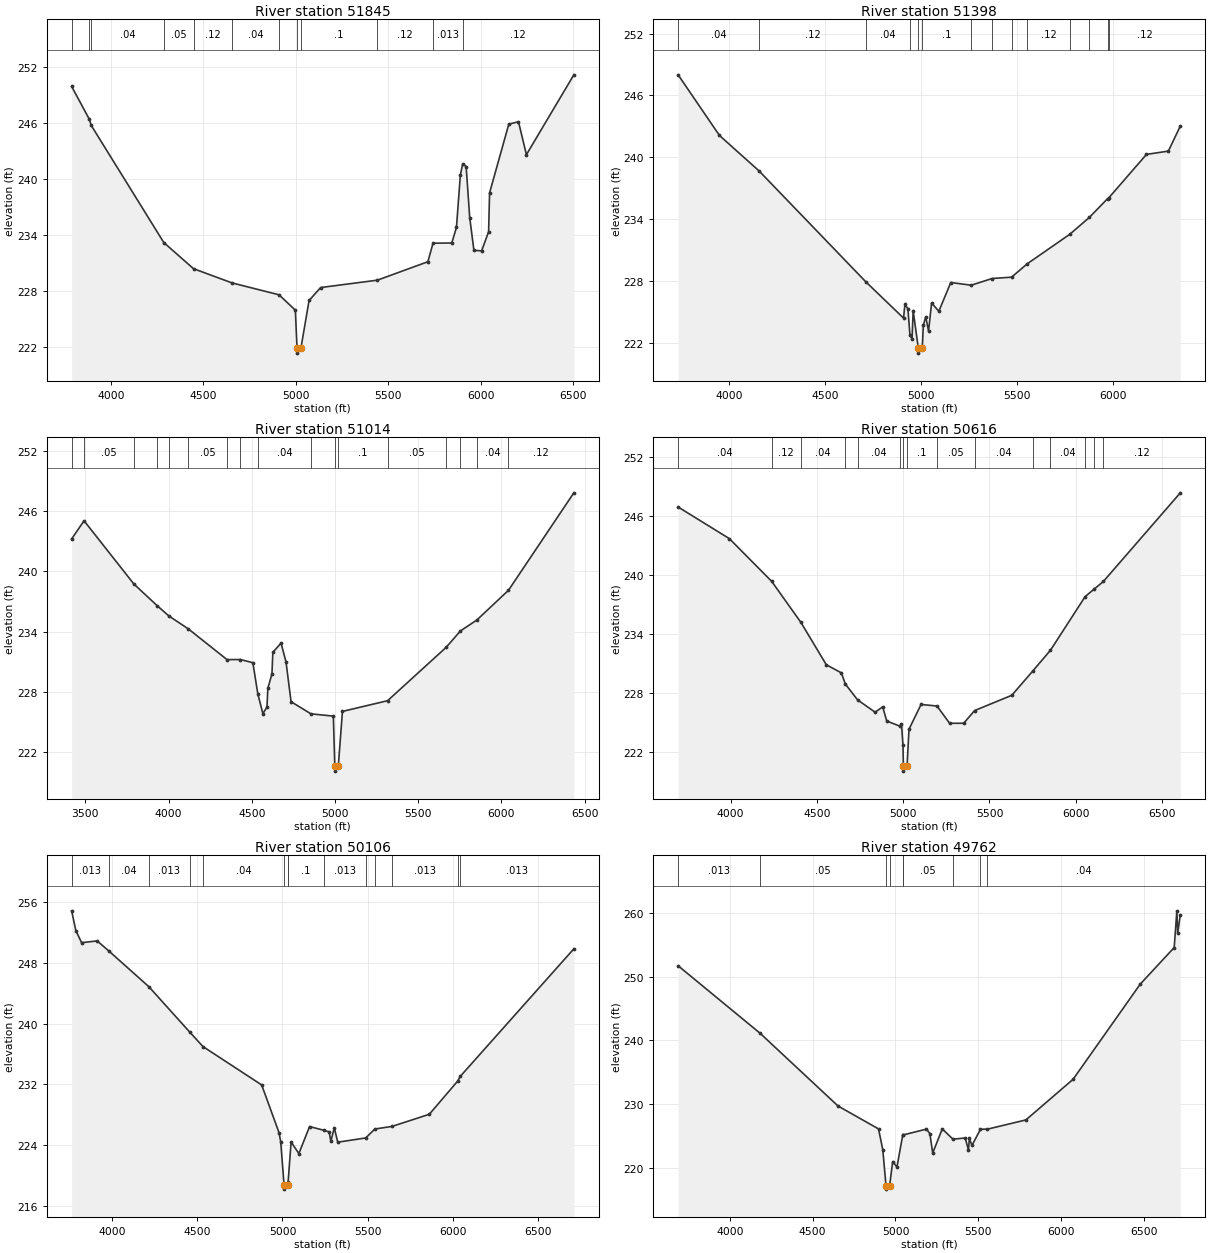
Type RM Length L Ch R = 1,51845,447,447,447
BEGIN DESCRIPTION:
Mapping XS 72b3f150
END DESCRIPTION:
XS GIS Cut Line= 3
      2503216.93     13553141.47      2503690.89     13552006.05
      2504138.70     13550589.72
#Sta/Elev= 30
  3788.1  249.93  3884.0  246.40  3893.7  245.76  4286.4  233.18  4447.2  230.37
  4656.4  228.84  4909.6  227.57  4997.9  225.92  5007.0  221.81  5007.5  221.31
  5027.7  221.81  5072.0  226.96  5134.9  228.35  5441.4  229.14  5714.6  231.12
  5742.3  233.11  5843.8  233.13  5869.1  234.80  5890.1  240.41  5902.9  241.62
  5921.5  241.34  5940.8  235.86  5963.5  232.34  6005.4  232.29  6043.0  234.35
  6048.2  238.51  6152.3  245.89  6204.6  246.14  6247.4  242.61  6503.9  251.18
#Mann=12,-1,0
  3788.1    0.04       0  3884.0    0.05       0  3893.7    0.04       0
  4286.4    0.05       0  4447.2    0.12       0  4656.4    0.04       0
  4909.6     0.1       0  5007.0    0.05       0  5027.7     0.1       0
  5441.4    0.12       0  5742.3   0.013       0  5902.9    0.12       0
Bank Sta=5007,5027.7
Exp/Cntr=0.3,0.1

Type RM Length L Ch R = 1,51398,384,384,384
BEGIN DESCRIPTION:
Mapping XS 36ef01b9
END DESCRIPTION:
XS GIS Cut Line= 3
      2503446.09     13553261.27      2504123.18     13552094.59
      2504456.53     13550870.60
#Sta/Elev= 30
  3734.8  248.00  3950.2  242.12  4157.1  238.67  4713.1  227.92  4909.8  224.40
  4916.8  225.72  4932.5  225.31  4943.1  222.75  4954.1  222.39  4959.9  225.12
  4986.6  221.50  4987.1  221.00  5007.6  221.50  5012.9  223.70  5025.4  224.53
  5040.2  223.14  5055.9  225.86  5093.7  225.06  5155.9  227.85  5262.7  227.59
  5371.5  228.24  5472.9  228.37  5555.5  229.68  5777.0  232.54  5878.4  234.17
  5973.0  235.98  5979.8  236.07  6176.0  240.28  6290.1  240.60  6352.3  243.03
#Mann=14,-1,0
  3734.8    0.04       0  4157.1    0.12       0  4713.1    0.04       0
  4943.1     0.1       0  4986.6    0.05       0  5007.6     0.1       0
  5262.7    0.05       0  5371.5    0.12       0  5472.9    0.05       0
  5555.5    0.12       0  5777.0   0.013       0  5878.4    0.12       0
  5973.0    0.03       0  5979.8    0.12       0
Bank Sta=4986.6,5007.6
Exp/Cntr=0.3,0.1

Type RM Length L Ch R = 1,51014,398,398,398
BEGIN DESCRIPTION:
Mapping XS a0d1b024
END DESCRIPTION:
XS GIS Cut Line= 3
      2503867.98     13553651.88      2504461.72     13552105.01
      2504654.16     13550757.99
#Sta/Elev= 30
  3417.9  243.25  3492.4  245.06  3792.3  238.74  3932.1  236.58  4002.0  235.56
  4118.9  234.27  4351.6  231.20  4432.3  231.21  4506.8  230.89  4536.7  227.77
  4566.9  225.81  4591.5  226.46  4596.9  228.34  4621.5  229.78  4626.9  231.93
  4676.2  232.85  4706.2  230.95  4736.3  227.00  4855.6  225.79  4990.4  225.56
  4999.2  220.57  4999.7  220.07  5020.2  220.57  5045.1  226.03  5316.3  227.10
  5667.9  232.42  5753.8  234.06  5853.0  235.16  6042.7  238.12  6435.5  247.85
#Mann=17,-1,0
  3417.9    0.04       0  3492.4    0.05       0  3792.3    0.04       0
  3932.1    0.05       0  4002.0    0.04       0  4118.9    0.05       0
  4351.6    0.12       0  4432.3    0.05       0  4536.7    0.04       0
  4855.6     0.1       0  4999.2    0.05       0  5020.2     0.1       0
  5316.3    0.05       0  5667.9    0.12       0  5753.8   0.013       0
  5853.0    0.04       0  6042.7    0.12       0
Bank Sta=4999.2,5020.2
Exp/Cntr=0.3,0.1

Type RM Length L Ch R = 1,50616,510,510,510
BEGIN DESCRIPTION:
Mapping XS 2cb08812
END DESCRIPTION:
XS GIS Cut Line= 4
      2504242.99     13553573.73      2504779.43     13552328.97
      2504909.64     13551662.30      2504764.01     13550798.89
#Sta/Elev= 30
  3695.6  246.90  3992.5  243.69  4237.9  239.35  4406.9  235.19  4554.5  230.88
  4641.6  230.06  4664.8  228.92  4736.0  227.31  4837.6  226.06  4881.1  226.61
  4904.6  225.17  4979.8  224.65  4990.0  224.85  4998.7  222.74  5001.2  220.58
  5001.7  220.08  5022.4  220.58  5033.6  224.33  5103.5  226.85  5195.9  226.69
  5269.0  224.94  5350.6  224.94  5413.9  226.23  5629.3  227.78  5753.1  230.29
  5853.6  232.36  6054.4  237.80  6106.8  238.57  6160.1  239.34  6605.9  248.34
#Mann=15,-1,0
  3695.6    0.04       0  4237.9    0.12       0  4406.9    0.04       0
  4664.8    0.05       0  4736.0    0.04       0  4979.8     0.1       0
  5001.2    0.05       0  5022.4     0.1       0  5195.9    0.05       0
  5413.9    0.04       0  5753.1    0.12       0  5853.6    0.04       0
  6054.4   0.013       0  6106.8    0.04       0  6160.1    0.12       0
Bank Sta=5001.2,5022.4
Exp/Cntr=0.3,0.1

Type RM Length L Ch R = 1,50106,344,344,344
BEGIN DESCRIPTION:
Mapping XS e591c14d
END DESCRIPTION:
XS GIS Cut Line= 3
      2505404.43     13553792.50      2505185.68     13552516.47
      2504930.77     13550888.14
#Sta/Elev= 30
  3764.8  254.87  3789.3  252.27  3823.1  250.67  3914.5  250.90  3983.5  249.56
  4217.1  244.87  4457.5  238.86  4534.4  236.97  4878.3  231.91  4979.8  225.63
  4989.9  224.43  5009.6  218.67  5010.1  218.17  5031.0  218.67  5033.2  219.08
  5050.8  224.38  5096.3  222.86  5159.0  226.42  5241.3  225.94  5273.5  225.72
  5283.6  224.48  5303.9  226.26  5324.1  224.36  5488.0  224.92  5541.9  226.10
  5642.1  226.44  5860.6  228.04  6026.6  232.41  6042.9  233.06  6707.6  249.86
#Mann=14,-1,0
  3764.8   0.013       0  3983.5    0.04       0  4217.1   0.013       0
  4457.5    0.05       0  4534.4    0.04       0  5009.6    0.04       0
  5031.0    0.04       0  5033.2     0.1       0  5241.3   0.013       0
  5488.0    0.05       0  5541.9    0.04       0  5642.1   0.013       0
  6026.6    0.04       0  6042.9   0.013       0
Bank Sta=5009.6,5031
Exp/Cntr=0.3,0.1

Type RM Length L Ch R = 1,49762,641,641,641
BEGIN DESCRIPTION:
Mapping XS 01295208
END DESCRIPTION:
XS GIS Cut Line= 3
      2505602.35     13553797.67      2505513.81     13552500.84
      2505196.31     13550798.85
#Sta/Elev= 30
  3688.0  251.69  4183.1  241.10  4652.9  229.71  4897.7  226.11  4923.5  222.83
  4942.9  217.17  4943.4  216.67  4964.3  217.17  4983.3  220.99  5008.8  220.13
  5044.5  225.23  5047.3  225.17  5187.1  226.08  5207.4  225.38  5224.7  222.34
  5282.5  226.11  5346.8  224.50  5421.0  224.69  5440.6  222.78  5445.7  224.64
  5461.7  223.52  5513.1  226.06  5554.9  226.07  5787.2  227.52  6072.1  233.89
  6477.4  248.81  6682.4  254.55  6698.4  260.30  6703.5  256.83  6719.2  259.66
#Mann=9,-1,0
  3688.0   0.013       0  4183.1    0.05       0  4942.9    0.05       0
  4964.3    0.05       0  5044.5    0.03       0  5047.3    0.05       0
  5346.8    0.03       0  5513.1    0.05       0  5554.9    0.04       0
Bank Sta=4942.9,4964.3
Exp/Cntr=0.3,0.1

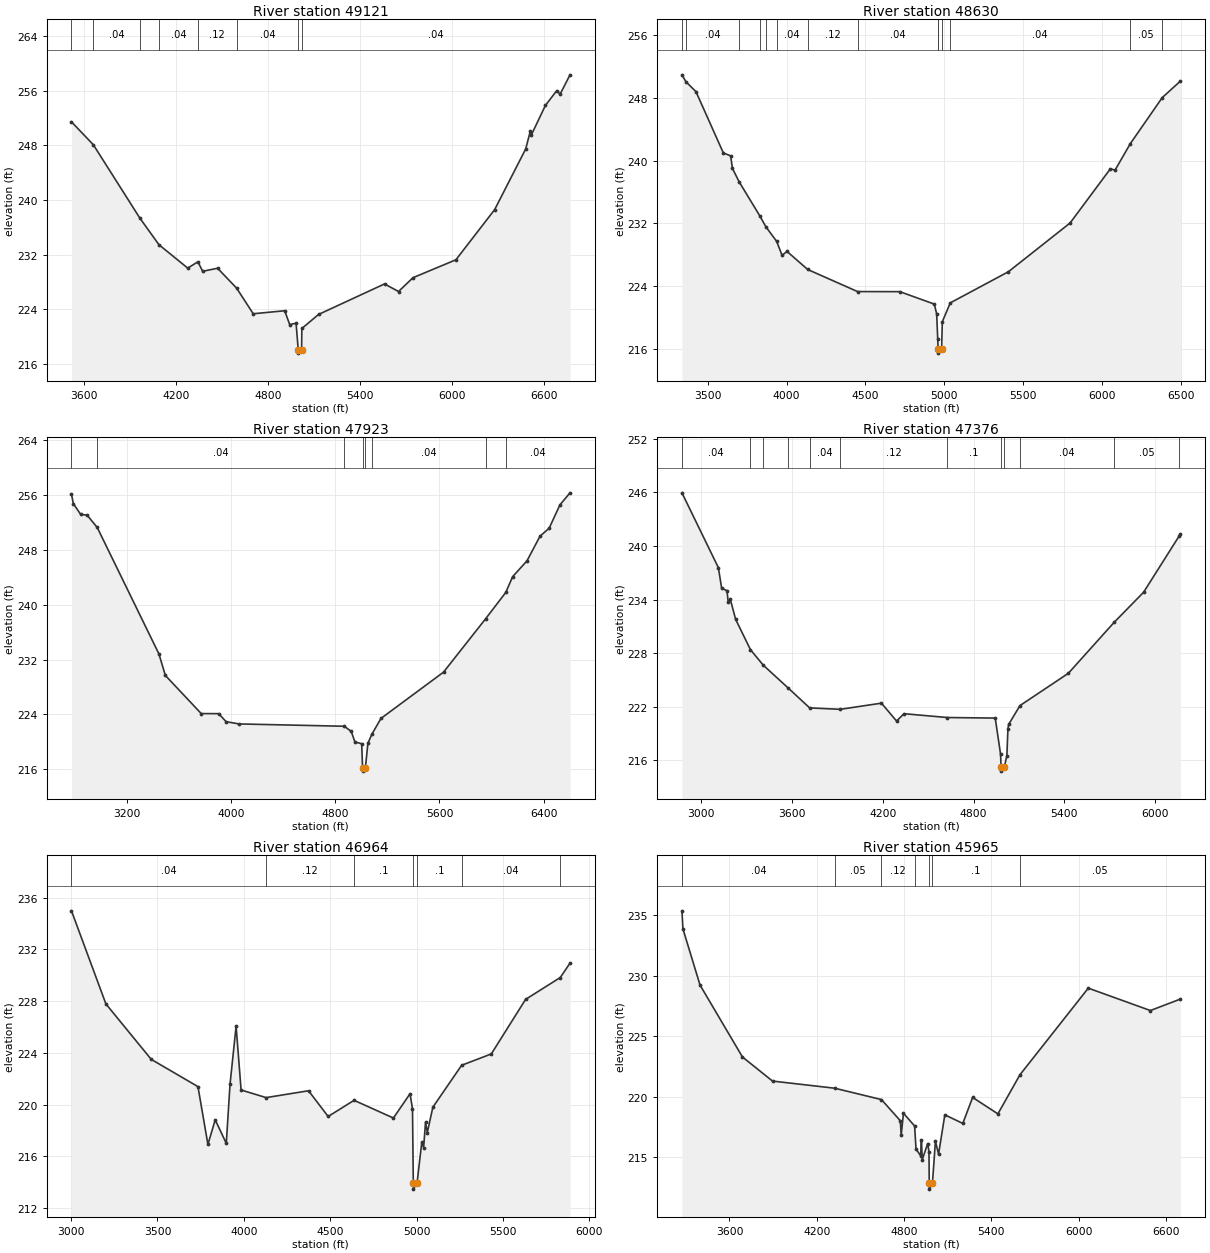
Type RM Length L Ch R = 1,49121,491,491,491
BEGIN DESCRIPTION:
Mapping XS d105d122
END DESCRIPTION:
XS GIS Cut Line= 3
      2505664.84     13553787.34      2506091.93     13552422.72
      2505461.71     13550714.36
#Sta/Elev= 30
  3519.2  251.46  3662.0  248.10  3964.4  237.38  4089.5  233.46  4277.2  230.03
  4343.8  230.95  4374.6  229.56  4471.9  230.01  4595.5  227.11  4704.4  223.34
  4909.6  223.78  4942.1  221.76  4983.8  221.95  4997.9  218.07  4998.4  217.57
  5019.8  218.07  5021.3  221.18  5130.6  223.24  5560.5  227.71  5651.8  226.60
  5746.1  228.62  6026.1  231.25  6278.7  238.60  6481.1  247.49  6511.5  250.12
  6516.9  249.49  6609.4  253.86  6683.5  256.03  6705.4  255.51  6770.0  258.35
#Mann=8,-1,0
  3519.2   0.013       0  3662.0    0.04       0  3964.4   0.013       0
  4089.5    0.04       0  4343.8    0.12       0  4595.5    0.04       0
  4997.9    0.04       0  5019.8    0.04       0
Bank Sta=4997.9,5019.8
Exp/Cntr=0.3,0.1

Type RM Length L Ch R = 1,48630,707,707,707
BEGIN DESCRIPTION:
Mapping XS 3c0b26e3
END DESCRIPTION:
XS GIS Cut Line= 3
      2505701.29     13553771.71      2506513.81     13552381.05
      2506742.98     13550844.58
#Sta/Elev= 30
  3335.6  250.95  3361.5  250.05  3424.4  248.81  3598.2  240.98  3644.5  240.60
  3656.1  239.00  3698.5  237.29  3829.9  232.93  3868.4  231.54  3936.8  229.68
  3971.0  227.90  4002.4  228.40  4133.7  226.09  4450.2  223.27  4718.2  223.26
  4937.3  221.67  4952.3  220.41  4959.0  217.17  4961.6  215.91  4962.1  215.41
  4983.5  215.91  4988.0  219.42  5038.7  221.83  5407.3  225.80  5799.1  232.03
  6054.4  238.94  6084.7  238.79  6181.2  242.16  6384.3  248.05  6499.7  250.16
#Mann=14,-1,0
  3335.6   0.013       0  3361.5    0.04       0  3698.5    0.03       0
  3829.9   0.013       0  3868.4    0.03       0  3936.8    0.04       0
  4133.7    0.12       0  4450.2    0.04       0  4959.0    0.12       0
  4961.6    0.05       0  4983.5    0.12       0  5038.7    0.04       0
  6181.2    0.05       0  6384.3    0.12       0
Bank Sta=4961.6,4983.5
Exp/Cntr=0.3,0.1

Type RM Length L Ch R = 1,47923,547,547,547
BEGIN DESCRIPTION:
FIVEMILE CREEK 72.0
END DESCRIPTION:
XS GIS Cut Line= 3
      2505574.97     13553925.03      2507175.00     13552375.00
      2507075.00     13550775.03
#Sta/Elev= 30
  2772.2  256.16  2786.3  254.77  2842.9  253.19  2892.5  253.08  2969.9  251.29
  3444.0  232.83  3493.7  229.68  3769.4  224.11  3903.7  224.10  3960.3  222.93
  4059.3  222.60  4869.3  222.26  4922.1  221.50  4950.4  219.97  5002.4  219.71
  5008.9  216.21  5009.4  215.71  5030.9  216.21  5050.0  219.77  5079.9  221.07
  5150.2  223.40  5631.1  230.16  5954.4  237.95  6109.5  241.80  6162.2  244.10
  6272.4  246.41  6372.6  250.01  6442.7  251.17  6525.4  254.58  6603.0  256.34
#Mann=8,-1,0
  2772.2   0.013       0  2969.9    0.04       0  4869.3    0.12       0
  5008.9    0.05       0  5030.9    0.12       0  5079.9    0.04       0
  5954.4    0.05       0  6109.5    0.04       0
Bank Sta=5008.9,5030.9
Exp/Cntr=0.3,0.1

Type RM Length L Ch R = 1,47376,412,412,412
BEGIN DESCRIPTION:
FIVEMILE CREEK 71.0
END DESCRIPTION:
XS GIS Cut Line= 3
      2506024.96     13554025.03      2507625.00     13552625.00
      2507824.99     13551475.04
#Sta/Elev= 30
  2873.9  245.95  3114.5  237.57  3136.4  235.25  3171.5  235.00  3179.1  233.74
  3192.9  234.06  3228.4  231.79  3326.4  228.39  3410.7  226.66  3574.2  224.12
  3717.6  221.87  3919.3  221.71  4191.8  222.40  4291.5  220.40  4340.8  221.22
  4627.3  220.79  4943.5  220.73  4978.6  216.69  4981.9  215.29  4982.4  214.79
  5003.9  215.29  5020.3  216.51  5027.3  219.52  5032.3  220.03  5107.0  222.13
  5426.3  225.74  5728.4  231.44  5923.6  234.82  6157.9  241.10  6167.2  241.35
#Mann=12,-1,0
  2873.9    0.04       0  3326.4    0.03       0  3410.7    0.04       0
  3574.2    0.03       0  3717.6    0.04       0  3919.3    0.12       0
  4627.3     0.1       0  4981.9    0.05       0  5003.9     0.1       0
  5107.0    0.04       0  5728.4    0.05       0  6157.9    0.12       0
Bank Sta=4981.9,5003.9
Exp/Cntr=0.3,0.1

Type RM Length L Ch R = 1,46964,999,999,999
BEGIN DESCRIPTION:
FIVEMILE CREEK 70.0
END DESCRIPTION:
XS GIS Cut Line= 3
      2506324.99     13554225.01      2507825.00     13553025.00
      2508175.00     13552125.01
#Sta/Elev= 30
  3002.2  234.99  3201.5  227.79  3464.0  223.50  3734.6  221.39  3792.2  216.92
  3834.6  218.82  3898.6  217.00  3920.3  221.57  3955.5  226.07  3984.3  221.13
  4129.4  220.54  4374.9  221.07  4488.5  219.08  4638.5  220.33  4866.3  218.96
  4962.6  220.84  4976.8  219.67  4981.5  213.96  4982.0  213.46  5003.5  213.96
  5030.4  217.07  5041.2  216.68  5052.3  218.64  5062.6  217.84  5094.8  219.80
  5261.3  223.04  5433.2  223.92  5631.7  228.14  5832.4  229.83  5888.8  230.94
#Mann=7,-1,0
  3002.2    0.04       0  4129.4    0.12       0  4638.5     0.1       0
  4981.5    0.05       0  5003.5     0.1       0  5261.3    0.04       0
  5832.4    0.05       0
Bank Sta=4981.5,5003.5
Exp/Cntr=0.3,0.1

Type RM Length L Ch R = 1,45965,1097,1097,1097
BEGIN DESCRIPTION:
Mapping XS aa4ec11a
END DESCRIPTION:
XS GIS Cut Line= 3
      2506414.85     13554573.76      2508117.97     13553589.39
      2508711.72     13552256.05
#Sta/Elev= 30
  3273.4  235.35  3280.1  233.86  3397.8  229.21  3689.4  223.27  3896.0  221.28
  4323.5  220.69  4644.9  219.75  4774.5  218.00  4780.3  216.81  4796.0  218.62
  4872.7  217.57  4882.2  215.67  4913.7  215.11  4919.5  216.37  4925.3  214.79
  4962.6  216.12  4971.4  215.43  4973.1  212.85  4973.6  212.35  4995.2  212.85
  5015.7  216.31  5037.2  215.24  5080.3  218.49  5203.8  217.78  5271.4  219.93
  5445.0  218.57  5596.6  221.80  6066.3  228.96  6493.3  227.11  6700.1  228.06
#Mann=7,-1,0
  3273.4    0.04       0  4323.5    0.05       0  4644.9    0.12       0
  4872.7     0.1       0  4973.1    0.05       0  4995.2     0.1       0
  5596.6    0.05       0
Bank Sta=4973.1,4995.2
Exp/Cntr=0.3,0.1

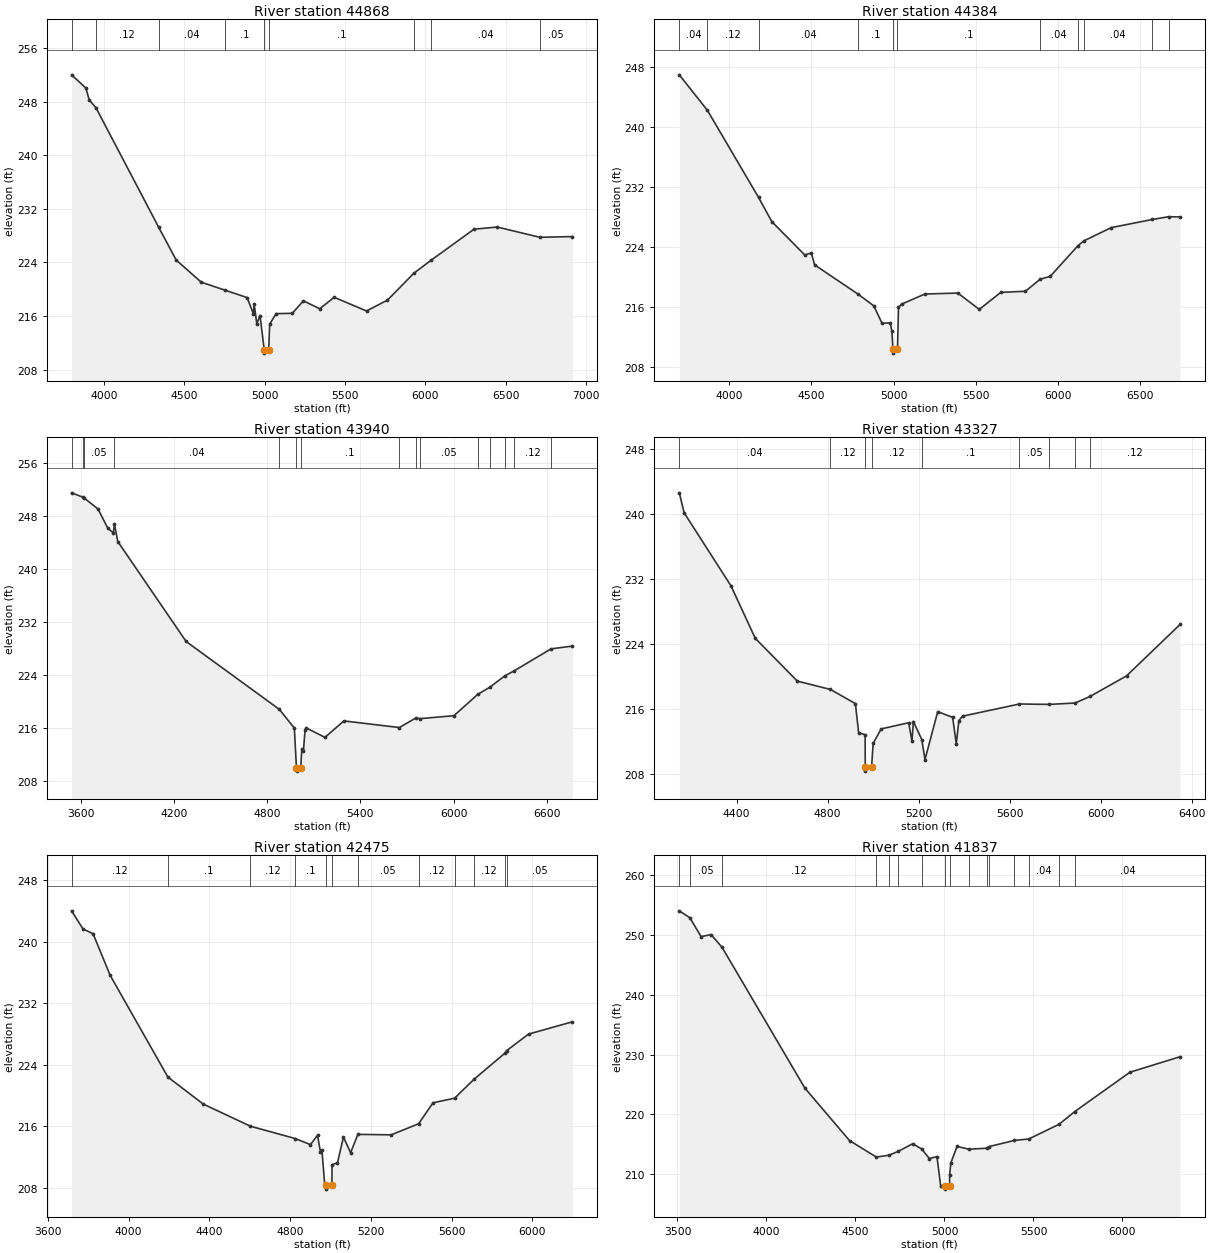
Type RM Length L Ch R = 1,44868,484,484,484
BEGIN DESCRIPTION:
Mapping XS 88bee38c
END DESCRIPTION:
XS GIS Cut Line= 3
      2508779.43     13555453.94      2508690.89     13554011.26
      2508831.51     13552349.90
#Sta/Elev= 30
  3800.3  251.98  3889.4  250.00  3909.4  248.26  3952.3  247.05  4340.9  229.27
  4450.5  224.35  4606.5  221.04  4754.3  219.85  4891.3  218.75  4930.0  216.36
  4935.1  217.80  4951.4  214.84  4971.4  216.07  4997.7  210.96  4998.2  210.46
  5025.3  210.96  5031.6  214.79  5071.6  216.35  5171.8  216.40  5241.3  218.27
  5342.3  217.08  5432.6  218.79  5633.3  216.75  5763.8  218.37  5927.7  222.38
  6032.6  224.28  6301.5  228.95  6446.2  229.27  6711.1  227.74  6913.0  227.85
#Mann=9,-1,0
  3800.3    0.04       0  3952.3    0.12       0  4340.9    0.04       0
  4754.3     0.1       0  4997.7    0.05       0  5025.3     0.1       0
  5927.7    0.12       0  6032.6    0.04       0  6711.1    0.05       0
Bank Sta=4997.7,5025.3
Exp/Cntr=0.3,0.1

Type RM Length L Ch R = 1,44384,444,444,444
BEGIN DESCRIPTION:
Mapping XS 5f843b2c
END DESCRIPTION:
XS GIS Cut Line= 3
      2509154.43     13555427.91      2509128.39     13553953.97
      2508993.14     13552388.17
#Sta/Elev= 30
  3696.1  246.97  3867.3  242.23  4177.9  230.63  4259.1  227.39  4459.1  222.95
  4499.1  223.22  4519.1  221.63  4784.3  217.71  4879.2  216.16  4929.2  213.84
  4979.2  213.90  4989.2  212.76  4995.4  210.36  4995.9  209.86  5023.0  210.36
  5029.2  215.98  5049.2  216.40  5189.3  217.74  5390.1  217.87  5520.5  215.69
  5651.0  217.96  5801.6  218.11  5891.0  219.72  5952.1  220.10  6120.5  224.18
  6155.8  224.82  6323.5  226.60  6572.4  227.68  6672.2  228.05  6741.9  228.02
#Mann=11,-1,0
  3696.1    0.04       0  3867.3    0.12       0  4177.9    0.04       0
  4784.3     0.1       0  4995.4    0.05       0  5023.0     0.1       0
  5891.0    0.04       0  6120.5    0.05       0  6155.8    0.04       0
  6572.4    0.05       0  6672.2    0.04       0
Bank Sta=4995.4,5023
Exp/Cntr=0.3,0.1

Type RM Length L Ch R = 1,43940,613,613,613
BEGIN DESCRIPTION:
Mapping XS 7bf69f92
END DESCRIPTION:
XS GIS Cut Line= 4
      2510269.01     13555349.80      2509628.39     13554578.97
      2509206.52     13552959.18      2509190.89     13552412.31
#Sta/Elev= 30
  3541.4  251.49  3616.7  250.81  3622.3  250.71  3711.1  249.07  3774.9  246.14
  3810.0  245.46  3817.3  246.76  3838.7  244.15  4278.7  229.08  4879.0  218.84
  4975.2  216.02  4988.6  210.04  4989.1  209.54  5016.3  210.04  5023.1  212.92
  5033.5  212.57  5043.8  215.69  5051.0  216.05  5172.5  214.63  5294.1  217.11
  5650.8  216.11  5755.3  217.53  5784.2  217.45  6002.5  217.90  6155.4  221.11
  6232.5  222.18  6331.2  223.92  6388.4  224.64  6627.3  227.97  6764.6  228.39
#Mann=15,-1,0
  3541.4    0.05       0  3616.7    0.12       0  3622.3    0.05       0
  3817.3    0.04       0  4879.0     0.1       0  4988.6    0.05       0
  5016.3     0.1       0  5650.8    0.05       0  5755.3    0.12       0
  5784.2    0.05       0  6155.4    0.12       0  6232.5    0.05       0
  6331.2    0.04       0  6388.4    0.12       0  6627.3    0.04       0
Bank Sta=4988.6,5016.3
Exp/Cntr=0.3,0.1

Type RM Length L Ch R = 1,43327,852,852,852
BEGIN DESCRIPTION:
FIVEMILE CREEK 65.0
END DESCRIPTION:
XS GIS Cut Line= 3
      2510575.01     13554525.01      2509825.00     13553625.00
      2509325.01     13552725.01
#Sta/Elev= 30
  4148.4  242.59  4169.9  240.12  4375.6  231.13  4482.3  224.67  4667.1  219.40
  4812.8  218.37  4922.3  216.63  4936.6  213.05  4965.2  212.79  4965.7  208.81
  4966.2  208.31  4993.5  208.81  5000.4  211.73  5035.5  213.51  5156.6  214.27
  5170.9  212.01  5177.4  214.42  5214.3  212.19  5228.2  209.73  5284.2  215.64
  5349.7  214.93  5365.7  211.69  5377.2  214.54  5393.2  215.08  5643.6  216.58
  5774.6  216.53  5887.9  216.70  5953.8  217.51  6113.9  220.04  6349.5  226.38
#Mann=9,-1,0
  4148.4    0.04       0  4812.8    0.12       0  4965.7    0.05       0
  4993.5    0.12       0  5214.3     0.1       0  5643.6    0.05       0
  5774.6    0.12       0  5887.9    0.05       0  5953.8    0.12       0
Bank Sta=4965.7,4993.5
Exp/Cntr=0.3,0.1

Type RM Length L Ch R = 1,42475,638,638,638
BEGIN DESCRIPTION:
Mapping XS 16dda14f
END DESCRIPTION:
XS GIS Cut Line= 3
      2511086.74     13554323.78      2510242.97     13553370.64
      2509534.62     13552391.44
#Sta/Elev= 30
  3717.1  244.01  3774.0  241.64  3823.4  241.04  3908.7  235.60  4194.4  222.39
  4369.6  218.88  4603.5  216.00  4826.2  214.39  4900.7  213.61  4935.8  214.83
  4950.1  212.67  4957.5  212.93  4971.0  208.53  4979.1  208.32  4979.6  207.82
  5006.9  208.32  5007.7  211.00  5034.7  211.25  5064.1  214.59  5099.7  212.56
  5135.5  214.94  5300.8  214.88  5436.6  216.32  5508.1  219.05  5614.7  219.64
  5711.3  222.11  5863.0  225.47  5872.8  225.83  5981.5  227.98  6198.6  229.58
#Mann=12,-1,0
  3717.1    0.12       0  4194.4     0.1       0  4603.5    0.12       0
  4826.2     0.1       0  4979.1    0.05       0  5006.9     0.1       0
  5135.5    0.05       0  5436.6    0.12       0  5614.7    0.05       0
  5711.3    0.12       0  5863.0    0.04       0  5872.8    0.05       0
Bank Sta=4979.1,5006.9
Exp/Cntr=0.3,0.1

Type RM Length L Ch R = 1,41837,633,633,633
BEGIN DESCRIPTION:
Mapping XS 7a1b1dcc
END DESCRIPTION:
XS GIS Cut Line= 3
      2511628.40     13554162.31      2510758.60     13553037.30
      2509711.74     13552120.65
#Sta/Elev= 30
  3510.4  254.05  3570.2  252.88  3632.8  249.73  3689.0  250.08  3750.5  247.95
  4216.0  224.38  4466.9  215.60  4618.0  212.84  4688.8  213.16  4741.4  213.82
  4821.8  215.08  4872.5  214.18  4915.1  212.60  4957.9  212.92  4978.8  208.02
  5000.9  207.98  5001.4  207.48  5028.8  207.98  5029.1  209.87  5035.8  211.86
  5070.9  214.62  5138.3  214.16  5237.9  214.33  5252.0  214.61  5393.4  215.63
  5473.5  215.87  5643.1  218.32  5732.6  220.47  6041.8  227.04  6323.9  229.64
#Mann=16,-1,0
  3510.4    0.04       0  3570.2    0.05       0  3750.5    0.12       0
  4618.0    0.04       0  4688.8    0.12       0  4741.4    0.05       0
  4872.5    0.12       0  5000.9    0.05       0  5028.8    0.12       0
  5138.3    0.05       0  5237.9    0.12       0  5252.0    0.05       0
  5393.4    0.12       0  5473.5    0.04       0  5643.1    0.12       0
  5732.6    0.04       0
Bank Sta=5000.9,5028.8
Exp/Cntr=0.3,0.1