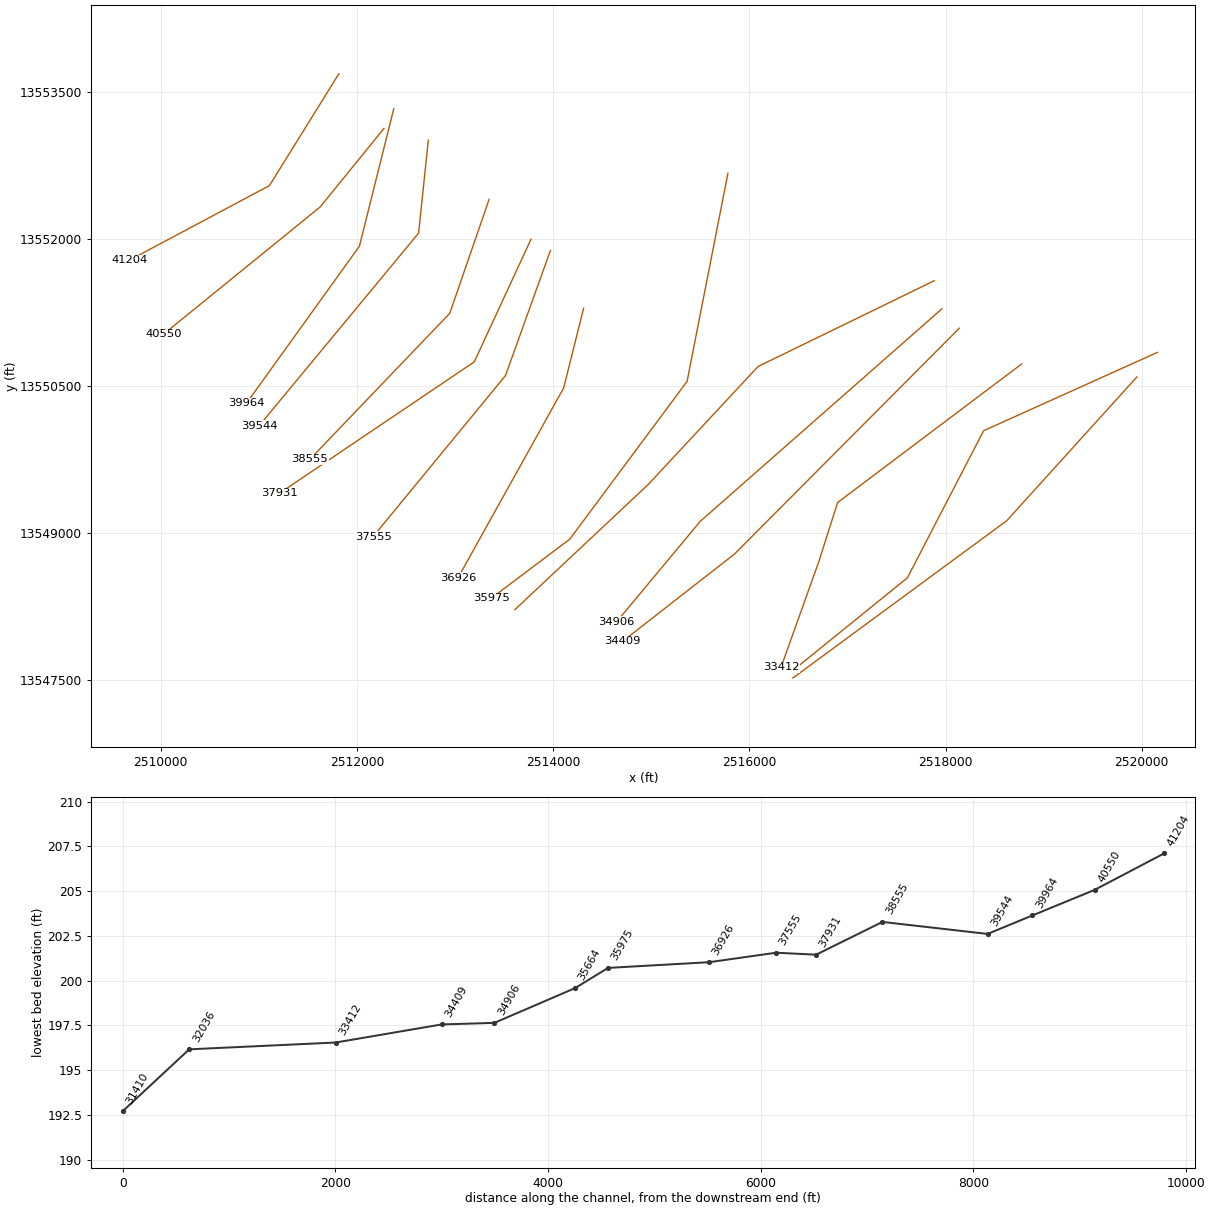
HEC-RAS study FIVEMILE CREEK.prj: FIVEMILE CREEK Base Level Engineering

--- FIVEMILE CREEK.g01 (geometry) --- (continued)

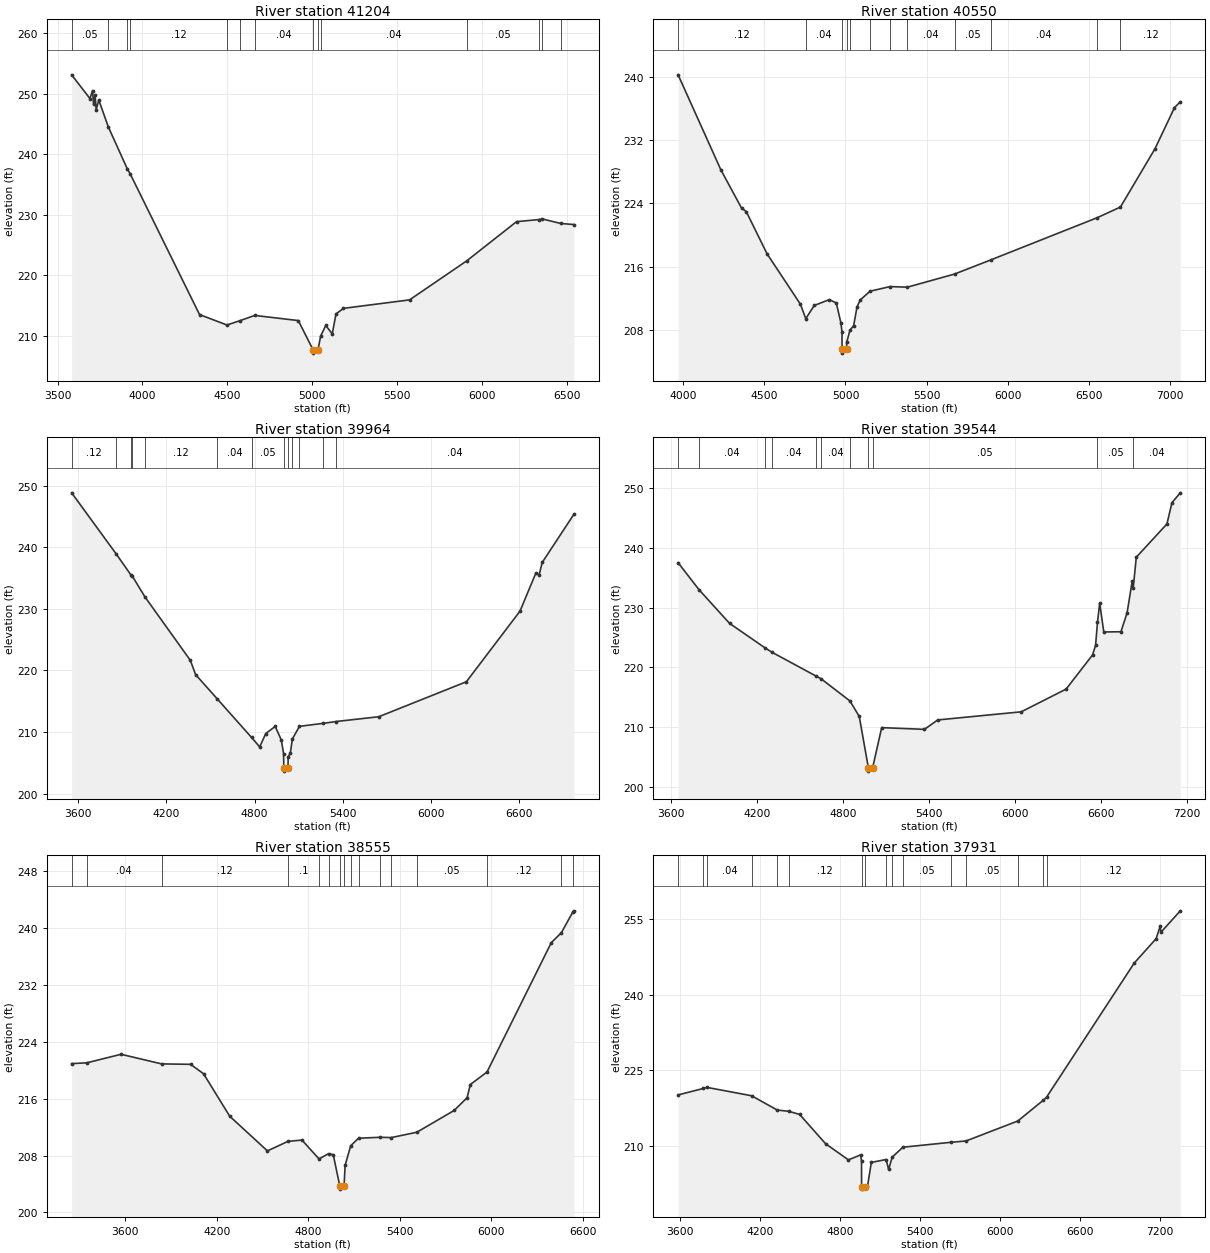
Type RM Length L Ch R = 1,41204,654,654,654
BEGIN DESCRIPTION:
Mapping XS 650acb15
END DESCRIPTION:
XS GIS Cut Line= 3
      2511815.89     13553683.14      2511107.56     13552542.51
      2509680.48     13551782.10
#Sta/Elev= 30
  3583.1  253.10  3690.9  249.18  3706.3  250.50  3712.1  248.21  3721.6  249.73
  3727.5  247.28  3742.9  248.95  3799.4  244.48  3910.9  237.57  3928.4  236.72
  4336.8  213.48  4498.2  211.76  4572.8  212.45  4661.9  213.34  4919.1  212.49
  5006.6  207.61  5007.1  207.11  5034.5  207.61  5050.9  209.95  5080.8  211.68
  5119.1  210.30  5141.0  213.58  5185.0  214.51  5574.6  215.91  5911.1  222.35
  6205.2  228.84  6337.8  229.18  6355.2  229.30  6464.9  228.54  6542.8  228.36
#Mann=14,-1,0
  3583.1    0.05       0  3799.4    0.12       0  3910.9    0.05       0
  3928.4    0.12       0  4498.2    0.04       0  4572.8    0.05       0
  4661.9    0.04       0  5006.6    0.04       0  5034.5    0.04       0
  5050.9    0.04       0  5911.1    0.05       0  6337.8    0.12       0
  6355.2    0.05       0  6464.9    0.04       0
Bank Sta=5006.6,5034.5
Exp/Cntr=0.3,0.1

Type RM Length L Ch R = 1,40550,586,586,586
BEGIN DESCRIPTION:
FIVEMILE CREEK 60.0
END DESCRIPTION:
XS GIS Cut Line= 3
      2512274.98     13553124.98      2511625.00     13552325.00
      2510025.00     13551025.00
#Sta/Elev= 30
  3969.5  240.23  4232.4  228.24  4360.2  223.39  4389.0  222.96  4516.8  217.63
  4723.0  211.24  4755.5  209.42  4807.7  211.09  4900.4  211.83  4943.5  211.41
  4972.2  208.86  4978.7  207.75  4979.1  205.57  4979.6  205.07  5007.1  205.57
  5007.4  206.42  5027.4  207.95  5050.5  208.55  5071.4  210.94  5092.2  211.81
  5151.3  212.89  5275.2  213.48  5380.8  213.40  5671.7  215.06  5896.4  216.86
  6550.2  222.18  6693.3  223.53  6905.9  230.89  7025.9  236.08  7061.8  236.83
#Mann=12,-1,0
  3969.5    0.12       0  4755.5    0.04       0  4979.1    0.04       0
  5007.1    0.04       0  5027.4    0.03       0  5151.3    0.05       0
  5275.2    0.03       0  5380.8    0.04       0  5671.7    0.05       0
  5896.4    0.04       0  6550.2    0.05       0  6693.3    0.12       0
Bank Sta=4979.1,5007.1
Exp/Cntr=0.3,0.1

Type RM Length L Ch R = 1,39964,420,420,420
BEGIN DESCRIPTION:
FIVEMILE CREEK 59.0
END DESCRIPTION:
XS GIS Cut Line= 3
      2512374.99     13553324.98      2512025.00     13551925.00
      2510874.98     13550324.97
#Sta/Elev= 30
  3556.9  248.82  3859.3  238.91  3961.6  235.43  3969.6  235.28  4054.6  231.94
  4363.5  221.63  4399.5  219.31  4547.9  215.33  4779.6  209.11  4835.0  207.57
  4876.3  209.74  4940.7  210.90  4981.9  208.70  4997.4  206.49  4999.2  204.14
  4999.7  203.64  5027.7  204.14  5028.2  205.99  5042.9  206.51  5057.3  208.87
  5105.5  210.91  5267.4  211.40  5353.3  211.69  5644.5  212.47  6239.9  218.15
  6604.5  229.62  6711.8  235.77  6734.6  235.51  6755.5  237.52  6970.4  245.32
#Mann=13,-1,0
  3556.9    0.12       0  3859.3    0.05       0  3961.6    0.12       0
  3969.6    0.05       0  4054.6    0.12       0  4547.9    0.04       0
  4779.6    0.05       0  4999.2    0.05       0  5027.7    0.05       0
  5057.3    0.04       0  5105.5    0.03       0  5267.4    0.05       0
  5353.3    0.04       0
Bank Sta=4999.2,5027.7
Exp/Cntr=0.3,0.1

Type RM Length L Ch R = 1,39544,989,989,989
BEGIN DESCRIPTION:
Mapping XS f6963a6f
END DESCRIPTION:
XS GIS Cut Line= 3
      2512727.35     13553006.07      2512628.39     13552058.14
      2511003.41     13550094.62
#Sta/Elev= 30
  3649.5  237.54  3795.7  233.00  4008.4  227.37  4254.2  223.29  4302.8  222.55
  4611.2  218.54  4645.3  218.11  4848.0  214.36  4912.7  211.77  4976.5  203.11
  4977.0  202.61  5005.2  203.11  5069.0  209.90  5367.3  209.61  5459.8  211.19
  6042.0  212.55  6354.6  216.35  6539.6  222.09  6560.4  223.68  6573.8  227.53
  6589.1  230.77  6617.7  225.93  6737.5  225.97  6780.5  229.16  6815.7  234.43
  6823.2  233.36  6844.4  238.46  7058.0  244.03  7093.2  247.61  7151.3  249.25
#Mann=11,-1,0
  3649.5    0.12       0  3795.7    0.04       0  4254.2    0.12       0
  4302.8    0.04       0  4611.2    0.05       0  4645.3    0.04       0
  4848.0    0.05       0  4976.5    0.04       0  5005.2    0.05       0
  6573.8    0.05       0  6823.2    0.04       0
Bank Sta=4976.5,5005.2
Exp/Cntr=0.3,0.1

Type RM Length L Ch R = 1,38555,624,624,624
BEGIN DESCRIPTION:
Mapping XS e07f226a
END DESCRIPTION:
XS GIS Cut Line= 3
      2513347.14     13552401.90      2512946.10     13551240.43
      2511519.52     13549751.37
#Sta/Elev= 30
  3249.8  220.91  3348.8  221.02  3573.6  222.22  3839.2  220.87  4029.4  220.81
  4114.0  219.49  4285.7  213.52  4532.6  208.65  4667.6  209.99  4759.1  210.17
  4870.9  207.52  4933.1  208.26  4964.1  208.12  5006.3  203.78  5006.8  203.28
  5035.1  203.78  5041.8  206.61  5078.2  209.37  5129.8  210.43  5270.1  210.56
  5344.2  210.52  5511.8  211.27  5756.3  214.33  5841.2  216.12  5862.3  217.97
  5971.6  219.73  6392.9  237.90  6459.1  239.30  6532.8  242.16  6540.7  242.37
#Mann=16,-1,0
  3249.8    0.05       0  3348.8    0.04       0  3839.2    0.12       0
  4667.6     0.1       0  4870.9    0.12       0  4933.1     0.1       0
  5006.3    0.05       0  5035.1     0.1       0  5078.2    0.05       0
  5129.8    0.04       0  5270.1    0.05       0  5344.2    0.04       0
  5511.8    0.05       0  5971.6    0.12       0  6459.1    0.05       0
  6532.8    0.12       0
Bank Sta=5006.3,5035.1
Exp/Cntr=0.3,0.1

Type RM Length L Ch R = 1,37931,376,376,376
BEGIN DESCRIPTION:
Mapping XS 4d6d0ed0
END DESCRIPTION:
XS GIS Cut Line= 3
      2513774.24     13551995.67      2513196.10     13550745.64
      2511211.71     13549407.08
#Sta/Elev= 30
  3583.4  220.13  3772.5  221.41  3800.4  221.62  4135.7  219.96  4327.4  217.13
  4414.3  216.88  4495.9  216.26  4690.4  210.46  4862.2  207.25  4953.6  208.24
  4960.7  207.03  4961.0  201.95  4961.5  201.45  4989.9  201.95  5005.3  201.99
  5034.4  206.75  5145.1  207.32  5164.2  205.36  5191.0  207.79  5271.2  209.76
  5629.2  210.73  5745.6  211.00  6134.1  214.96  6325.7  219.08  6349.6  219.66
  7007.9  246.26  7172.8  251.11  7202.8  253.55  7208.8  252.38  7354.3  256.63
#Mann=16,-1,0
  3583.4    0.04       0  3772.5    0.12       0  3800.4    0.04       0
  4135.7    0.12       0  4327.4    0.05       0  4414.3    0.12       0
  4961.0    0.05       0  4989.9    0.12       0  5145.1    0.05       0
  5191.0    0.12       0  5271.2    0.05       0  5629.2    0.04       0
  5745.6    0.05       0  6134.1    0.04       0  6325.7    0.05       0
  6349.6    0.12       0
Bank Sta=4961,4989.9
Exp/Cntr=0.3,0.1

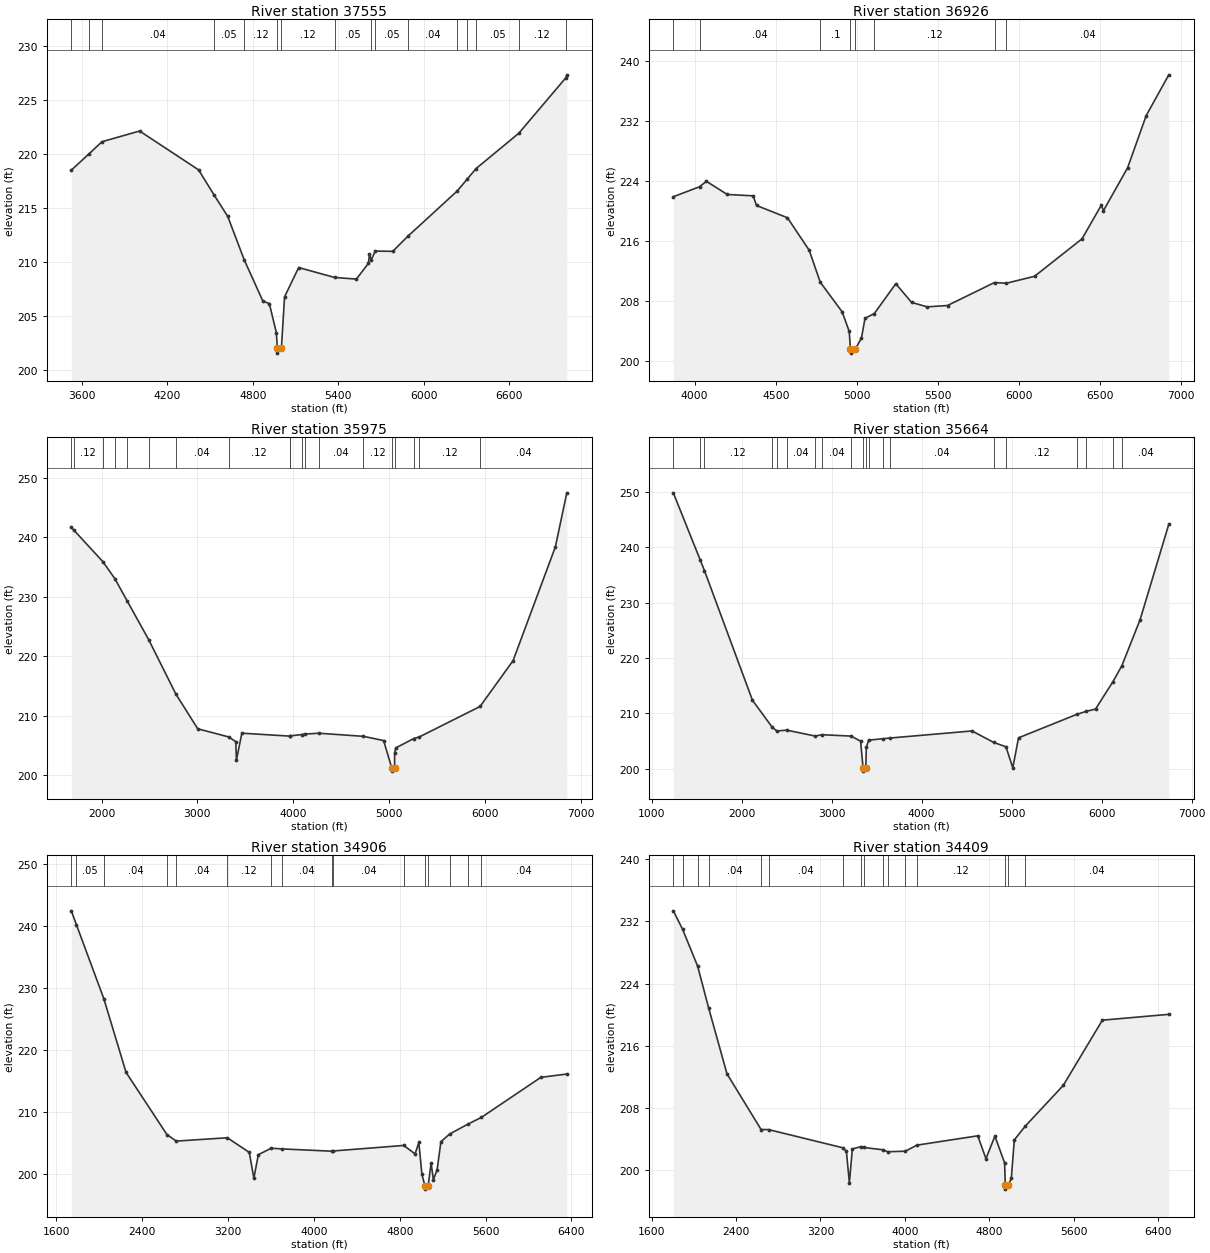
Type RM Length L Ch R = 1,37555,629,629,629
BEGIN DESCRIPTION:
Mapping XS e0521c5a
END DESCRIPTION:
XS GIS Cut Line= 3
      2513972.14     13551881.05      2513513.81     13550605.01
      2512164.88     13548964.42
#Sta/Elev= 30
  3524.5  218.49  3650.6  220.02  3739.5  221.12  4004.0  222.11  4418.2  218.52
  4528.7  216.16  4622.7  214.22  4739.5  210.17  4869.7  206.38  4915.3  206.14
  4964.8  203.44  4971.1  202.06  4971.6  201.56  5000.1  202.06  5022.2  206.77
  5121.2  209.48  5373.8  208.56  5526.6  208.41  5611.2  209.87  5618.3  210.71
  5631.0  210.18  5658.7  211.00  5782.0  210.98  5887.8  212.37  6234.0  216.55
  6306.8  217.69  6367.4  218.64  6666.9  221.90  6997.1  227.03  7004.3  227.31
#Mann=16,-1,0
  3524.5    0.04       0  3650.6    0.05       0  3739.5    0.04       0
  4528.7    0.05       0  4739.5    0.12       0  4971.1    0.05       0
  5000.1    0.12       0  5373.8    0.05       0  5631.0    0.12       0
  5658.7    0.05       0  5887.8    0.04       0  6234.0    0.05       0
  6306.8    0.04       0  6367.4    0.05       0  6666.9    0.12       0
  6997.1    0.05       0
Bank Sta=4971.1,5000.1
Exp/Cntr=0.3,0.1

Type RM Length L Ch R = 1,36926,951,951,951
BEGIN DESCRIPTION:
Mapping XS b7748fa9
END DESCRIPTION:
XS GIS Cut Line= 3
      2514310.69     13551292.53      2514107.56     13550480.01
      2513029.72     13548543.03
#Sta/Elev= 30
  3868.6  221.92  4030.2  223.25  4072.2  223.98  4201.2  222.22  4360.8  222.04
  4381.4  220.75  4572.3  219.11  4706.1  214.77  4774.2  210.51  4909.4  206.54
  4952.9  203.93  4960.6  201.53  4961.1  201.03  4989.6  201.53  5028.4  203.05
  5050.1  205.68  5107.8  206.32  5239.9  210.30  5337.1  207.81  5432.8  207.21
  5558.7  207.39  5848.6  210.46  5920.2  210.36  6095.2  211.29  6388.0  216.30
  6506.9  220.79  6520.0  220.06  6668.8  225.78  6783.6  232.76  6922.8  238.20
#Mann=8,-1,0
  3868.6    0.05       0  4030.2    0.04       0  4774.2     0.1       0
  4960.6    0.05       0  4989.6     0.1       0  5107.8    0.12       0
  5848.6    0.05       0  5920.2    0.04       0
Bank Sta=4960.6,4989.6
Exp/Cntr=0.3,0.1

Type RM Length L Ch R = 1,35975,311,311,311
BEGIN DESCRIPTION:
Mapping XS a82f7125
END DESCRIPTION:
XS GIS Cut Line= 4
      2515782.12     13552669.20      2515365.47     13550546.84
      2514170.06     13548938.34      2513369.01     13548334.96
#Sta/Elev= 30
  1685.0  241.61  1710.5  241.18  2015.0  235.86  2138.8  233.03  2266.5  229.32
  2492.5  222.77  2776.2  213.64  3003.9  207.82  3327.1  206.45  3401.3  205.65
  3407.7  202.56  3464.3  207.08  3962.3  206.59  3966.3  206.62  4087.7  206.85
  4125.1  206.94  4270.5  207.07  4733.6  206.55  4943.5  205.84  5029.2  201.21
  5029.7  200.71  5058.2  201.21  5058.3  203.78  5071.2  204.61  5257.9  206.18
  5317.1  206.46  5949.6  211.56  6294.1  219.25  6735.5  238.35  6854.8  247.43
#Mann=19,-1,0
  1685.0    0.04       0  1710.5    0.12       0  2015.0    0.05       0
  2138.8    0.12       0  2266.5   0.013       0  2492.5    0.12       0
  2776.2    0.04       0  3327.1    0.12       0  3962.3    0.04       0
  3966.3    0.12       0  4087.7    0.05       0  4125.1    0.12       0
  4270.5    0.04       0  4733.6    0.12       0  5029.2    0.05       0
  5058.2    0.12       0  5257.9    0.05       0  5317.1    0.12       0
  5949.6    0.04       0
Bank Sta=5029.2,5058.2
Exp/Cntr=0.3,0.1

Type RM Length L Ch R = 1,35664,758,758,758
BEGIN DESCRIPTION:
Mapping XS 19849589
END DESCRIPTION:
XS GIS Cut Line= 4
      2517885.19     13551572.77      2516088.35     13550697.78
      2514968.56     13549494.66      2513610.36     13548219.72
#Sta/Elev= 30
  1241.0  249.87  1538.9  237.77  1586.8  235.82  2120.4  212.38  2340.1  207.51
  2391.4  206.83  2499.3  206.99  2816.8  205.92  2894.3  206.16  3216.3  205.91
  3321.8  204.99  3349.7  200.08  3350.2  199.58  3379.1  200.08  3385.4  203.85
  3410.5  205.18  3573.9  205.44  3647.9  205.56  4559.9  206.84  4800.2  204.77
  4936.8  203.98  5012.6  200.18  5076.6  205.60  5725.2  209.85  5826.1  210.37
  5932.3  210.80  6126.0  215.76  6225.0  218.64  6427.6  226.97  6746.0  244.20
#Mann=20,-1,0
  1241.0    0.12       0  1538.9    0.05       0  1586.8    0.12       0
  2340.1    0.05       0  2391.4   0.013       0  2499.3    0.04       0
  2816.8    0.05       0  2894.3    0.04       0  3216.3    0.05       0
  3349.7    0.05       0  3379.1    0.05       0  3410.5    0.04       0
  3573.9    0.03       0  3647.9    0.04       0  4800.2    0.12       0
  4936.8    0.12       0  5725.2    0.05       0  5826.1    0.12       0
  6126.0    0.12       0  6225.0    0.04       0
Bank Sta=3349.7,3379.1
Exp/Cntr=0.3,0.1

Type RM Length L Ch R = 1,34906,497,497,497
BEGIN DESCRIPTION:
Mapping XS fc7b52bd
END DESCRIPTION:
XS GIS Cut Line= 3
      2517963.33     13551286.30      2515499.81     13549119.66
      2514645.64     13548093.61
#Sta/Elev= 30
  1740.9  242.49  1788.7  240.24  2044.3  228.30  2250.8  216.46  2631.7  206.43
  2718.9  205.38  3194.5  205.92  3398.8  203.56  3441.5  199.41  3483.3  203.19
  3602.4  204.23  3705.7  204.12  4170.6  203.75  4181.8  203.79  4838.1  204.68
  4943.4  203.31  4978.6  205.17  5007.0  200.03  5035.2  198.14  5035.7  197.64
  5064.7  198.14  5092.8  201.83  5113.7  199.17  5148.8  200.76  5184.0  205.28
  5265.4  206.52  5439.5  208.15  5560.2  209.19  6114.8  215.65  6356.7  216.19
#Mann=16,-1,0
  1740.9    0.12       0  1788.7    0.05       0  2044.3    0.04       0
  2631.7   0.013       0  2718.9    0.04       0  3194.5    0.12       0
  3602.4    0.05       0  3705.7    0.04       0  4170.6    0.03       0
  4181.8    0.04       0  4838.1    0.12       0  5035.2    0.05       0
  5064.7    0.12       0  5265.4    0.04       0  5439.5    0.12       0
  5560.2    0.04       0
Bank Sta=5035.2,5064.7
Exp/Cntr=0.3,0.1

Type RM Length L Ch R = 1,34409,997,997,997
BEGIN DESCRIPTION:
Mapping XS caf64a98
END DESCRIPTION:
XS GIS Cut Line= 3
      2518140.45     13551088.43      2515848.77     13548786.33
      2514709.05     13547896.41
#Sta/Elev= 30
  1806.4  233.36  1894.0  230.99  2037.1  226.23  2141.2  220.85  2314.7  212.39
  2637.9  205.22  2708.7  205.21  3415.4  202.86  3446.1  202.41  3474.4  198.38
  3502.7  202.72  3584.7  203.02  3611.1  202.91  3794.6  202.61  3836.0  202.36
  4003.8  202.43  4114.9  203.21  4690.6  204.41  4768.4  201.47  4853.2  204.37
  4945.2  200.91  4951.6  198.05  4952.1  197.55  4981.1  198.05  5008.8  198.96
  5037.1  203.89  5141.9  205.67  5500.5  210.89  5871.3  219.29  6500.7  220.04
#Mann=16,-1,0
  1806.4    0.12       0  1894.0    0.05       0  2037.1    0.12       0
  2141.2    0.04       0  2637.9   0.013       0  2708.7    0.04       0
  3415.4    0.05       0  3584.7    0.04       0  3611.1    0.03       0
  3794.6    0.04       0  3836.0    0.12       0  4003.8    0.04       0
  4114.9    0.12       0  4951.6    0.05       0  4981.1    0.12       0
  5141.9    0.04       0
Bank Sta=4951.6,4981.1
Exp/Cntr=0.3,0.1

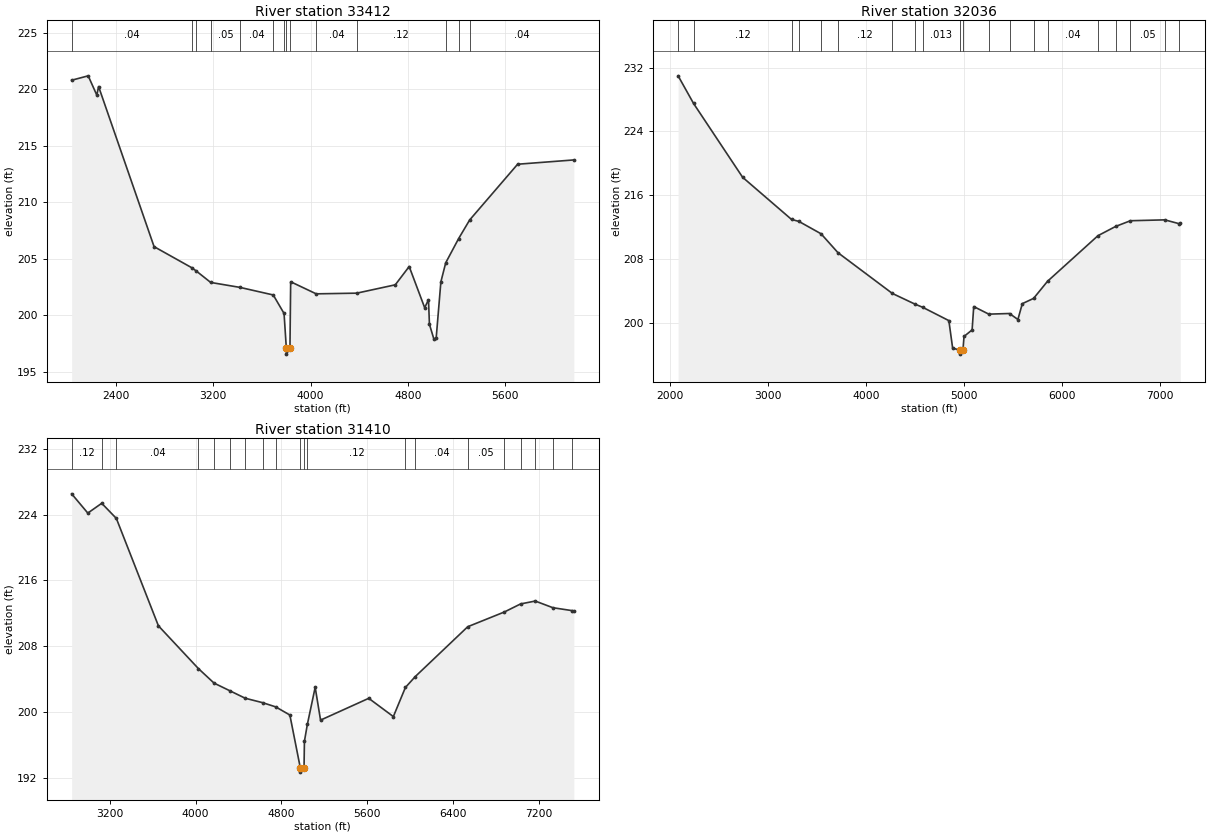
Type RM Length L Ch R = 1,33412,1376,1376,1376
BEGIN DESCRIPTION:
Mapping XS 40362ee9
END DESCRIPTION:
XS GIS Cut Line= 4
      2518775.81     13550723.80      2516899.94     13549311.00
      2516708.14     13548708.20      2516322.73     13547630.08
#Sta/Elev= 30
  2037.0  220.80  2172.9  221.19  2243.7  219.48  2258.3  220.24  2714.2  206.06
  3022.7  204.20  3058.7  203.92  3179.3  202.89  3420.4  202.45  3693.3  201.78
  3782.1  200.14  3800.9  197.04  3801.4  196.54  3830.5  197.04  3836.5  202.95
  4046.1  201.88  4379.4  201.94  4696.0  202.68  4810.1  204.30  4937.4  200.65
  4968.8  201.36  4976.5  199.18  5014.0  197.84  5032.0  197.97  5070.5  202.94
  5110.3  204.63  5216.6  206.78  5306.8  208.42  5701.0  213.36  6162.9  213.74
#Mann=14,-1,0
  2037.0    0.04       0  3022.7    0.05       0  3058.7   0.013       0
  3179.3    0.05       0  3420.4    0.04       0  3693.3    0.05       0
  3782.1    0.12       0  3800.9    0.05       0  3830.5    0.12       0
  4046.1    0.04       0  4379.4    0.12       0  5110.3    0.04       0
  5216.6   0.013       0  5306.8    0.04       0
Bank Sta=3800.9,3830.5
Exp/Cntr=0.3,0.1

Type RM Length L Ch R = 1,32036,626,626,626
BEGIN DESCRIPTION:
Mapping XS b97c4952
END DESCRIPTION:
XS GIS Cut Line= 4
      2520159.56     13550841.90      2518388.70     13550043.27
      2517610.92     13548543.27      2516444.96     13547599.39
#Sta/Elev= 30
  2079.4  230.96  2237.4  227.50  2738.9  218.27  3238.7  213.00  3313.0  212.76
  3540.1  211.21  3713.4  208.84  4268.8  203.75  4497.0  202.43  4578.3  202.02
  4846.4  200.35  4885.0  196.92  4956.3  196.66  4957.0  196.16  4990.7  196.66
  5001.2  198.37  5084.1  199.19  5100.6  202.11  5254.4  201.16  5466.3  201.24
  5552.0  200.49  5597.1  202.47  5712.3  203.13  5854.9  205.27  6370.2  210.97
  6551.6  212.13  6702.0  212.84  7052.9  212.95  7196.8  212.48  7211.8  212.53
#Mann=20,-1,0
  2079.4    0.04       0  2237.4    0.12       0  3238.7   0.013       0
  3313.0    0.12       0  3540.1    0.04       0  3713.4    0.12       0
  4268.8   0.013       0  4497.0    0.12       0  4578.3   0.013       0
  4956.3    0.03       0  4990.7   0.013       0  5254.4    0.05       0
  5466.3   0.013       0  5712.3    0.12       0  5854.9    0.04       0
  6370.2    0.05       0  6551.6    0.05       0  6702.0    0.05       0
  7052.9    0.05       0  7196.8    0.04       0
Bank Sta=4956.3,4990.7
Exp/Cntr=0.3,0.1

Type RM Length L Ch R = 1,31410,664,664,664
BEGIN DESCRIPTION:
Mapping XS 835f96be
END DESCRIPTION:
XS GIS Cut Line= 3
      2519951.17     13550591.85      2518624.81     13549126.60
      2516444.23     13547522.42
#Sta/Elev= 30
  2843.7  226.52  2994.5  224.18  3124.2  225.37  3260.6  223.53  3652.8  210.48
  4025.3  205.29  4171.6  203.52  4320.2  202.58  4462.3  201.68  4624.9  201.14
  4746.6  200.63  4878.8  199.64  4976.5  193.20  4977.2  192.70  5010.9  193.20
  5014.6  196.45  5041.9  198.50  5114.9  203.01  5165.0  199.02  5614.4  201.67
  5843.9  199.45  5956.4  202.99  6048.9  204.32  6537.7  210.37  6879.1  212.16
  7030.7  213.14  7167.2  213.49  7331.9  212.68  7509.2  212.33  7527.2  212.28
#Mann=20,-1,0
  2843.7    0.12       0  3124.2   0.013       0  3260.6    0.04       0
  4025.3    0.05       0  4171.6    0.04       0  4320.2    0.05       0
  4462.3    0.04       0  4624.9   0.013       0  4746.6    0.12       0
  4976.5    0.05       0  5010.9    0.12       0  5041.9    0.12       0
  5956.4    0.12       0  6048.9    0.04       0  6537.7    0.05       0
  6879.1    0.04       0  7030.7    0.05       0  7167.2    0.04       0
  7331.9    0.05       0  7509.2    0.04       0
Bank Sta=4976.5,5010.9
Exp/Cntr=0.3,0.1