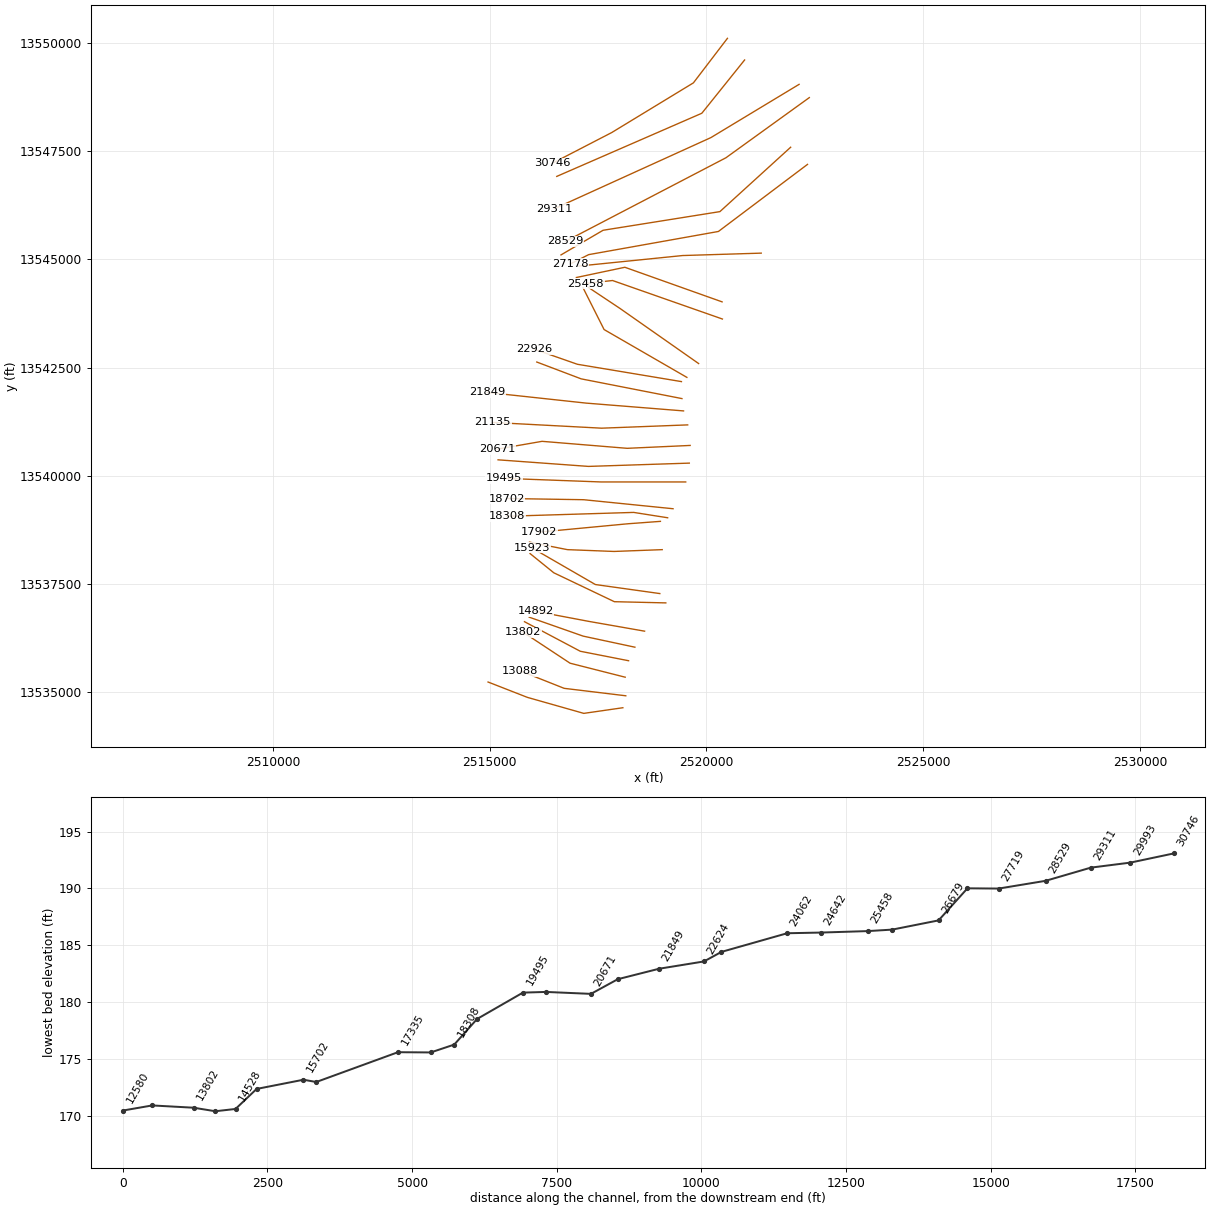
HEC-RAS study FIVEMILE CREEK.prj: FIVEMILE CREEK Base Level Engineering

--- FIVEMILE CREEK.g01 (geometry) --- (continued)

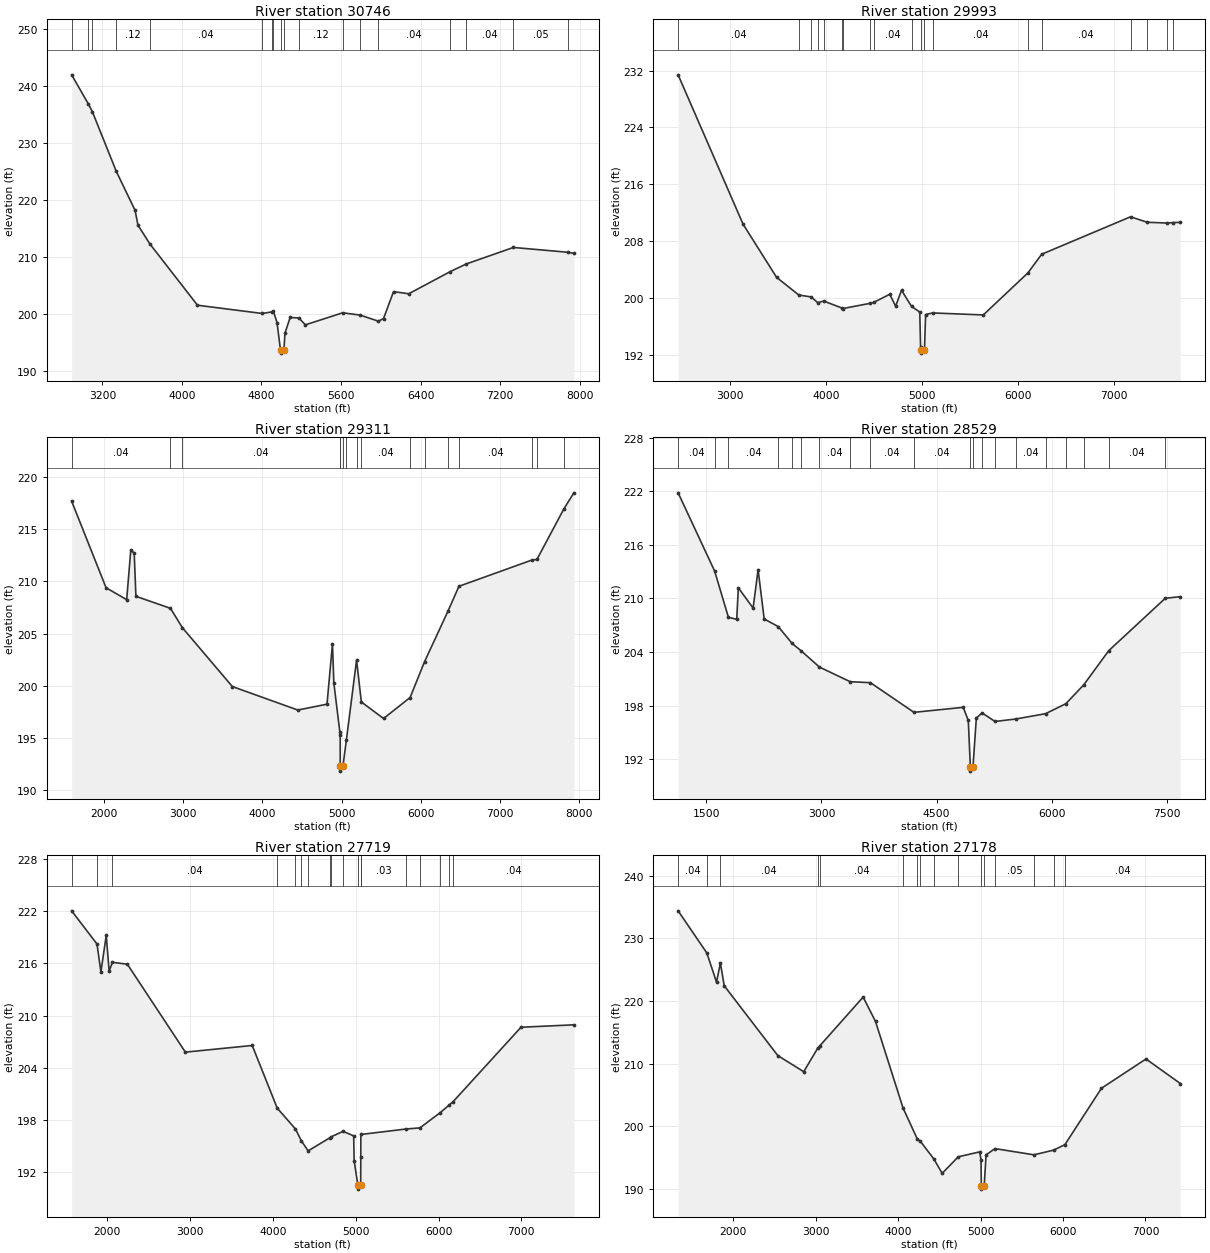
Type RM Length L Ch R = 1,30746,753,753,753
BEGIN DESCRIPTION:
Mapping XS bc86d296
END DESCRIPTION:
XS GIS Cut Line= 4
      2520485.93     13550098.84      2519701.20     13549071.05
      2517819.25     13547925.22      2516438.67     13547210.64
#Sta/Elev= 30
  2890.7  241.88  3059.8  236.74  3100.2  235.36  3340.2  224.93  3528.8  218.11
  3557.8  215.51  3677.4  212.23  4156.4  201.48  4809.2  200.03  4909.7  200.33
  4918.7  200.49  4956.5  198.45  4991.5  193.58  4992.2  193.08  5025.9  193.58
  5035.9  196.56  5088.2  199.33  5176.1  199.25  5241.2  198.04  5616.7  200.15
  5792.1  199.75  5975.9  198.68  6027.6  199.14  6128.3  203.86  6281.4  203.49
  6695.9  207.35  6859.1  208.71  7333.8  211.61  7886.6  210.76  7941.7  210.56
#Mann=18,-1,0
  2890.7    0.04       0  3059.8    0.12       0  3100.2    0.04       0
  3340.2    0.12       0  3677.4    0.04       0  4809.2   0.013       0
  4909.7    0.04       0  4918.7     0.1       0  4991.5    0.05       0
  5025.9     0.1       0  5176.1    0.12       0  5616.7    0.04       0
  5792.1    0.12       0  5975.9    0.04       0  6695.9    0.05       0
  6859.1    0.04       0  7333.8    0.05       0  7886.6    0.12       0
Bank Sta=4991.5,5025.9
Exp/Cntr=0.3,0.1

Type RM Length L Ch R = 1,29993,682,682,682
BEGIN DESCRIPTION:
Mapping XS 166792cb
END DESCRIPTION:
XS GIS Cut Line= 3
      2520881.78     13549598.86      2519895.64     13548369.66
      2516549.25     13546911.69
#Sta/Elev= 30
  2461.9  231.40  3137.9  210.40  3486.8  202.92  3718.0  200.44  3847.2  200.17
  3914.6  199.37  3976.5  199.59  4163.8  198.63  4176.6  198.54  4456.2  199.26
  4495.8  199.40  4664.3  200.54  4725.7  198.87  4786.8  201.11  4891.1  198.84
  4976.6  198.05  4985.2  193.11  4991.3  192.77  4992.0  192.27  5025.8  192.77
  5037.5  197.70  5111.4  197.92  5637.9  197.64  6102.8  203.56  6245.1  206.17
  7170.1  211.44  7343.0  210.67  7554.7  210.56  7606.8  210.62  7688.0  210.66
#Mann=19,-1,0
  2461.9    0.04       0  3718.0   0.013       0  3847.2    0.04       0
  3914.6   0.013       0  3976.5    0.04       0  4163.8   0.013       0
  4176.6    0.04       0  4456.2   0.013       0  4495.8    0.04       0
  4891.1     0.1       0  4991.3    0.05       0  5025.8     0.1       0
  5111.4    0.04       0  6102.8    0.05       0  6245.1    0.04       0
  7170.1    0.05       0  7343.0    0.12       0  7554.7    0.05       0
  7606.8    0.12       0
Bank Sta=4991.3,5025.8
Exp/Cntr=0.3,0.1

Type RM Length L Ch R = 1,29311,782,782,782
BEGIN DESCRIPTION:
Mapping XS a5f6b2d5
END DESCRIPTION:
XS GIS Cut Line= 3
      2522138.74     13549036.35      2520103.98     13547807.16
      2516499.91     13546168.31
#Sta/Elev= 30
  1593.2  217.68  2027.5  209.39  2287.5  208.25  2339.9  213.02  2382.6  212.69
  2404.0  208.57  2840.2  207.42  2989.7  205.57  3620.7  199.93  4446.9  197.68
  4815.2  198.24  4884.1  204.02  4901.6  200.26  4977.8  195.54  4981.8  195.25
  4982.1  192.33  4982.8  191.83  5016.6  192.33  5059.0  194.77  5188.2  202.46
  5248.5  198.45  5528.8  196.87  5863.7  198.88  6045.9  202.31  6341.6  207.15
  6479.8  209.53  7399.2  212.04  7463.7  212.10  7800.8  216.90  7929.6  218.48
#Mann=16,-1,0
  1593.2    0.04       0  2840.2   0.013       0  2989.7    0.04       0
  4977.8    0.12       0  4982.1    0.05       0  5016.6    0.12       0
  5059.0    0.04       0  5188.2    0.05       0  5248.5    0.04       0
  5863.7    0.05       0  6045.9    0.04       0  6341.6    0.05       0
  6479.8    0.04       0  7399.2    0.05       0  7463.7    0.03       0
  7800.8    0.04       0
Bank Sta=4982.1,5016.6
Exp/Cntr=0.3,0.1

Type RM Length L Ch R = 1,28529,810,810,810
BEGIN DESCRIPTION:
Mapping XS c0a9ff04
END DESCRIPTION:
XS GIS Cut Line= 3
      2522374.81     13548730.77      2520451.20     13547341.88
      2516749.92     13545411.38
#Sta/Elev= 30
  1131.4  221.82  1607.7  213.06  1787.4  207.88  1895.6  207.67  1916.5  211.19
  2109.1  208.92  2174.1  213.22  2253.6  207.70  2436.9  206.85  2617.7  204.96
  2736.6  204.13  2973.2  202.32  3374.5  200.68  3638.8  200.57  4206.0  197.25
  4848.1  197.81  4914.4  196.34  4941.3  191.17  4942.0  190.67  4975.9  191.17
  5019.2  196.60  5093.8  197.19  5262.8  196.23  5531.0  196.50  5922.2  197.10
  6186.8  198.22  6419.7  200.33  6745.1  204.15  7481.7  210.01  7678.5  210.20
#Mann=20,-1,0
  1131.4    0.04       0  1607.7    0.03       0  1787.4    0.04       0
  2436.9   0.013       0  2617.7    0.05       0  2736.6    0.04       0
  2973.2    0.04       0  3374.5    0.12       0  3638.8    0.04       0
  4206.0    0.04       0  4941.3    0.05       0  4975.9    0.05       0
  5093.8    0.12       0  5262.8    0.12       0  5531.0    0.04       0
  5922.2    0.05       0  6186.8    0.04       0  6419.7    0.12       0
  6745.1    0.04       0  7481.7    0.04       0
Bank Sta=4941.3,4975.9
Exp/Cntr=0.3,0.1

Type RM Length L Ch R = 1,27719,541,541,541
BEGIN DESCRIPTION:
Mapping XS a4a5b9b6
END DESCRIPTION:
XS GIS Cut Line= 4
      2521944.25     13547584.93      2520312.31     13546098.83
      2517617.87     13545668.27      2516646.63     13545099.40
#Sta/Elev= 30
  1571.7  222.07  1877.8  218.24  1924.9  215.02  1989.0  219.23  2024.2  215.13
  2064.0  216.13  2243.8  215.92  2944.4  205.78  3751.2  206.55  4052.8  199.33
  4272.4  196.93  4345.6  195.54  4426.0  194.40  4693.9  195.94  4703.6  196.02
  4847.2  196.65  4975.9  196.13  4981.3  193.28  5025.7  190.49  5026.4  189.99
  5060.3  190.49  5061.4  193.68  5062.3  196.29  5607.8  196.92  5775.3  197.05
  6022.0  198.82  6128.5  199.69  6176.7  200.08  6995.3  208.65  7633.1  208.93
#Mann=18,-1,0
  1571.7    0.04       0  1877.8   0.013       0  2064.0    0.04       0
  4052.8    0.12       0  4272.4    0.03       0  4345.6    0.12       0
  4426.0    0.05       0  4693.9    0.03       0  4703.6    0.05       0
  4847.2     0.1       0  5025.7    0.05       0  5060.3     0.1       0
  5061.4    0.03       0  5607.8    0.04       0  5775.3    0.03       0
  6022.0    0.04       0  6128.5    0.03       0  6176.7    0.04       0
Bank Sta=5025.7,5060.3
Exp/Cntr=0.3,0.1

Type RM Length L Ch R = 1,27178,499,499,499
BEGIN DESCRIPTION:
Mapping XS 197e032a
END DESCRIPTION:
XS GIS Cut Line= 4
      2522333.17     13547189.13      2520277.59     13545640.49
      2517284.53     13545105.77      2516860.90     13544890.48
#Sta/Elev= 30
  1333.0  234.38  1680.7  227.67  1798.6  223.01  1845.8  226.06  1892.2  222.43
  2541.8  211.30  2856.2  208.73  3026.6  212.50  3052.6  212.88  3576.6  220.63
  3726.5  216.74  4060.1  202.95  4233.8  197.99  4270.3  197.63  4432.6  194.85
  4534.5  192.53  4730.8  195.17  4990.5  195.95  5006.4  194.58  5009.4  190.51
  5010.1  190.01  5044.1  190.51  5067.3  195.47  5174.7  196.47  5648.0  195.48
  5886.1  196.23  6022.9  197.10  6466.1  206.09  7006.1  210.76  7422.3  206.85
#Mann=16,-1,0
  1333.0    0.04       0  1680.7   0.013       0  1845.8    0.04       0
  3026.6    0.03       0  3052.6    0.04       0  4060.1    0.12       0
  4233.8    0.03       0  4270.3    0.12       0  4432.6    0.05       0
  4730.8     0.1       0  5009.4    0.05       0  5044.1     0.1       0
  5174.7    0.05       0  5648.0    0.12       0  5886.1    0.05       0
  6022.9    0.04       0
Bank Sta=5009.4,5044.1
Exp/Cntr=0.3,0.1

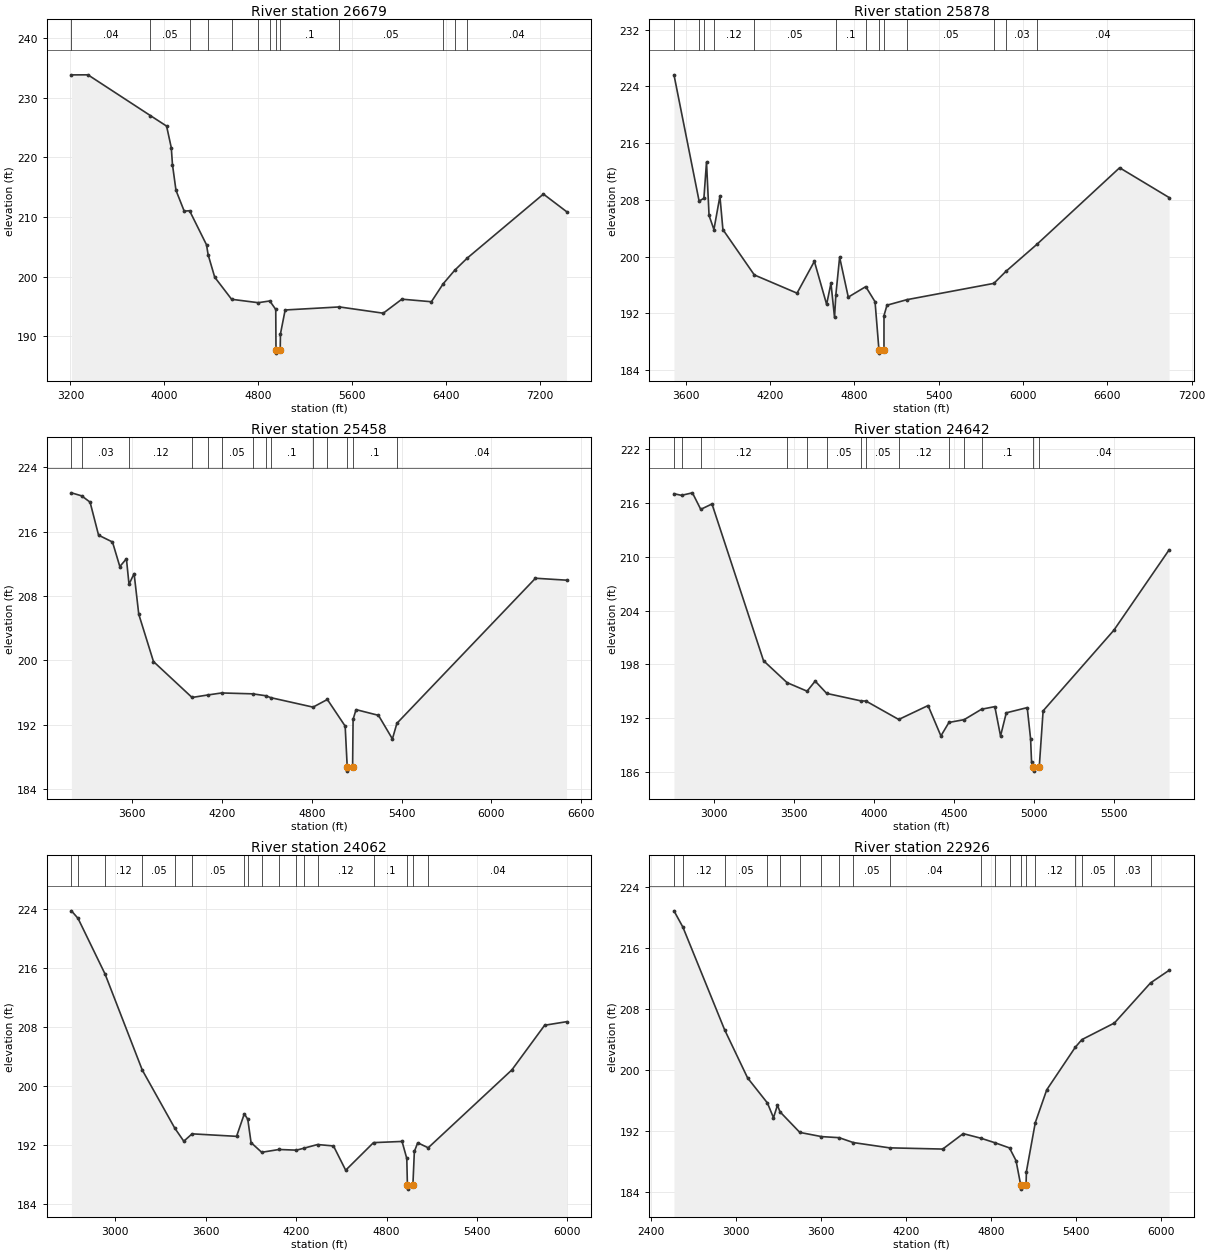
Type RM Length L Ch R = 1,26679,801,801,801
BEGIN DESCRIPTION:
Mapping XS bf356792
END DESCRIPTION:
XS GIS Cut Line= 3
      2521265.82     13545140.49      2519453.37     13545084.94
      2517058.76     13544842.01
#Sta/Elev= 30
  3208.7  233.81  3349.6  233.82  3882.6  226.98  4019.9  225.23  4059.9  221.61
  4069.9  218.78  4099.9  214.47  4170.0  210.98  4215.8  211.05  4360.1  205.34
  4373.9  203.68  4430.1  199.91  4574.2  196.21  4801.0  195.64  4899.3  195.93
  4950.3  194.51  4952.4  187.69  4953.2  187.19  4988.2  187.69  4990.4  190.41
  5030.4  194.42  5493.2  194.93  5866.6  193.88  6025.5  196.23  6276.8  195.80
  6377.3  198.81  6475.9  201.08  6582.8  203.12  7231.7  213.84  7428.9  210.90
#Mann=13,-1,0
  3208.7    0.04       0  3882.6    0.05       0  4215.8   0.013       0
  4373.9    0.05       0  4574.2    0.03       0  4801.0    0.12       0
  4899.3     0.1       0  4952.4    0.05       0  4988.2     0.1       0
  5493.2    0.05       0  6377.3    0.04       0  6475.9    0.03       0
  6582.8    0.04       0
Bank Sta=4952.4,4988.2
Exp/Cntr=0.3,0.1

Type RM Length L Ch R = 1,25878,420,420,420
BEGIN DESCRIPTION:
Mapping XS 47a5792d
END DESCRIPTION:
XS GIS Cut Line= 3
      2520363.10     13544015.49      2518120.04     13544814.10
      2517001.98     13544577.99
#Sta/Elev= 30
  3515.3  225.64  3694.2  207.83  3728.3  208.22  3746.8  213.34  3765.0  205.80
  3799.6  203.82  3842.3  208.51  3863.6  203.81  4087.2  197.41  4391.2  194.84
  4514.5  199.33  4601.7  193.26  4632.5  196.24  4658.0  191.42  4667.5  194.64
  4694.2  199.91  4755.8  194.28  4880.2  195.76  4946.3  193.63  4973.9  186.88
  4974.7  186.38  5009.8  186.88  5010.0  191.68  5031.2  193.14  5172.9  193.92
  5791.9  196.22  5879.1  197.94  6098.3  201.73  6686.9  212.53  7039.0  208.33
#Mann=13,-1,0
  3515.3    0.05       0  3694.2    0.03       0  3728.3    0.05       0
  3799.6    0.12       0  4087.2    0.05       0  4667.5     0.1       0
  4880.2    0.12       0  4973.9    0.05       0  5009.8    0.12       0
  5172.9    0.05       0  5791.9    0.04       0  5879.1    0.03       0
  6098.3    0.04       0
Bank Sta=4973.9,5009.8
Exp/Cntr=0.3,0.1

Type RM Length L Ch R = 1,25458,816,816,816
BEGIN DESCRIPTION:
Mapping XS 42baffd8
END DESCRIPTION:
XS GIS Cut Line= 3
      2520370.05     13543619.65      2517835.31     13544508.55
      2517218.68     13544439.26
#Sta/Elev= 30
  3195.2  220.82  3264.0  220.44  3319.8  219.66  3376.5  215.56  3469.5  214.71
  3518.5  211.66  3562.5  212.63  3579.8  209.46  3613.8  210.79  3644.9  205.74
  3743.2  199.86  4000.7  195.40  4106.0  195.71  4198.5  195.96  4405.7  195.85
  4494.8  195.61  4525.6  195.38  4808.8  194.20  4904.3  195.15  5023.3  191.84
  5037.1  186.75  5037.9  186.25  5073.0  186.75  5076.2  192.68  5096.1  193.89
  5245.8  193.18  5338.8  190.25  5368.9  192.19  6294.2  210.21  6501.8  209.97
#Mann=14,-1,0
  3195.2    0.05       0  3264.0    0.03       0  3579.8    0.12       0
  4000.7   0.013       0  4106.0    0.12       0  4198.5    0.05       0
  4405.7     0.1       0  4494.8    0.05       0  4525.6     0.1       0
  4808.8    0.12       0  4904.3     0.1       0  5037.1    0.05       0
  5073.0     0.1       0  5368.9    0.04       0
Bank Sta=5037.1,5073
Exp/Cntr=0.3,0.1

Type RM Length L Ch R = 1,24642,580,580,580
BEGIN DESCRIPTION:
Mapping XS 6a97e51e
END DESCRIPTION:
XS GIS Cut Line= 3
      2519821.44     13542591.87      2518008.92     13543862.72
      2517279.84     13544348.77
#Sta/Elev= 30
  2753.0  217.00  2800.0  216.82  2868.2  217.10  2920.1  215.26  2990.2  215.86
  3311.9  198.41  3458.8  195.97  3583.8  195.02  3634.1  196.14  3706.3  194.77
  3919.9  193.94  3951.3  193.92  4155.6  191.87  4338.7  193.42  4418.8  190.04
  4469.0  191.54  4563.9  191.85  4672.5  193.01  4755.3  193.30  4791.0  190.03
  4826.8  192.61  4957.5  193.19  4978.6  189.71  4984.6  187.10  4996.6  186.62
  4997.4  186.12  5032.7  186.62  5056.7  192.83  5498.4  201.81  5842.9  210.75
#Mann=14,-1,0
  2753.0    0.12       0  2800.0    0.05       0  2920.1    0.12       0
  3458.8    0.05       0  3583.8   0.013       0  3706.3    0.05       0
  3919.9    0.12       0  3951.3    0.05       0  4155.6    0.12       0
  4469.0    0.05       0  4563.9    0.12       0  4672.5     0.1       0
  4996.6    0.05       0  5032.7    0.04       0
Bank Sta=4996.6,5032.7
Exp/Cntr=0.3,0.1

Type RM Length L Ch R = 1,24062,1136,1136,1136
BEGIN DESCRIPTION:
Mapping XS 88e46816
END DESCRIPTION:
XS GIS Cut Line= 3
      2519550.58     13542272.45      2517640.87     13543376.60
      2517155.21     13544340.99
#Sta/Elev= 30
  2709.0  223.76  2752.8  222.74  2932.4  215.19  3179.2  202.19  3394.3  194.34
  3454.7  192.55  3509.8  193.55  3805.0  193.21  3856.2  196.26  3879.3  195.52
  3901.1  192.36  3971.6  191.05  4087.1  191.43  4202.6  191.34  4254.9  191.62
  4342.0  192.10  4448.1  191.91  4529.0  188.62  4713.6  192.36  4903.1  192.52
  4934.5  190.21  4938.7  186.56  4939.6  186.06  4974.9  186.56  4984.7  191.16
  5007.1  192.34  5076.5  191.66  5631.8  202.21  5849.3  208.26  5994.7  208.74
#Mann=17,-1,0
  2709.0    0.04       0  2752.8    0.05       0  2932.4    0.12       0
  3179.2    0.05       0  3394.3   0.013       0  3509.8    0.05       0
  3856.2    0.12       0  3879.3    0.05       0  3971.6    0.12       0
  4087.1    0.05       0  4202.6    0.12       0  4254.9    0.05       0
  4342.0    0.12       0  4713.6     0.1       0  4938.7    0.05       0
  4974.9     0.1       0  5076.5    0.04       0
Bank Sta=4938.7,4974.9
Exp/Cntr=0.3,0.1

Type RM Length L Ch R = 1,22926,302,302,302
BEGIN DESCRIPTION:
FIVEMILE CREEK 35.0
END DESCRIPTION:
XS GIS Cut Line= 3
      2519424.98     13542175.00      2517025.00     13542575.00
      2516024.97     13542925.01
#Sta/Elev= 30
  2562.8  220.82  2625.9  218.68  2919.4  205.29  3082.3  198.96  3221.9  195.69
  3264.8  193.76  3292.7  195.39  3310.9  194.53  3450.4  191.84  3603.3  191.29
  3727.7  191.15  3827.8  190.51  4083.2  189.82  4458.6  189.66  4603.0  191.68
  4729.3  191.07  4829.4  190.47  4929.6  189.81  4975.6  188.15  5009.1  184.92
  5010.0  184.42  5046.3  184.92  5048.9  186.72  5111.4  193.11  5192.3  197.41
  5393.7  202.98  5440.5  203.98  5669.8  206.15  5924.3  211.39  6055.4  213.04
#Mann=20,-1,0
  2562.8    0.04       0  2625.9    0.12       0  2919.4    0.05       0
  3221.9   0.013       0  3310.9    0.05       0  3450.4    0.12       0
  3603.3    0.05       0  3727.7    0.12       0  3827.8    0.05       0
  4083.2    0.04       0  4729.3     0.1       0  4829.4    0.05       0
  4929.6     0.1       0  5009.1    0.05       0  5046.3     0.1       0
  5111.4    0.12       0  5393.7    0.12       0  5440.5    0.05       0
  5669.8    0.03       0  5924.3    0.05       0
Bank Sta=5009.1,5046.3
Exp/Cntr=0.3,0.1

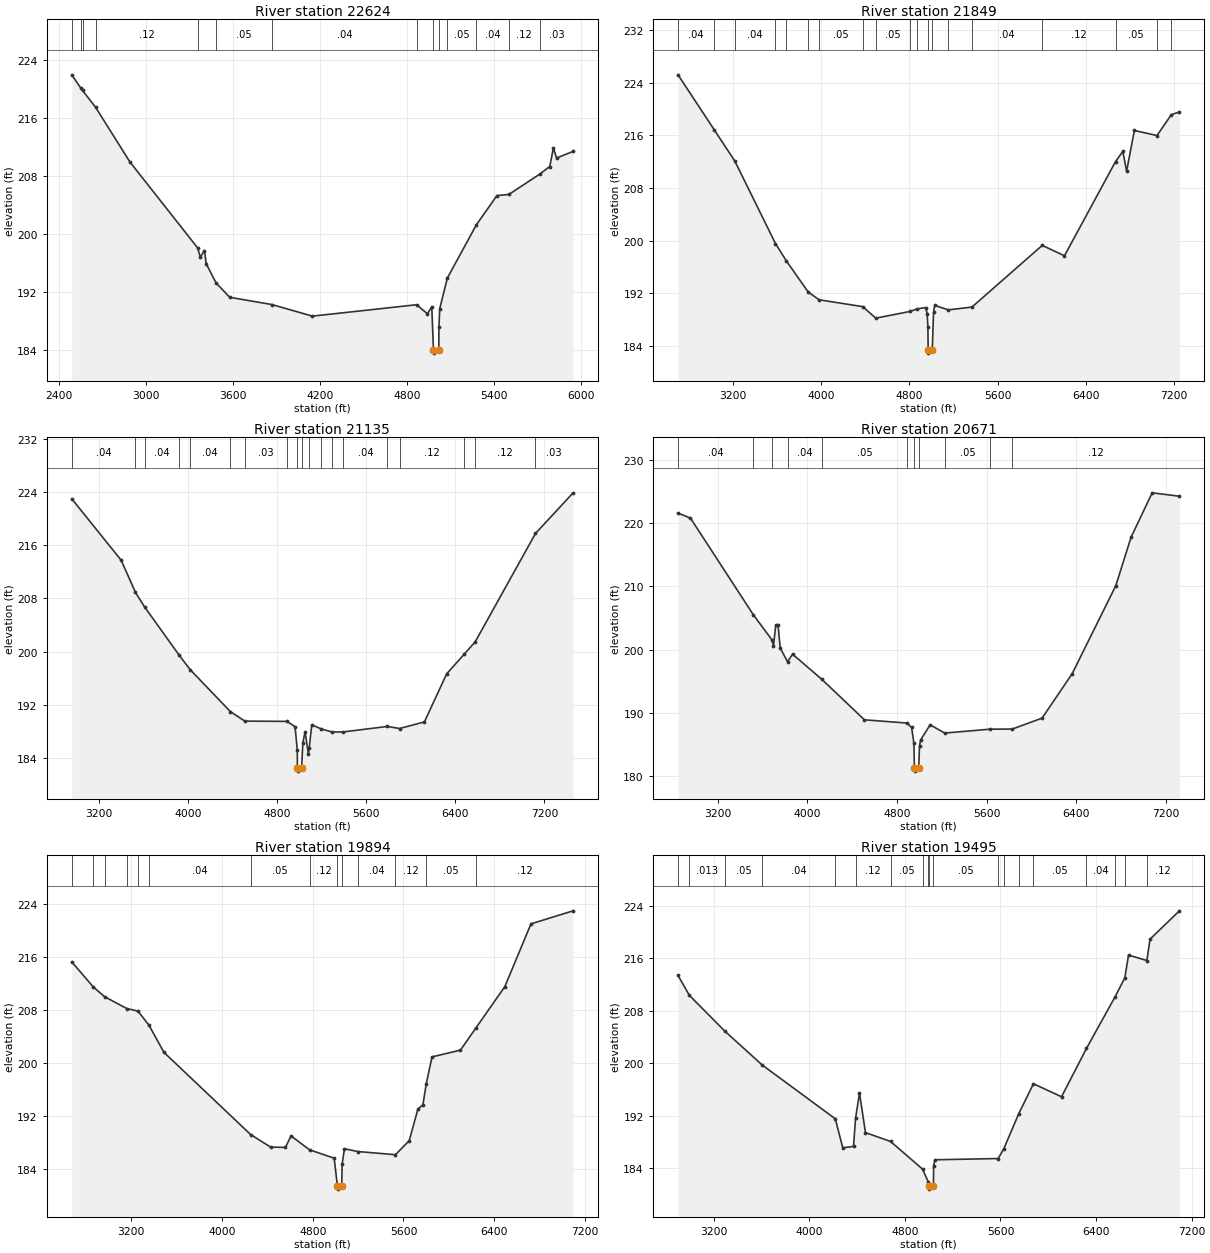
Type RM Length L Ch R = 1,22624,775,775,775
BEGIN DESCRIPTION:
Mapping XS 3739aa1e
END DESCRIPTION:
XS GIS Cut Line= 3
      2519436.18     13541782.96      2517111.51     13542238.41
      2516088.32     13542626.84
#Sta/Elev= 30
  2485.1  221.95  2547.4  220.13  2559.6  219.79  2649.5  217.49  2887.3  209.93
  3354.8  198.09  3372.8  196.83  3402.1  197.71  3413.6  195.92  3482.0  193.26
  3576.6  191.28  3869.2  190.27  4147.3  188.68  4866.9  190.25  4942.1  189.01
  4972.2  189.96  4983.7  184.08  4984.6  183.58  5020.9  184.08  5021.4  187.14
  5027.1  189.71  5079.5  193.92  5280.2  201.27  5422.2  205.30  5504.8  205.46
  5717.4  208.25  5787.2  209.31  5812.0  211.84  5834.3  210.48  5948.4  211.39
#Mann=14,-1,0
  2485.1    0.04       0  2547.4    0.12       0  2559.6    0.05       0
  2649.5    0.12       0  3354.8   0.013       0  3482.0    0.05       0
  3869.2    0.04       0  4866.9     0.1       0  4983.7    0.05       0
  5020.9     0.1       0  5079.5    0.05       0  5280.2    0.04       0
  5504.8    0.12       0  5717.4    0.03       0
Bank Sta=4983.7,5020.9
Exp/Cntr=0.3,0.1

Type RM Length L Ch R = 1,21849,714,714,714
BEGIN DESCRIPTION:
Mapping XS 9b448556
END DESCRIPTION:
XS GIS Cut Line= 3
      2519474.15     13541498.30      2517225.37     13541678.58
      2514949.08     13541925.18
#Sta/Elev= 30
  2702.8  225.20  3031.3  216.85  3217.9  212.10  3586.3  199.58  3685.2  196.94
  3883.0  192.22  3981.8  191.04  4377.3  190.00  4495.7  188.25  4809.8  189.28
  4871.7  189.67  4949.1  189.85  4961.5  188.94  4968.1  186.98  4970.7  183.44
  4971.6  182.94  5007.9  183.44  5019.5  189.12  5029.6  190.19  5152.9  189.51
  5367.5  189.93  6004.8  199.30  6206.4  197.72  6669.1  212.02  6735.3  213.57
  6769.7  210.56  6840.1  216.75  7045.4  215.98  7175.3  219.15  7248.4  219.56
#Mann=19,-1,0
  2702.8    0.04       0  3031.3    0.05       0  3217.9    0.04       0
  3586.3   0.013       0  3685.2    0.05       0  3883.0    0.12       0
  3981.8    0.05       0  4377.3     0.1       0  4495.7    0.05       0
  4809.8    0.12       0  4871.7     0.1       0  4970.7    0.05       0
  5007.9     0.1       0  5152.9    0.12       0  5367.5    0.04       0
  6004.8    0.12       0  6669.1    0.05       0  7045.4    0.04       0
  7175.3    0.05       0
Bank Sta=4970.7,5007.9
Exp/Cntr=0.3,0.1

Type RM Length L Ch R = 1,21135,464,464,464
BEGIN DESCRIPTION:
Mapping XS 727661c9
END DESCRIPTION:
XS GIS Cut Line= 3
      2519569.04     13541175.69      2517585.94     13541099.78
      2515071.50     13541232.62
#Sta/Elev= 30
  2955.0  222.97  3399.4  213.73  3527.5  208.89  3608.6  206.73  3919.2  199.47
  4017.5  197.30  4379.6  190.97  4509.8  189.54  4888.4  189.50  4960.5  188.71
  4980.5  185.21  4981.6  182.52  4982.6  182.02  5019.6  182.52  5030.6  186.32
  5050.6  187.92  5080.7  184.55  5088.0  185.56  5110.7  188.99  5197.9  188.35
  5296.6  187.89  5395.2  187.92  5789.7  188.74  5899.3  188.43  6122.1  189.42
  6322.4  196.66  6480.0  199.61  6578.6  201.47  7119.6  217.76  7457.5  223.87
#Mann=19,-1,0
  2955.0    0.04       0  3527.5    0.12       0  3608.6    0.04       0
  3919.2   0.013       0  4017.5    0.04       0  4379.6    0.05       0
  4509.8    0.03       0  4888.4    0.12       0  4981.6    0.05       0
  5019.6    0.12       0  5088.0     0.1       0  5197.9    0.12       0
  5296.6    0.05       0  5395.2    0.04       0  5789.7    0.05       0
  5899.3    0.12       0  6480.0    0.05       0  6578.6    0.12       0
  7119.6    0.03       0
Bank Sta=4981.6,5019.6
Exp/Cntr=0.3,0.1

Type RM Length L Ch R = 1,20671,777,777,777
BEGIN DESCRIPTION:
Mapping XS 8a067dde
END DESCRIPTION:
XS GIS Cut Line= 4
      2519626.00     13540701.26      2518174.23     13540634.84
      2516210.09     13540796.15      2515175.83     13540615.86
#Sta/Elev= 30
  2845.2  221.62  2956.3  220.82  3517.5  205.50  3683.6  201.52  3697.1  200.60
  3717.1  203.85  3737.1  203.95  3757.2  200.23  3822.2  198.07  3867.3  199.26
  4129.5  195.26  4508.4  188.86  4888.1  188.35  4929.8  187.65  4949.9  185.12
  4954.7  181.23  4955.7  180.73  4992.7  181.23  5000.1  184.77  5010.1  185.68
  5095.0  188.07  5224.8  186.76  5630.6  187.38  5828.3  187.40  6093.7  189.13
  6362.0  196.16  6751.5  210.11  6887.9  217.80  7076.3  224.83  7319.1  224.29
#Mann=11,-1,0
  2845.2    0.04       0  3517.5    0.12       0  3683.6   0.013       0
  3822.2    0.04       0  4129.5    0.05       0  4888.1    0.12       0
  4954.7    0.05       0  4992.7    0.12       0  5224.8    0.05       0
  5630.6    0.04       0  5828.3    0.12       0
Bank Sta=4954.7,4992.7
Exp/Cntr=0.3,0.1

Type RM Length L Ch R = 1,19894,399,399,399
BEGIN DESCRIPTION:
Mapping XS eb4f8eac
END DESCRIPTION:
XS GIS Cut Line= 3
      2519606.96     13540293.25      2517282.30     13540217.34
      2515194.81     13540369.16
#Sta/Elev= 30
  2676.1  215.28  2867.0  211.48  2965.3  210.02  3161.9  208.22  3260.2  207.84
  3358.4  205.66  3488.5  201.60  4252.8  189.16  4429.0  187.26  4559.1  187.21
  4609.1  188.95  4772.1  186.85  4989.3  185.58  5017.5  181.40  5018.5  180.90
  5055.5  181.40  5059.4  184.70  5079.5  187.01  5196.4  186.59  5529.4  186.11
  5651.0  188.25  5727.1  193.01  5771.3  193.66  5800.8  196.84  5851.5  200.91
  6102.2  201.93  6238.0  205.28  6493.2  211.54  6723.8  221.04  7095.0  223.01
#Mann=14,-1,0
  2676.1    0.05       0  2867.0    0.04       0  2965.3    0.05       0
  3161.9    0.04       0  3260.2   0.013       0  3358.4    0.04       0
  4252.8    0.05       0  4772.1    0.12       0  5017.5    0.05       0
  5055.5    0.12       0  5196.4    0.04       0  5529.4    0.12       0
  5800.8    0.05       0  6238.0    0.12       0
Bank Sta=5017.5,5055.5
Exp/Cntr=0.3,0.1

Type RM Length L Ch R = 1,19495,793,793,793
BEGIN DESCRIPTION:
Mapping XS 28c50aa7
END DESCRIPTION:
XS GIS Cut Line= 3
      2519523.47     13539858.36      2517572.05     13539858.36
      2515329.51     13539941.67
#Sta/Elev= 30
  2901.9  213.39  2997.1  210.35  3292.1  204.93  3606.2  199.75  4217.9  191.55
  4280.4  187.13  4370.4  187.35  4387.5  191.63  4420.4  195.47  4470.4  189.45
  4680.2  188.10  4948.0  183.89  4995.4  181.95  5001.4  181.34  5002.4  180.84
  5039.5  181.34  5040.5  184.29  5050.5  185.31  5581.0  185.50  5628.8  187.02
  5752.0  192.29  5876.0  196.89  6111.2  194.91  6320.0  202.28  6560.1  210.17
  6640.5  213.01  6671.6  216.49  6825.0  215.66  6851.7  218.91  7097.4  223.23
#Mann=19,-1,0
  2901.9    0.12       0  2997.1   0.013       0  3292.1    0.05       0
  3606.2    0.04       0  4217.9    0.05       0  4387.5    0.12       0
  4680.2    0.05       0  4948.0    0.12       0  4995.4    0.05       0
  5001.4    0.05       0  5039.5    0.05       0  5581.0    0.03       0
  5628.8    0.05       0  5752.0    0.03       0  5876.0    0.05       0
  6320.0    0.04       0  6560.1    0.12       0  6640.5    0.04       0
  6825.0    0.12       0
Bank Sta=5001.4,5039.5
Exp/Cntr=0.3,0.1

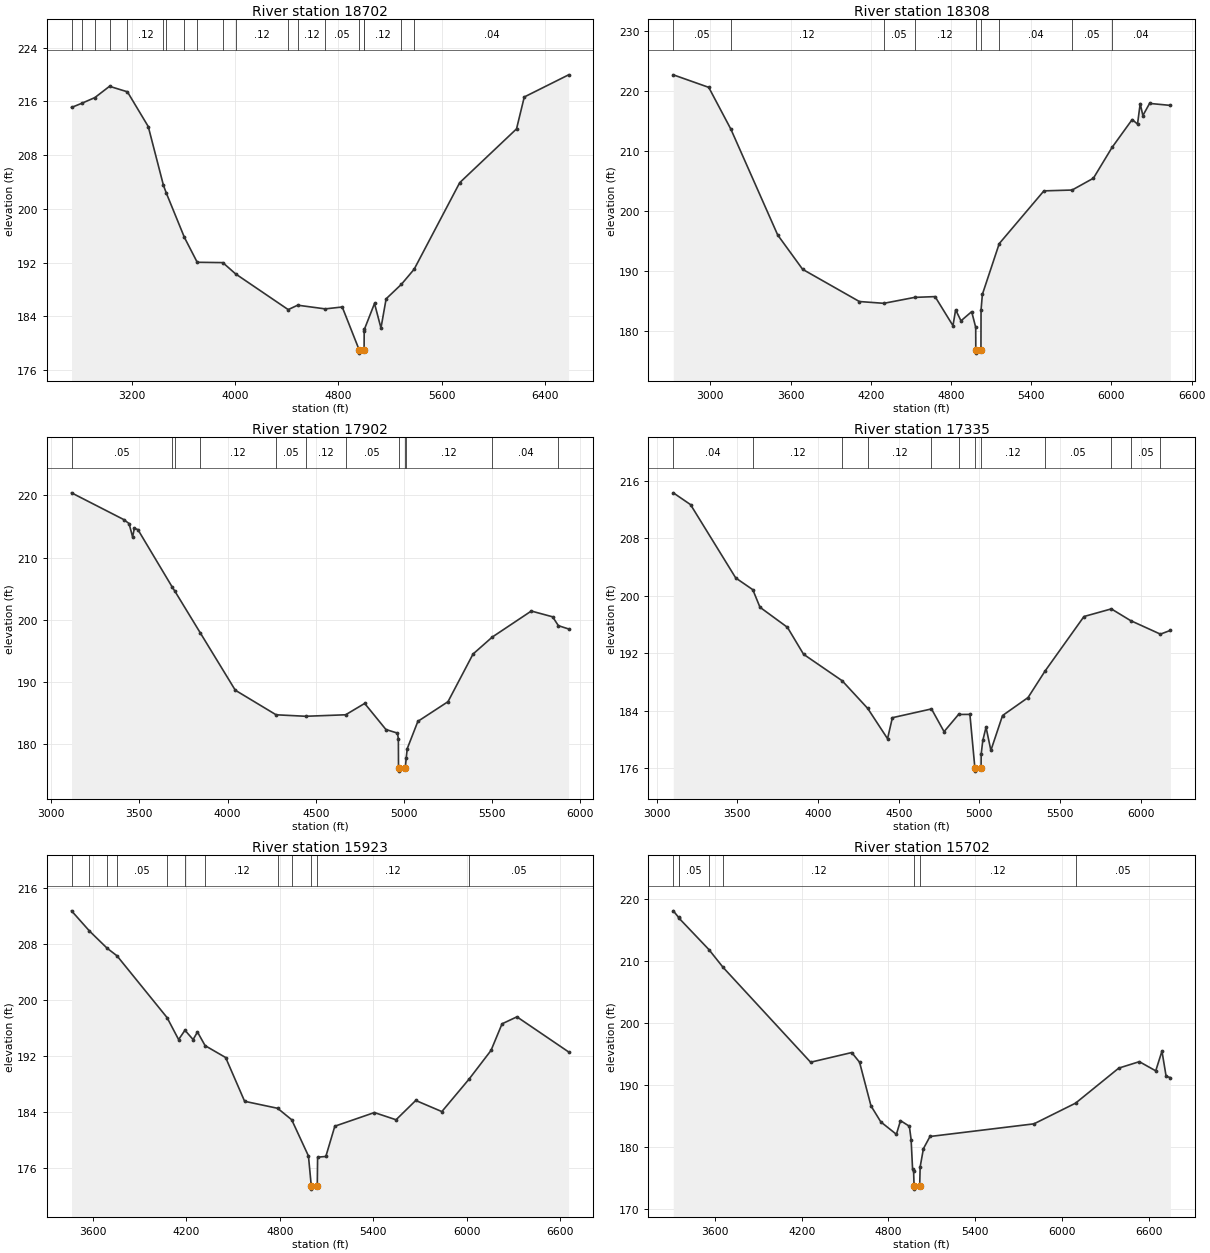
Type RM Length L Ch R = 1,18702,394,394,394
BEGIN DESCRIPTION:
Mapping XS fe9d8164
END DESCRIPTION:
XS GIS Cut Line= 3
      2519231.79     13539240.30      2517169.27     13539448.64
      2515391.51     13539476.41
#Sta/Elev= 30
  2732.6  215.11  2814.4  215.75  2913.5  216.58  3027.0  218.26  3165.6  217.44
  3327.0  212.27  3444.8  203.51  3466.3  202.39  3607.3  195.75  3706.4  192.05
  3904.7  192.00  4003.8  190.32  4411.3  185.00  4484.6  185.66  4697.6  185.11
  4829.9  185.39  4960.7  179.02  4961.7  178.52  4999.2  179.02  4999.9  181.80
  5002.0  182.09  5079.9  185.92  5129.9  182.26  5169.9  186.61  5288.7  188.78
  5387.1  191.02  5740.0  203.91  6180.1  211.92  6240.1  216.67  6583.6  219.97
#Mann=19,-1,0
  2732.6    0.04       0  2814.4    0.05       0  2913.5    0.12       0
  3027.0    0.05       0  3165.6    0.12       0  3444.8    0.05       0
  3466.3    0.12       0  3607.3    0.04       0  3706.4    0.05       0
  3904.7    0.04       0  4003.8    0.12       0  4411.3    0.05       0
  4484.6    0.12       0  4697.6    0.05       0  4960.7    0.05       0
  4999.2    0.05       0  5002.0    0.12       0  5288.7    0.05       0
  5387.1    0.04       0
Bank Sta=4960.7,4999.2
Exp/Cntr=0.3,0.1

Type RM Length L Ch R = 1,18308,406,406,406
BEGIN DESCRIPTION:
Mapping XS 4457d481
END DESCRIPTION:
XS GIS Cut Line= 3
      2519106.73     13539031.98      2518323.30     13539155.32
      2515399.23     13539066.72
#Sta/Elev= 30
  2722.5  222.70  2987.5  220.61  3153.2  213.63  3503.7  195.97  3690.1  190.25
  4114.2  184.88  4297.3  184.58  4528.0  185.57  4680.6  185.70  4814.5  180.85
  4834.5  183.50  4874.5  181.66  4954.5  183.19  4984.6  180.57  4985.3  176.77
  4986.3  176.27  5023.8  176.77  5024.6  183.47  5034.6  186.08  5160.6  194.54
  5494.8  203.34  5705.9  203.48  5865.0  205.45  6004.3  210.58  6155.1  215.24
  6195.1  214.48  6215.1  217.90  6235.1  215.90  6285.2  217.93  6441.0  217.60
#Mann=9,-1,0
  2722.5    0.05       0  3153.2    0.12       0  4297.3    0.05       0
  4528.0    0.12       0  4985.3    0.05       0  5023.8    0.12       0
  5160.6    0.04       0  5705.9    0.05       0  6004.3    0.04       0
Bank Sta=4985.3,5023.8
Exp/Cntr=0.3,0.1

Type RM Length L Ch R = 1,17902,567,567,567
BEGIN DESCRIPTION:
Mapping XS 73206d9b
END DESCRIPTION:
XS GIS Cut Line= 3
      2518940.15     13538948.64      2518190.11     13538893.08
      2516134.58     13538698.64
#Sta/Elev= 30
  3116.0  220.43  3412.0  216.12  3442.0  215.48  3462.1  213.32  3472.1  214.71
  3492.2  214.50  3685.5  205.30  3701.9  204.57  3845.7  197.86  4044.0  188.62
  4275.2  184.66  4442.9  184.42  4669.2  184.66  4777.2  186.49  4897.8  182.28
  4962.9  181.71  4968.1  180.78  4968.9  176.08  4969.9  175.58  5007.4  176.08
  5012.5  177.67  5018.3  179.20  5078.6  183.60  5249.3  186.77  5391.2  194.45
  5500.4  197.19  5721.4  201.38  5842.0  200.45  5874.9  199.02  5932.8  198.49
#Mann=12,-1,0
  3116.0    0.05       0  3685.5    0.12       0  3701.9    0.05       0
  3845.7    0.12       0  4275.2    0.05       0  4442.9    0.12       0
  4669.2    0.05       0  4968.9    0.05       0  5007.4    0.05       0
  5012.5    0.12       0  5500.4    0.04       0  5874.9    0.05       0
Bank Sta=4968.9,5007.4
Exp/Cntr=0.3,0.1

Type RM Length L Ch R = 1,17335,1412,1412,1412
BEGIN DESCRIPTION:
Mapping XS 5d048a78
END DESCRIPTION:
XS GIS Cut Line= 4
      2518981.75     13538295.86      2517870.66     13538254.19
      2516794.27     13538295.86      2515919.68     13538469.39
#Sta/Elev= 30
  3103.0  214.30  3209.8  212.66  3490.0  202.46  3595.7  200.83  3640.1  198.39
  3810.2  195.60  3910.3  191.85  4149.4  188.17  4307.9  184.32  4430.7  180.11
  4460.7  183.03  4703.1  184.25  4781.0  181.09  4870.7  183.48  4941.1  183.49
  4971.8  176.10  4972.8  175.60  5010.4  176.10  5011.1  177.98  5021.1  179.86
  5041.1  181.71  5071.2  178.48  5143.4  183.33  5301.5  185.83  5406.3  189.50
  5648.1  197.10  5817.6  198.16  5937.2  196.53  6121.7  194.65  6183.7  195.17
#Mann=12,-1,0
  3103.0    0.04       0  3595.7    0.12       0  4149.4    0.05       0
  4307.9    0.12       0  4703.1    0.05       0  4870.7    0.12       0
  4971.8    0.05       0  5010.4    0.12       0  5406.3    0.05       0
  5817.6    0.04       0  5937.2    0.05       0  6121.7    0.04       0
Bank Sta=4971.8,5010.4
Exp/Cntr=0.3,0.1

Type RM Length L Ch R = 1,15923,221,221,221
BEGIN DESCRIPTION:
Mapping XS 683b0fde
END DESCRIPTION:
XS GIS Cut Line= 3
      2518926.23     13537281.97      2517440.11     13537490.30
      2515974.86     13538337.51
#Sta/Elev= 30
  3462.2  212.78  3577.6  209.89  3691.6  207.42  3754.2  206.35  4076.0  197.51
  4150.1  194.37  4190.8  195.70  4243.2  194.37  4271.3  195.45  4320.4  193.50
  4452.2  191.80  4574.2  185.54  4786.2  184.54  4876.6  182.90  4984.2  177.72
  5002.1  173.48  5003.1  172.98  5040.9  173.48  5043.0  177.55  5095.8  177.65
  5153.6  181.98  5407.7  183.93  5546.9  182.90  5673.4  185.66  5841.1  184.07
  6016.5  188.73  6156.8  192.81  6227.8  196.62  6323.4  197.62  6655.4  192.60
#Mann=12,-1,0
  3462.2    0.04       0  3577.6    0.05       0  3691.6    0.12       0
  3754.2    0.05       0  4076.0    0.12       0  4190.8    0.05       0
  4320.4    0.12       0  4786.2     0.1       0  4876.6    0.12       0
  5002.1    0.05       0  5040.9    0.12       0  6016.5    0.05       0
Bank Sta=5002.1,5040.9
Exp/Cntr=0.3,0.1

Type RM Length L Ch R = 1,15702,810,810,810
BEGIN DESCRIPTION:
Mapping XS 08f1ab59
END DESCRIPTION:
XS GIS Cut Line= 4
      2519065.11     13537066.69      2517877.61     13537094.47
      2516481.77     13537761.14      2515933.19     13538205.56
#Sta/Elev= 30
  3310.8  218.07  3347.2  217.02  3350.1  216.89  3557.6  211.81  3656.1  208.93
  4261.2  193.65  4545.8  195.21  4600.0  193.65  4679.1  186.61  4747.2  184.02
  4855.0  182.02  4883.3  184.23  4944.8  183.32  4956.9  181.15  4967.0  176.39
  4974.0  176.09  4977.3  173.68  4978.3  173.18  5016.1  173.68  5019.4  176.77
  5042.1  179.71  5087.4  181.67  5807.2  183.71  6095.3  187.05  6394.2  192.70
  6536.5  193.74  6650.0  192.26  6693.1  195.44  6721.9  191.38  6751.5  191.17
#Mann=8,-1,0
  3310.8    0.05       0  3347.2    0.04       0  3350.1    0.05       0
  3557.6    0.04       0  3656.1    0.12       0  4977.3    0.05       0
  5016.1    0.12       0  6095.3    0.05       0
Bank Sta=4977.3,5016.1
Exp/Cntr=0.3,0.1

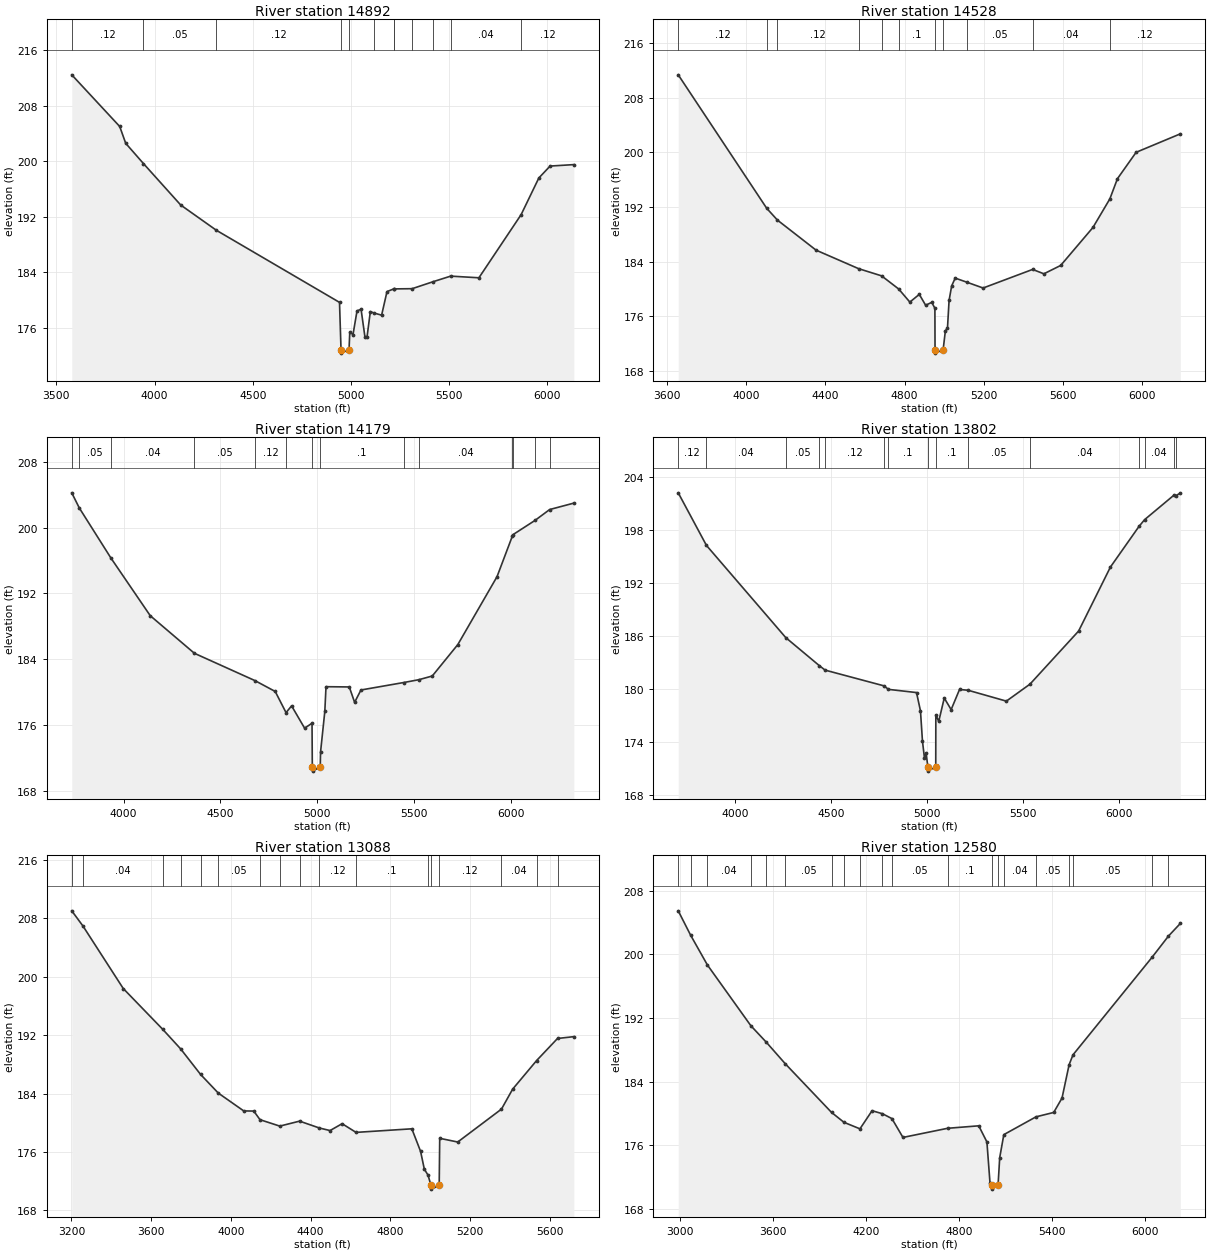
Type RM Length L Ch R = 1,14892,364,364,364
BEGIN DESCRIPTION:
Mapping XS d4c36084
END DESCRIPTION:
XS GIS Cut Line= 3
      2518575.53     13536413.91      2517299.48     13536637.87
      2516059.90     13536872.25
#Sta/Elev= 30
  3578.2  212.45  3822.4  205.01  3852.9  202.59  3943.3  199.67  4133.1  193.70
  4314.8  190.06  4941.8  179.68  4949.5  172.87  4950.5  172.37  4990.4  172.87
  4994.1  175.38  5010.6  175.05  5031.0  178.45  5051.6  178.69  5071.7  174.63
  5081.9  174.68  5098.8  178.35  5118.2  178.14  5156.3  177.84  5183.6  181.23
  5218.8  181.63  5220.4  181.62  5311.6  181.65  5420.0  182.67  5508.0  183.46
  5651.8  183.22  5866.9  192.32  5956.9  197.59  6014.3  199.31  6135.3  199.52
#Mann=12,-1,0
  3578.2    0.12       0  3943.3    0.05       0  4314.8    0.12       0
  4949.5    0.05       0  4990.4    0.12       0  5118.2    0.05       0
  5218.8    0.12       0  5220.4    0.05       0  5311.6    0.12       0
  5420.0    0.05       0  5508.0    0.04       0  5866.9    0.12       0
Bank Sta=4949.5,4990.4
Exp/Cntr=0.3,0.1

Type RM Length L Ch R = 1,14528,349,349,349
BEGIN DESCRIPTION:
Mapping XS 7281ca24
END DESCRIPTION:
XS GIS Cut Line= 3
      2518351.57     13536044.12      2517158.86     13536299.33
      2515914.11     13536736.82
#Sta/Elev= 30
  3655.4  211.34  4103.0  191.80  4157.1  190.08  4352.5  185.68  4567.7  182.97
  4683.7  181.92  4770.1  180.00  4826.7  178.08  4874.5  179.21  4906.5  177.62
  4937.5  178.04  4953.4  177.17  4954.1  171.11  4955.1  170.61  4995.1  171.11
  5006.4  173.88  5017.0  174.26  5025.1  178.32  5038.2  180.45  5056.1  181.59
  5116.0  180.98  5197.2  180.14  5447.6  182.86  5504.6  182.22  5589.4  183.44
  5752.7  189.00  5838.1  193.18  5876.6  196.14  5971.0  200.00  6194.5  202.70
#Mann=11,-1,0
  3655.4    0.12       0  4103.0    0.05       0  4157.1    0.12       0
  4567.7    0.05       0  4683.7    0.12       0  4770.1     0.1       0
  4954.1    0.05       0  4995.1     0.1       0  5116.0    0.05       0
  5447.6    0.04       0  5838.1    0.12       0
Bank Sta=4954.1,4995.1
Exp/Cntr=0.3,0.1

Type RM Length L Ch R = 1,14179,377,377,377
BEGIN DESCRIPTION:
Mapping XS 0abc0c27
END DESCRIPTION:
XS GIS Cut Line= 3
      2518205.75     13535731.62      2517091.15     13535950.37
      2515804.65     13536632.68
#Sta/Elev= 30
  3732.6  204.23  3771.5  202.39  3934.9  196.30  4137.7  189.30  4365.7  184.73
  4678.4  181.41  4783.0  180.09  4838.8  177.52  4867.5  178.34  4934.7  175.63
  4973.0  176.23  4974.5  170.91  4975.5  170.41  5015.5  170.91  5017.0  172.73
  5039.0  177.66  5045.2  180.67  5165.3  180.64  5192.9  178.77  5225.6  180.27
  5447.0  181.18  5524.4  181.52  5593.8  181.97  5725.7  185.79  5928.1  194.04
  6006.6  198.93  6011.3  199.16  6124.3  200.88  6199.9  202.20  6324.7  202.98
#Mann=14,-1,0
  3732.6    0.12       0  3771.5    0.05       0  3934.9    0.04       0
  4365.7    0.05       0  4678.4    0.12       0  4838.8     0.1       0
  4974.5    0.05       0  5015.5     0.1       0  5447.0    0.05       0
  5524.4    0.04       0  6006.6    0.12       0  6011.3    0.05       0
  6124.3    0.04       0  6199.9    0.05       0
Bank Sta=4974.5,5015.5
Exp/Cntr=0.3,0.1

Type RM Length L Ch R = 1,13802,714,714,714
BEGIN DESCRIPTION:
Mapping XS 94e03702
END DESCRIPTION:
XS GIS Cut Line= 3
      2518127.64     13535351.41      2516856.77     13535674.33
      2515769.13     13536392.49
#Sta/Elev= 30
  3703.7  202.21  3850.6  196.26  4264.0  185.82  4438.2  182.66  4468.4  182.15
  4774.9  180.37  4798.4  179.97  4944.6  179.61  4965.2  177.53  4975.5  174.12
  4985.8  172.23  4994.2  172.77  5003.7  171.22  5004.7  170.72  5044.7  171.22
  5045.2  177.09  5060.3  176.35  5089.0  178.99  5124.9  177.68  5168.6  179.96
  5213.2  179.87  5412.5  178.64  5535.3  180.56  5788.7  186.57  5954.3  193.81
  6103.2  198.41  6132.2  199.17  6284.3  201.93  6293.8  201.87  6318.3  202.18
#Mann=15,-1,0
  3703.7    0.12       0  3850.6    0.04       0  4264.0    0.05       0
  4438.2    0.04       0  4468.4    0.12       0  4774.9    0.05       0
  4798.4     0.1       0  5003.7    0.05       0  5044.7     0.1       0
  5213.2    0.05       0  5535.3    0.04       0  6103.2    0.05       0
  6132.2    0.04       0  6284.3    0.05       0  6293.8    0.04       0
Bank Sta=5003.7,5044.7
Exp/Cntr=0.3,0.1

Type RM Length L Ch R = 1,13088,508,508,508
BEGIN DESCRIPTION:
Mapping XS ae038402
END DESCRIPTION:
XS GIS Cut Line= 3
      2518141.47     13534922.60      2516719.62     13535094.47
      2515709.57     13535495.37
#Sta/Elev= 30
  3201.9  209.03  3258.5  206.93  3460.2  198.39  3658.0  192.81  3748.6  190.11
  3848.0  186.63  3937.1  184.07  4064.6  181.63  4115.0  181.61  4146.2  180.43
  4245.5  179.55  4344.9  180.23  4444.3  179.29  4497.7  178.94  4558.2  179.88
  4628.1  178.69  4908.0  179.18  4951.9  176.09  4970.8  173.64  4989.3  172.84
  5004.2  171.42  5005.2  170.92  5045.3  171.42  5047.9  177.88  5138.2  177.37
  5357.8  181.88  5413.7  184.61  5534.1  188.53  5638.9  191.55  5720.8  191.80
#Mann=17,-1,0
  3201.9    0.12       0  3258.5    0.04       0  3658.0    0.05       0
  3748.6    0.12       0  3848.0    0.04       0  3937.1    0.05       0
  4146.2    0.04       0  4245.5    0.05       0  4344.9    0.04       0
  4444.3    0.12       0  4628.1     0.1       0  4989.3    0.12       0
  5004.2    0.05       0  5045.3    0.12       0  5357.8    0.04       0
  5534.1    0.12       0  5638.9    0.04       0
Bank Sta=5004.2,5045.3
Exp/Cntr=0.3,0.1

Type RM Length L Ch R = 1,12580,285,285,285
BEGIN DESCRIPTION:
Mapping XS 63f475c4
END DESCRIPTION:
XS GIS Cut Line= 4
      2518073.74     13534646.55      2517172.74     13534516.35
      2515870.66     13534886.14      2514964.81     13535240.15
#Sta/Elev= 30
  2990.3  205.46  3070.3  202.39  3178.4  198.65  3458.6  191.01  3557.6  188.95
  3680.4  186.23  3978.3  180.12  4058.6  178.87  4161.7  178.05  4239.8  180.33
  4306.5  179.95  4367.7  179.34  4438.9  176.97  4727.2  178.12  4927.5  178.43
  4980.1  176.40  5000.2  171.19  5010.9  170.97  5011.9  170.47  5052.0  170.97
  5062.6  174.43  5089.1  177.32  5296.6  179.56  5410.6  180.11  5464.3  181.92
  5510.1  186.12  5535.2  187.36  6043.9  199.60  6150.6  202.29  6226.8  203.87
#Mann=20,-1,0
  2990.3    0.04       0  3070.3    0.12       0  3178.4    0.04       0
  3458.6    0.12       0  3557.6    0.04       0  3680.4    0.05       0
  3978.3    0.05       0  4058.6    0.04       0  4161.7    0.05       0
  4306.5    0.12       0  4367.7    0.05       0  4727.2     0.1       0
  5010.9    0.05       0  5052.0     0.1       0  5089.1    0.04       0
  5296.6    0.05       0  5510.1    0.04       0  5535.2    0.05       0
  6043.9    0.12       0  6150.6    0.05       0
Bank Sta=5010.9,5052
Exp/Cntr=0.3,0.1