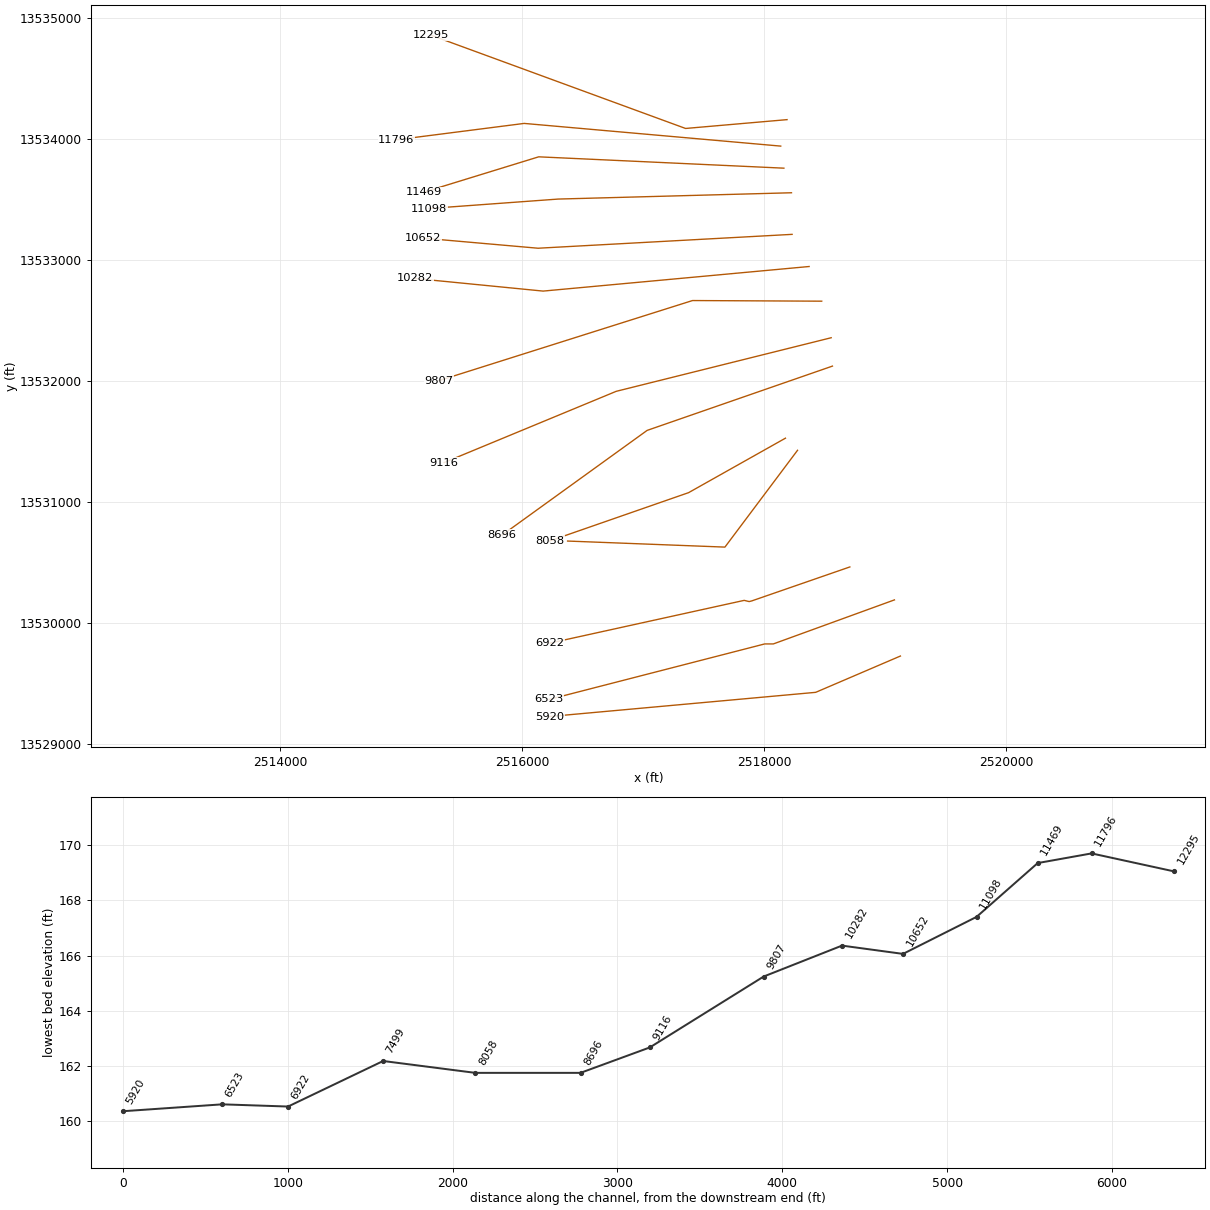
HEC-RAS study FIVEMILE CREEK.prj: FIVEMILE CREEK Base Level Engineering

--- FIVEMILE CREEK.g01 (geometry) --- (continued)

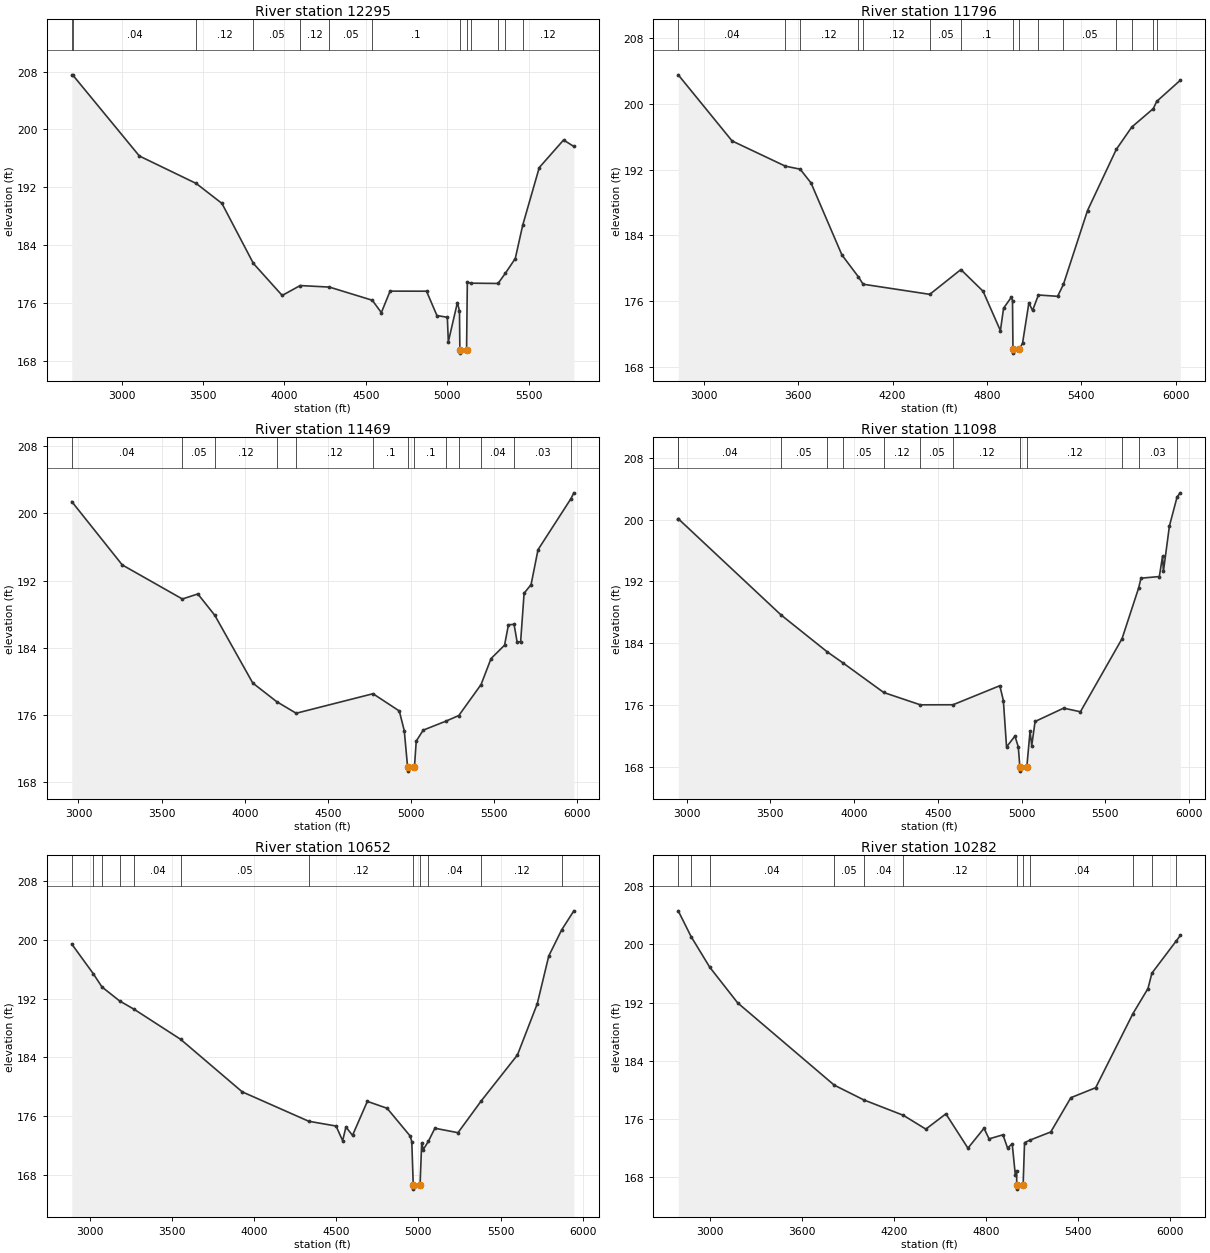
Type RM Length L Ch R = 1,12295,499,499,499
BEGIN DESCRIPTION:
Mapping XS 5fbceff3
END DESCRIPTION:
XS GIS Cut Line= 3
      2518188.36     13534156.97      2517349.83     13534084.05
      2515245.67     13534854.88
#Sta/Elev= 30
  2694.3  207.56  2700.9  207.52  3109.2  196.33  3458.2  192.53  3616.2  189.77
  3809.5  181.46  3986.2  177.03  4096.6  178.40  4275.9  178.19  4539.1  176.37
  4595.0  174.66  4648.7  177.63  4872.4  177.62  4936.3  174.25  5000.2  174.01
  5006.2  170.61  5061.9  176.04  5074.7  174.89  5077.1  169.55  5078.1  169.05
  5118.3  169.55  5122.9  178.85  5145.4  178.73  5311.4  178.69  5357.0  180.12
  5417.3  182.14  5462.9  186.75  5564.6  194.73  5713.7  198.54  5776.9  197.65
#Mann=13,-1,0
  2694.3    0.05       0  2700.9    0.04       0  3458.2    0.12       0
  3809.5    0.05       0  4096.6    0.12       0  4275.9    0.05       0
  4539.1     0.1       0  5077.1    0.05       0  5118.3     0.1       0
  5145.4    0.05       0  5311.4    0.04       0  5357.0    0.05       0
  5462.9    0.12       0
Bank Sta=5077.1,5118.3
Exp/Cntr=0.3,0.1

Type RM Length L Ch R = 1,11796,327,327,327
BEGIN DESCRIPTION:
Mapping XS ea1667d3
END DESCRIPTION:
XS GIS Cut Line= 3
      2518136.31     13533938.22      2516016.49     13534125.72
      2514959.62     13533990.36
#Sta/Elev= 30
  2836.8  203.50  3179.4  195.47  3517.8  192.41  3612.4  192.04  3681.4  190.37
  3877.8  181.63  3982.6  178.97  4012.8  178.07  4436.7  176.84  4634.6  179.85
  4775.7  177.22  4886.1  172.43  4906.2  175.16  4956.4  176.51  4963.1  176.06
  4965.9  170.20  4966.9  169.70  5007.2  170.20  5026.9  170.91  5067.2  175.81
  5090.5  174.88  5127.8  176.76  5249.9  176.60  5286.7  178.04  5440.2  187.02
  5623.0  194.44  5721.8  197.16  5858.8  199.40  5880.0  200.27  6030.4  202.84
#Mann=15,-1,0
  2836.8    0.04       0  3517.8    0.05       0  3612.4    0.12       0
  3982.6    0.05       0  4012.8    0.12       0  4436.7    0.05       0
  4634.6     0.1       0  4965.9    0.05       0  5007.2     0.1       0
  5127.8    0.12       0  5286.7    0.05       0  5623.0   0.013       0
  5721.8    0.04       0  5858.8    0.12       0  5880.0    0.04       0
Bank Sta=4965.9,5007.2
Exp/Cntr=0.3,0.1

Type RM Length L Ch R = 1,11469,371,371,371
BEGIN DESCRIPTION:
Mapping XS 7e7b0e6f
END DESCRIPTION:
XS GIS Cut Line= 3
      2518162.35     13533755.93      2516136.29     13533849.68
      2515189.14     13533558.25
#Sta/Elev= 30
  2959.9  201.39  3263.5  193.86  3625.1  189.81  3718.1  190.41  3820.1  187.87
  4048.4  179.82  4192.0  177.61  4309.4  176.23  4771.4  178.55  4929.4  176.50
  4959.4  174.16  4979.3  169.85  4980.3  169.35  5020.6  169.85  5031.3  172.92
  5073.2  174.22  5210.9  175.30  5287.3  175.96  5421.1  179.64  5481.2  182.73
  5562.4  184.32  5585.9  186.75  5619.7  186.79  5638.3  184.68  5659.1  184.74
  5680.0  190.50  5721.9  191.52  5763.7  195.67  5961.4  201.73  5979.1  202.43
#Mann=13,-1,0
  2959.9    0.04       0  3625.1    0.05       0  3820.1    0.12       0
  4192.0    0.05       0  4309.4    0.12       0  4771.4     0.1       0
  4979.3    0.05       0  5020.6     0.1       0  5210.9    0.12       0
  5287.3    0.05       0  5421.1    0.04       0  5619.7    0.03       0
  5961.4    0.05       0
Bank Sta=4979.3,5020.6
Exp/Cntr=0.3,0.1

Type RM Length L Ch R = 1,11098,446,446,446
BEGIN DESCRIPTION:
Mapping XS c6d09f39
END DESCRIPTION:
XS GIS Cut Line= 3
      2518224.87     13533552.80      2516297.74     13533500.72
      2515230.03     13533422.59
#Sta/Elev= 30
  2949.6  200.12  2950.7  200.12  3563.0  187.67  3838.3  182.89  3935.3  181.41
  4176.8  177.60  4395.6  176.00  4590.7  176.01  4870.2  178.48  4891.3  176.55
  4910.3  170.54  4960.4  171.95  4980.5  170.54  4989.9  167.90  4990.9  167.40
  5031.2  167.90  5050.6  172.58  5060.7  170.72  5080.7  173.84  5251.2  175.57
  5351.4  175.10  5600.0  184.58  5698.4  191.11  5713.5  192.43  5822.7  192.64
  5842.1  195.30  5847.1  193.31  5882.9  199.19  5928.9  202.98  5948.0  203.50
#Mann=13,-1,0
  2949.6    0.03       0  2950.7    0.04       0  3563.0    0.05       0
  3838.3    0.12       0  3935.3    0.05       0  4176.8    0.12       0
  4395.6    0.05       0  4590.7    0.12       0  4989.9    0.05       0
  5031.2    0.12       0  5600.0    0.05       0  5698.4    0.03       0
  5928.9    0.05       0
Bank Sta=4989.9,5031.2
Exp/Cntr=0.3,0.1

Type RM Length L Ch R = 1,10652,370,370,370
BEGIN DESCRIPTION:
Mapping XS eefbfaf7
END DESCRIPTION:
XS GIS Cut Line= 3
      2518230.04     13533209.05      2516131.08     13533094.47
      2515183.12     13533177.81
#Sta/Elev= 30
  2891.8  199.46  3022.3  195.43  3075.6  193.61  3182.7  191.71  3272.6  190.55
  3553.8  186.48  3928.4  179.32  4333.1  175.31  4499.2  174.66  4539.3  172.66
  4559.3  174.53  4599.4  173.39  4689.5  178.02  4809.7  177.08  4949.9  173.30
  4959.9  172.52  4968.8  166.56  4969.8  166.06  5010.1  166.56  5020.1  172.37
  5030.1  171.46  5060.5  172.57  5100.4  174.36  5240.9  173.75  5383.4  178.12
  5602.3  184.34  5722.8  191.31  5793.0  197.84  5871.0  201.38  5945.5  203.99
#Mann=12,-1,0
  2891.8    0.04       0  3022.3    0.03       0  3075.6    0.04       0
  3182.7    0.03       0  3272.6    0.04       0  3553.8    0.05       0
  4333.1    0.12       0  4968.8    0.05       0  5010.1    0.12       0
  5060.5    0.04       0  5383.4    0.12       0  5871.0    0.05       0
Bank Sta=4968.8,5010.1
Exp/Cntr=0.3,0.1

Type RM Length L Ch R = 1,10282,475,475,475
BEGIN DESCRIPTION:
Mapping XS bca5bbef
END DESCRIPTION:
XS GIS Cut Line= 3
      2518370.70     13532943.43      2516172.74     13532740.30
      2515115.49     13532844.47
#Sta/Elev= 30
  2795.3  204.62  2879.3  201.07  3000.8  196.86  3182.6  191.96  3811.1  180.66
  4003.4  178.63  4261.3  176.51  4407.8  174.61  4538.4  176.71  4682.0  171.99
  4786.5  174.73  4819.6  173.27  4910.0  173.83  4940.1  172.01  4970.2  172.60
  4990.3  168.36  4999.0  168.90  4999.8  166.86  5000.8  166.36  5041.2  166.86
  5050.6  172.75  5087.3  173.11  5221.4  174.22  5352.1  178.93  5513.7  180.30
  5756.5  190.49  5854.5  193.94  5879.9  196.05  6039.9  200.52  6065.0  201.24
#Mann=12,-1,0
  2795.3    0.04       0  2879.3    0.12       0  3000.8    0.04       0
  3811.1    0.05       0  4003.4    0.04       0  4261.3    0.12       0
  4999.8    0.05       0  5041.2    0.12       0  5087.3    0.04       0
  5756.5    0.12       0  5879.9    0.05       0  6039.9    0.04       0
Bank Sta=4999.8,5041.2
Exp/Cntr=0.3,0.1

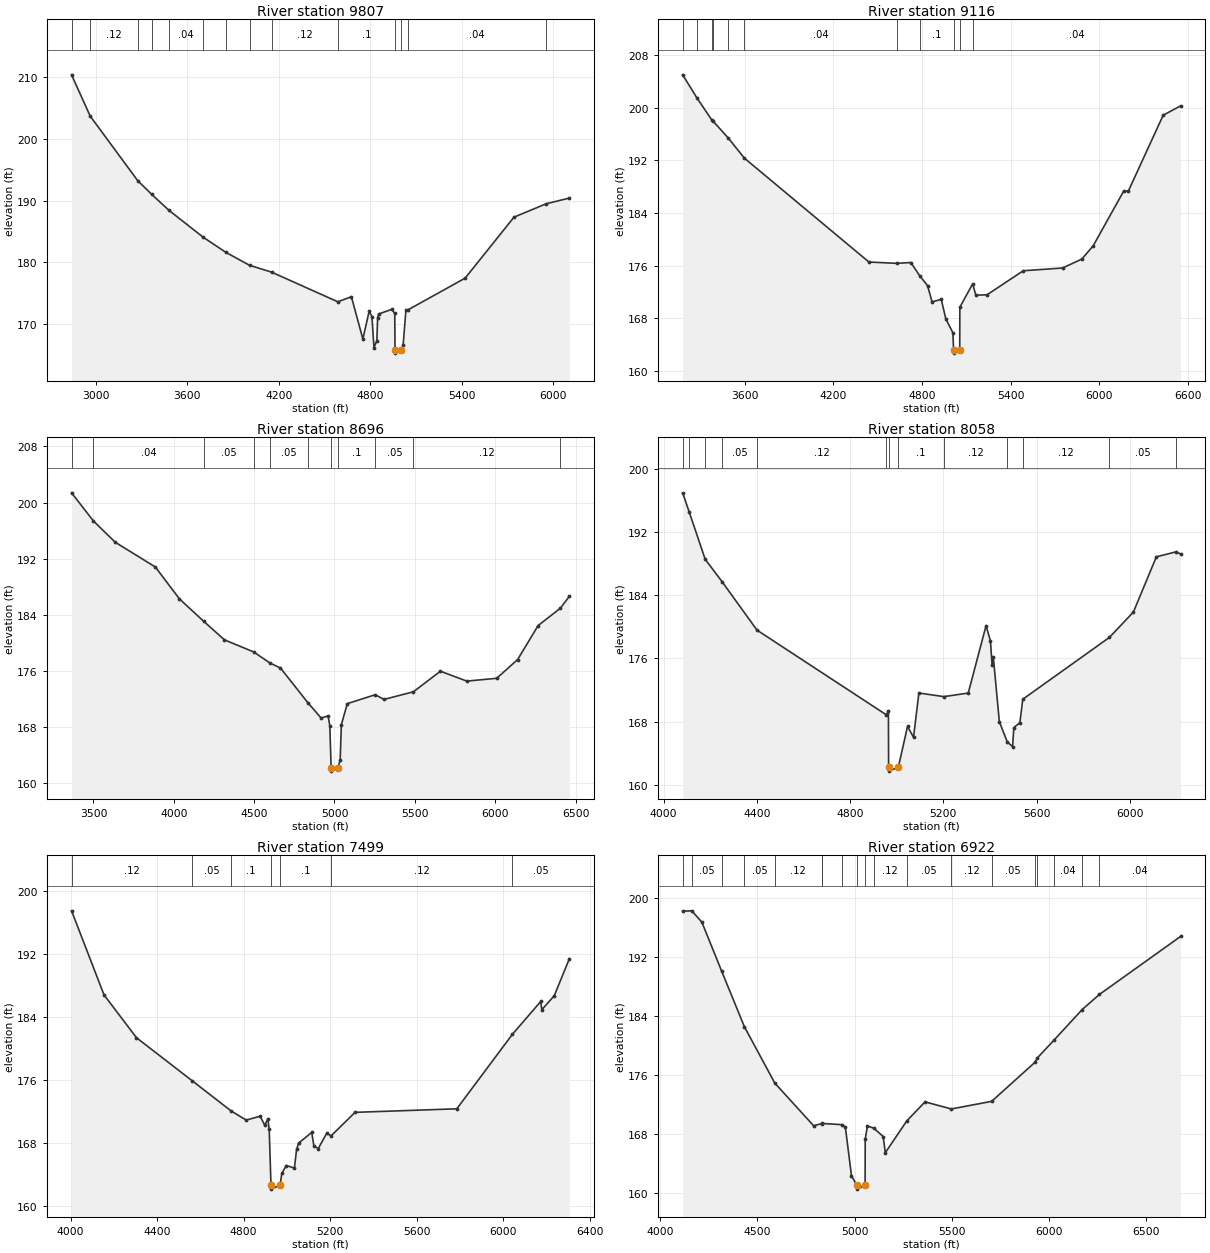
Type RM Length L Ch R = 1,9807,691,691,691
BEGIN DESCRIPTION:
Mapping XS eebbe08f
END DESCRIPTION:
XS GIS Cut Line= 3
      2518474.87     13532656.97      2517407.12     13532662.18
      2515313.38     13532000.72
#Sta/Elev= 30
  2842.4  210.41  2964.6  203.71  3275.9  193.24  3368.1  191.00  3481.7  188.40
  3706.0  184.04  3853.0  181.61  4009.6  179.49  4154.0  178.38  4588.1  173.57
  4676.8  174.40  4751.9  167.53  4793.3  172.05  4811.4  171.18  4824.8  166.13
  4843.7  167.28  4848.9  171.02  4856.2  171.60  4940.1  172.33  4961.1  171.70
  4962.8  165.74  4963.8  165.24  5004.2  165.74  5015.8  166.51  5034.5  172.29
  5047.5  172.26  5422.5  177.41  5742.8  187.31  5952.7  189.47  6105.9  190.41
#Mann=14,-1,0
  2842.4    0.04       0  2964.6    0.12       0  3275.9    0.04       0
  3368.1    0.05       0  3481.7    0.04       0  3706.0    0.05       0
  3853.0    0.04       0  4009.6    0.05       0  4154.0    0.12       0
  4588.1     0.1       0  4962.8    0.05       0  5004.2     0.1       0
  5047.5    0.04       0  5952.7    0.12       0
Bank Sta=4962.8,5004.2
Exp/Cntr=0.3,0.1

Type RM Length L Ch R = 1,9116,420,420,420
BEGIN DESCRIPTION:
Mapping XS 4875acea
END DESCRIPTION:
XS GIS Cut Line= 3
      2518552.99     13532354.90      2516776.91     13531912.18
      2515355.03     13531323.63
#Sta/Elev= 30
  3179.4  205.04  3275.1  201.55  3375.7  198.19  3382.2  198.06  3489.2  195.38
  3596.7  192.36  4439.9  176.54  4627.3  176.34  4723.2  176.46  4784.6  174.42
  4836.6  172.94  4867.5  170.47  4929.3  170.86  4960.3  167.88  5008.2  165.77
  5012.7  163.17  5013.7  162.67  5054.4  163.17  5055.2  169.66  5141.8  173.21
  5163.4  171.49  5239.2  171.55  5484.4  175.21  5750.4  175.63  5880.8  176.99
  5957.9  179.02  6165.3  187.39  6194.6  187.29  6431.3  198.89  6548.7  200.31
#Mann=11,-1,0
  3179.4    0.04       0  3275.1    0.05       0  3375.7    0.12       0
  3382.2    0.04       0  3489.2    0.05       0  3596.7    0.04       0
  4627.3    0.05       0  4784.6     0.1       0  5012.7    0.05       0
  5054.4     0.1       0  5141.8    0.04       0
Bank Sta=5012.7,5054.4
Exp/Cntr=0.3,0.1

Type RM Length L Ch R = 1,8696,638,638,638
BEGIN DESCRIPTION:
Mapping XS 9971d29d
END DESCRIPTION:
XS GIS Cut Line= 3
      2518563.35     13532120.51      2517032.12     13531589.26
      2515834.20     13530724.68
#Sta/Elev= 30
  3363.9  201.38  3499.6  197.38  3636.0  194.34  3885.1  190.82  4035.5  186.27
  4187.4  183.06  4315.6  180.44  4496.6  178.73  4599.7  177.13  4664.1  176.43
  4835.0  171.48  4917.1  169.31  4960.4  169.62  4971.0  168.22  4979.2  162.25
  4980.2  161.75  5020.9  162.25  5035.6  163.35  5042.8  168.36  5079.8  171.36
  5253.8  172.63  5308.0  171.96  5491.5  173.05  5659.4  175.98  5823.3  174.57
  6009.8  174.97  6139.8  177.64  6267.4  182.48  6406.3  184.96  6462.0  186.65
#Mann=11,-1,0
  3363.9    0.05       0  3499.6    0.04       0  4187.4    0.05       0
  4496.6    0.04       0  4599.7    0.05       0  4835.0     0.1       0
  4979.2    0.05       0  5020.9     0.1       0  5253.8    0.05       0
  5491.5    0.12       0  6406.3    0.05       0
Bank Sta=4979.2,5020.9
Exp/Cntr=0.3,0.1

Type RM Length L Ch R = 1,8058,559,559,559
BEGIN DESCRIPTION:
FIVEMILE CREEK 9.0
END DESCRIPTION:
XS GIS Cut Line= 3
      2518175.01     13531525.00      2517375.00     13531075.00
      2516224.97     13530674.99
#Sta/Elev= 30
  4082.1  196.94  4109.8  194.54  4178.6  188.54  4252.0  185.67  4400.8  179.58
  4956.1  168.86  4964.6  169.39  4965.4  162.25  4966.4  161.75  5007.2  162.25
  5046.6  167.40  5072.4  166.03  5095.3  171.63  5202.1  171.17  5307.0  171.62
  5383.5  180.15  5402.3  178.19  5409.3  175.20  5414.6  176.15  5440.4  168.01
  5474.7  165.42  5497.3  164.86  5502.6  167.26  5528.4  167.87  5541.0  170.84
  5912.7  178.66  6015.4  181.86  6114.0  188.85  6196.4  189.46  6217.6  189.23
#Mann=13,-1,0
  4082.1   0.013       0  4109.8    0.12       0  4178.6   0.013       0
  4252.0    0.05       0  4400.8    0.12       0  4956.1     0.1       0
  4965.4    0.05       0  5007.2     0.1       0  5202.1    0.12       0
  5474.7    0.05       0  5541.0    0.12       0  5912.7    0.05       0
  6196.4    0.12       0
Bank Sta=4965.4,5007.2
Exp/Cntr=0.3,0.1

Type RM Length L Ch R = 1,7499,577,577,577
BEGIN DESCRIPTION:
FIVEMILE CREEK 8.0
END DESCRIPTION:
XS GIS Cut Line= 3
      2518274.97     13531424.96      2517675.00     13530625.00
      2516375.02     13530675.00
#Sta/Elev= 30
  4004.6  197.45  4154.6  186.80  4304.6  181.37  4561.8  175.92  4741.5  172.10
  4811.8  170.93  4876.4  171.42  4897.3  170.28  4911.8  171.07  4918.1  169.74
  4926.3  162.68  4927.3  162.18  4968.2  162.68  4976.4  164.18  4997.3  165.17
  5034.6  164.85  5044.6  167.21  5054.6  168.03  5114.6  169.37  5124.6  167.65
  5144.7  167.32  5184.7  169.30  5203.3  168.91  5314.8  171.91  5785.1  172.36
  6041.5  181.78  6172.9  185.96  6177.9  184.92  6235.5  186.69  6305.5  191.39
#Mann=7,-1,0
  4004.6    0.12       0  4561.8    0.05       0  4741.5     0.1       0
  4926.3    0.05       0  4968.2     0.1       0  5203.3    0.12       0
  6041.5    0.05       0
Bank Sta=4926.3,4968.2
Exp/Cntr=0.3,0.1

Type RM Length L Ch R = 1,6922,399,399,399
BEGIN DESCRIPTION:
FIVEMILE CREEK 7.0
END DESCRIPTION:
XS GIS Cut Line= 5
      2518707.09     13530461.06      2517896.83     13530180.46
      2517875.00     13530175.00      2517834.17     13530184.86
      2516229.45     13529831.71
#Sta/Elev= 30
  4114.5  198.22  4161.4  198.26  4213.3  196.73  4316.0  190.04  4432.4  182.55
  4589.3  174.90  4789.4  169.12  4831.3  169.42  4833.4  169.43  4936.5  169.27
  4952.7  168.94  4984.2  162.34  5012.5  161.03  5013.5  160.53  5054.4  161.03
  5055.0  167.28  5066.3  169.08  5098.3  168.81  5147.6  167.66  5158.5  165.47
  5269.5  169.79  5363.3  172.36  5498.8  171.40  5706.4  172.43  5929.1  177.71
  5942.4  178.33  6029.1  180.77  6173.1  184.88  6261.5  186.92  6679.6  194.78
#Mann=19,-1,0
  4114.5    0.12       0  4161.4    0.05       0  4316.0    0.12       0
  4432.4    0.05       0  4589.3    0.12       0  4831.3    0.05       0
  4833.4     0.1       0  4936.5    0.12       0  5012.5    0.05       0
  5054.4    0.12       0  5098.3    0.12       0  5269.5    0.05       0
  5498.8    0.12       0  5706.4    0.05       0  5929.1    0.04       0
  5942.4    0.05       0  6029.1    0.04       0  6173.1    0.05       0
  6261.5    0.04       0
Bank Sta=5012.5,5054.4
Exp/Cntr=0.3,0.1

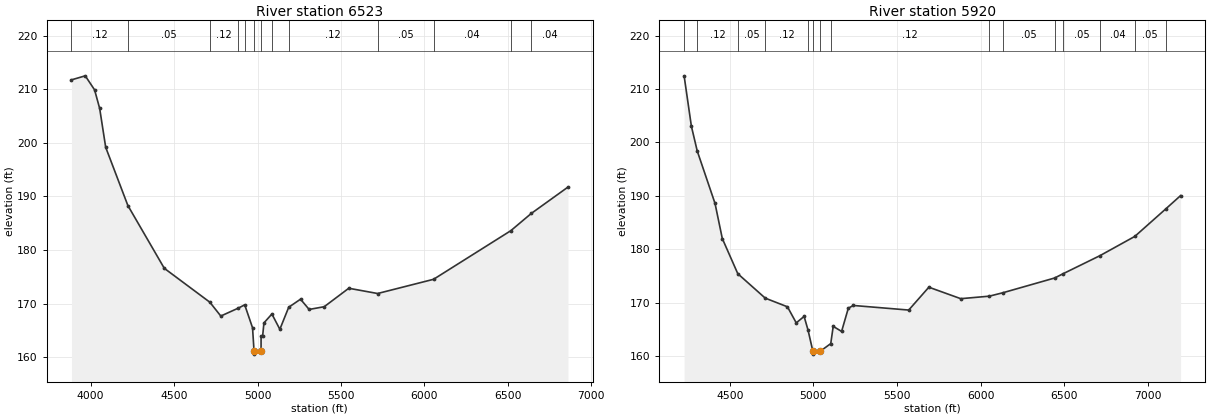
Type RM Length L Ch R = 1,6523,603,603,603
BEGIN DESCRIPTION:
FIVEMILE CREEK 6.0
END DESCRIPTION:
XS GIS Cut Line= 4
      2519075.71     13530188.84      2518075.00     13529825.00
      2518003.90     13529825.00      2516223.17     13529366.54
#Sta/Elev= 30
  3885.2  211.74  3967.7  212.49  4023.6  209.87  4054.1  206.40  4090.1  199.17
  4223.0  188.31  4441.2  176.61  4714.1  170.29  4779.8  167.71  4884.3  169.18
  4923.1  169.80  4970.0  165.52  4979.1  161.11  4980.1  160.61  5021.0  161.11
  5021.1  164.00  5030.3  163.94  5038.3  166.43  5085.9  168.09  5133.6  165.24
  5186.7  169.35  5257.5  170.85  5309.1  168.94  5399.5  169.45  5546.6  172.89
  5719.4  171.91  6054.6  174.56  6517.4  183.62  6640.3  186.84  6859.9  191.75
#Mann=13,-1,0
  3885.2    0.12       0  4223.0    0.05       0  4714.1    0.12       0
  4884.3     0.1       0  4923.1    0.12       0  4979.1    0.05       0
  5021.0    0.12       0  5085.9     0.1       0  5186.7    0.12       0
  5719.4    0.05       0  6054.6    0.04       0  6517.4    0.05       0
  6640.3    0.04       0
Bank Sta=4979.1,5021
Exp/Cntr=0.3,0.1

Type RM Length L Ch R = 1,5920,527,527,527
BEGIN DESCRIPTION:
FIVEMILE CREEK 5.0
END DESCRIPTION:
XS GIS Cut Line= 3
      2519124.98     13529724.99      2518425.00     13529425.00
      2516225.03     13529225.00
#Sta/Elev= 30
  4226.3  212.46  4269.8  203.03  4304.8  198.39  4411.2  188.58  4454.8  182.00
  4547.6  175.41  4711.8  170.84  4844.6  169.22  4897.2  166.21  4944.3  167.42
  4967.8  164.86  4997.0  160.86  4998.0  160.36  5039.0  160.86  5103.7  162.33
  5118.4  165.56  5168.6  164.61  5208.8  168.96  5238.9  169.47  5570.2  168.61
  5690.7  172.89  5881.5  170.74  6052.5  171.21  6133.5  171.85  6443.1  174.61
  6492.5  175.39  6714.8  178.80  6923.0  182.40  7107.6  187.53  7196.9  190.04
#Mann=15,-1,0
  4226.3    0.05       0  4304.8    0.12       0  4547.6    0.05       0
  4711.8    0.12       0  4967.8     0.1       0  4997.0    0.05       0
  5039.0     0.1       0  5103.7    0.12       0  6052.5    0.04       0
  6133.5    0.05       0  6443.1    0.04       0  6492.5    0.05       0
  6714.8    0.04       0  6923.0    0.05       0  7107.6    0.04       0
Bank Sta=4997,5039
Exp/Cntr=0.3,0.1