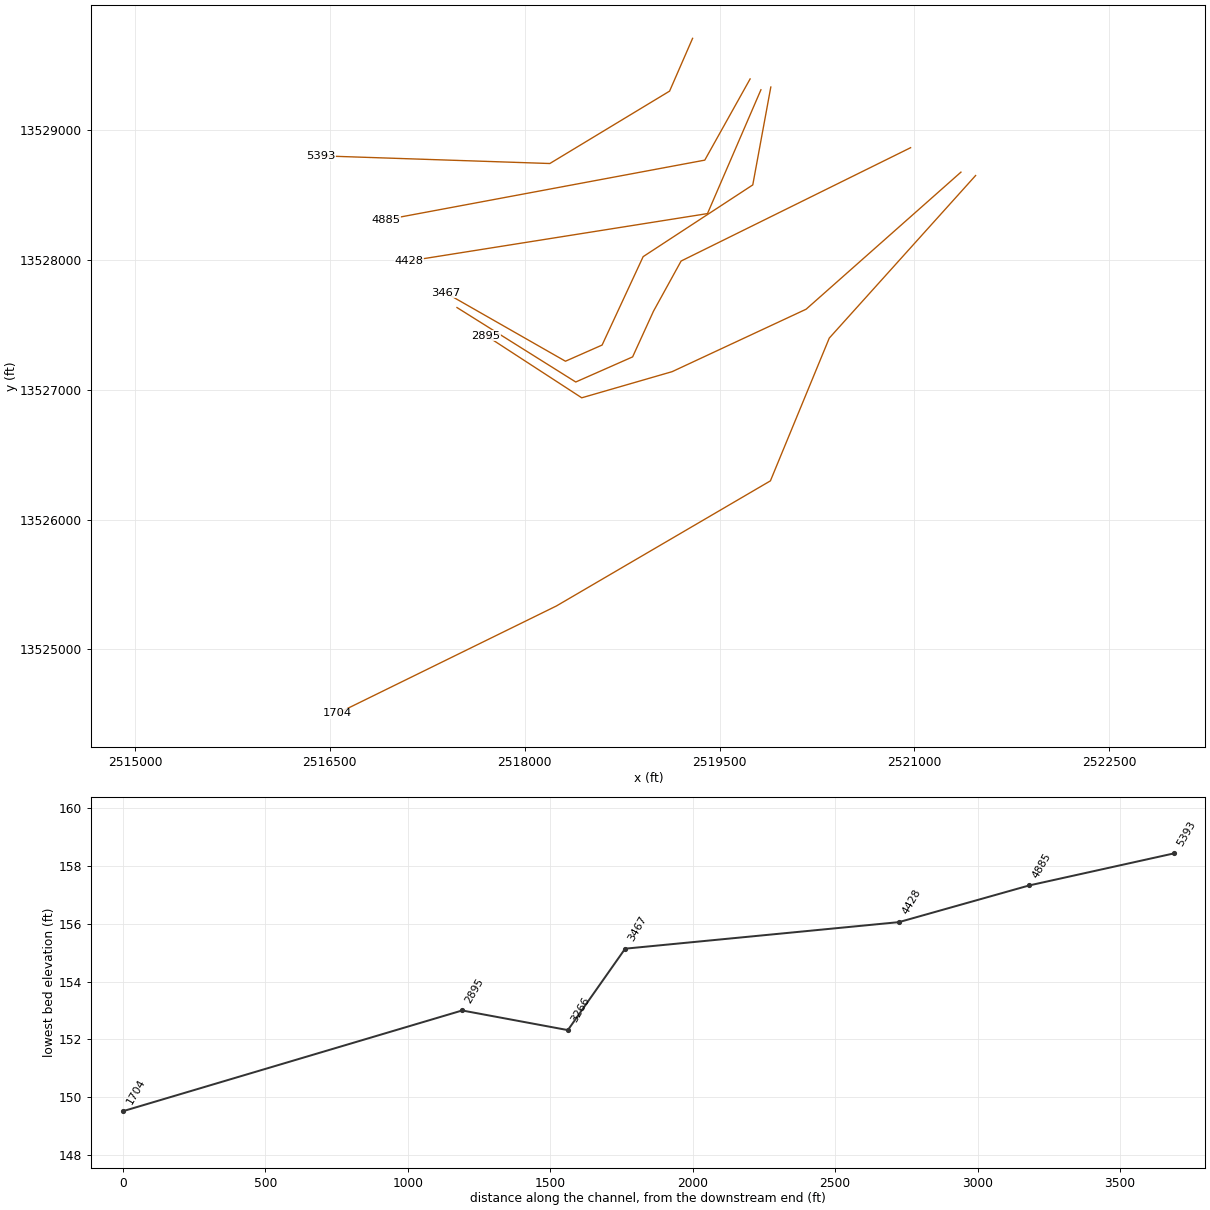
HEC-RAS study FIVEMILE CREEK.prj: FIVEMILE CREEK Base Level Engineering

--- FIVEMILE CREEK.g01 (geometry) --- (continued)

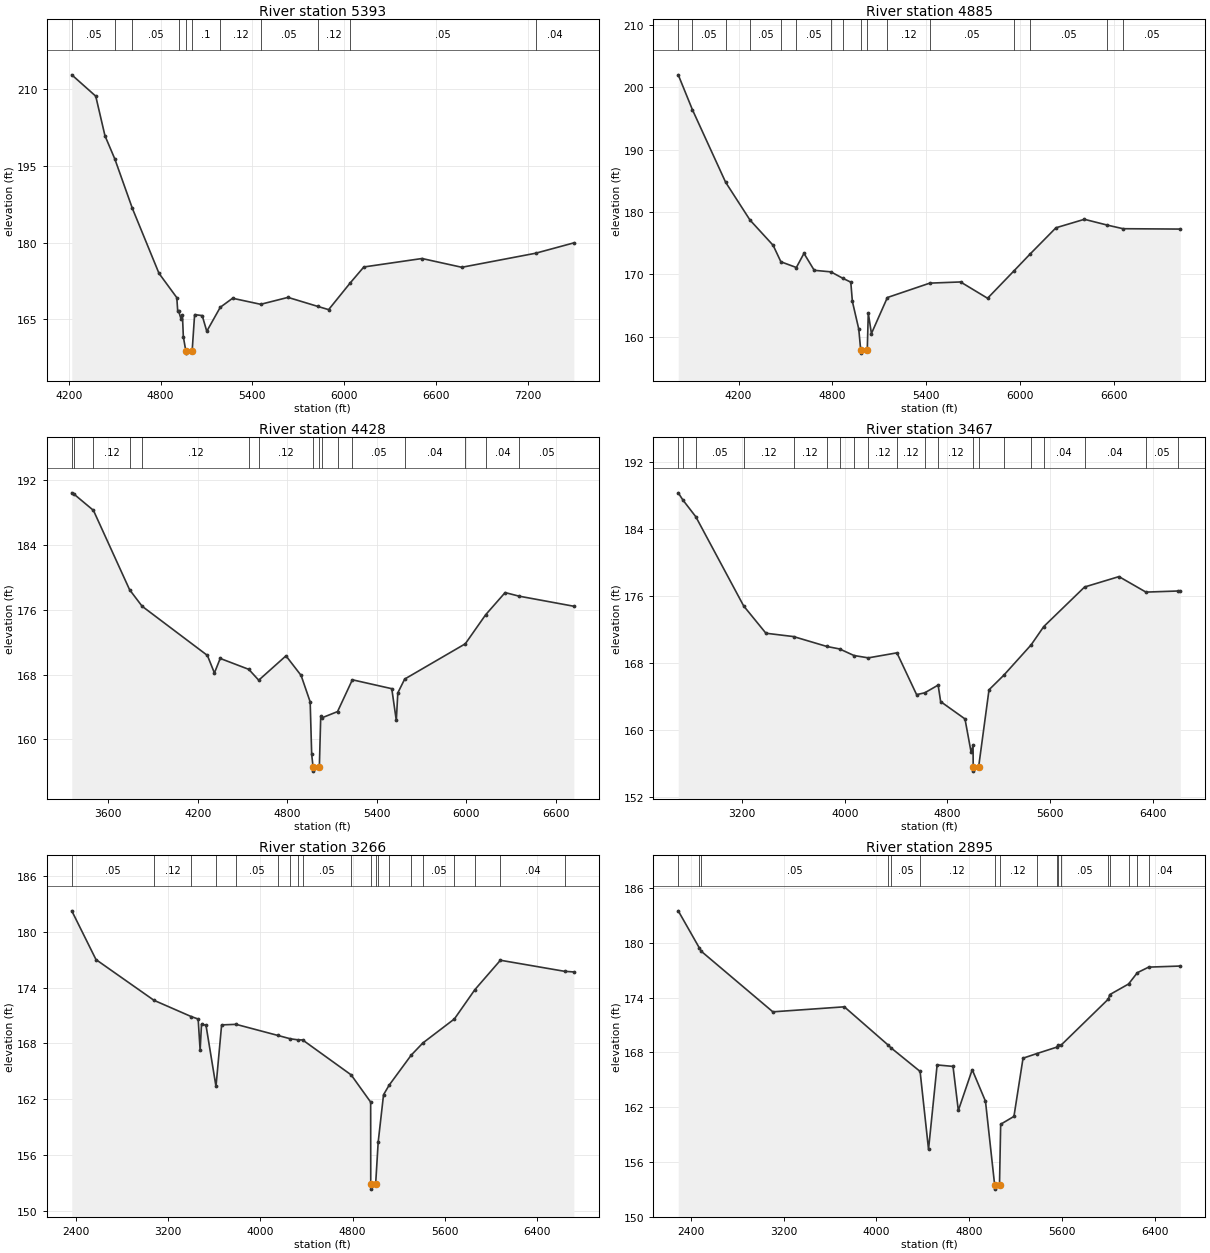
Type RM Length L Ch R = 1,5393,508,508,508
BEGIN DESCRIPTION:
Mapping XS af8d45d3
END DESCRIPTION:
XS GIS Cut Line= 4
      2519292.55     13529703.88      2519115.45     13529297.60
      2518193.58     13528740.30      2516433.01     13528799.43
#Sta/Elev= 30
  4219.8  212.71  4376.5  208.55  4436.8  200.83  4501.5  196.28  4615.9  186.67
  4789.9  174.00  4906.4  169.26  4912.2  166.70  4918.7  166.61  4933.6  165.15
  4943.2  165.93  4949.1  161.64  4964.9  158.94  4965.9  158.44  5006.9  158.94
  5022.8  165.95  5072.5  165.76  5102.3  162.70  5190.5  167.38  5271.1  169.14
  5454.6  167.96  5633.4  169.31  5828.0  167.55  5898.9  166.92  6040.0  172.13
  6129.0  175.24  6509.2  176.89  6769.4  175.18  7252.0  177.92  7501.8  179.94
#Mann=11,-1,0
  4219.8    0.05       0  4501.5    0.12       0  4615.9    0.05       0
  4918.7     0.1       0  4964.9    0.05       0  5006.9     0.1       0
  5190.5    0.12       0  5454.6    0.05       0  5828.0    0.12       0
  6040.0    0.05       0  7252.0    0.04       0
Bank Sta=4964.9,5006.9
Exp/Cntr=0.3,0.1

Type RM Length L Ch R = 1,4885,457,457,457
BEGIN DESCRIPTION:
Mapping XS d873099e
END DESCRIPTION:
XS GIS Cut Line= 3
      2519735.26     13529391.37      2519386.29     13528766.35
      2516933.18     13528308.02
#Sta/Elev= 30
  3814.5  202.02  3905.0  196.43  4117.6  184.77  4273.5  178.70  4421.6  174.64
  4471.0  172.00  4570.0  171.08  4618.7  173.35  4684.3  170.63  4791.0  170.38
  4868.5  169.33  4918.2  168.73  4928.4  165.63  4969.1  161.21  4981.6  157.83
  4982.6  157.33  5023.6  157.83  5030.1  163.77  5050.2  160.47  5152.2  166.26
  5423.5  168.57  5620.2  168.76  5793.1  166.14  5963.1  170.57  6062.6  173.18
  6230.6  177.46  6412.4  178.82  6560.1  177.88  6659.6  177.31  7025.9  177.25
#Mann=16,-1,0
  3814.5    0.12       0  3905.0    0.05       0  4117.6    0.12       0
  4273.5    0.05       0  4471.0    0.12       0  4570.0    0.05       0
  4791.0    0.12       0  4868.5     0.1       0  4981.6    0.05       0
  5023.6     0.1       0  5152.2    0.12       0  5423.5    0.05       0
  5963.1    0.12       0  6062.6    0.05       0  6560.1    0.04       0
  6659.6    0.05       0
Bank Sta=4981.6,5023.6
Exp/Cntr=0.3,0.1

Type RM Length L Ch R = 1,4428,961,961,961
BEGIN DESCRIPTION:
Mapping XS 06d5643a
END DESCRIPTION:
XS GIS Cut Line= 3
      2519818.57     13529307.99      2519407.12     13528354.89
      2517110.29     13527990.31
#Sta/Elev= 30
  3356.5  190.46  3372.6  190.28  3501.7  188.29  3744.0  178.48  3827.8  176.44
  4265.2  170.36  4312.2  168.19  4350.9  169.99  4542.5  168.64  4609.0  167.30
  4791.6  170.31  4892.9  167.89  4953.7  164.62  4963.8  158.15  4973.2  156.56
  4974.2  156.06  5015.2  156.56  5024.5  162.84  5033.8  162.66  5137.2  163.42
  5236.3  167.35  5500.4  166.25  5530.8  162.32  5540.9  165.73  5586.9  167.44
  5993.0  171.80  6129.4  175.39  6259.8  178.13  6352.7  177.69  6720.2  176.44
#Mann=16,-1,0
  3356.5    0.12       0  3372.6    0.05       0  3501.7    0.12       0
  3744.0    0.05       0  3827.8    0.12       0  4542.5    0.05       0
  4609.0    0.12       0  4973.2    0.05       0  5015.2    0.12       0
  5033.8     0.1       0  5137.2    0.12       0  5236.3    0.05       0
  5586.9    0.04       0  5993.0    0.05       0  6129.4    0.04       0
  6352.7    0.05       0
Bank Sta=4973.2,5015.2
Exp/Cntr=0.3,0.1

Type RM Length L Ch R = 1,3467,201,201,201
BEGIN DESCRIPTION:
Mapping XS 53f27cb0
END DESCRIPTION:
XS GIS Cut Line= 6
      2519894.59     13529329.08      2519755.70     13528575.58
      2518911.95     13528023.49      2518595.97     13527342.94
      2518313.82     13527218.55      2517391.08     13527745.19
#Sta/Elev= 30
  2700.7  188.36  2737.2  187.50  2838.0  185.50  3210.9  174.86  3384.5  171.60
  3600.3  171.20  3859.9  170.02  3959.8  169.72  4071.3  168.94  4182.9  168.66
  4406.1  169.26  4559.6  164.27  4623.3  164.49  4727.5  165.41  4747.1  163.44
  4936.9  161.37  4984.5  157.41  4999.8  158.20  5001.0  155.64  5002.0  155.14
  5043.3  155.64  5124.3  164.85  5239.0  166.58  5452.6  170.21  5551.4  172.40
  5869.7  177.12  6137.7  178.36  6348.0  176.51  6594.8  176.64  6616.1  176.60
#Mann=20,-1,0
  2700.7    0.05       0  2737.2    0.12       0  2838.0    0.05       0
  3210.9    0.12       0  3600.3    0.12       0  3859.9   0.013       0
  3959.8    0.05       0  4071.3    0.12       0  4182.9    0.12       0
  4406.1    0.12       0  4623.3    0.05       0  4727.5    0.12       0
  5001.0    0.05       0  5043.3     0.1       0  5239.0    0.05       0
  5452.6    0.05       0  5551.4    0.04       0  5869.7    0.04       0
  6348.0    0.05       0  6594.8    0.12       0
Bank Sta=5001,5043.3
Exp/Cntr=0.3,0.1

Type RM Length L Ch R = 1,3266,371,371,371
BEGIN DESCRIPTION:
Mapping XS 951320cf
END DESCRIPTION:
XS GIS Cut Line= 6
      2520970.56     13528862.05      2519204.05     13527989.64
      2518991.37     13527603.35      2518830.78     13527251.79
      2518393.12     13527058.60      2517478.94     13527631.69
#Sta/Elev= 30
  2363.0  182.28  2573.2  177.03  3075.7  172.65  3398.8  170.90  3459.5  170.63
  3476.6  167.28  3488.6  170.06  3527.4  169.97  3614.2  163.37  3663.0  170.00
  3788.4  170.06  4152.8  168.86  4260.5  168.50  4326.9  168.39  4365.9  168.38
  4786.8  164.62  4956.1  161.69  4956.8  152.82  4957.8  152.32  4999.1  152.82
  5021.4  157.38  5067.8  162.48  5115.8  163.50  5308.3  166.75  5409.5  168.06
  5682.5  170.64  5860.1  173.79  6081.7  176.96  6637.9  175.77  6718.9  175.70
#Mann=20,-1,0
  2363.0    0.05       0  3075.7    0.12       0  3398.8    0.12       0
  3614.2    0.12       0  3788.4    0.05       0  4152.8    0.12       0
  4260.5    0.05       0  4326.9    0.12       0  4365.9    0.05       0
  4786.8    0.05       0  4956.8    0.05       0  4999.1    0.05       0
  5021.4    0.05       0  5115.8    0.12       0  5308.3    0.12       0
  5409.5    0.05       0  5682.5   0.013       0  5860.1    0.04       0
  6081.7    0.04       0  6637.9    0.05       0
Bank Sta=4956.8,4999.1
Exp/Cntr=0.3,0.1

Type RM Length L Ch R = 1,2895,1191,1191,1191
BEGIN DESCRIPTION:
FIVEMILE CREEK 3.0
END DESCRIPTION:
XS GIS Cut Line= 6
      2521358.14     13528673.99      2520166.48     13527618.89
      2519212.50     13527174.29      2519134.80     13527138.08
      2518439.23     13526936.95      2517703.60     13527415.32
#Sta/Elev= 30
  2290.5  183.50  2473.2  179.42  2489.9  179.06  3106.9  172.43  3723.4  172.98
  4098.7  168.82  4122.7  168.52  4377.0  165.90  4449.8  157.36  4523.9  166.61
  4661.1  166.45  4706.9  161.62  4826.7  166.09  4941.1  162.63  5019.8  153.50
  5020.8  153.00  5062.1  153.50  5072.2  160.11  5186.7  160.97  5265.1  167.35
  5385.0  167.86  5560.8  168.58  5566.0  168.77  5591.7  168.76  6002.1  173.84
  6012.4  174.31  6175.4  175.48  6251.3  176.72  6348.7  177.33  6621.9  177.45
#Mann=17,-1,0
  2290.5    0.05       0  2473.2   0.013       0  2489.9    0.05       0
  4098.7    0.12       0  4122.7    0.05       0  4377.0    0.12       0
  5019.8    0.05       0  5062.1    0.12       0  5385.0    0.04       0
  5560.8    0.05       0  5566.0    0.04       0  5591.7    0.05       0
  6002.1   0.013       0  6012.4    0.05       0  6175.4    0.04       0
  6251.3   0.013       0  6348.7    0.04       0
Bank Sta=5019.8,5062.1
Exp/Cntr=0.3,0.1

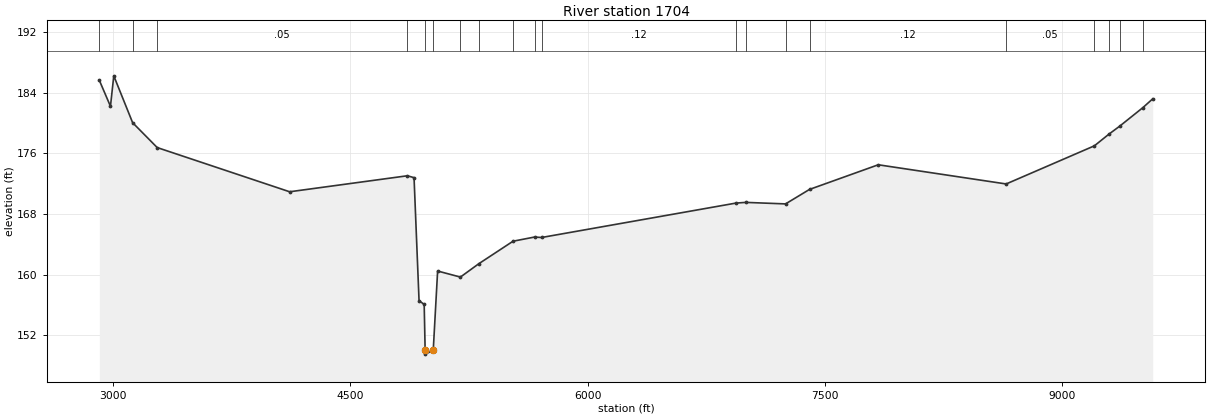
Type RM Length L Ch R = 1,1704,0,0,0
BEGIN DESCRIPTION:
FIVEMILE CREEK 2.0
END DESCRIPTION:
XS GIS Cut Line= 5
      2521470.97     13528647.93      2520344.62     13527396.55
      2519891.49     13526297.60      2518243.99     13525334.44
      2516558.92     13524507.88
#Sta/Elev= 30
  2914.5  185.62  2984.8  182.19  3005.8  186.21  3124.9  180.03  3280.2  176.75
  4117.2  170.92  4861.2  173.03  4903.5  172.78  4935.1  156.57  4967.6  156.06
  4973.6  150.01  4974.6  149.51  5024.8  150.01  5052.5  160.47  5196.4  159.67
  5313.4  161.44  5529.2  164.40  5665.1  164.95  5709.2  164.89  6938.5  169.43
  7000.3  169.52  7251.4  169.32  7402.8  171.23  7837.4  174.48  8645.7  171.95
  9203.4  176.98  9295.9  178.53  9362.5  179.56  9509.9  182.02  9572.1  183.18
#Mann=20,-1,0
  2914.5    0.05       0  3124.9   0.013       0  3280.2    0.05       0
  4861.2    0.12       0  4973.6    0.05       0  5024.8    0.12       0
  5196.4     0.1       0  5313.4    0.12       0  5529.2    0.12       0
  5665.1    0.05       0  5709.2    0.12       0  6938.5    0.05       0
  7000.3    0.12       0  7251.4    0.05       0  7402.8    0.12       0
  8645.7    0.05       0  9203.4    0.12       0  9295.9    0.05       0
  9362.5    0.12       0  9509.9    0.05       0
Bank Sta=4973.6,5024.8
Exp/Cntr=0.3,0.1

Chan Stop Cuts=-1