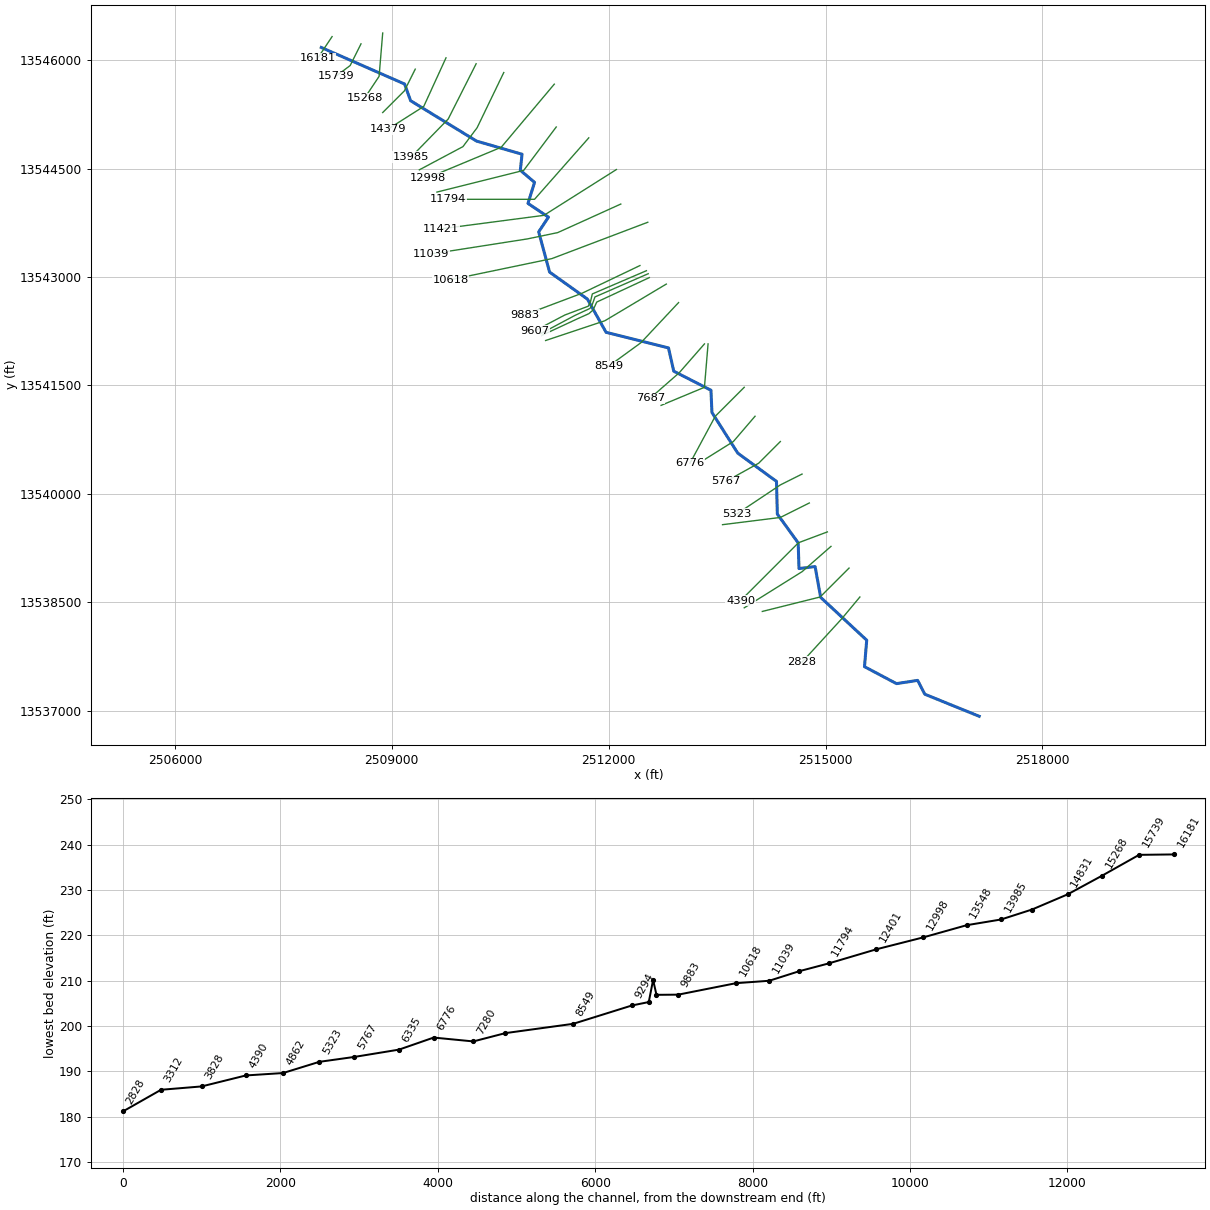
--- HOG BRANCH.prj (project) ---

Proj Title=HOG BRANCH Base Level Engineering
Current Plan=p01
Default Exp/Contr=0.3,0.1
English Units
Geom File=g01
Flow File=f01
Plan File=p01
Y Axis Title=Elevation
X Axis Title(PF)=Main Channel Distance
X Axis Title(XS)=Station
BEGIN DESCRIPTION:
HOG BRANCH
END DESCRIPTION:
DSS Export Rating Curves= 0
DSS Export Rating Curve Sorted= 0
DSS Export Volume Flow Curves= 0
DXF OffsetX= 0
DXF OffsetY= 0
DXF ScaleX= 1
DXF ScaleY= 10

--- HOG BRANCH.p01 (plan) ---

Plan Title=Multiple Run
Short Identifier=Multiple
Geom File=g01
Flow File=f01
Subcritical Flow
K Sum by GR= 0
Std Step Tol= 0.01
Critical Tol= 0.01
Num of Std Step Trials= 20
Max Error Tol= 0.3
Flow Tol Ratio= 0.001
Split Flow NTrial= 30
Split Flow Tol= 0.02
Split Flow Ratio= 0.02
Log Output Level= 0
Friction Slope Method= 1
Unsteady Friction Slope Method= 2
Unsteady Bridges Friction Slope Method= 1
Parabolic Critical Depth
Global Vel Dist=  1 , 1 , 1
Global Log Level= 0
CheckData=True
Encroach Param= -1, 0, 0, 0
BEGIN DESCRIPTION:
Multiple Run
END DESCRIPTION:

--- HOG BRANCH.f01 (steady flow) ---

Flow Title=Multiple
Number of Profiles=7
Profile Names=10-year,25-year,50-year,1pct_min,100-year,1pct_plu,500-year
River Rch & RM= HOG BRANCH,Reach-1,16181
     433     679     895     572    1141    2277    1833
River Rch & RM= HOG BRANCH,Reach-1,13985
     600     959    1279     826    1648    3288    2705
River Rch & RM= HOG BRANCH,Reach-1,10618
     841    1369    1850    1208    2411    4810    4053
River Rch & RM= HOG BRANCH,Reach-1,8549
    1016    1660    2248    1470    2934    5853    4945
River Rch & RM= HOG BRANCH,Reach-1,1479
    1164    1915    2606    1712    3416    6815    5809
Boundary for River Rch & Prof#=HOG BRANCH,Reach-1,1
Up Type=0
Dn Type=3
Dn Slope=0.005
Boundary for River Rch & Prof#=HOG BRANCH,Reach-1,2
Up Type=0
Dn Type=3
Dn Slope=0.005
Boundary for River Rch & Prof#=HOG BRANCH,Reach-1,3
Up Type=0
Dn Type=3
Dn Slope=0.005
Boundary for River Rch & Prof#=HOG BRANCH,Reach-1,4
Up Type=0
Dn Type=3
Dn Slope=0.005
Boundary for River Rch & Prof#=HOG BRANCH,Reach-1,5
Up Type=0
Dn Type=3
Dn Slope=0.005
Boundary for River Rch & Prof#=HOG BRANCH,Reach-1,6
Up Type=0
Dn Type=3
Dn Slope=0.005
Boundary for River Rch & Prof#=HOG BRANCH,Reach-1,7
Up Type=0
Dn Type=3
Dn Slope=0.005

--- HOG BRANCH.g01 (geometry) ---

Geom Title=Existing Conditions

River Reach=HOG BRANCH,Reach-1
Reach XY= 30
      2508025.00     13546175.00      2509177.70     13545669.64
      2509261.00     13545438.62      2510172.72     13544880.13
      2510802.31     13544698.52      2510778.46     13544476.48
      2510975.19     13544309.71      2510884.30     13544018.31
      2511167.41     13543828.35      2511032.29     13543624.91
      2511182.85     13543068.81      2511705.72     13542695.47
      2511964.95     13542235.06      2512827.47     13542019.55
      2512900.53     13541697.85      2513414.53     13541434.83
      2513428.75     13541126.55      2513785.51     13540564.48
      2514321.25     13540173.45      2514333.08     13539721.70
      2514621.25     13539323.45      2514632.81     13538968.14
      2514855.38     13538995.69      2514932.81     13538568.81
      2515569.16     13537977.29      2515538.34     13537611.21
      2515981.03     13537376.62      2516273.78     13537421.57
      2516372.26     13537230.34      2517125.00     13536925.00

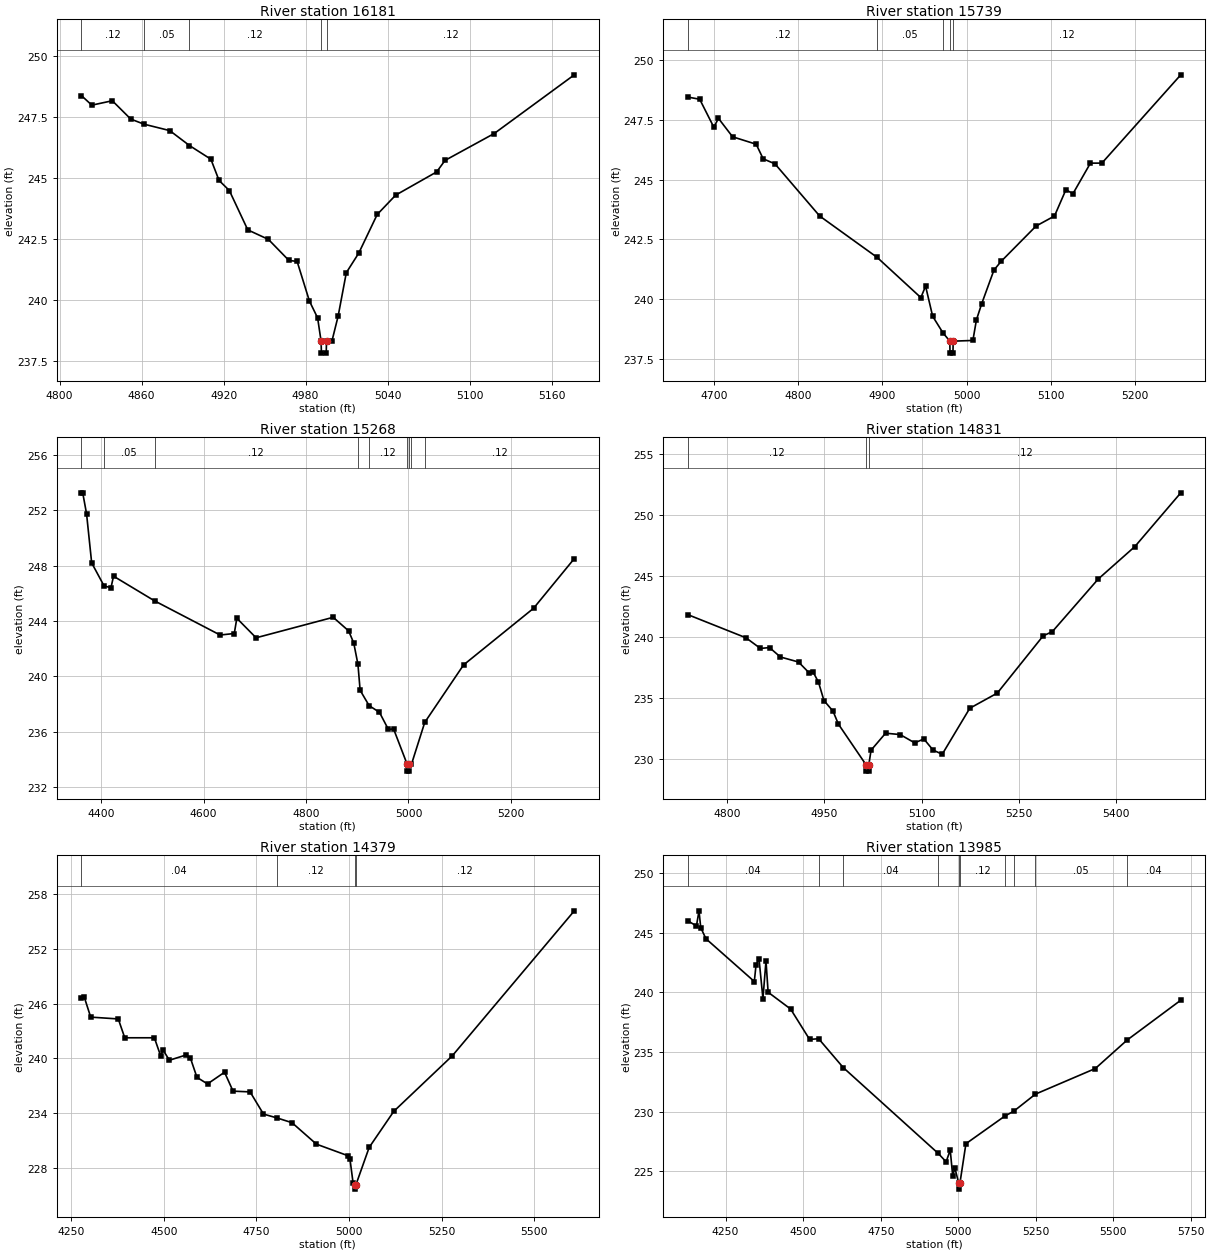
Type RM Length L Ch R = 1,16181,442,442,442
BEGIN DESCRIPTION:
HOG BRANCH 32.0
END DESCRIPTION:
XS GIS Cut Line= 3
      2508175.02     13546325.04      2508075.00     13546175.00
      2507975.00     13546025.00
#Sta/Elev= 30
  4816.0  248.37  4823.6  247.98  4838.6  248.16  4852.1  247.41  4861.9  247.20
  4880.6  246.94  4895.0  246.33  4910.7  245.77  4916.7  244.90  4924.2  244.49
  4937.7  242.88  4952.8  242.49  4967.8  241.63  4973.8  241.59  4982.8  239.97
  4988.8  239.28  4991.3  238.34  4991.6  237.84  4995.1  237.84  4995.3  238.34
  4999.3  238.34  5003.8  239.35  5009.8  241.13  5018.9  241.93  5032.4  243.51
  5045.9  244.30  5075.9  245.25  5082.0  245.72  5118.0  246.82  5176.6  249.22
#Mann=5,-1,0
  4816.0    0.12       0  4861.9    0.05       0  4895.0    0.12       0
  4991.3    0.05       0  4995.3    0.12       0
Bank Sta=4991.3,4995.3
Exp/Cntr=0.3,0.1

Type RM Length L Ch R = 1,15739,471,471,471
BEGIN DESCRIPTION:
HOG BRANCH 31.0
END DESCRIPTION:
XS GIS Cut Line= 3
      2508575.00     13546225.00      2508425.00     13545925.00
      2508225.01     13545775.01
#Sta/Elev= 30
  4668.9  248.45  4682.9  248.36  4699.7  247.19  4705.2  247.56  4722.0  246.79
  4750.0  246.48  4758.3  245.87  4772.3  245.66  4825.4  243.48  4893.7  241.75
  4945.6  240.07  4951.2  240.55  4959.6  239.29  4971.8  238.60  4980.0  238.25
  4980.2  237.75  4983.7  237.75  4984.0  238.25  5007.4  238.28  5011.6  239.14
  5017.9  239.82  5032.4  241.22  5040.8  241.58  5082.4  243.06  5104.3  243.48
  5117.9  244.58  5126.2  244.41  5147.0  245.69  5160.6  245.69  5254.3  249.38
#Mann=5,-1,0
  4668.9    0.12       0  4893.7    0.05       0  4971.8    0.12       0
  4980.0    0.05       0  4984.0    0.12       0
Bank Sta=4980,4984
Exp/Cntr=0.3,0.1

Type RM Length L Ch R = 1,15268,437,437,437
BEGIN DESCRIPTION:
HOG BRANCH 30.0
END DESCRIPTION:
XS GIS Cut Line= 3
      2508875.00     13546374.96      2508825.00     13545775.00
      2508625.00     13545475.00
#Sta/Elev= 30
  4361.3  253.25  4363.8  253.25  4371.3  251.74  4381.3  248.19  4405.6  246.52
  4419.0  246.40  4424.0  247.23  4504.0  245.45  4632.2  242.98  4659.8  243.09
  4664.8  244.19  4702.4  242.78  4853.0  244.26  4883.1  243.28  4893.1  242.41
  4901.3  240.87  4905.6  238.99  4923.2  237.88  4943.3  237.40  4960.8  236.16
  4970.9  236.20  4997.4  233.65  4997.6  233.15  5001.1  233.15  5001.4  233.65
  5005.9  233.65  5031.8  236.67  5107.6  240.82  5244.3  244.91  5323.9  248.50
#Mann=9,-1,0
  4361.3    0.12       0  4405.6    0.05       0  4504.0    0.12       0
  4901.3    0.05       0  4923.2    0.12       0  4997.4    0.05       0
  5001.4    0.12       0  5005.9    0.05       0  5031.8    0.12       0
Bank Sta=4997.4,5001.4
Exp/Cntr=0.3,0.1

Type RM Length L Ch R = 1,14831,452,452,452
BEGIN DESCRIPTION:
HOG BRANCH 29.0
END DESCRIPTION:
XS GIS Cut Line= 3
      2509325.02     13545875.04      2509175.00     13545575.00
      2508875.01     13545275.01
#Sta/Elev= 30
  4739.6  241.83  4829.1  239.94  4851.4  239.07  4865.4  239.14  4882.2  238.37
  4910.1  237.96  4926.9  237.05  4932.5  237.15  4940.9  236.31  4949.3  234.81
  4963.3  233.94  4971.6  232.88  5014.4  229.54  5014.6  229.04  5018.1  229.04
  5018.4  229.54  5021.9  230.75  5044.3  232.14  5066.7  232.03  5089.2  231.35
  5103.3  231.67  5117.5  230.76  5131.6  230.42  5174.1  234.18  5216.5  235.42
  5287.2  240.10  5301.3  240.44  5372.0  244.74  5428.6  247.40  5499.3  251.79
#Mann=3,-1,0
  4739.6    0.12       0  5014.4    0.05       0  5018.4    0.12       0
Bank Sta=5014.4,5018.4
Exp/Cntr=0.3,0.1

Type RM Length L Ch R = 1,14379,394,394,394
BEGIN DESCRIPTION:
Mapping XS 6f20d48e
END DESCRIPTION:
XS GIS Cut Line= 3
      2509750.68     13546032.06      2509442.51     13545359.31
      2508943.36     13545042.46
#Sta/Elev= 30
  4277.3  246.59  4285.1  246.69  4302.3  244.52  4376.8  244.32  4394.3  242.26
  4474.3  242.26  4491.8  240.22  4497.3  240.96  4514.8  239.80  4560.0  240.38
  4571.8  240.02  4589.3  237.93  4617.8  237.21  4663.8  238.49  4686.8  236.42
  4732.8  236.34  4769.0  233.91  4805.4  233.49  4846.0  232.97  4912.0  230.62
  4996.9  229.36  5002.4  229.04  5011.0  226.38  5014.9  226.20  5015.1  225.70
  5018.9  226.20  5054.5  230.27  5120.9  234.21  5279.0  240.29  5608.5  256.15
#Mann=4,-1,0
  4277.3    0.04       0  4805.4    0.12       0  5014.9    0.05       0
  5018.9    0.12       0
Bank Sta=5014.9,5018.9
Exp/Cntr=0.3,0.1

Type RM Length L Ch R = 1,13985,437,437,437
BEGIN DESCRIPTION:
Mapping XS f69a97d9
END DESCRIPTION:
XS GIS Cut Line= 3
      2510167.33     13545949.57      2509781.06     13545185.70
      2509269.42     13544661.06
#Sta/Elev= 30
  4128.5  246.01  4156.0  245.58  4164.3  246.85  4169.9  245.44  4186.6  244.51
  4342.6  240.92  4348.2  242.33  4357.7  242.83  4370.4  239.48  4380.2  242.65
  4387.1  240.02  4459.6  238.61  4520.8  236.06  4549.9  236.12  4629.2  233.70
  4935.3  226.50  4961.0  225.79  4974.1  226.79  4982.1  224.61  4989.2  225.27
  5001.4  224.00  5001.6  223.50  5005.4  224.00  5024.7  227.31  5150.8  229.64
  5179.1  230.04  5248.8  231.47  5441.9  233.62  5544.5  236.01  5717.3  239.35
#Mann=10,-1,0
  4128.5    0.04       0  4549.9    0.03       0  4629.2    0.04       0
  4935.3    0.12       0  5001.4    0.05       0  5005.4    0.12       0
  5150.8    0.05       0  5179.1    0.04       0  5248.8    0.05       0
  5544.5    0.04       0
Bank Sta=5001.4,5005.4
Exp/Cntr=0.3,0.1

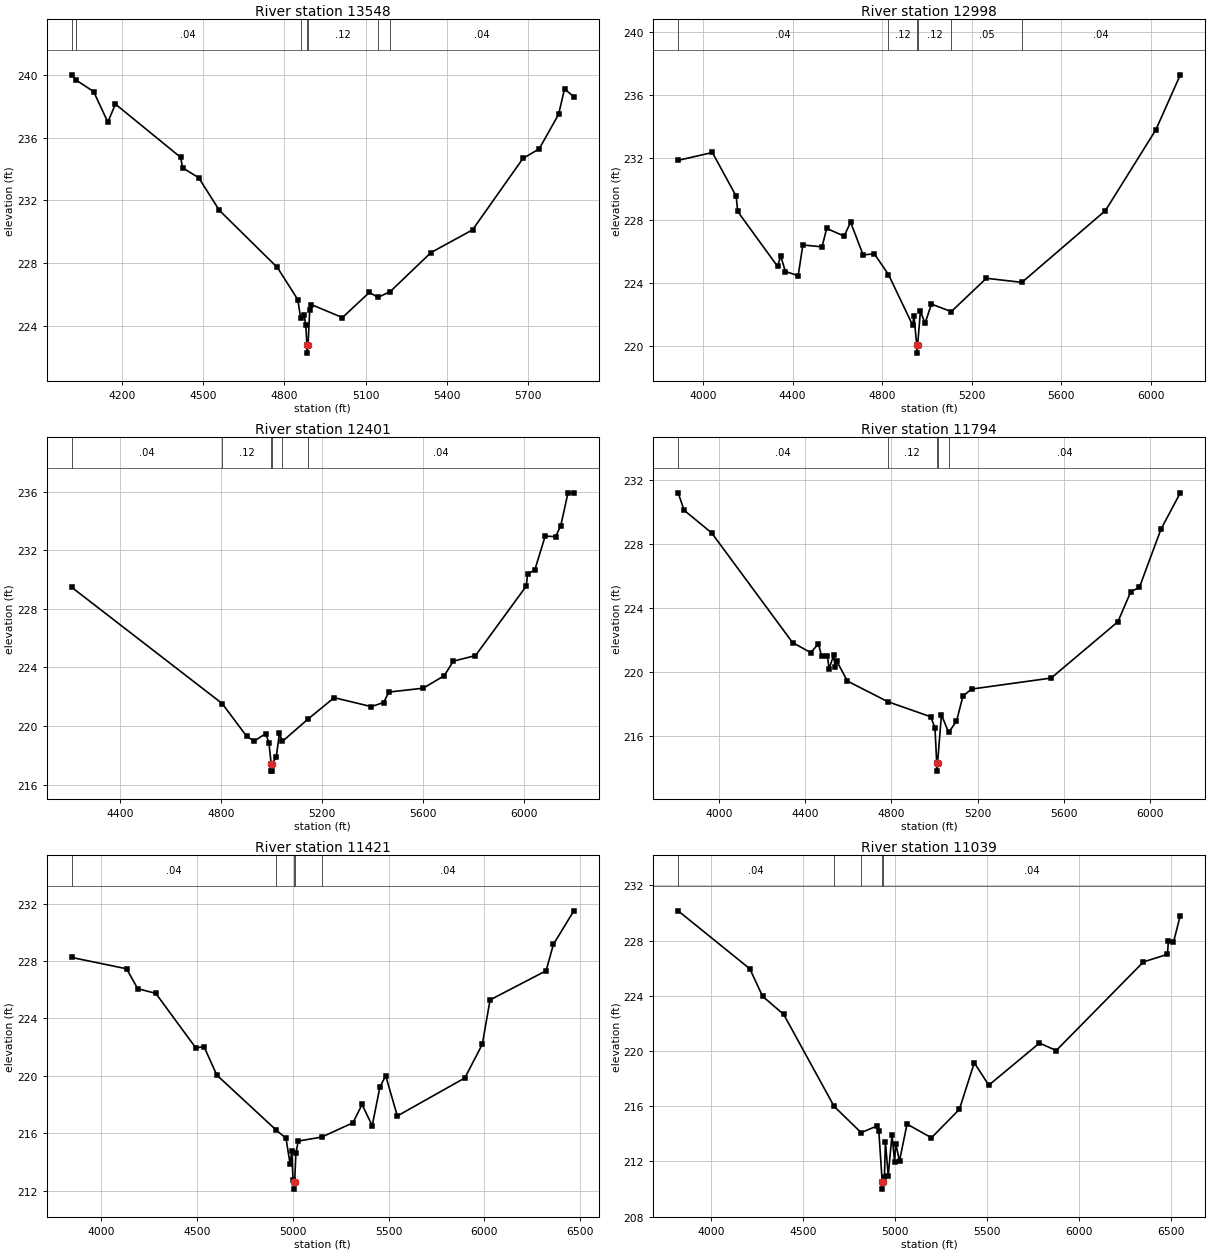
Type RM Length L Ch R = 1,13548,550,550,550
BEGIN DESCRIPTION:
Mapping XS 125699bc
END DESCRIPTION:
XS GIS Cut Line= 4
      2510549.30     13545828.10      2510180.36     13545064.17
      2509985.05     13544803.75      2509381.78     13544482.59
#Sta/Elev= 30
  4012.9  240.01  4028.8  239.68  4094.1  238.94  4146.7  236.99  4174.8  238.14
  4416.1  234.74  4423.4  234.07  4482.8  233.44  4559.0  231.36  4773.6  227.71
  4849.2  225.66  4859.7  224.49  4872.5  224.68  4878.7  224.03  4883.2  222.74
  4883.5  222.24  4887.2  222.74  4893.3  224.97  4899.6  225.34  5014.2  224.51
  5114.2  226.12  5145.8  225.80  5191.2  226.17  5341.7  228.66  5495.5  230.11
  5681.9  234.67  5741.9  235.28  5813.7  237.48  5835.7  239.10  5870.2  238.62
#Mann=7,-1,0
  4012.9   0.013       0  4028.8    0.04       0  4859.7    0.12       0
  4883.2    0.05       0  4887.2    0.12       0  5145.8    0.05       0
  5191.2    0.04       0
Bank Sta=4883.2,4887.2
Exp/Cntr=0.3,0.1

Type RM Length L Ch R = 1,12998,597,597,597
BEGIN DESCRIPTION:
Mapping XS 71169141
END DESCRIPTION:
XS GIS Cut Line= 3
      2511248.10     13545667.50      2510514.56     13544795.07
      2509494.90     13544369.85
#Sta/Elev= 30
  3888.6  231.82  4041.6  232.32  4148.2  229.54  4154.8  228.57  4332.9  225.08
  4347.2  225.73  4368.0  224.75  4425.3  224.49  4446.1  226.44  4531.9  226.32
  4552.7  227.49  4630.8  227.00  4659.4  227.89  4715.4  225.81  4766.0  225.87
  4828.7  224.56  4936.4  221.35  4942.9  221.89  4955.2  220.06  4955.5  219.56
  4959.2  220.06  4971.5  222.22  4992.4  221.46  5021.0  222.68  5109.4  222.20
  5266.3  224.32  5425.3  224.06  5798.8  228.63  6024.1  233.77  6133.2  237.26
#Mann=6,-1,0
  3888.6    0.04       0  4828.7    0.12       0  4955.2    0.05       0
  4959.2    0.12       0  5109.4    0.05       0  5425.3    0.04       0
Bank Sta=4955.2,4959.2
Exp/Cntr=0.3,0.1

Type RM Length L Ch R = 1,12401,607,607,607
BEGIN DESCRIPTION:
HOG BRANCH 24.0
END DESCRIPTION:
XS GIS Cut Line= 3
      2511274.98     13545074.97      2510825.00     13544475.00
      2509625.00     13544175.00
#Sta/Elev= 30
  4209.3  229.47  4804.8  221.54  4902.0  219.30  4931.1  218.98  4977.3  219.49
  4990.2  218.83  4998.5  217.43  4998.7  216.93  5002.2  216.93  5002.5  217.43
  5018.5  217.87  5031.4  219.50  5043.2  218.96  5143.8  220.47  5247.9  221.94
  5394.8  221.33  5443.7  221.61  5464.3  222.32  5600.9  222.59  5683.4  223.44
  5719.5  224.43  5807.1  224.81  6008.1  229.55  6013.2  230.39  6041.6  230.64
  6082.8  232.96  6124.0  232.92  6144.7  233.68  6173.0  235.91  6196.2  235.90
#Mann=6,-1,0
  4209.3    0.04       0  4804.8    0.12       0  4998.5    0.05       0
  5002.5    0.12       0  5043.2    0.05       0  5143.8    0.04       0
Bank Sta=4998.5,5002.5
Exp/Cntr=0.3,0.1

Type RM Length L Ch R = 1,11794,373,373,373
BEGIN DESCRIPTION:
HOG BRANCH 23.0
END DESCRIPTION:
XS GIS Cut Line= 3
      2511725.02     13544925.03      2510975.00     13544075.00
      2509775.01     13544075.00
#Sta/Elev= 30
  3808.8  231.21  3836.8  230.12  3964.9  228.70  4340.5  221.85  4425.0  221.22
  4461.0  221.77  4475.2  221.00  4502.8  220.98  4510.3  220.21  4531.2  221.04
  4538.8  220.30  4545.4  220.70  4595.7  219.44  4783.2  218.15  4982.4  217.21
  5002.4  216.52  5010.4  214.31  5010.7  213.81  5014.4  214.31  5032.4  217.33
  5065.9  216.23  5102.4  216.93  5132.4  218.50  5172.4  218.94  5542.4  219.63
  5852.4  223.15  5912.4  225.03  5952.4  225.30  6052.4  228.93  6142.4  231.21
#Mann=5,-1,0
  3808.8    0.04       0  4783.2    0.12       0  5010.4    0.05       0
  5014.4    0.12       0  5065.9    0.04       0
Bank Sta=5010.4,5014.4
Exp/Cntr=0.3,0.1

Type RM Length L Ch R = 1,11421,382,382,382
BEGIN DESCRIPTION:
Mapping XS c4e9c02b
END DESCRIPTION:
XS GIS Cut Line= 3
      2512107.42     13544486.90      2511104.84     13543853.23
      2509681.27     13543666.61
#Sta/Elev= 30
  3845.0  228.25  4131.8  227.46  4189.9  226.07  4284.0  225.75  4493.4  221.94
  4535.8  222.04  4602.8  220.05  4913.4  216.21  4964.0  215.65  4985.2  213.87
  4994.6  214.76  5000.5  212.76  5005.2  212.60  5005.4  212.10  5009.2  212.60
  5015.7  214.61  5028.0  215.45  5150.4  215.73  5313.3  216.72  5361.2  218.00
  5414.1  216.52  5454.5  219.23  5484.7  220.00  5545.2  217.20  5897.7  219.85
  5989.0  222.20  6029.4  225.29  6321.8  227.32  6360.4  229.17  6466.8  231.50
#Mann=5,-1,0
  3845.0    0.04       0  4913.4    0.12       0  5005.2    0.05       0
  5009.2    0.12       0  5150.4    0.04       0
Bank Sta=5005.2,5009.2
Exp/Cntr=0.3,0.1

Type RM Length L Ch R = 1,11039,421,421,421
BEGIN DESCRIPTION:
Mapping XS c3e82ba6
END DESCRIPTION:
XS GIS Cut Line= 4
      2512168.20     13544009.48      2511295.81     13543614.52
      2510879.15     13543527.71      2509548.36     13543319.64
#Sta/Elev= 30
  3822.0  230.15  4211.9  225.95  4281.2  223.96  4396.3  222.64  4669.9  215.99
  4817.1  214.08  4904.0  214.57  4913.3  214.17  4931.7  210.49  4931.9  209.99
  4935.7  210.49  4943.8  210.87  4948.9  213.44  4964.3  210.96  4984.8  213.92
  4999.0  211.97  5005.2  213.28  5025.6  212.04  5066.5  214.70  5199.3  213.71
  5351.1  215.77  5432.1  219.14  5511.1  217.52  5786.4  220.57  5877.5  220.03
  6351.9  226.45  6482.4  227.00  6487.5  228.00  6515.1  227.88  6552.2  229.81
#Mann=5,-1,0
  3822.0    0.04       0  4669.9   0.013       0  4817.1    0.04       0
  4931.7    0.04       0  4935.7    0.04       0
Bank Sta=4931.7,4935.7
Exp/Cntr=0.3,0.1

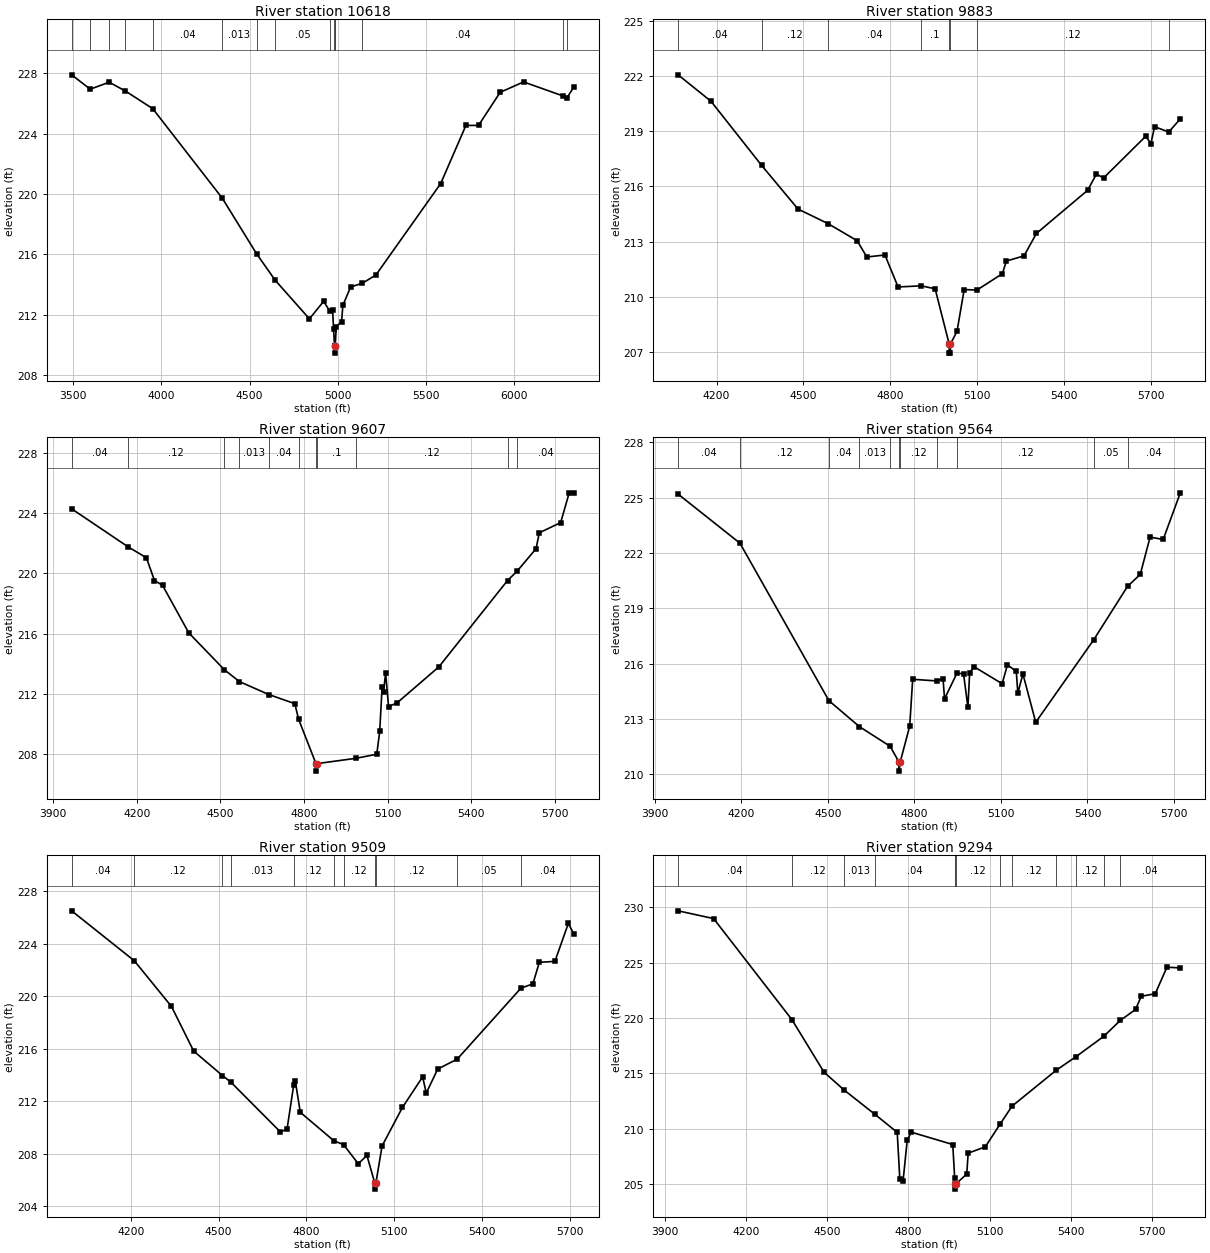
Type RM Length L Ch R = 1,10618,735,735,735
BEGIN DESCRIPTION:
Mapping XS 46ae0bb2
END DESCRIPTION:
XS GIS Cut Line= 3
      2512541.46     13543757.74      2511213.35     13543254.27
      2509815.81     13542963.48
#Sta/Elev= 30
  3491.0  227.89  3596.4  226.94  3703.8  227.40  3795.3  226.82  3950.8  225.65
  4345.2  219.72  4540.2  216.03  4645.7  214.28  4839.4  211.73  4919.9  212.89
  4954.6  212.25  4970.9  212.34  4976.2  211.06  4981.8  209.96  4982.0  209.46
  4985.9  209.96  4991.4  211.21  5022.0  211.55  5028.8  212.62  5073.1  213.84
  5139.7  214.09  5216.1  214.63  5583.8  220.69  5726.8  224.54  5798.3  224.54
  5920.8  226.73  6053.6  227.42  6277.9  226.49  6299.3  226.36  6338.8  227.09
#Mann=15,-1,0
  3491.0    0.04       0  3596.4   0.013       0  3703.8    0.04       0
  3795.3   0.013       0  3950.8    0.04       0  4345.2   0.013       0
  4540.2    0.04       0  4645.7    0.05       0  4954.6    0.12       0
  4976.2    0.05       0  4981.8    0.05       0  4985.9    0.05       0
  5139.7    0.04       0  6277.9    0.05       0  6299.3    0.04       0
Bank Sta=4981.8,4985.9
Exp/Cntr=0.3,0.1

Type RM Length L Ch R = 1,9883,276,276,276
BEGIN DESCRIPTION:
Mapping XS 15cb9db7
END DESCRIPTION:
XS GIS Cut Line= 3
      2512432.92     13543158.77      2511634.35     13542776.84
      2510840.04     13542477.35
#Sta/Elev= 30
  4067.1  222.07  4180.7  220.63  4355.6  217.14  4481.0  214.77  4584.2  213.98
  4685.0  213.05  4718.8  212.16  4781.3  212.27  4826.6  210.53  4906.8  210.59
  4954.6  210.43  5003.0  207.43  5003.3  206.93  5007.1  206.93  5007.5  207.43
  5030.1  208.11  5054.9  210.39  5098.8  210.36  5186.7  211.25  5200.6  211.94
  5261.5  212.22  5304.3  213.44  5481.3  215.79  5511.5  216.67  5536.3  216.46
  5682.0  218.73  5699.7  218.32  5712.2  219.25  5761.1  218.96  5801.2  219.67
#Mann=8,-1,0
  4067.1    0.04       0  4355.6    0.12       0  4584.2    0.04       0
  4906.8     0.1       0  5003.0    0.05       0  5007.5     0.1       0
  5098.8    0.12       0  5761.1    0.04       0
Bank Sta=5003,5007.5
Exp/Cntr=0.3,0.1

Type RM Length L Ch R = 1,9607,43,43,43
BEGIN DESCRIPTION:
Mapping XS b93e8d8e
END DESCRIPTION:
XS GIS Cut Line= 6
      2512522.56     13543087.53      2511774.33     13542766.36
      2511748.29     13542656.99      2511717.04     13542596.22
      2511394.12     13542474.69      2510984.97     13542259.71
#Sta/Elev= 30
  3966.1  224.27  4169.6  221.74  4234.4  221.03  4263.4  219.52  4292.4  219.20
  4386.6  216.05  4514.2  213.61  4568.6  212.82  4674.4  211.96  4767.2  211.36
  4780.9  210.32  4843.1  207.39  4843.4  206.89  4847.6  207.39  4987.0  207.74
  5061.4  208.01  5071.9  209.52  5080.6  212.47  5085.9  212.16  5093.1  213.40
  5103.7  211.16  5135.4  211.43  5284.4  213.80  5530.7  219.52  5565.3  220.14
  5633.2  221.63  5644.7  222.68  5721.6  223.36  5751.8  225.31  5768.8  225.33
#Mann=11,-1,0
  3966.1    0.04       0  4169.6    0.12       0  4514.2    0.04       0
  4568.6   0.013       0  4674.4    0.04       0  4780.9     0.1       0
  4843.1    0.05       0  4847.6     0.1       0  4987.0    0.12       0
  5530.7    0.05       0  5565.3    0.04       0
Bank Sta=4843.1,4847.6
Exp/Cntr=0.3,0.1

Type RM Length L Ch R = 1,9564,55,55,55
BEGIN DESCRIPTION:
Mapping XS 3d969084
END DESCRIPTION:
XS GIS Cut Line= 6
      2512546.92     13543045.88      2511810.79     13542724.69
      2511763.91     13542594.49      2511739.61     13542564.97
      2511531.28     13542467.75      2511062.56     13542217.77
#Sta/Elev= 30
  3980.2  225.19  4194.6  222.53  4503.2  213.99  4609.2  212.58  4715.2  211.52
  4746.0  210.67  4746.3  210.17  4750.5  210.67  4783.4  212.61  4793.7  215.15
  4877.6  215.06  4898.9  215.19  4904.2  214.09  4947.6  215.49  4970.2  215.44
  4985.3  213.63  4991.3  215.51  5006.7  215.83  5104.0  214.91  5122.3  215.93
  5153.0  215.58  5158.4  214.40  5176.0  215.44  5220.5  212.82  5421.9  217.30
  5539.0  220.19  5583.1  220.84  5617.1  222.86  5662.5  222.73  5721.9  225.26
#Mann=11,-1,0
  3980.2    0.04       0  4194.6    0.12       0  4503.2    0.04       0
  4609.2   0.013       0  4715.2    0.12       0  4746.0    0.05       0
  4750.5    0.12       0  4877.6     0.1       0  4947.6    0.12       0
  5421.9    0.05       0  5539.0    0.04       0
Bank Sta=4746,4750.5
Exp/Cntr=0.3,0.1

Type RM Length L Ch R = 1,9509,215,215,215
BEGIN DESCRIPTION:
Mapping XS e5d037f0
END DESCRIPTION:
XS GIS Cut Line= 6
      2512562.57     13542992.07      2511835.09     13542653.51
      2511784.75     13542544.14      2511727.46     13542493.79
      2511572.94     13542424.35      2511078.20     13542194.27
#Sta/Elev= 30
  3998.7  226.49  4212.4  222.69  4339.4  219.21  4415.2  215.81  4513.3  213.95
  4542.4  213.44  4711.0  209.66  4733.9  209.86  4756.5  213.21  4762.3  213.50
  4779.1  211.15  4893.8  208.98  4926.6  208.69  4977.1  207.23  5006.5  207.87
  5032.9  205.80  5033.2  205.30  5037.4  205.80  5058.3  208.59  5127.8  211.52
  5196.8  213.85  5209.0  212.61  5248.1  214.44  5314.8  215.20  5532.2  220.60
  5573.0  220.93  5595.0  222.57  5648.2  222.64  5694.0  225.53  5712.8  224.73
#Mann=11,-1,0
  3998.7    0.04       0  4212.4    0.12       0  4513.3    0.04       0
  4542.4   0.013       0  4756.5    0.12       0  4893.8    0.04       0
  4926.6    0.12       0  5032.9    0.05       0  5037.4    0.12       0
  5314.8    0.05       0  5532.2    0.04       0
Bank Sta=5032.9,5037.4
Exp/Cntr=0.3,0.1

Type RM Length L Ch R = 1,9294,745,745,745
BEGIN DESCRIPTION:
Mapping XS 5bfb5432
END DESCRIPTION:
XS GIS Cut Line= 3
      2512797.52     13542902.69      2511946.85     13542394.90
      2511128.23     13542122.03
#Sta/Elev= 30
  3950.2  229.68  4081.2  228.98  4370.5  219.84  4488.9  215.10  4563.1  213.49
  4675.3  211.32  4758.9  209.67  4768.4  205.50  4780.3  205.23  4795.9  208.98
  4811.5  209.68  4963.9  208.57  4971.0  205.55  4972.2  205.04  4972.5  204.54
  4976.7  205.04  5015.5  205.90  5020.8  207.79  5084.0  208.36  5138.9  210.42
  5182.4  212.03  5345.2  215.27  5418.0  216.49  5520.6  218.33  5582.3  219.78
  5638.6  220.77  5659.6  221.96  5711.2  222.19  5754.5  224.59  5803.8  224.52
#Mann=13,-1,0
  3950.2    0.04       0  4370.5    0.12       0  4563.1   0.013       0
  4675.3    0.04       0  4971.0    0.12       0  4972.2    0.05       0
  4976.7    0.12       0  5138.9    0.05       0  5182.4    0.12       0
  5345.2    0.05       0  5418.0    0.12       0  5520.6    0.05       0
  5582.3    0.04       0
Bank Sta=4972.2,4976.7
Exp/Cntr=0.3,0.1

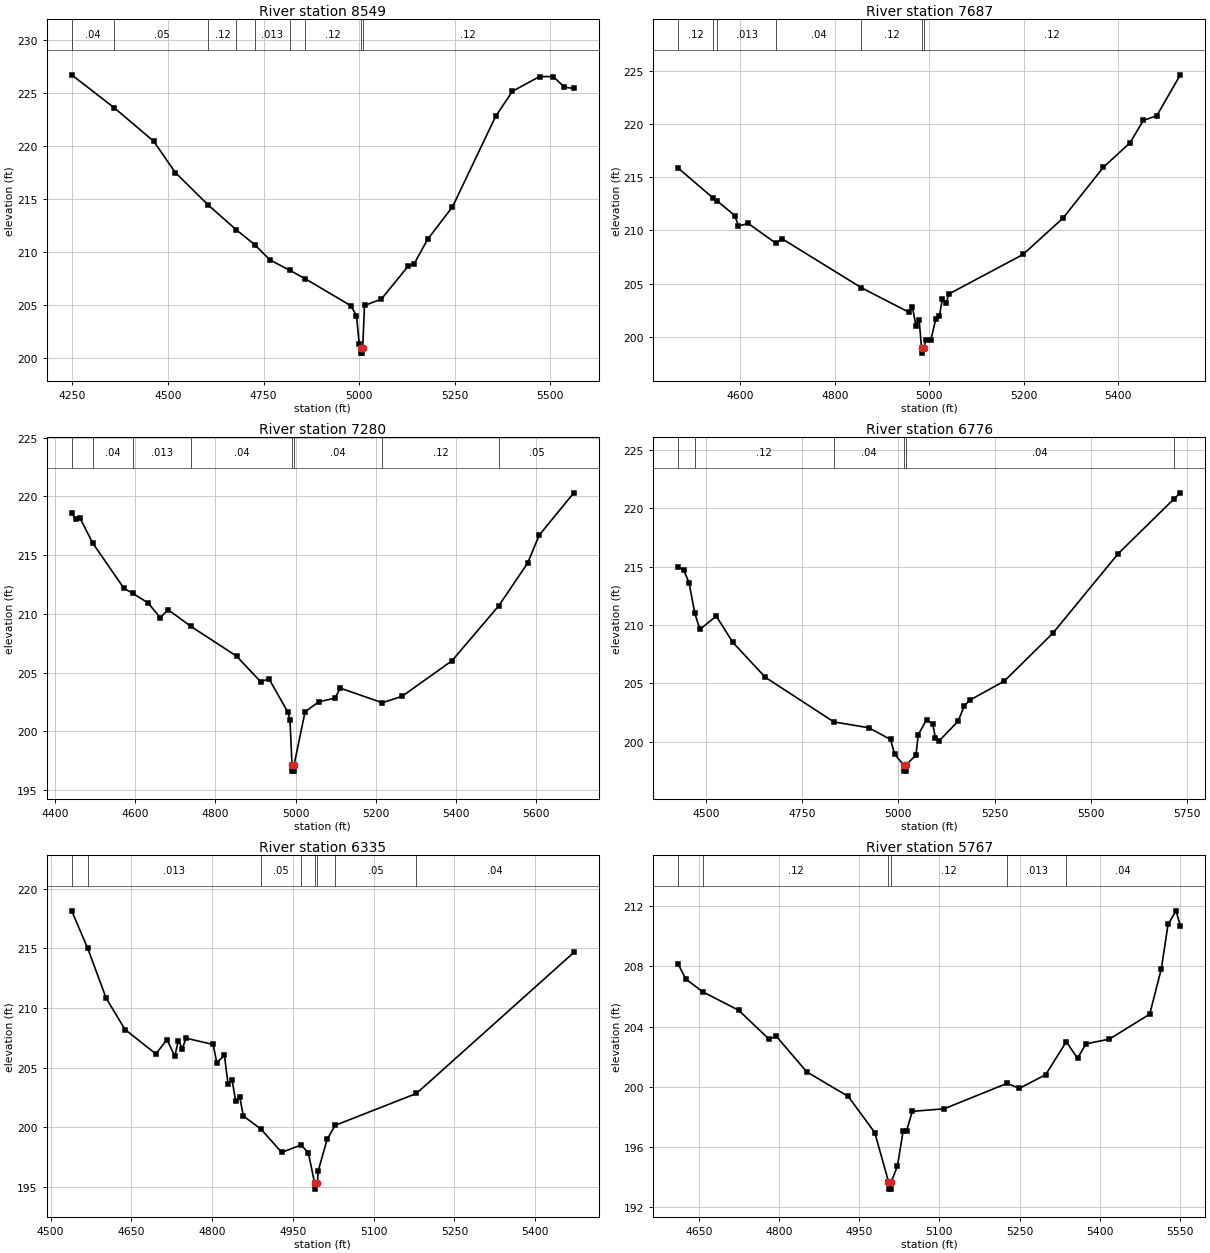
Type RM Length L Ch R = 1,8549,862,862,862
BEGIN DESCRIPTION:
Mapping XS 908142c2
END DESCRIPTION:
XS GIS Cut Line= 3
      2512966.83     13542646.65      2512445.99     13542091.08
      2511999.46     13541765.94
#Sta/Elev= 30
  4247.8  226.76  4359.5  223.64  4462.5  220.49  4519.2  217.53  4605.6  214.46
  4679.1  212.12  4726.5  210.74  4766.8  209.29  4818.7  208.31  4858.9  207.52
  4978.8  204.96  4993.0  204.02  5000.3  201.34  5004.1  201.00  5004.4  200.50
  5008.5  200.50  5008.8  201.00  5009.3  201.00  5014.0  205.00  5058.0  205.59
  5129.1  208.75  5143.8  208.92  5179.3  211.25  5244.2  214.30  5357.0  222.83
  5401.1  225.21  5472.2  226.60  5507.7  226.59  5537.1  225.59  5561.7  225.48
#Mann=9,-1,0
  4247.8    0.04       0  4359.5    0.05       0  4605.6    0.12       0
  4679.1    0.04       0  4726.5   0.013       0  4818.7    0.04       0
  4858.9    0.12       0  5004.1    0.05       0  5008.8    0.12       0
Bank Sta=5004.1,5008.8
Exp/Cntr=0.3,0.1

Type RM Length L Ch R = 1,7687,407,407,407
BEGIN DESCRIPTION:
HOG BRANCH 15.0
END DESCRIPTION:
XS GIS Cut Line= 3
      2513324.99     13542074.99      2512975.00     13541675.00
      2512575.00     13541325.00
#Sta/Elev= 30
  4468.5  215.87  4541.9  213.07  4550.8  212.79  4588.6  211.39  4596.1  210.42
  4617.0  210.65  4676.2  208.77  4688.2  209.22  4856.3  204.61  4957.8  202.28
  4964.4  202.81  4972.0  201.00  4978.6  201.59  4983.8  198.95  4984.2  198.45
  4988.7  198.95  4992.9  199.65  5003.3  199.66  5013.8  201.64  5021.4  201.90
  5028.0  203.59  5035.6  203.17  5042.2  204.03  5198.8  207.74  5283.3  211.16
  5368.7  215.94  5425.2  218.25  5453.2  220.35  5481.7  220.79  5531.5  224.64
#Mann=7,-1,0
  4468.5    0.12       0  4541.9    0.04       0  4550.8   0.013       0
  4676.2    0.04       0  4856.3    0.12       0  4983.8    0.05       0
  4988.7    0.12       0
Bank Sta=4983.8,4988.7
Exp/Cntr=0.3,0.1

Type RM Length L Ch R = 1,7280,504,504,504
BEGIN DESCRIPTION:
HOG BRANCH 14.0
END DESCRIPTION:
XS GIS Cut Line= 3
      2513375.00     13542075.01      2513325.00     13541475.00
      2512724.99     13541224.99
#Sta/Elev= 30
  4441.8  218.59  4451.8  218.04  4461.9  218.20  4494.6  216.01  4572.3  212.17
  4593.7  211.76  4632.5  210.93  4662.6  209.68  4682.6  210.35  4739.0  208.94
  4853.2  206.40  4913.4  204.21  4933.5  204.49  4981.2  201.62  4986.2  200.96
  4991.3  197.12  4991.6  196.62  4995.8  196.62  4996.2  197.12  5023.8  201.67
  5058.5  202.53  5098.1  202.82  5111.6  203.68  5216.3  202.44  5265.4  202.98
  5390.0  206.01  5506.8  210.69  5578.5  214.31  5607.8  216.71  5693.9  220.30
#Mann=8,-1,0
  4441.8    0.05       0  4494.6    0.04       0  4593.7   0.013       0
  4739.0    0.04       0  4991.3    0.04       0  4996.2    0.04       0
  5216.3    0.12       0  5506.8    0.05       0
Bank Sta=4991.3,4996.2
Exp/Cntr=0.3,0.1

Type RM Length L Ch R = 1,6776,441,441,441
BEGIN DESCRIPTION:
HOG BRANCH 13.0
END DESCRIPTION:
XS GIS Cut Line= 3
      2513874.98     13541474.98      2513475.00     13541075.00
      2513125.00     13540425.00
#Sta/Elev= 30
  4428.1  215.00  4442.2  214.75  4456.4  213.64  4471.4  211.01  4484.6  209.62
  4527.1  210.77  4569.5  208.54  4654.4  205.52  4832.5  201.69  4923.1  201.19
  4979.6  200.19  4990.2  198.93  5013.9  197.97  5014.3  197.47  5018.6  197.47
  5019.0  197.97  5045.7  198.85  5051.4  200.59  5073.3  201.88  5089.5  201.48
  5096.0  200.34  5105.7  200.06  5155.2  201.76  5171.4  203.09  5186.8  203.58
  5275.3  205.20  5401.0  209.30  5570.6  216.12  5716.6  220.85  5732.0  221.34
#Mann=6,-1,0
  4428.1    0.05       0  4471.4    0.12       0  4832.5    0.04       0
  5013.9    0.04       0  5019.0    0.04       0  5716.6   0.013       0
Bank Sta=5013.9,5019
Exp/Cntr=0.3,0.1

Type RM Length L Ch R = 1,6335,568,568,568
BEGIN DESCRIPTION:
HOG BRANCH 12.0
END DESCRIPTION:
XS GIS Cut Line= 3
      2514024.98     13541074.98      2513725.00     13540725.00
      2513325.04     13540475.02
#Sta/Elev= 30
  4539.1  218.15  4568.8  215.02  4603.3  210.81  4638.4  208.19  4695.5  206.15
  4716.3  207.35  4730.6  205.94  4737.2  207.26  4744.9  206.60  4751.4  207.47
  4801.9  206.94  4808.5  205.42  4822.8  206.03  4829.4  203.66  4837.1  203.94
  4843.6  202.22  4851.3  202.54  4857.9  200.94  4890.3  199.86  4929.3  197.89
  4965.0  198.51  4978.6  197.87  4990.3  195.31  4990.7  194.81  4995.5  195.31
  4996.8  196.31  5013.6  198.99  5028.5  200.16  5179.3  202.83  5471.7  214.66
#Mann=8,-1,0
  4539.1    0.05       0  4568.8   0.013       0  4890.3    0.05       0
  4965.0    0.04       0  4990.3    0.04       0  4995.5    0.04       0
  5028.5    0.05       0  5179.3    0.04       0
Bank Sta=4990.3,4995.5
Exp/Cntr=0.3,0.1

Type RM Length L Ch R = 1,5767,444,444,444
BEGIN DESCRIPTION:
HOG BRANCH 11.0
END DESCRIPTION:
XS GIS Cut Line= 3
      2514375.02     13540725.02      2514075.00     13540425.00
      2513624.98     13540174.99
#Sta/Elev= 30
  4611.4  208.17  4625.6  207.17  4657.2  206.32  4724.6  205.09  4781.1  203.18
  4795.3  203.35  4851.8  201.00  4929.6  199.36  4979.1  196.96  5004.8  193.70
  5005.2  193.20  5009.6  193.20  5010.1  193.70  5021.5  194.72  5032.2  197.08
  5038.6  197.08  5049.4  198.37  5108.9  198.54  5226.5  200.23  5249.6  199.90
  5298.8  200.81  5337.3  203.00  5358.3  201.90  5374.3  202.86  5417.8  203.17
  5493.3  204.83  5515.0  207.85  5527.6  210.80  5542.5  211.70  5550.5  210.71
#Mann=6,-1,0
  4611.4    0.05       0  4657.2    0.12       0  5004.8    0.05       0
  5010.1    0.12       0  5226.5   0.013       0  5337.3    0.04       0
Bank Sta=5004.8,5010.1
Exp/Cntr=0.3,0.1

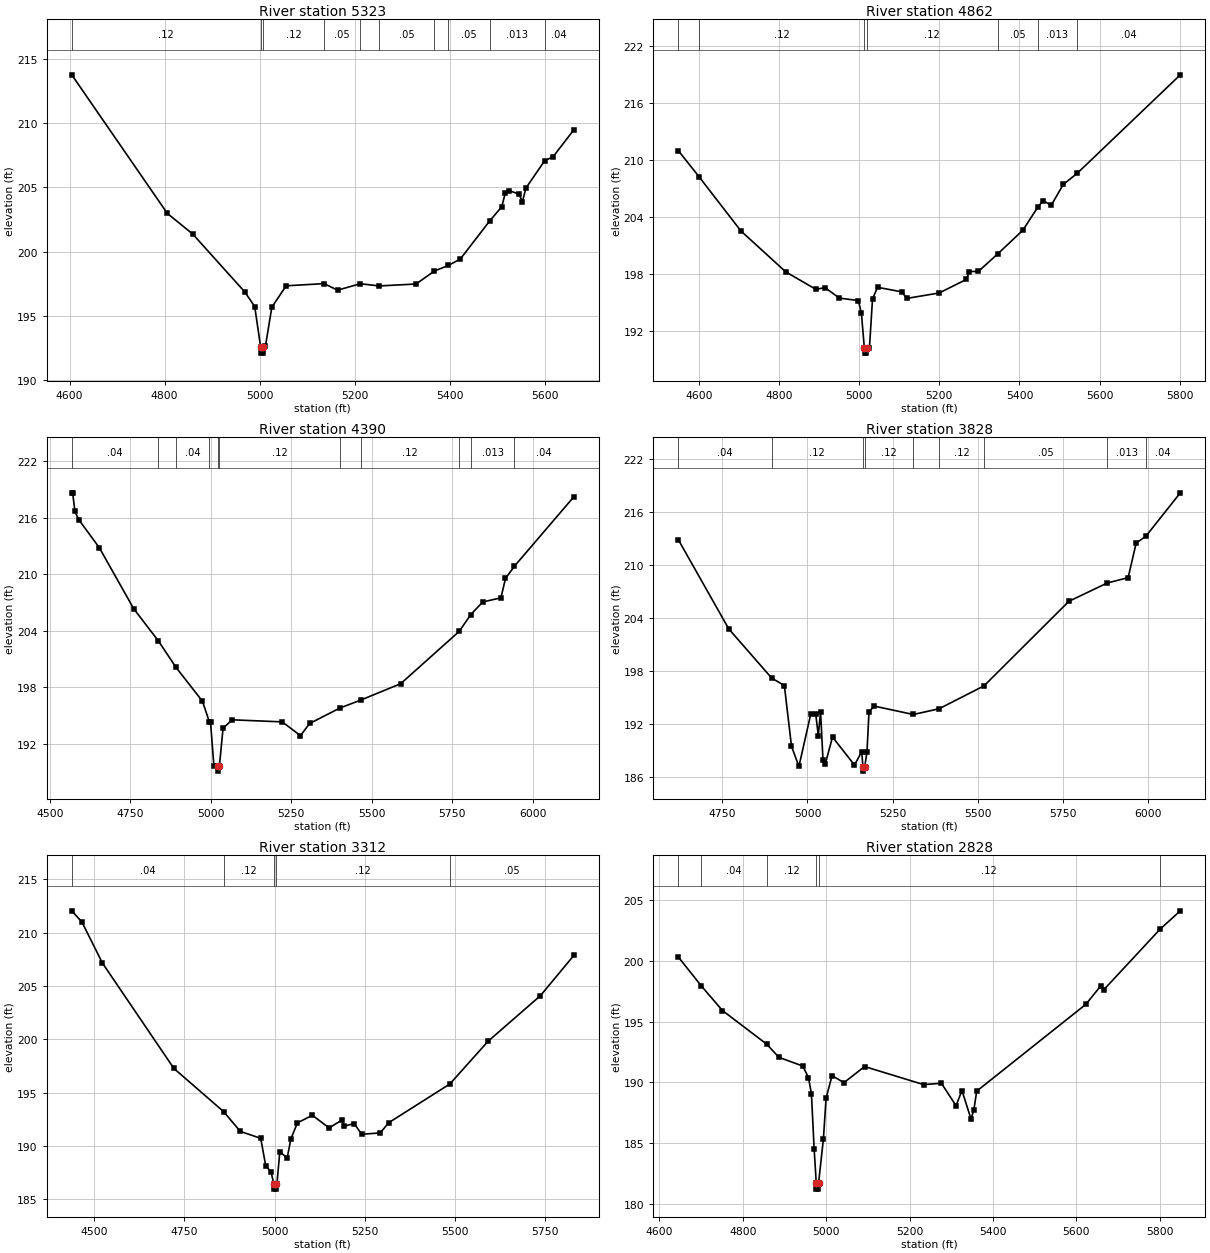
Type RM Length L Ch R = 1,5323,461,461,461
BEGIN DESCRIPTION:
HOG BRANCH 10.0
END DESCRIPTION:
XS GIS Cut Line= 3
      2514674.98     13540274.99      2514375.00     13540125.00
      2513775.00     13539725.00
#Sta/Elev= 30
  4604.7  213.74  4805.9  202.97  4859.0  201.38  4968.6  196.88  4989.7  195.74
  5002.0  192.62  5002.4  192.12  5006.9  192.12  5007.3  192.62  5012.2  192.65
  5025.7  195.69  5055.8  197.35  5135.9  197.52  5163.9  197.01  5211.6  197.51
  5251.9  197.34  5329.2  197.49  5367.9  198.50  5397.1  198.93  5422.3  199.43
  5483.9  202.38  5509.5  203.49  5517.0  204.57  5524.5  204.75  5545.5  204.48
  5553.0  203.89  5560.5  204.95  5599.9  207.07  5617.6  207.38  5661.2  209.47
#Mann=10,-1,0
  4604.7    0.12       0  5002.0    0.05       0  5007.3    0.12       0
  5135.9    0.05       0  5211.6    0.12       0  5251.9    0.05       0
  5367.9    0.12       0  5397.1    0.05       0  5483.9   0.013       0
  5599.9    0.04       0
Bank Sta=5002,5007.3
Exp/Cntr=0.3,0.1

Type RM Length L Ch R = 1,4862,472,472,472
BEGIN DESCRIPTION:
HOG BRANCH 9.0
END DESCRIPTION:
XS GIS Cut Line= 3
      2514774.99     13539874.99      2514375.00     13539675.00
      2513575.02     13539575.00
#Sta/Elev= 30
  4548.2  211.01  4599.9  208.26  4704.7  202.53  4816.5  198.22  4892.0  196.37
  4914.3  196.56  4950.7  195.45  4997.9  195.19  5005.5  193.83  5012.9  190.15
  5013.3  189.65  5017.8  189.65  5018.2  190.15  5025.6  190.23  5033.2  195.36
  5045.8  196.59  5106.3  196.11  5118.9  195.42  5199.5  195.99  5267.5  197.42
  5275.1  198.25  5297.7  198.27  5346.8  200.15  5408.6  202.61  5445.6  205.02
  5459.0  205.74  5479.1  205.22  5509.4  207.43  5544.3  208.61  5801.6  218.99
#Mann=7,-1,0
  4548.2    0.05       0  4599.9    0.12       0  5012.9    0.05       0
  5018.2    0.12       0  5346.8    0.05       0  5445.6   0.013       0
  5544.3    0.04       0
Bank Sta=5012.9,5018.2
Exp/Cntr=0.3,0.1

Type RM Length L Ch R = 1,4390,562,562,562
BEGIN DESCRIPTION:
HOG BRANCH 8.0
END DESCRIPTION:
XS GIS Cut Line= 3
      2515025.00     13539475.00      2514625.00     13539325.00
      2513824.98     13538524.98
#Sta/Elev= 30
  4568.3  218.62  4571.0  218.62  4578.1  216.65  4589.7  215.79  4653.7  212.81
  4760.5  206.34  4837.4  202.91  4891.7  200.13  4974.1  196.52  4995.6  194.32
  4999.0  194.32  5009.6  189.64  5021.1  189.62  5021.5  189.12  5026.5  189.62
  5037.9  193.66  5066.2  194.56  5221.8  194.34  5278.3  192.88  5306.6  194.17
  5401.4  195.82  5465.4  196.65  5589.5  198.39  5771.2  203.94  5807.1  205.72
  5844.0  207.05  5900.6  207.49  5914.7  209.54  5942.4  210.84  6126.9  218.20
#Mann=11,-1,0
  4568.3    0.04       0  4837.4    0.12       0  4891.7    0.04       0
  4995.6    0.12       0  5021.1    0.05       0  5026.5    0.12       0
  5401.4   0.013       0  5465.4    0.12       0  5771.2    0.05       0
  5807.1   0.013       0  5942.4    0.04       0
Bank Sta=5021.1,5026.5
Exp/Cntr=0.3,0.1

Type RM Length L Ch R = 1,3828,516,516,516
BEGIN DESCRIPTION:
HOG BRANCH 7.0
END DESCRIPTION:
XS GIS Cut Line= 3
      2515074.99     13539274.99      2514675.00     13538925.00
      2513874.99     13538424.99
#Sta/Elev= 30
  4620.3  212.87  4768.8  202.77  4894.7  197.22  4932.1  196.37  4953.0  189.51
  4974.8  187.23  5009.9  193.20  5024.1  193.19  5031.7  190.72  5038.4  193.40
  5045.5  187.99  5052.6  187.56  5073.5  190.55  5138.0  187.39  5159.5  188.91
  5162.7  187.20  5163.1  186.70  5168.1  187.20  5174.8  188.89  5180.7  193.41
  5196.0  194.05  5310.7  193.10  5386.2  193.74  5518.7  196.34  5767.9  205.89
  5880.5  207.96  5941.9  208.56  5965.5  212.47  5994.4  213.26  6095.2  218.15
#Mann=9,-1,0
  4620.3    0.04       0  4894.7    0.12       0  5162.7    0.05       0
  5168.1    0.12       0  5310.7    0.05       0  5386.2    0.12       0
  5518.7    0.05       0  5880.5   0.013       0  5994.4    0.04       0
Bank Sta=5162.7,5168.1
Exp/Cntr=0.3,0.1

Type RM Length L Ch R = 1,3312,484,484,484
BEGIN DESCRIPTION:
HOG BRANCH 6.0
END DESCRIPTION:
XS GIS Cut Line= 3
      2515324.98     13538974.98      2514925.00     13538575.00
      2514124.98     13538375.00
#Sta/Elev= 30
  4438.6  212.04  4466.9  210.98  4523.4  207.15  4721.4  197.27  4859.5  193.21
  4905.3  191.37  4961.8  190.72  4976.0  188.10  4990.1  187.61  4998.0  186.46
  4998.4  185.96  5003.0  185.96  5003.5  186.46  5006.8  186.46  5014.6  189.44
  5035.2  188.90  5045.5  190.69  5063.5  192.17  5104.8  192.88  5151.1  191.70
  5187.2  192.44  5192.4  191.86  5220.7  192.10  5241.3  191.10  5292.9  191.23
  5316.1  192.18  5485.4  195.81  5591.8  199.83  5736.1  204.08  5828.9  207.86
#Mann=5,-1,0
  4438.6    0.04       0  4859.5    0.12       0  4998.0    0.05       0
  5003.5    0.12       0  5485.4    0.05       0
Bank Sta=4998,5003.5
Exp/Cntr=0.3,0.1

Type RM Length L Ch R = 1,2828,392,392,392
BEGIN DESCRIPTION:
HOG BRANCH 5.0
END DESCRIPTION:
XS GIS Cut Line= 3
      2515474.97     13538574.97      2515225.00     13538275.00
      2514675.01     13537675.01
#Sta/Elev= 30
  4645.2  200.34  4700.8  197.94  4751.2  195.92  4857.6  193.14  4886.6  192.06
  4943.9  191.34  4957.6  190.39  4964.7  189.06  4971.2  184.51  4976.3  181.69
  4976.7  181.19  4981.3  181.19  4981.8  181.69  4993.4  185.31  4999.9  188.70
  5014.2  190.55  5042.8  189.97  5092.1  191.30  5233.9  189.81  5276.5  189.92
  5311.6  188.07  5325.8  189.32  5347.4  186.99  5354.2  187.69  5361.2  189.27
  5623.0  196.43  5658.8  197.95  5665.5  197.61  5801.2  202.63  5849.6  204.14
#Mann=6,-1,0
  4645.2    0.05       0  4700.8    0.04       0  4857.6    0.12       0
  4976.3    0.05       0  4981.8    0.12       0  5801.2    0.05       0
Bank Sta=4976.3,4981.8
Exp/Cntr=0.3,0.1