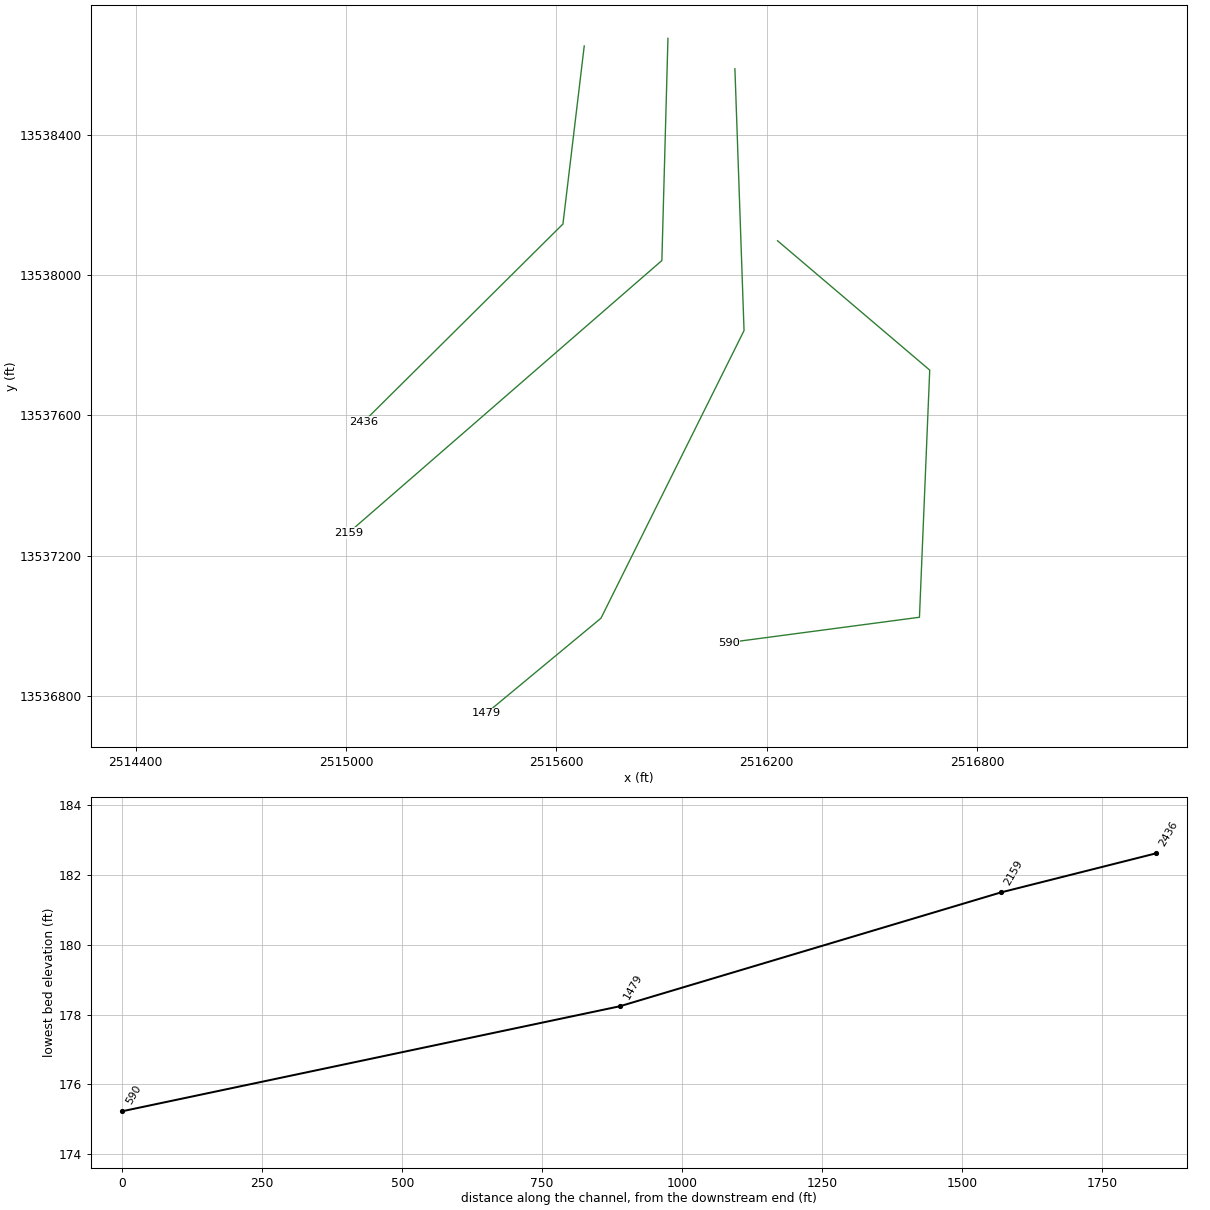
HEC-RAS study HOG BRANCH.prj: HOG BRANCH Base Level Engineering

--- HOG BRANCH.g01 (geometry) --- (continued)

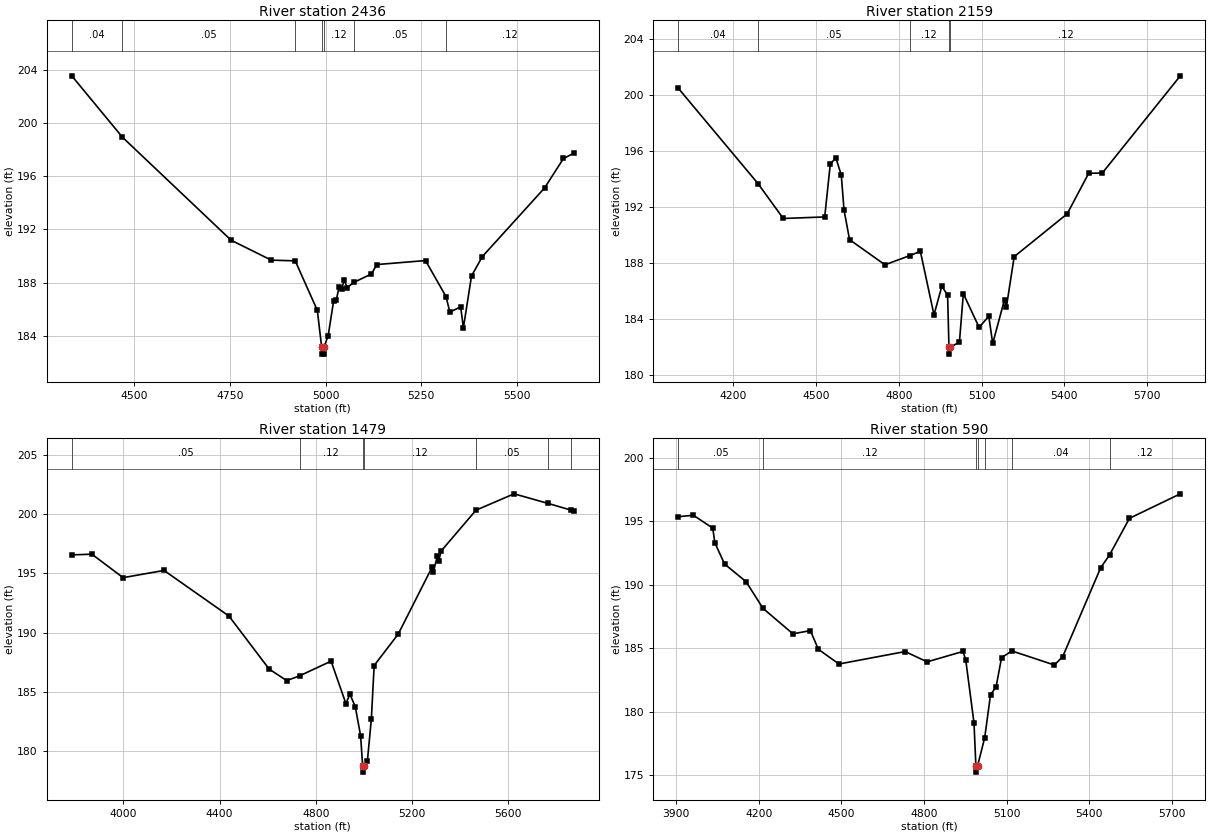
Type RM Length L Ch R = 1,2436,277,277,277
BEGIN DESCRIPTION:
Mapping XS f6eca9da
END DESCRIPTION:
XS GIS Cut Line= 3
      2515679.49     13538653.53      2515618.73     13538145.77
      2515050.16     13537581.54
#Sta/Elev= 30
  4336.7  203.56  4469.2  198.94  4753.2  191.19  4858.3  189.69  4920.8  189.64
  4978.6  185.91  4990.0  183.12  4990.4  182.62  4995.0  182.62  4995.5  183.12
  5006.9  184.00  5021.0  186.59  5028.0  186.66  5035.1  187.64  5042.2  187.54
  5049.3  188.21  5056.3  187.62  5074.0  188.02  5120.0  188.65  5134.1  189.36
  5261.4  189.66  5315.1  186.94  5325.0  185.78  5353.3  186.18  5360.4  184.60
  5381.6  188.50  5409.9  189.96  5572.5  195.12  5622.0  197.34  5649.1  197.74
#Mann=7,-1,0
  4336.7    0.04       0  4469.2    0.05       0  4920.8    0.12       0
  4990.0    0.05       0  4995.5    0.12       0  5074.0    0.05       0
  5315.1    0.12       0
Bank Sta=4990,4995.5
Exp/Cntr=0.3,0.1

Type RM Length L Ch R = 1,2159,680,680,680
BEGIN DESCRIPTION:
Mapping XS 6f0e91eb
END DESCRIPTION:
XS GIS Cut Line= 3
      2515918.21     13538675.29      2515900.85     13538041.60
      2515006.76     13537264.70
#Sta/Elev= 30
  4001.3  200.46  4290.1  193.66  4381.7  191.17  4531.8  191.28  4551.8  195.02
  4571.8  195.51  4591.8  194.27  4601.8  191.77  4621.8  189.66  4750.0  187.87
  4839.7  188.52  4878.2  188.83  4927.6  184.30  4956.1  186.35  4976.9  185.69
  4981.8  182.00  4982.3  181.50  4987.3  182.00  5019.7  182.36  5033.9  185.81
  5090.9  183.41  5126.0  184.20  5140.3  182.26  5183.0  185.39  5189.6  184.83
  5218.1  188.45  5410.0  191.50  5487.8  194.39  5537.2  194.41  5819.7  201.34
#Mann=5,-1,0
  4001.3    0.04       0  4290.1    0.05       0  4839.7    0.12       0
  4981.8    0.05       0  4987.3    0.12       0
Bank Sta=4981.8,4987.3
Exp/Cntr=0.3,0.1

Type RM Length L Ch R = 1,1479,889,889,889
BEGIN DESCRIPTION:
Mapping XS 6ff70440
END DESCRIPTION:
XS GIS Cut Line= 4
      2516109.18     13538588.50      2516135.22     13537841.95
      2515727.24     13537021.64      2515399.79     13536750.20
#Sta/Elev= 30
  3784.9  196.56  3868.5  196.62  3998.5  194.64  4168.6  195.25  4438.8  191.40
  4606.0  186.93  4678.8  185.96  4732.5  186.36  4863.6  187.60  4925.2  184.02
  4941.7  184.81  4964.1  183.77  4986.4  181.31  4994.9  178.74  4995.4  178.24
  5001.0  178.74  5014.8  179.22  5031.1  182.72  5042.7  187.23  5142.8  189.88
  5283.5  195.51  5289.1  195.14  5305.9  196.48  5311.5  196.06  5321.5  196.89
  5466.3  200.33  5624.7  201.71  5766.4  200.90  5862.6  200.33  5873.4  200.28
#Mann=7,-1,0
  3784.9    0.05       0  4732.5    0.12       0  4994.9    0.05       0
  5001.0    0.12       0  5466.3    0.05       0  5766.4    0.12       0
  5862.6    0.05       0
Bank Sta=4994.9,5001
Exp/Cntr=0.3,0.1

Type RM Length L Ch R = 1,590,0,0,0
BEGIN DESCRIPTION:
HOG BRANCH 1.0
END DESCRIPTION:
XS GIS Cut Line= 4
      2516230.74     13538097.99      2516664.74     13537729.10
      2516635.44     13537024.32      2516091.79     13536952.19
#Sta/Elev= 30
  3907.7  195.36  3962.8  195.47  4033.0  194.46  4040.8  193.30  4075.9  191.63
  4153.9  190.24  4215.8  188.13  4324.1  186.13  4387.8  186.38  4416.4  184.91
  4491.4  183.75  4731.6  184.73  4811.7  183.92  4941.8  184.74  4951.8  184.08
  4981.8  179.11  4988.7  175.73  4989.2  175.23  4994.9  175.73  5020.7  177.94
  5041.9  181.34  5061.9  181.93  5081.9  184.25  5119.4  184.78  5273.9  183.67
  5304.2  184.34  5442.0  191.34  5474.0  192.34  5546.3  195.23  5731.1  197.16
#Mann=7,-1,0
  3907.7    0.05       0  4215.8    0.12       0  4988.7    0.05       0
  4994.9    0.12       0  5020.7    0.05       0  5119.4    0.04       0
  5474.0    0.12       0
Bank Sta=4988.7,4994.9
Exp/Cntr=0.3,0.1

Chan Stop Cuts=-1