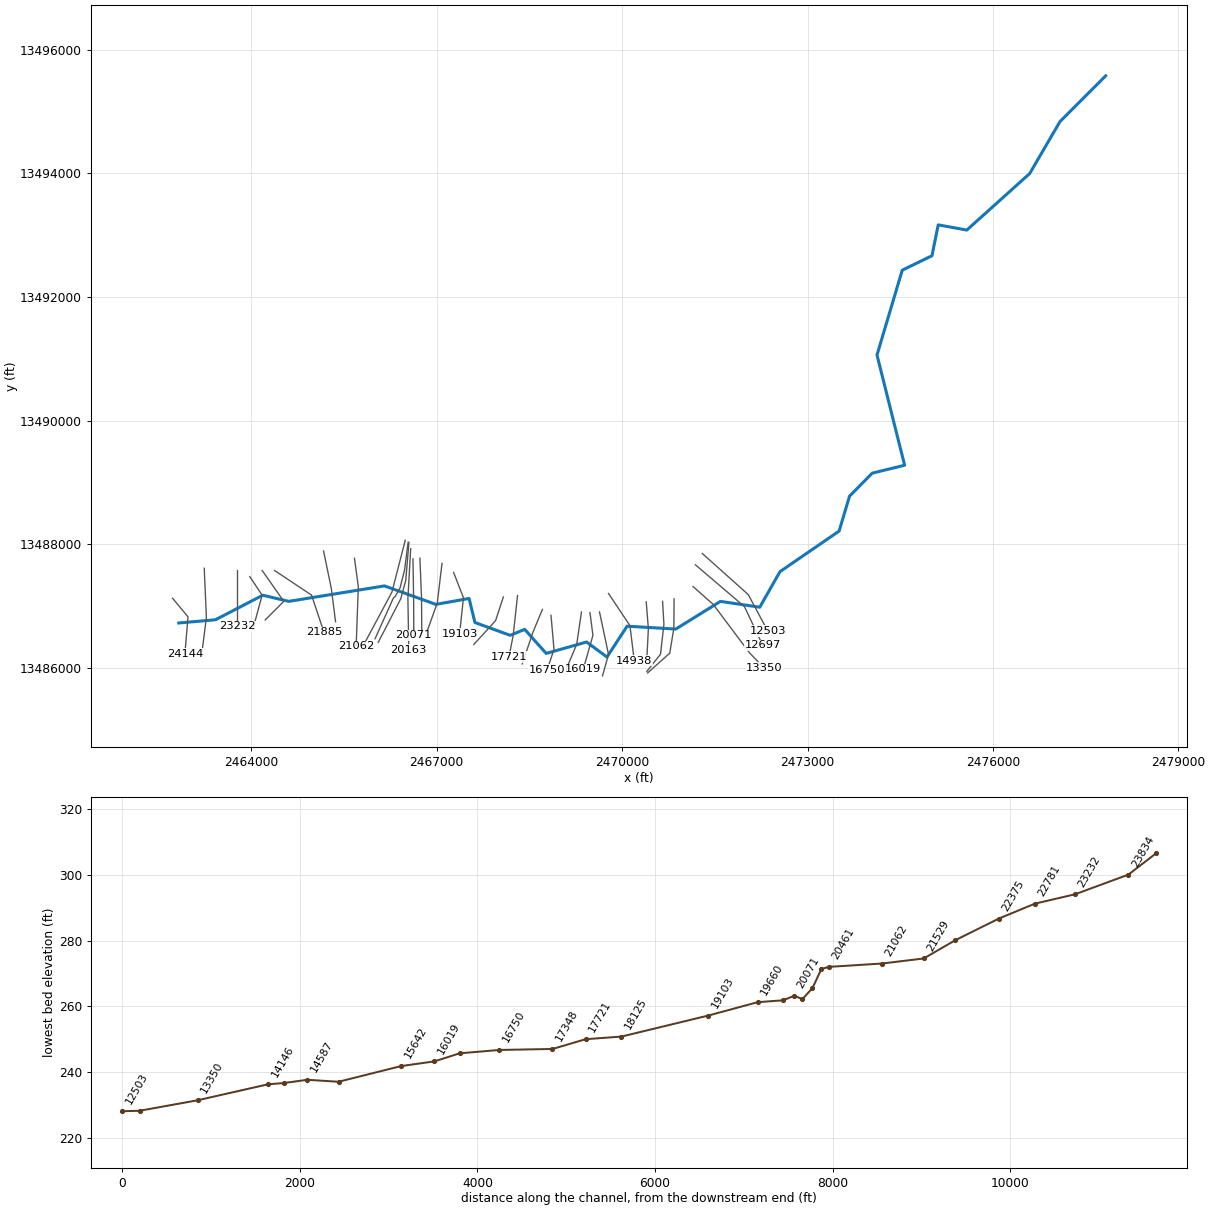
--- HOG CREEK.prj (project) ---

Proj Title=HOG CREEK Base Level Engineering
Current Plan=p01
Default Exp/Contr=0.3,0.1
English Units
Geom File=g01
Flow File=f01
Plan File=p01
Y Axis Title=Elevation
X Axis Title(PF)=Main Channel Distance
X Axis Title(XS)=Station
BEGIN DESCRIPTION:
HOG CREEK
END DESCRIPTION:
DSS Export Rating Curves= 0
DSS Export Rating Curve Sorted= 0
DSS Export Volume Flow Curves= 0
DXF OffsetX= 0
DXF OffsetY= 0
DXF ScaleX= 1
DXF ScaleY= 10

--- HOG CREEK.p01 (plan) ---

Plan Title=Multiple Run
Short Identifier=Multiple
Geom File=g01
Flow File=f01
Subcritical Flow
K Sum by GR= 0
Std Step Tol= 0.01
Critical Tol= 0.01
Num of Std Step Trials= 20
Max Error Tol= 0.3
Flow Tol Ratio= 0.001
Split Flow NTrial= 30
Split Flow Tol= 0.02
Split Flow Ratio= 0.02
Log Output Level= 0
Friction Slope Method= 1
Unsteady Friction Slope Method= 2
Unsteady Bridges Friction Slope Method= 1
Parabolic Critical Depth
Global Vel Dist=  1 , 1 , 1
Global Log Level= 0
CheckData=True
Encroach Param= -1, 0, 0, 0
BEGIN DESCRIPTION:
Multiple Run
END DESCRIPTION:

--- HOG CREEK.f01 (steady flow) ---

Flow Title=Multiple
Program Version=4.10
Number of Profiles= 7
Profile Names=10-year,25-year,50-year,1pct_min,100-year,1pct_plu,500-year
River Rch & RM=HOG CREEK,Reach-1         ,24144
     502     799    1065     688    1372    2738    2253
River Rch & RM=HOG CREEK,Reach-1         ,20461
     696    1132    1528     999    1994    3978    3358
River Rch & RM=HOG CREEK,Reach-1         ,17721
     902    1484    2018    1326    2647    5281    4510
River Rch & RM=HOG CREEK,Reach-1         ,13350
    1732    2939    4082    2734    5454   10883    9652
River Rch & RM=HOG CREEK,Reach-1         ,7380
    2042    3489    4867    3273    6531   13031   11654
River Rch & RM=HOG CREEK,Reach-1         ,5428
    2118    3618    5045    3391    6765   13498   12054
Boundary for River Rch & Prof#=HOG CREEK,Reach-1         , 1
Up Type= 0
Dn Type= 3
Dn Slope=0.005
Boundary for River Rch & Prof#=HOG CREEK,Reach-1         , 2
Up Type= 0
Dn Type= 3
Dn Slope=0.005
Boundary for River Rch & Prof#=HOG CREEK,Reach-1         , 3
Up Type= 0
Dn Type= 3
Dn Slope=0.005
Boundary for River Rch & Prof#=HOG CREEK,Reach-1         , 4
Up Type= 0
Dn Type= 3
Dn Slope=0.005
Boundary for River Rch & Prof#=HOG CREEK,Reach-1         , 5
Up Type= 0
Dn Type= 3
Dn Slope=0.005
Boundary for River Rch & Prof#=HOG CREEK,Reach-1         , 6
Up Type= 0
Dn Type= 3
Dn Slope=0.005
Boundary for River Rch & Prof#=HOG CREEK,Reach-1         , 7
Up Type= 0
Dn Type= 3
Dn Slope=0.005
DSS Import GetInterval= 0
DSS Import GetPeak= 0
DSS Import FillOption= 0

--- HOG CREEK.g01 (geometry) ---

Geom Title=Existing Conditions
Program Version=4.10

River Reach=HOG CREEK       ,Reach-1
Reach XY= 30
        2462825.       13486725.      2463419.14     13486777.06
      2464185.63      13487174.4      2464604.95     13487074.79
      2466155.02     13487325.04      2466985.44     13487026.05
      2467523.53     13487121.46      2467618.43     13486732.69
      2468190.09     13486525.18      2468423.27     13486621.69
      2468771.57     13486232.79      2469424.94      13486417.7
      2469754.87     13486174.59      2470080.49     13486673.04
      2470869.11     13486626.97      2471590.23     13487074.52
      2472227.44     13486980.39       2472554.8     13487555.39
       2473511.6      13488211.7      2473680.83      13488777.3
      2474048.13     13489148.83      2474571.47     13489276.45
      2474124.57     13491059.82      2474533.13     13492431.08
      2475014.53     13492665.17        2475115.     13493164.37
      2475577.71     13493080.28      2476595.64     13493994.43
      2477085.75     13494834.71        2477825.       13495575.

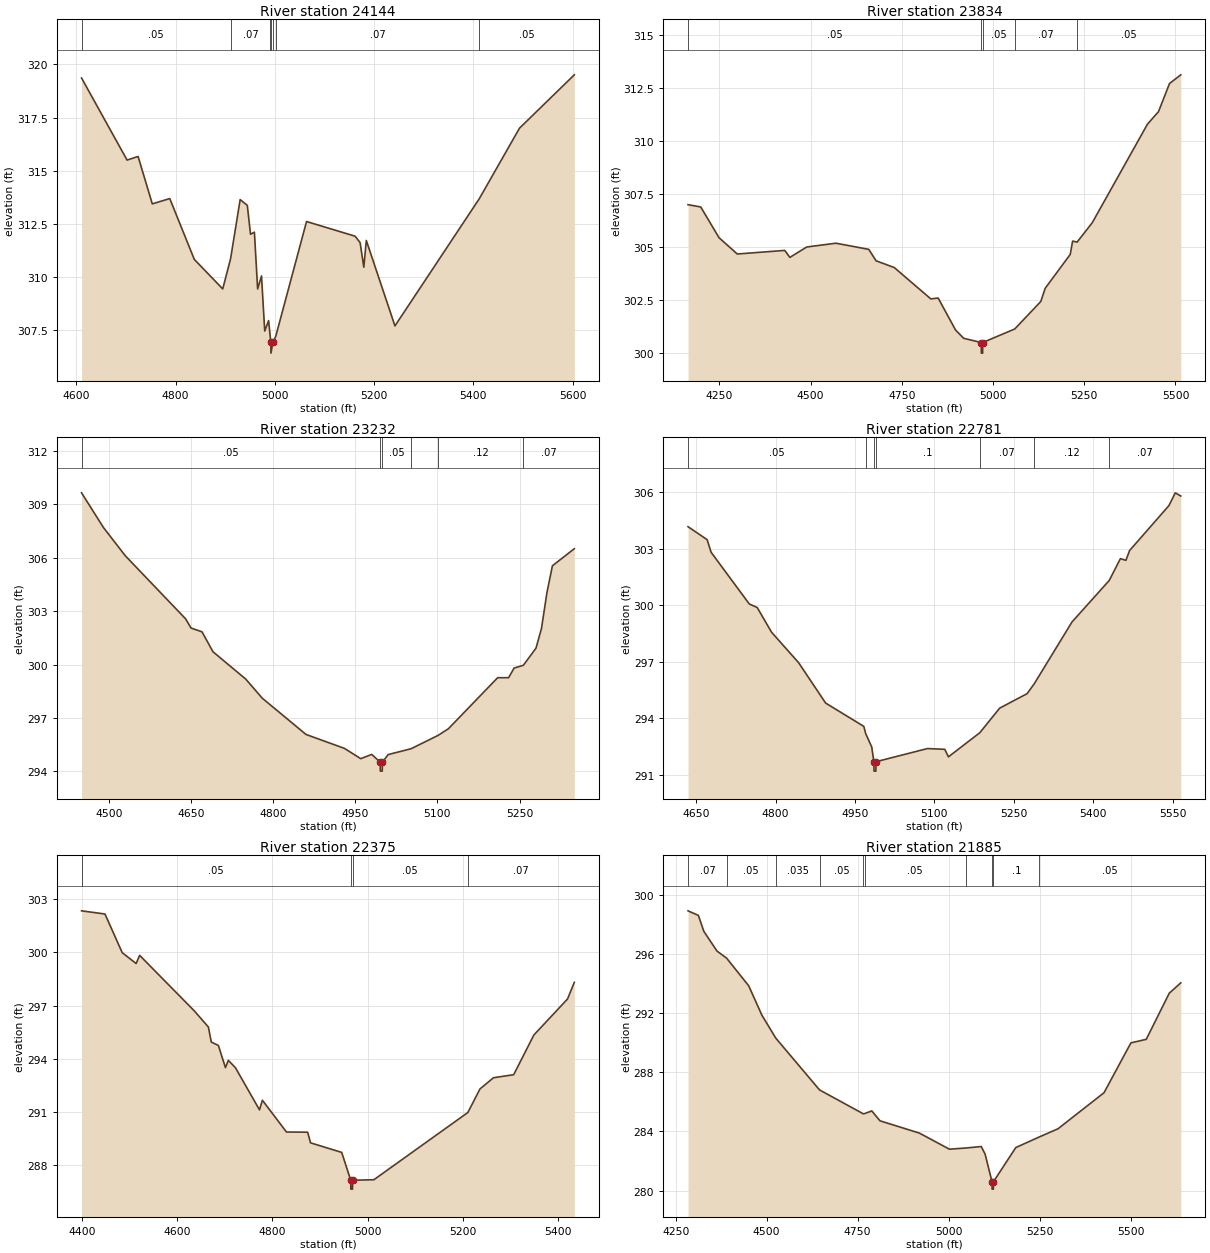
Type RM Length L Ch R = 1 ,24144   ,310,310,310
BEGIN DESCRIPTION:
HOG CREEK 49.0
END DESCRIPTION:
XS GIS Cut Line= 3
      2462725.02     13487124.97        2462975.       13486825.
        2462925.     13486224.96
#Sta/Elev= 30
  4610.6  319.36  4702.3   315.5  4724.5  315.67  4753.1  313.44  4788.3  313.69
  4837.7  310.83    4895  309.44  4910.8  310.86  4930.1  313.64  4944.5  313.37
    4951  312.01  4958.8  312.11  4965.3  309.44  4973.1  310.05  4979.6  307.46
  4987.4  307.95  4991.1   307.1  4991.9  306.92  4992.2  306.42  4995.9  306.92
  5001.8  307.21  5063.8  312.61  5161.6  311.92  5171.7  311.62  5179.2  310.46
  5184.2  311.72  5241.9   307.7  5411.7  313.68  5492.8     317  5603.2  319.51
#Mann= 7 ,-1 , 0
  4610.6     .05       0  4910.8     .07       0  4991.1     .05       0
  4991.9     .05       0  4995.9     .05       0  5001.8     .07       0
  5411.7     .05       0
Bank Sta=4991.9,4995.9
XS Rating Curve= 0 ,0
Exp/Cntr=0.3,0.1

Type RM Length L Ch R = 1 ,23834   ,602,602,602
BEGIN DESCRIPTION:
Mapping XS 94eca23e
END DESCRIPTION:
XS GIS Cut Line= 3
      2463237.85     13487609.91      2463272.57     13486815.61
      2463203.13     13486264.42
#Sta/Elev= 30
    4164  306.99  4198.9  306.88    4249  305.43    4299  304.66  4429.2  304.83
  4443.2   304.5  4489.2  304.99  4569.3  305.17  4659.4  304.88  4679.4  304.34
  4729.4  304.02  4829.5  302.54  4849.6  302.58  4897.4  301.07  4919.6  300.68
  4967.7  300.48    4968  299.98  4971.5  299.98  4971.7  300.48  5059.5  301.12
    5131  302.42  5142.9  303.04  5211.6  304.64  5218.2  305.27  5230.4  305.22
  5272.1  306.14  5423.3  310.79  5453.5  311.38  5483.8  312.71  5514.6  313.12
#Mann= 5 ,-1 , 0
    4164     .05       0  4967.7     .05       0  4971.7     .05       0
  5059.5     .07       0  5230.4     .05       0
Bank Sta=4967.7,4971.7
XS Rating Curve= 0 ,0
Exp/Cntr=0.3,0.1

Type RM Length L Ch R = 1 ,23232   ,451,451,451
BEGIN DESCRIPTION:
HOG CREEK 47.0
END DESCRIPTION:
XS GIS Cut Line= 3
        2463775.     13487574.95        2463775.       13487025.
        2463775.     13486674.95
#Sta/Elev= 30
  4450.1  309.65  4490.1   307.7  4530.1  306.11  4640.1  302.57  4650.1  302.05
  4670.1  301.84  4690.1  300.72  4750.1  299.18  4780.1  298.11  4860.1  296.07
  4930.1  295.29  4960.1  294.71  4980.1  294.95  4995.6  294.51  4995.8  294.01
  4999.3  294.01  4999.6  294.51  5010.1  294.94  5052.1  295.27  5101.4  296.02
  5120.1  296.39  5210.1  299.26  5230.1  299.26  5240.1   299.8  5257.1  299.96
  5280.1  300.92  5290.1  302.02  5300.1  304.04  5310.1  305.55  5350.1  306.51
#Mann= 6 ,-1 , 0
  4450.1     .05       0  4995.6     .05       0  4999.6     .05       0
  5052.1     .07       0  5101.4     .12       0  5257.1     .07       0
Bank Sta=4995.6,4999.6
XS Rating Curve= 0 ,0
Exp/Cntr=0.3,0.1

Type RM Length L Ch R = 1 ,22781   ,406,406,406
BEGIN DESCRIPTION:
HOG CREEK 46.0
END DESCRIPTION:
XS GIS Cut Line= 3
        2463975.       13487475.        2464175.       13487175.
      2464025.01     13486625.04
#Sta/Elev= 30
  4634.7  304.18  4670.8  303.49  4678.3  302.82  4750.4  300.07  4765.4  299.88
  4792.4  298.57  4843.5  296.95  4894.6   294.8  4966.7  293.56  4970.2  293.18
  4981.7  292.46  4985.7  291.68    4986  291.18  4989.5  291.18  4989.7  291.68
  5086.8  292.38  5119.6  292.34  5126.5  291.94  5185.7  293.22  5223.3  294.53
  5275.1   295.3  5288.7  295.83  5359.8  299.11  5430.2  301.32  5451.3  302.48
  5461.7  302.39  5468.6  302.91  5542.9   305.3    5555  305.98  5565.3  305.81
#Mann= 7 ,-1 , 0
  4634.7     .05       0  4970.2      .1       0  4985.7     .05       0
  4989.7      .1       0  5185.7     .07       0  5288.7     .12       0
  5430.2     .07       0
Bank Sta=4985.7,4989.7
XS Rating Curve= 0 ,0
Exp/Cntr=0.3,0.1

Type RM Length L Ch R = 1 ,22375   ,490,490,490
BEGIN DESCRIPTION:
HOG CREEK 45.0
END DESCRIPTION:
XS GIS Cut Line= 3
      2464175.01     13487574.98        2464525.       13487075.
      2464224.98     13486774.98
#Sta/Elev= 30
  4399.1  302.34  4448.3  302.16  4484.5  299.98  4513.7  299.37  4521.1  299.83
  4635.8   296.7  4665.4  295.79  4671.5  294.94  4686.4  294.75  4701.2   293.5
  4707.3  293.91  4722.1   293.5  4772.7  291.12  4778.8  291.66  4829.4  289.87
  4873.8  289.86  4879.9  289.26  4945.3  288.72  4964.3  287.15  4964.5  286.65
    4968  286.65  4968.3  287.15  5012.9  287.18  5210.2  290.97  5235.7   292.3
    5264  292.93  5306.4   293.1  5348.8  295.34  5419.5  297.37  5433.7  298.31
#Mann= 4 ,-1 , 0
  4399.1     .05       0  4964.3     .05       0  4968.3     .05       0
  5210.2     .07       0
Bank Sta=4964.3,4968.3
XS Rating Curve= 0 ,0
Exp/Cntr=0.3,0.1

Type RM Length L Ch R = 1 ,21885   ,356,356,356
BEGIN DESCRIPTION:
HOG CREEK 44.0
END DESCRIPTION:
XS GIS Cut Line= 3
      2464375.02     13487574.99        2464975.       13487175.
      2465174.99     13486575.04
#Sta/Elev= 30
    4284  298.92  4312.5  298.61  4327.5  297.53  4363.6   296.2    4390  295.72
  4450.7  293.85  4486.8  291.87  4524.8  290.32  4645.2  286.81  4765.7  285.19
  4769.4  285.21  4788.8  285.39  4811.3  284.72  4919.5  283.89  5002.1   282.8
  5046.4  282.88  5089.4  282.98    5100  282.47    5119   280.6  5119.3   280.1
  5122.8   280.1    5123   280.6  5184.3  282.91    5249  283.63  5300.2  284.18
  5426.7  286.62  5500.5  289.99  5542.7  290.23  5605.9  293.35  5637.5  294.05
#Mann= 10 ,-1 , 0
    4284     .07       0    4390     .05       0  4524.8    .035       0
  4645.2     .05       0  4765.7    .035       0  4769.4     .05       0
  5046.4      .1       0    5119     .05       0    5123      .1       0
    5249     .05       0
Bank Sta=5119,5123
XS Rating Curve= 0 ,0
Exp/Cntr=0.3,0.1

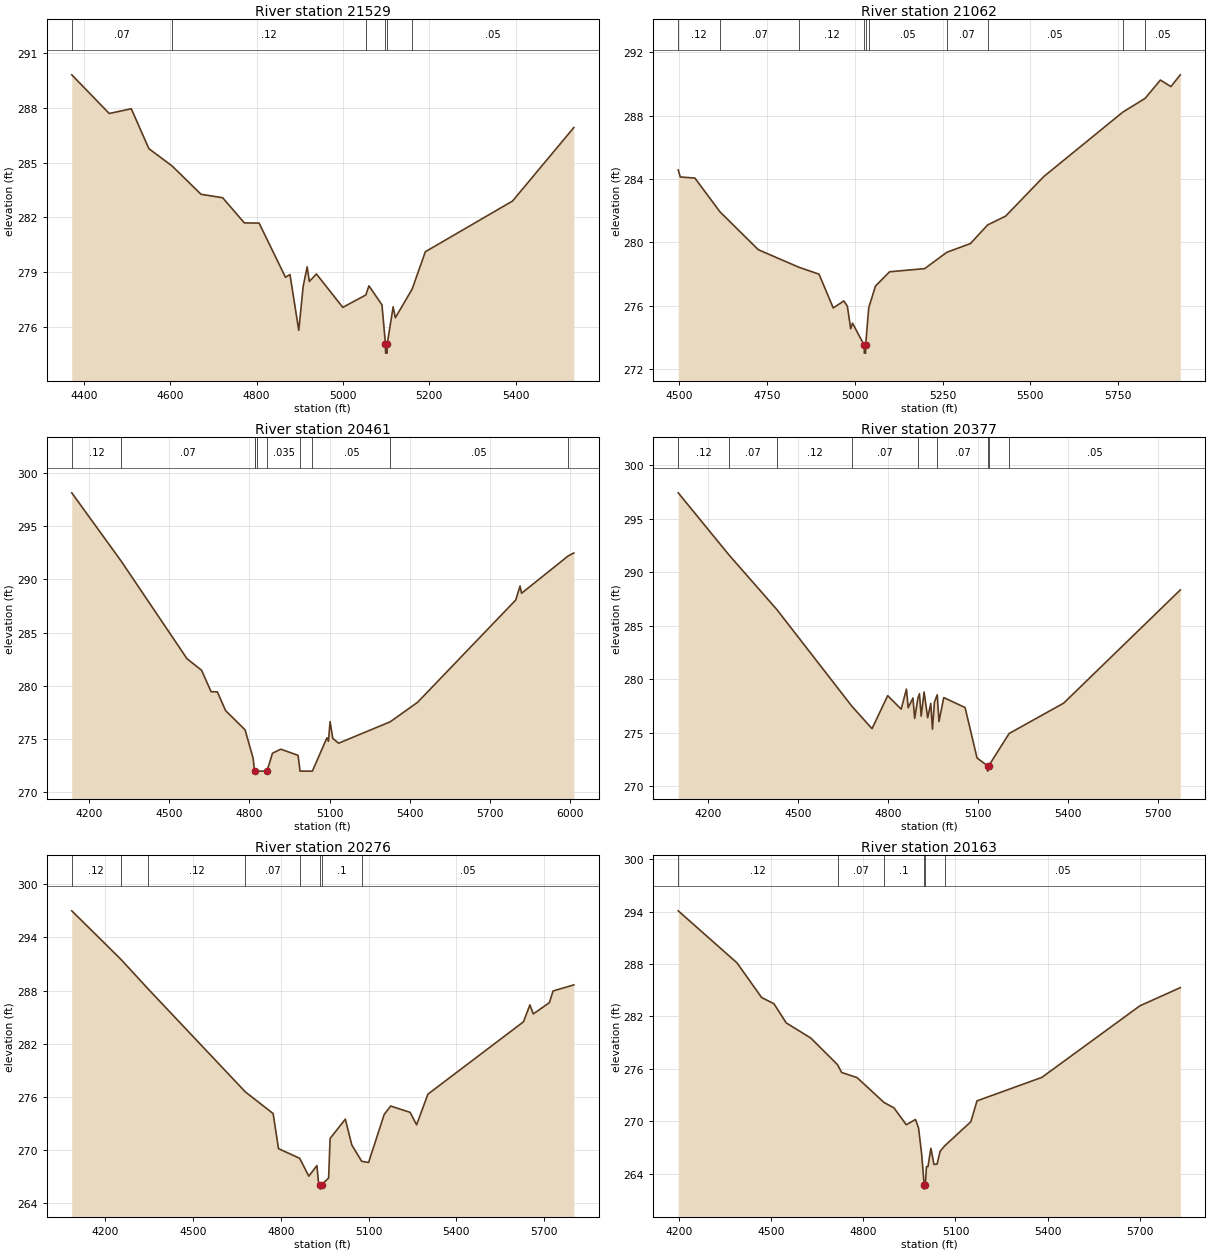
Type RM Length L Ch R = 1 ,21529   ,467,467,467
BEGIN DESCRIPTION:
Mapping XS 45709dc0
END DESCRIPTION:
XS GIS Cut Line= 3
      2465168.69       13487890.      2465293.69      13487285.8
      2465363.14     13486744.13
#Sta/Elev= 30
  4371.8  289.81  4458.6  287.69  4509.7  287.95  4550.5  285.76  4604.4  284.81
  4671.2  283.26  4721.4  283.07  4771.6  281.69  4805.8  281.68  4866.9  278.71
  4877.3  278.86  4897.7   275.8  4907.9  278.22  4917.1  279.28  4922.2  278.48
  4938.6  278.89  4999.7  277.06  5053.1  277.74  5060.2  278.24  5090.4   277.2
  5098.5  275.05  5098.8  274.55  5102.3  274.55  5102.5  275.05  5116.3  277.09
  5121.4  276.49  5160.3  278.06  5190.9  280.11  5392.9  282.89  5534.9  286.92
#Mann= 6 ,-1 , 0
  4371.8     .07       0  4604.4     .12       0  5053.1      .1       0
  5098.5     .05       0  5102.5      .1       0  5160.3     .05       0
Bank Sta=5098.5,5102.5
XS Rating Curve= 0 ,0
Exp/Cntr=0.3,0.1

Type RM Length L Ch R = 1 ,21062   ,601,601,601
BEGIN DESCRIPTION:
Mapping XS ca5faf01
END DESCRIPTION:
XS GIS Cut Line= 3
      2465668.69     13487771.94      2465731.19     13487313.58
      2465695.99     13486348.32
#Sta/Elev= 30
    4498  284.57  4503.8  284.13  4545.4  284.06  4616.8  281.93  4725.9  279.54
    4842  278.43  4898.6     278    4939  275.87  4969.2  276.31  4979.2  275.98
  4988.7  274.56  4993.8  274.91  5027.2  273.52  5027.5  273.02    5031  273.02
  5031.2  273.52    5040  275.88  5059.2  277.25  5099.3  278.15  5199.3  278.35
  5262.3  279.38  5329.4  279.93  5378.1   281.1  5429.5  281.66  5538.3  284.16
    5763  288.22  5826.1  289.08  5869.8  290.24  5899.8  289.83  5926.5  290.57
#Mann= 10 ,-1 , 0
    4498     .12       0  4616.8     .07       0    4842     .12       0
  5027.2     .05       0  5031.2     .12       0    5040     .05       0
  5262.3     .07       0  5378.1     .05       0    5763     .07       0
  5826.1     .05       0
Bank Sta=5027.2,5031.2
XS Rating Curve= 0 ,0
Exp/Cntr=0.3,0.1

Type RM Length L Ch R = 1 ,20461   ,84,84,84
BEGIN DESCRIPTION:
HOG CREEK 41.0
END DESCRIPTION:
XS GIS Cut Line= 3
      2466490.66      13488062.8        2466275.       13487225.
      2465796.05     13486330.35
#Sta/Elev= 30
  4134.9  298.11  4320.6  291.68  4566.3  282.55    4621  281.46  4656.6  279.45
  4679.9  279.44  4710.9  277.68  4783.9  275.87  4814.1  273.19  4819.3     272
  4822.6     272  4826.6     272  4865.8     272  4886.4  273.68  4917.4  274.06
  4982.2  273.48  4989.7     272  5035.8     272  5090.2  275.12  5095.9   274.8
  5102.1  276.64  5112.2  275.07  5134.1  274.62  5327.4  276.63  5429.9  278.46
  5797.1  288.05  5813.4  289.37  5819.1  288.69  5993.6  292.19  6014.8  292.47
#Mann= 10 ,-1 , 0
  4134.9     .12       0  4320.6     .07       0  4819.3     .05       0
  4822.6     .05       0  4826.6    .035       0  4865.8    .035       0
  4989.7    .035       0  5035.8     .05       0  5327.4     .05       0
  5993.6     .07       0
Bank Sta=4819.3,4865.8
XS Rating Curve= 0 ,0
Exp/Cntr=0.3,0.1

Type RM Length L Ch R = 1 ,20377   ,101,101,101
BEGIN DESCRIPTION:
Mapping XS d10f2ba2
END DESCRIPTION:
XS GIS Cut Line= 6
      2466537.65     13488032.15       2466478.6     13487574.95
       2466406.9     13487294.63      2466325.18     13487149.58
      2466300.66     13487133.23       2466002.4     13486471.33
#Sta/Elev= 30
  4101.1  297.42  4270.5   291.6  4429.7   286.5  4679.5  277.46  4746.7  275.36
  4798.8  278.45  4843.7  277.19  4861.3  279.06  4867.1  277.32    4883  278.23
  4888.7  276.32  4899.5  278.22  4904.7  278.63  4910.4  276.53  4920.1  278.79
  4932.1  276.38  4942.3  277.73    4948  275.31  4954.5  277.84  4963.9  278.53
  4969.7  276.03  4985.6  278.27  5056.6  277.34  5096.5  272.62  5131.4  271.89
  5131.7  271.39  5135.4  271.89  5203.4  274.91  5385.1  277.75  5773.6  288.34
#Mann= 9 ,-1 , 0
  4101.1     .12       0  4270.5     .07       0  4429.7     .12       0
  4679.5     .07       0  4899.5      .1       0  4963.9     .07       0
  5131.4     .05       0  5135.4     .07       0  5203.4     .05       0
Bank Sta=5131.4,5135.4
XS Rating Curve= 0 ,0
Exp/Cntr=0.3,0.1

Type RM Length L Ch R = 1 ,20276   ,113,113,113
BEGIN DESCRIPTION:
Mapping XS 8d0d5919
END DESCRIPTION:
XS GIS Cut Line= 4
      2466549.92     13488026.07      2466498.84     13487415.17
      2466419.16     13487118.93      2466053.45     13486412.02
#Sta/Elev= 30
    4086     297  4253.8  291.53  4345.3  288.24  4679.4  276.55  4774.2  274.11
  4792.4  270.15  4864.9  269.06    4896  267.04  4923.7  268.24  4928.9  266.42
  4935.4  266.08  4935.6  265.58  4939.4  266.08  4963.7  266.83  4968.8   271.3
  5020.8  273.48  5042.9  270.57  5076.8  268.72  5100.3  268.59  5153.6  274.01
  5175.8  274.96  5242.2  274.25  5264.3  272.84    5303   276.3  5629.5  284.47
  5651.6  286.38  5663.2  285.36    5718  286.63  5730.8  287.95  5801.7  288.64
#Mann= 8 ,-1 , 0
    4086     .12       0  4253.8     .07       0  4345.3     .12       0
  4679.4     .07       0  4864.9      .1       0  4935.4     .05       0
  4939.4      .1       0  5076.8     .05       0
Bank Sta=4935.4,4939.4
XS Rating Curve= 0 ,0
Exp/Cntr=0.3,0.1

Type RM Length L Ch R = 1 ,20163   ,92,92,92
BEGIN DESCRIPTION:
Mapping XS e85e4ef7
END DESCRIPTION:
XS GIS Cut Line= 3
      2466578.52     13487925.94      2466533.57     13487118.93
      2466547.87     13486293.51
#Sta/Elev= 30
  4197.8  294.09    4389  288.13  4469.2  284.16  4509.2  283.45  4549.3  281.25
  4629.4  279.51  4716.1  276.47  4729.6  275.57  4779.6  274.99  4867.3  272.14
  4899.8  271.52  4939.9  269.59  4969.9  270.19  4979.9   269.2    4990   266.2
    4998  262.71  4998.2  262.21    5002  262.71  5005.5  264.79  5010.5  264.79
    5020  266.89    5030  265.04    5040  265.07    5050  266.54  5064.9  267.17
    5150  269.93    5170  272.32  5381.1  275.01  5700.1  283.21  5831.6  285.29
#Mann= 6 ,-1 , 0
  4197.8     .12       0  4716.1     .07       0  4867.3      .1       0
    4998     .05       0    5002      .1       0  5064.9     .05       0
Bank Sta=4998,5002
XS Rating Curve= 0 ,0
Exp/Cntr=0.3,0.1

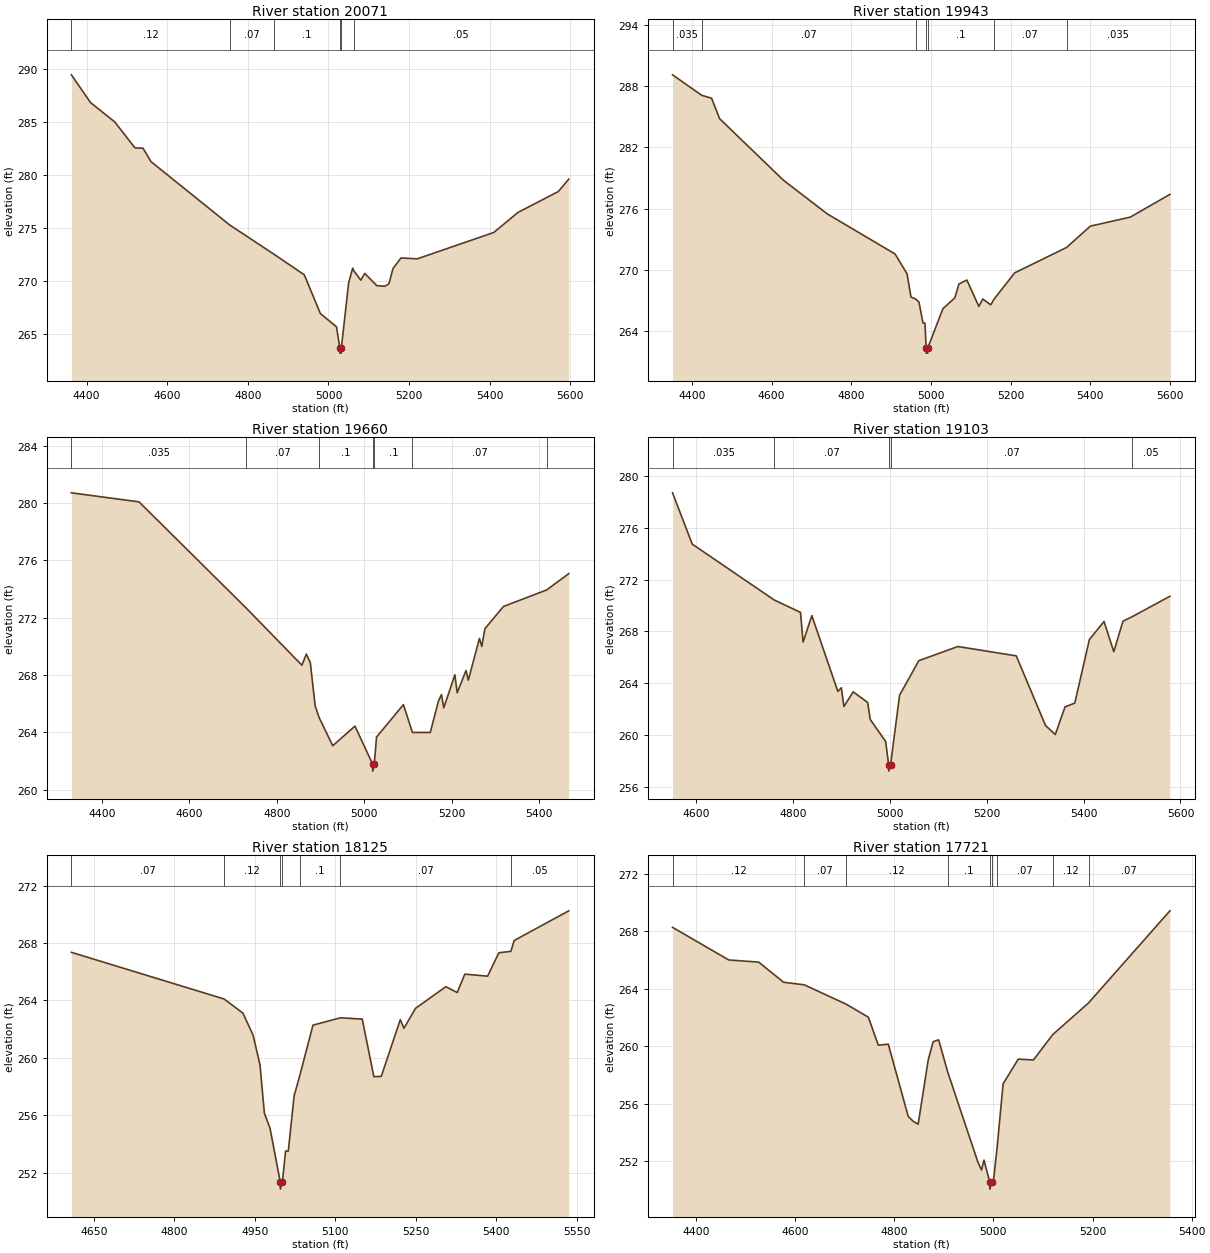
Type RM Length L Ch R = 1 ,20071   ,128,128,128
BEGIN DESCRIPTION:
Mapping XS 1c783a5c
END DESCRIPTION:
XS GIS Cut Line= 3
      2466615.71     13487762.52      2466626.13     13487125.01
      2466628.73     13486529.01
#Sta/Elev= 30
  4362.4  289.49  4409.9  286.87  4469.9  285.05  4519.9   282.6  4539.9  282.57
  4559.9   281.3  4755.3  275.32  4865.2  272.56    4940  270.63    4980  266.97
    5020  265.72    5028  263.74  5028.3  263.24  5031.8  263.24    5032  263.74
    5050  269.85    5060  271.25  5062.3  271.04    5080  270.12    5090  270.76
    5120   269.6    5140  269.55    5150  269.78    5160  271.22    5180  272.22
    5220  272.13    5410  274.62    5470  276.51    5570  278.48    5596  279.65
#Mann= 6 ,-1 , 0
  4362.4     .12       0  4755.3     .07       0  4865.2      .1       0
    5028     .05       0    5032      .1       0  5062.3     .05       0
Bank Sta=5028,5032
XS Rating Curve= 0 ,0
Exp/Cntr=0.3,0.1

Type RM Length L Ch R = 1 ,19943   ,283,283,283
BEGIN DESCRIPTION:
Mapping XS e7925cdb
END DESCRIPTION:
XS GIS Cut Line= 3
      2466727.69     13487772.91      2466753.73     13487140.09
      2466758.94     13486525.47
#Sta/Elev= 30
  4351.6  289.11  4424.9   287.1  4449.6  286.82  4469.6  284.82  4629.7  278.79
  4739.8  275.49    4910  271.56    4940  269.62    4950  267.33  4961.3  267.16
    4970  266.85    4980   264.8    4985   264.8    4988  262.35  4988.3  261.85
  4991.8  261.85    4992  262.35    5030   266.2    5060  267.26    5070  268.61
  5090.1  269.01  5120.1  266.43  5130.1  267.15  5150.1  266.58  5158.2  267.13
  5210.1  269.71  5340.3   272.2  5400.1  274.29  5500.1  275.17  5599.6   277.4
#Mann= 7 ,-1 , 0
  4351.6    .035       0  4424.9     .07       0  4961.3      .1       0
    4988     .05       0    4992      .1       0  5158.2     .07       0
  5340.3    .035       0
Bank Sta=4988,4992
XS Rating Curve= 0 ,0
Exp/Cntr=0.3,0.1

Type RM Length L Ch R = 1 ,19660   ,557,557,557
BEGIN DESCRIPTION:
Mapping XS edbafbe5
END DESCRIPTION:
XS GIS Cut Line= 3
      2467085.36      13487688.6      2467008.97     13487049.69
       2466842.3      13486584.4
#Sta/Elev= 30
    4330  280.72  4484.7  280.09  4729.5  272.69  4857.3  268.69  4867.4  269.47
  4876.5  268.87  4887.5  265.87  4896.3  265.06  4927.8  263.07  4978.6  264.44
  5018.9   261.8  5019.2   261.3  5022.9   261.8    5028  263.68  5089.5  265.94
  5110.1     264    5151     264  5169.6  266.19  5176.5  266.64  5181.8  265.72
  5207.2  268.02  5212.5  266.77  5232.7  268.32    5238  267.65  5263.4  270.56
  5268.7     270  5275.9  271.24  5318.4  272.79    5417  273.94  5467.7  275.08
#Mann= 7 ,-1 , 0
    4330    .035       0  4729.5     .07       0  4896.3      .1       0
  5018.9     .05       0  5022.9      .1       0  5110.1     .07       0
    5417     .05       0
Bank Sta=5018.9,5022.9
XS Rating Curve= 0 ,0
Exp/Cntr=0.3,0.1

Type RM Length L Ch R = 1 ,19103   ,978,978,978
BEGIN DESCRIPTION:
Mapping XS 85ff031b
END DESCRIPTION:
XS GIS Cut Line= 3
      2467272.85     13487542.78      2467432.58     13487133.02
       2467370.1     13486549.85
#Sta/Elev= 30
  4551.9  278.68  4592.5  274.73  4761.9  270.42  4815.9  269.47  4821.3  267.18
  4839.3  269.22    4893  263.38  4900.2  263.66  4905.5  262.22  4924.7  263.35
  4954.5  262.53  4959.9  261.22  4991.7  259.52  4997.8  257.74    4998  257.24
  5001.8  257.74  5020.4  263.09  5060.1  265.75  5140.6  266.84  5261.2  266.12
  5321.6  260.75  5341.7  260.06  5361.8  262.19  5381.9  262.48  5412.1  267.38
  5442.3  268.77  5462.4  266.44  5481.4  268.79  5500.5  269.14  5578.2  270.71
#Mann= 5 ,-1 , 0
  4551.9    .035       0  4761.9     .07       0  4997.8     .05       0
  5001.8     .07       0  5500.5     .05       0
Bank Sta=4997.8,5001.8
XS Rating Curve= 0 ,0
Exp/Cntr=0.3,0.1

Type RM Length L Ch R = 1 ,18125   ,404,404,404
BEGIN DESCRIPTION:
Mapping XS 0cfb74f1
END DESCRIPTION:
XS GIS Cut Line= 3
      2468078.42     13487146.95      2467953.41     13486764.97
      2467599.66     13486376.53
#Sta/Elev= 30
  4608.2  267.35  4892.9   264.1  4927.9  263.12  4946.9  261.59  4959.8  259.52
    4968  256.15  4978.5   255.1  4997.6  251.36  4997.8  250.86  5001.6  251.36
  5007.5  253.51  5012.6  253.51  5023.4  257.35  5033.8  258.74  5058.6  262.28
  5109.9  262.79  5150.5   262.7  5172.1  258.69  5185.9  258.71  5221.4  262.66
  5228.2  262.06  5249.8  263.45  5306.5  264.96  5327.5  264.55  5341.7  265.83
  5384.2  265.69  5405.2  267.32  5427.7  267.42  5433.6  268.17  5535.5  270.24
#Mann= 7 ,-1 , 0
  4608.2     .07       0  4892.9     .12       0  4997.6     .05       0
  5001.6     .12       0  5033.8      .1       0  5109.9     .07       0
  5427.7     .05       0
Bank Sta=4997.6,5001.6
XS Rating Curve= 0 ,0
Exp/Cntr=0.3,0.1

Type RM Length L Ch R = 1 ,17721   ,373,373,373
BEGIN DESCRIPTION:
Mapping XS ec1a3350
END DESCRIPTION:
XS GIS Cut Line= 3
      2468307.58     13487167.73      2468238.14     13486528.86
       2468168.7     13486174.74
#Sta/Elev= 30
  4352.6  268.28    4466  266.01  4526.4  265.86  4576.6  264.46  4618.3  264.28
  4702.5  262.94  4747.6  262.03  4767.8  260.08  4787.9  260.15  4828.1  255.12
  4838.2  254.78  4848.2  254.58  4868.4  259.04  4878.4  260.32  4889.5  260.45
  4907.7  258.22  4968.9  251.92    4976  251.39    4981  252.08  4992.6  250.56
  4992.9  250.06  4996.7  250.56  4999.8  250.56  5007.3   252.9  5019.6  257.39
  5050.1  259.11  5080.7  259.05  5119.6  260.81  5191.9  263.02  5356.1  269.43
#Mann= 9 ,-1 , 0
  4352.6     .12       0  4618.3     .07       0  4702.5     .12       0
  4907.7      .1       0  4992.6     .05       0  4996.7      .1       0
  5007.3     .07       0  5119.6     .12       0  5191.9     .07       0
Bank Sta=4992.6,4996.7
XS Rating Curve= 0 ,0
Exp/Cntr=0.3,0.1

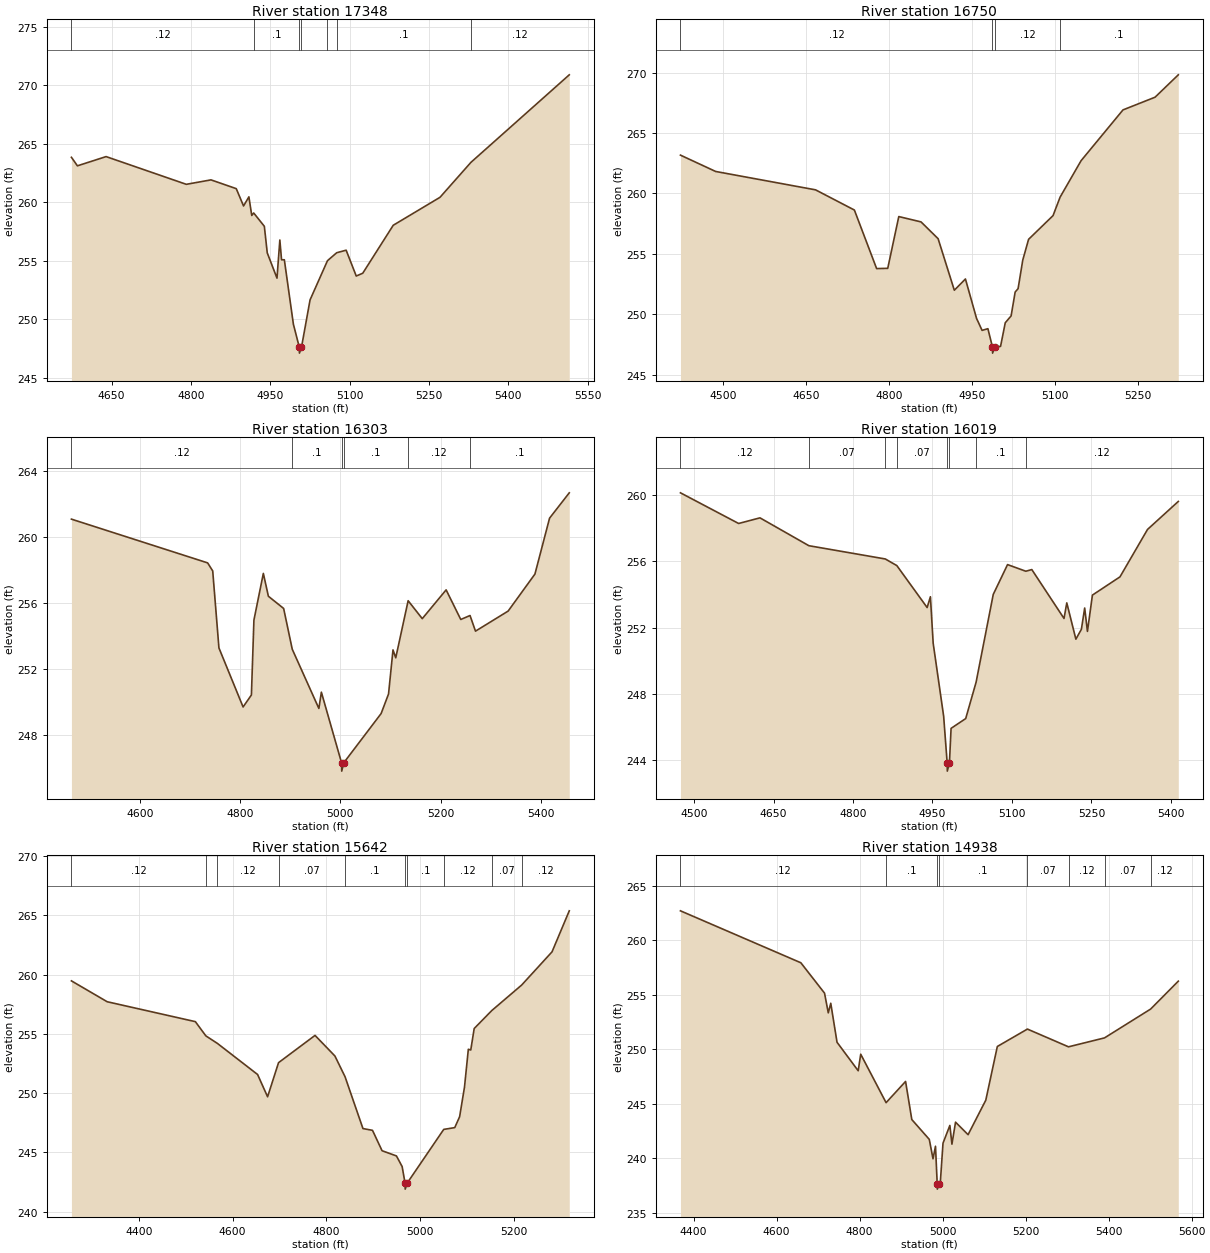
Type RM Length L Ch R = 1 ,17348   ,598,598,598
BEGIN DESCRIPTION:
Mapping XS 412936dc
END DESCRIPTION:
XS GIS Cut Line= 3
      2468710.34     13486945.48      2468557.58     13486577.47
      2468383.96     13486063.56
#Sta/Elev= 30
  4574.2  263.84  4585.5  263.11  4639.7   263.9  4791.3  261.53    4838  261.91
  4885.7  261.16  4899.5  259.68  4909.6  260.46    4915  258.87  4918.7  259.08
  4938.8  257.94  4944.3  255.67  4962.7  253.51  4968.1  256.77  4971.3  255.08
  4976.6  255.08  4993.7  249.57  5004.9   247.6  5005.1   247.1    5009   247.6
  5025.2  251.65  5058.1     255  5075.5  255.68  5093.4   255.9  5112.5  253.69
  5124.8  253.93  5182.4  258.03  5270.8  260.42  5329.3  263.41  5515.1  270.89
#Mann= 7 ,-1 , 0
  4574.2     .12       0  4918.7      .1       0  5004.9     .05       0
    5009      .1       0  5058.1     .12       0  5075.5      .1       0
  5329.3     .12       0
Bank Sta=5004.9,5009
XS Rating Curve= 0 ,0
Exp/Cntr=0.3,0.1

Type RM Length L Ch R = 1 ,16750   ,447,447,447
BEGIN DESCRIPTION:
Mapping XS e8fa9d2e
END DESCRIPTION:
XS GIS Cut Line= 3
      2468849.25      13486848.3      2468897.86     13486299.69
      2468787.36     13485968.18
#Sta/Elev= 30
    4423  263.17  4486.6  261.82  4667.3   260.3  4737.5  258.63  4777.7  253.79
  4797.8  253.81  4817.8  258.09    4858  257.65  4888.9  256.26  4918.2     252
  4938.3  252.93  4958.4  249.67  4968.4  248.68  4978.9  248.82  4987.2   247.3
  4987.4   246.8  4991.3   247.3  5001.8  247.36  5010.3  249.31  5020.9  249.88
  5028.2  251.85  5033.5  252.13    5042   254.5  5052.5  256.21  5096.7  258.17
  5109.5   259.7  5147.4  262.71  5223.2  266.91  5281.2  267.96  5323.2  269.81
#Mann= 4 ,-1 , 0
    4423     .12       0  4987.2     .05       0  4991.3     .12       0
  5109.5      .1       0
Bank Sta=4987.2,4991.3
XS Rating Curve= 0 ,0
Exp/Cntr=0.3,0.1

Type RM Length L Ch R = 1 ,16303   ,284,284,284
BEGIN DESCRIPTION:
Mapping XS 23283544
END DESCRIPTION:
XS GIS Cut Line= 3
      2469342.31     13486903.88      2469265.91     13486383.02
      2469085.36     13485952.47
#Sta/Elev= 30
  4463.3   261.1  4735.1  258.44  4745.2  257.95  4757.6  253.27  4805.8  249.68
  4822.4  250.41  4827.4  254.96  4846.2   257.8  4856.3  256.41  4886.7  255.67
  4903.9  253.19    4957  249.59    4962  250.58  5002.3  246.28  5002.6  245.78
  5006.5  246.28  5081.2  249.28    5096  250.47  5104.9  253.15  5110.4  252.67
  5135.1  256.14  5163.3  255.05  5210.9   256.8  5240.1     255  5258.6  255.24
  5269.5  254.29  5334.6  255.51  5388.1  257.76  5417.3  261.16  5456.6   262.7
#Mann= 6 ,-1 , 0
  4463.3     .12       0  4903.9      .1       0  5002.3     .05       0
  5006.5      .1       0  5135.1     .12       0  5258.6      .1       0
Bank Sta=5002.3,5006.5
XS Rating Curve= 0 ,0
Exp/Cntr=0.3,0.1

Type RM Length L Ch R = 1 ,16019   ,377,377,377
BEGIN DESCRIPTION:
Mapping XS 47c5ab1b
END DESCRIPTION:
XS GIS Cut Line= 3
      2469479.95     13486893.89      2469527.69     13486524.99
      2469371.72     13485979.11
#Sta/Elev= 30
  4474.3  260.13  4584.1  258.28  4624.4  258.62  4716.7  256.94  4860.9  256.14
  4882.7  255.74  4939.9  253.21  4946.1  253.86  4951.3  251.06  4971.1  246.65
  4977.7  243.84    4978  243.34    4982  243.84  4985.1  245.92  5012.7  246.51
  5032.3   248.7  5064.7     254  5091.7   255.8  5126.2   255.4  5137.5   255.5
  5198.3  252.55  5203.5  253.49  5220.7   251.3  5231.1   251.9  5237.3  253.18
  5242.5  251.77  5251.9  253.96  5303.9  255.06  5355.9  257.92    5414  259.61
#Mann= 8 ,-1 , 0
  4474.3     .12       0  4716.7     .07       0  4860.9     .12       0
  4882.7     .07       0  4977.7     .05       0    4982     .07       0
  5032.3      .1       0  5126.2     .12       0
Bank Sta=4977.7,4982
XS Rating Curve= 0 ,0
Exp/Cntr=0.3,0.1

Type RM Length L Ch R = 1 ,15642   ,704,704,704
BEGIN DESCRIPTION:
Mapping XS 44ad060a
END DESCRIPTION:
XS GIS Cut Line= 3
      2469633.98     13486903.81       2469779.8     13486216.36
       2469682.7     13485869.55
#Sta/Elev= 30
  4255.9  259.47  4332.2  257.71  4520.5  256.03  4542.9  254.83  4567.7  254.19
  4653.4  251.57  4674.7  249.69  4698.1  252.57    4776  254.87  4818.5  253.13
  4840.1  251.38  4878.3  247.01  4898.7  246.86  4919.1  245.14  4949.8   244.7
    4962   243.8  4968.2   242.4  4968.5   241.9  4972.6   242.4  5050.8  246.94
  5074.3  247.09  5084.7  248.01  5095.1  250.51  5103.3   253.7  5108.5  253.64
  5115.8  255.45  5153.2  256.96  5217.2  259.12    5282  261.92  5318.8  265.38
#Mann= 10 ,-1 , 0
  4255.9     .12       0  4542.9     .07       0  4567.7     .12       0
  4698.1     .07       0  4840.1      .1       0  4968.2     .05       0
  4972.6      .1       0  5050.8     .12       0  5153.2     .07       0
  5217.2     .12       0
Bank Sta=4968.2,4972.6
XS Rating Curve= 0 ,0
Exp/Cntr=0.3,0.1

Type RM Length L Ch R = 1 ,14938   ,351,351,351
BEGIN DESCRIPTION:
Mapping XS 2f8d070f
END DESCRIPTION:
XS GIS Cut Line= 3
      2469779.79     13487202.49      2470127.03     13486681.64
      2470196.48     13486112.15
#Sta/Elev= 30
  4368.2  262.71  4658.3  257.94  4715.4  255.15  4724.4  253.34  4730.4  254.22
  4745.5  250.64  4796.5  248.02  4802.6  249.54  4863.7  245.09  4910.7  247.04
  4925.7  243.54  4967.8  241.72  4976.8  239.94  4982.8  241.09  4986.9  237.65
  4987.2  237.15  4991.4  237.65  4994.2  237.65  5000.9  241.37  5017.4     243
  5022.4  241.28  5031.1   243.3  5061.3  242.15    5104  245.32  5131.8  250.25
  5204.3  251.85  5303.3  250.22  5390.1  251.04  5501.3  253.69  5567.9  256.25
#Mann= 8 ,-1 , 0
  4368.2     .12       0  4863.7      .1       0  4986.9     .05       0
  4991.4      .1       0  5204.3     .07       0  5303.3     .12       0
  5390.1     .07       0  5501.3     .12       0
Bank Sta=4986.9,4991.4
XS Rating Curve= 0 ,0
Exp/Cntr=0.3,0.1

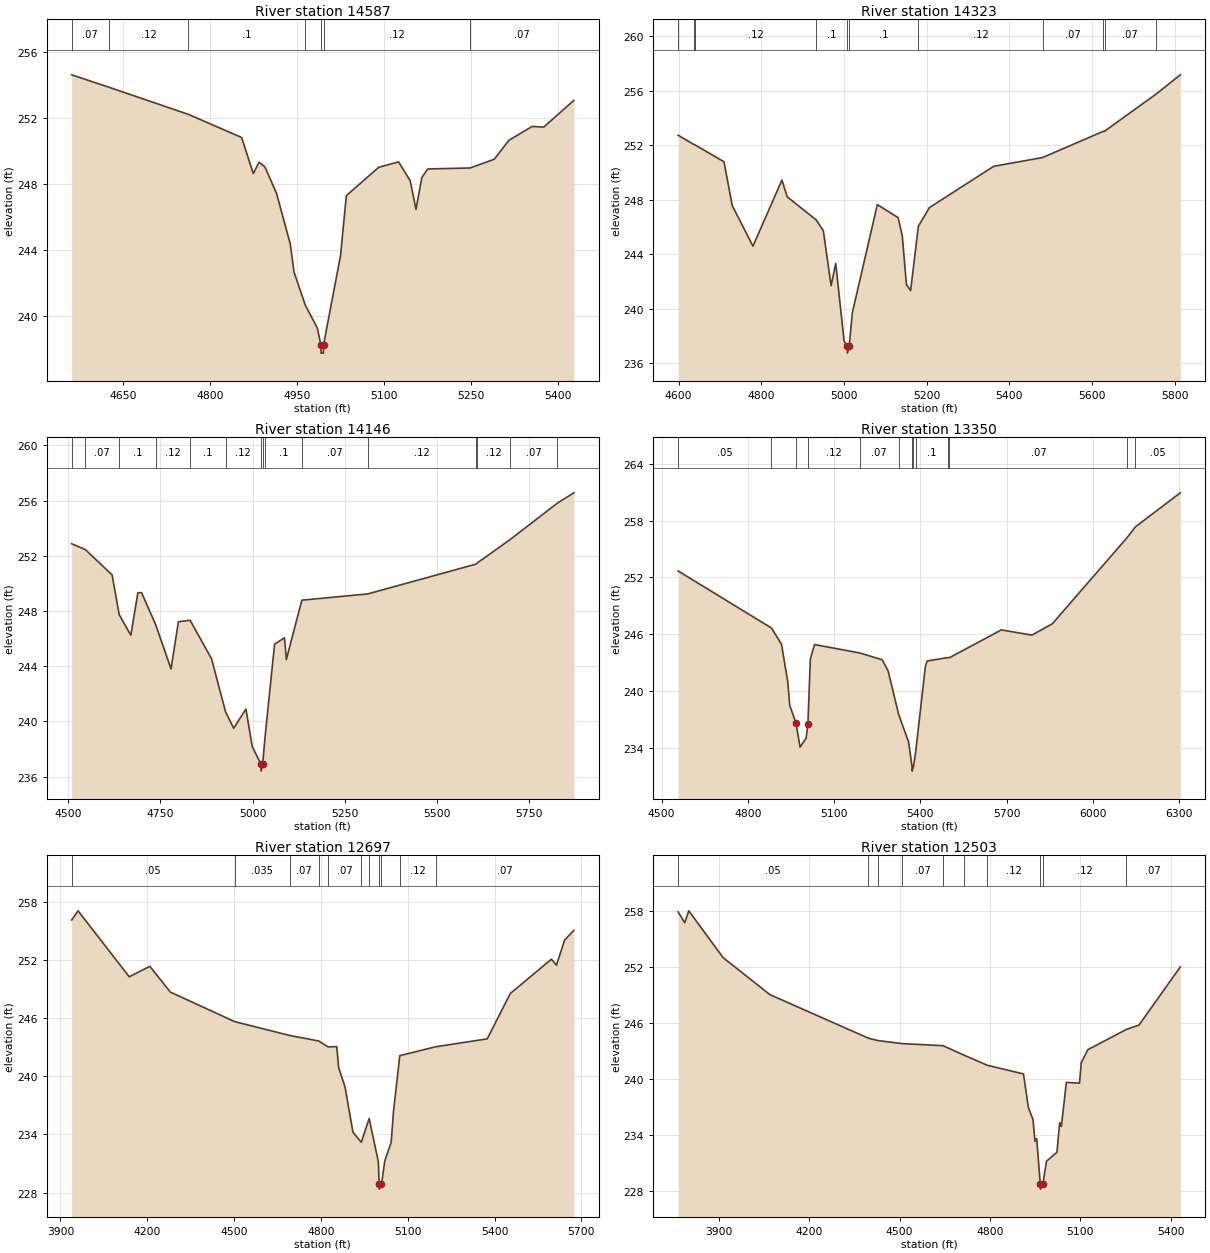
Type RM Length L Ch R = 1 ,14587   ,264,264,264
BEGIN DESCRIPTION:
Mapping XS c03112c4
END DESCRIPTION:
XS GIS Cut Line= 3
      2470390.05     13487067.06      2470424.77     13486633.02
      2470403.06     13486203.29
#Sta/Elev= 30
  4561.4  254.63  4625.5  253.88    4762  252.24  4854.4  250.83  4874.5  248.64
  4884.5  249.33  4894.5  249.05  4914.6  247.44  4938.3  244.37  4944.7  242.67
  4964.3  240.65  4984.8  239.28  4991.1  238.25  4991.4  237.75  4995.3  237.75
  4995.6  238.25  5024.9  243.66  5034.9   247.3  5090.7  249.02    5125  249.35
    5145  248.21    5155  246.47  5165.1   248.4  5175.1  248.92  5248.3  248.98
  5289.9  249.51  5315.2  250.66  5355.3   251.5  5375.3  251.46  5427.1  253.08
#Mann= 7 ,-1 , 0
  4561.4     .07       0  4625.5     .12       0    4762      .1       0
  4964.3     .12       0  4991.1     .05       0  4995.6     .12       0
  5248.3     .07       0
Bank Sta=4991.1,4995.6
XS Rating Curve= 0 ,0
Exp/Cntr=0.3,0.1

Type RM Length L Ch R = 1 ,14323   ,177,177,177
BEGIN DESCRIPTION:
Mapping XS 744a24fe
END DESCRIPTION:
XS GIS Cut Line= 4
       2470654.8     13487075.77       2470676.5     13486702.47
      2470621.71     13486221.03      2470399.96      13485941.6
#Sta/Elev= 30
  4598.8  252.75  4636.1  252.08  4639.1  252.05  4709.8   250.8  4729.8  247.58
  4779.9  244.61    4850  249.46  4862.8  248.23  4932.8  246.54  4950.2  245.74
    4969  241.71  4980.2  243.34  5000.4  237.66  5008.2  237.26  5008.5  236.76
  5012.7  237.26  5020.5  239.74  5080.9  247.66  5131.2   246.7  5141.3  245.35
  5151.3  241.79  5161.4  241.35  5180.2  246.07  5206.9  247.44  5362.7  250.47
  5480.7  251.11  5625.8  253.01  5630.6  253.04  5755.1  255.76    5814  257.18
#Mann= 11 ,-1 , 0
  4598.8     .12       0  4636.1     .07       0  4639.1     .12       0
  4932.8      .1       0  5008.2     .05       0  5012.7      .1       0
  5180.2     .12       0  5480.7     .07       0  5625.8     .12       0
  5630.6     .07       0  5755.1     .12       0
Bank Sta=5008.2,5012.7
XS Rating Curve= 0 ,0
Exp/Cntr=0.3,0.1

Type RM Length L Ch R = 1 ,14146   ,796,796,796
BEGIN DESCRIPTION:
Mapping XS 96273009
END DESCRIPTION:
XS GIS Cut Line= 4
      2470841.44     13487114.82      2470837.09      13486641.7
      2470771.12     13486237.63      2470412.96     13485917.26
#Sta/Elev= 30
  4509.1  252.87  4546.2  252.45  4618.9  250.61  4638.2  247.73  4669.7  246.24
  4688.9  249.32  4698.9  249.32  4736.8  247.03  4778.9   243.8  4798.9  247.22
  4830.7  247.32  4888.9  244.53  4927.1  240.67  4948.9   239.5  4982.2  240.89
  4999.2  238.18    5023  236.89  5023.3  236.39  5027.7  236.89  5033.6  238.75
    5060   245.6  5086.8  246.05  5091.9  244.48    5134  248.78  5312.5  249.23
  5607.5   251.4  5610.7  251.49  5699.1  253.17  5827.8  255.82  5872.2  256.56
#Mann= 15 ,-1 , 0
  4509.1     .12       0  4546.2     .07       0  4638.2      .1       0
  4736.8     .12       0  4830.7      .1       0  4927.1     .12       0
    5023     .05       0  5027.7     .12       0  5033.6      .1       0
    5134     .07       0  5312.5     .12       0  5607.5     .07       0
  5610.7     .12       0  5699.1     .07       0  5827.8     .12       0
Bank Sta=5023,5027.7
XS Rating Curve= 0 ,0
Exp/Cntr=0.3,0.1

Type RM Length L Ch R = 1 ,13350   ,653,653,653
BEGIN DESCRIPTION:
HOG CREEK 26.0
END DESCRIPTION:
XS GIS Cut Line= 4
      2471146.63     13487314.91        2471475.       13487025.
      2472061.54     13486242.94      2472289.89     13486002.78
#Sta/Elev= 30
  4557.2  252.69  4881.9  246.66    4917  244.93  4938.8  240.93  4945.5  238.49
  4967.2  236.61  4981.5  234.07  5002.5  235.01  5008.8  236.53  5017.1  243.36
  5031.7  244.91  5189.7  244.02  5267.1   243.3  5287.9  242.11  5324.5  237.51
  5358.8  234.63  5370.9  232.03  5371.3  231.53  5375.9  232.03  5383.2  233.44
  5417.1  242.54  5423.4  243.17  5494.8  243.53  5500.9  243.52  5681.7  246.46
  5787.9  245.91  5858.8   247.1  6120.4  256.26  6148.3  257.36  6304.2  260.95
#Mann= 13 ,-1 , 0
  4557.2     .05       0  4881.9     .12       0  4967.2     .05       0
  5008.8     .12       0  5189.7     .07       0  5324.5     .12       0
  5370.9     .07       0  5375.9     .12       0  5383.2      .1       0
  5494.8     .12       0  5500.9     .07       0  6120.4     .12       0
  6148.3     .05       0
Bank Sta=4967.2,5008.8
XS Rating Curve= 0 ,0
Exp/Cntr=0.3,0.1

Type RM Length L Ch R = 1 ,12697   ,194,194,194
BEGIN DESCRIPTION:
Mapping XS d72dc006
END DESCRIPTION:
XS GIS Cut Line= 3
      2471185.65      13487666.5      2471979.95      13486989.4
      2472275.08     13486364.41
#Sta/Elev= 30
  3938.9  256.18    3961  257.13  4137.8  250.31  4209.2  251.39  4279.7  248.73
  4502.2  245.67  4692.4  244.24  4792.5  243.67  4824.8  243.06  4854.8  243.09
  4861.4  240.91  4883.4  238.91  4910.8  234.23  4939.6   233.2  4966.6  235.65
  4998.6  231.16    5001  228.85  5001.5  228.35  5009.3  228.85  5020.7  231.27
  5042.8  233.19  5050.7  236.37  5072.5  242.15  5196.4  243.07  5374.6  243.89
  5454.3  248.58  5596.5  252.13  5613.7  251.51    5642  254.11  5673.8  255.11
#Mann= 11 ,-1 , 0
  3938.9     .05       0  4502.2    .035       0  4692.4     .07       0
  4792.5     .12       0  4824.8     .07       0  4939.6     .12       0
  4966.6     .07       0    5001     .05       0  5009.3     .07       0
  5072.5     .12       0  5196.4     .07       0
Bank Sta=5001,5009.3
XS Rating Curve= 0 ,0
Exp/Cntr=0.3,0.1

Type RM Length L Ch R = 1 ,12503   ,111,111,111
BEGIN DESCRIPTION:
Mapping XS 46ffd4e9
END DESCRIPTION:
XS GIS Cut Line= 3
      2471298.54     13487848.76      2472040.71     13487184.72
      2472357.54     13486594.45
#Sta/Elev= 30
  3765.6  257.86  3787.4   256.7  3801.1  257.97  3914.4  252.98  4069.9  249.01
  4396.8  244.35  4427.7   244.1  4508.8  243.77  4644.1  243.55  4714.3  242.53
  4790.6  241.46  4911.2  240.53  4927.4  236.94  4942.7  235.66  4949.3  233.33
    4955  233.61  4967.1  228.71  4967.6  228.21  4975.5  228.71  4987.5  231.19
  5022.2  232.15  5031.4  235.33    5037  234.91  5053.3  239.62  5097.1  239.54
  5102.8  241.72  5124.7  243.12    5252  245.28  5294.6  245.76  5431.4  251.97
#Mann= 10 ,-1 , 0
  3765.6     .05       0  4396.8     .07       0  4427.7    .035       0
  4508.8     .07       0  4644.1     .12       0  4714.3     .07       0
  4790.6     .12       0  4967.1     .05       0  4975.5     .12       0
    5252     .07       0
Bank Sta=4967.1,4975.5
XS Rating Curve= 0 ,0
Exp/Cntr=0.3,0.1