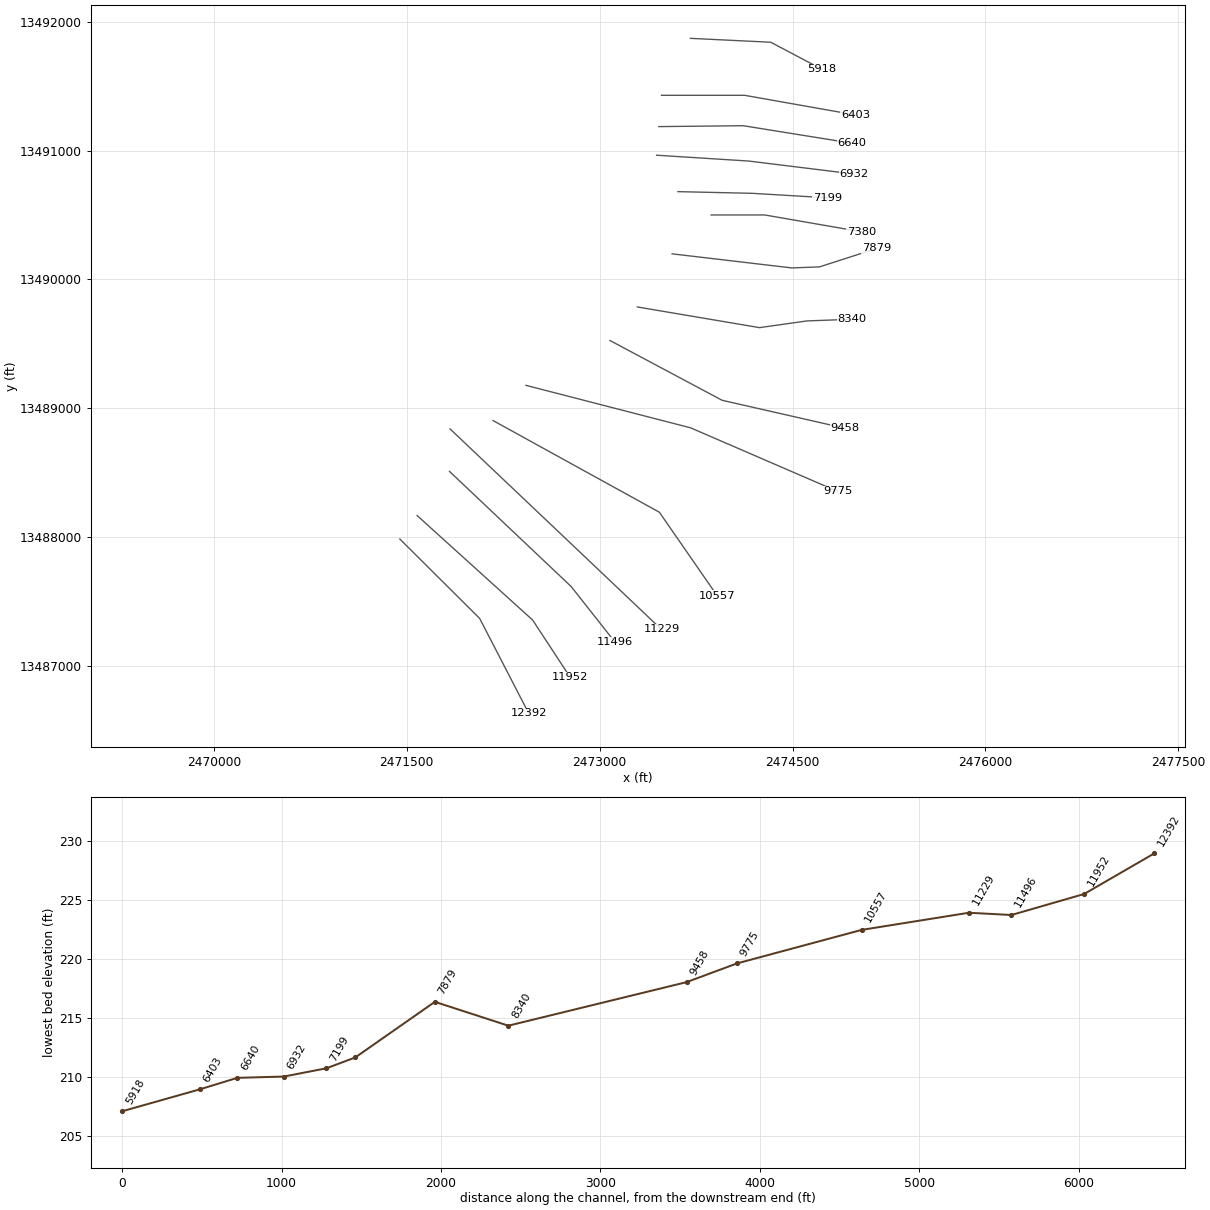
HEC-RAS study HOG CREEK.prj: HOG CREEK Base Level Engineering

--- HOG CREEK.g01 (geometry) --- (continued)

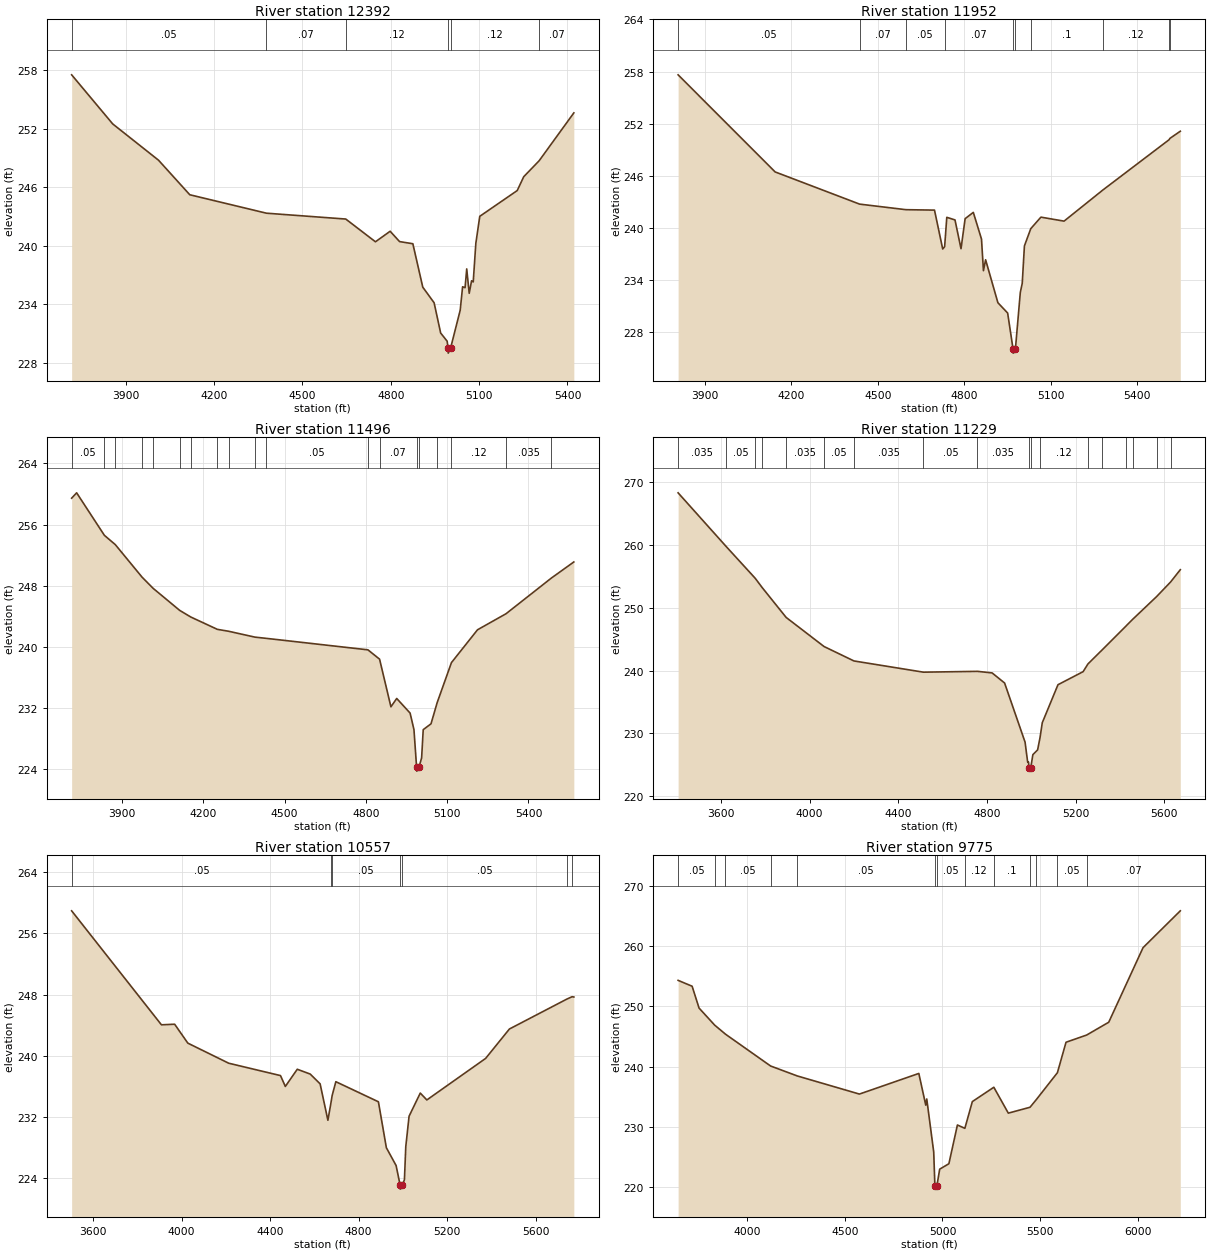
Type RM Length L Ch R = 1 ,12392   ,440,440,440
BEGIN DESCRIPTION:
Mapping XS 54db2bfb
END DESCRIPTION:
XS GIS Cut Line= 3
      2471446.09     13487983.33      2472066.75     13487367.01
       2472448.5     13486629.54
#Sta/Elev= 30
  3716.5  257.51  3855.9  252.48  4011.5  248.76  4117.6  245.22  4377.9  243.33
  4647.2  242.73    4748   240.4  4797.9  241.48  4829.9  240.42    4875   240.2
  4908.7  235.75  4947.2  234.15  4969.4  231.05  4991.5  230.21  4994.6  229.49
  4995.1  228.99    5003  229.49  5035.8  233.39  5043.9  235.79  5052.3   235.7
  5057.9  237.62  5066.4  235.12  5074.4  236.41    5080  236.29  5088.9  240.25
  5102.2  243.01  5229.4  245.65  5251.5  247.07  5303.7   248.7  5421.6  253.61
#Mann= 6 ,-1 , 0
  3716.5     .05       0  4377.9     .07       0  4647.2     .12       0
  4994.6     .05       0    5003     .12       0  5303.7     .07       0
Bank Sta=4994.6,5003
XS Rating Curve= 0 ,0
Exp/Cntr=0.3,0.1

Type RM Length L Ch R = 1 ,11952   ,456,456,456
BEGIN DESCRIPTION:
Mapping XS 273c161a
END DESCRIPTION:
XS GIS Cut Line= 3
      2471580.62     13488165.63      2472479.08     13487353.99
       2472769.9     13486911.24
#Sta/Elev= 30
  3808.1  257.62  4144.4  246.43  4437.2  242.72  4597.7  242.08  4696.7  242.03
  4725.1  237.55  4731.8  237.81  4739.3   241.2  4767.7   240.9  4788.6  237.58
  4802.8  241.04  4831.2  241.77  4859.6  238.69  4866.3  235.05  4873.8  236.31
  4916.4  231.36  4950.2  230.17  4968.8  226.05  4969.3  225.55  4977.2  226.05
  4994.1  232.55  5000.8   233.6  5008.3   237.9  5030.3  239.89  5065.5  241.22
  5145.7  240.76  5280.7  244.36  5510.1  250.15  5512.3  250.29  5548.6  251.12
#Mann= 10 ,-1 , 0
  3808.1     .05       0  4437.2     .07       0  4597.7     .05       0
  4731.8     .07       0  4968.8     .05       0  4977.2     .07       0
  5030.3      .1       0  5280.7     .12       0  5510.1      .1       0
  5512.3     .12       0
Bank Sta=4968.8,4977.2
XS Rating Curve= 0 ,0
Exp/Cntr=0.3,0.1

Type RM Length L Ch R = 1 ,11496   ,267,267,267
BEGIN DESCRIPTION:
Mapping XS bb96dd2c
END DESCRIPTION:
XS GIS Cut Line= 3
      2471832.34     13488508.53      2472778.56      13487614.4
      2473120.72     13487181.29
#Sta/Elev= 30
  3713.7  259.46  3732.1  260.16  3834.6   254.6  3874.8  253.39  3973.5  249.14
  4014.2  247.68  4112.5  244.79  4153.6  243.92  4251.5  242.31  4292.9  242.06
  4390.5  241.29  4432.3  241.13  4807.4  239.63  4850.4  238.41  4892.3  232.18
  4913.7  233.27  4963.1  231.36  4977.3   229.2  4987.1  224.27  4987.6  223.77
  4995.8  224.27  5005.6  225.51  5011.5  229.19  5040.3  229.96    5063  232.73
  5115.7  237.96  5211.9  242.25  5317.2  244.35  5484.4  249.01  5567.5  251.12
#Mann= 19 ,-1 , 0
  3713.7     .05       0  3834.6    .035       0  3874.8     .05       0
  3973.5    .035       0  4014.2     .05       0  4112.5    .035       0
  4153.6     .05       0  4251.5    .035       0  4292.9     .05       0
  4390.5    .035       0  4432.3     .05       0  4807.4    .035       0
  4850.4     .07       0  4987.1     .05       0  4995.8     .07       0
    5063    .063       0  5115.7     .12       0  5317.2    .035       0
  5484.4     .07       0
Bank Sta=4987.1,4995.8
XS Rating Curve= 0 ,0
Exp/Cntr=0.3,0.1

Type RM Length L Ch R = 1 ,11229   ,672,672,672
BEGIN DESCRIPTION:
Mapping XS 40841c7e
END DESCRIPTION:
XS GIS Cut Line= 3
      2471836.71     13488838.36      2472982.55     13487753.29
      2473480.82     13487281.02
#Sta/Elev= 30
  3407.2  268.34  3623.9  259.78  3755.2   254.7    3787   253.2  3894.4  248.47
  4065.3  243.83  4200.1  241.53  4513.4  239.74  4757.1  239.87  4823.3  239.62
  4879.5  238.01  4971.8  228.58  4983.5  225.39  4987.7  225.39  4988.5  224.46
    4989  223.96  4997.2  224.46    5007  226.59  5028.4  227.35  5039.2   229.3
  5049.4  231.68  5120.2  237.74  5233.5  239.82  5255.3  241.05  5317.6  243.23
  5425.6  247.05  5456.8  248.16  5564.8  251.79    5628  254.12  5671.8  256.08
#Mann= 18 ,-1 , 0
  3407.2    .035       0  3623.9     .05       0  3755.2    .035       0
    3787     .05       0  3894.4    .035       0  4065.3     .05       0
  4200.1    .035       0  4513.4     .05       0  4757.1    .035       0
  4988.5    .035       0  4997.2    .035       0  5039.2     .12       0
  5255.3    .035       0  5317.6     .12       0  5425.6    .035       0
  5456.8     .12       0  5564.8    .035       0    5628     .12       0
Bank Sta=4988.5,4997.2
XS Rating Curve= 0 ,0
Exp/Cntr=0.3,0.1

Type RM Length L Ch R = 1 ,10557   ,782,782,782
BEGIN DESCRIPTION:
Mapping XS b8c3a060
END DESCRIPTION:
XS GIS Cut Line= 3
      2472170.88     13488903.49      2473464.32     13488191.66
      2473915.71     13487540.62
#Sta/Elev= 30
  3503.7  258.96  3909.3  244.03    3969  244.11  4028.6  241.63  4213.3     239
  4447.2  237.38    4469  235.96  4522.9  238.21  4581.4  237.58  4626.1   236.3
  4661.3  231.53  4675.2  233.83  4680.6  234.78  4697.2  236.58  4889.5  233.95
  4925.4  227.93  4969.4   225.6  4987.8  223.01  4988.3  222.51  4996.6  223.01
    5007  223.73  5013.1  228.07    5028  232.06  5078.6  235.09  5108.3  234.19
  5373.8  239.63  5481.2  243.48  5741.4  247.41  5764.5  247.71  5772.3  247.67
#Mann= 7 ,-1 , 0
  3503.7     .05       0  4675.2     .12       0  4680.6     .05       0
  4987.8     .05       0  4996.6     .05       0  5741.4     .07       0
  5764.5     .12       0
Bank Sta=4987.8,4996.6
XS Rating Curve= 0 ,0
Exp/Cntr=0.3,0.1

Type RM Length L Ch R = 1 ,9775    ,317,317,317
BEGIN DESCRIPTION:
Mapping XS c639f39a
END DESCRIPTION:
XS GIS Cut Line= 3
      2472427.01      13489176.9      2473707.38     13488847.04
      2474851.58     13488352.96
#Sta/Elev= 30
  3647.8  254.28  3719.4  253.31  3754.9  249.69  3834.8  246.86  3890.1  245.36
    4121  240.08  4257.7  238.43  4575.1  235.43  4878.9  238.85  4914.4  233.59
  4919.5  234.62  4955.1  225.83  4961.2  220.17  4961.7  219.67  4971.1  220.17
  4985.7  222.98  5032.7  223.88  5076.3   230.3  5114.4  229.75  5152.6  234.18
  5262.5  236.56  5336.6  232.27  5447.6  233.24  5479.3  234.49  5587.7  238.97
  5631.8  244.02  5737.5  245.22  5850.3  247.34  6025.7   259.7  6216.3  265.81
#Mann= 13 ,-1 , 0
  3647.8     .05       0  3834.8    .035       0  3890.1     .05       0
    4121    .035       0  4257.7     .05       0  4961.2     .05       0
  4971.1     .05       0  5114.4     .12       0  5262.5      .1       0
  5447.6     .07       0  5479.3     .12       0  5587.7     .05       0
  5737.5     .07       0
Bank Sta=4961.2,4971.1
XS Rating Curve= 0 ,0
Exp/Cntr=0.3,0.1

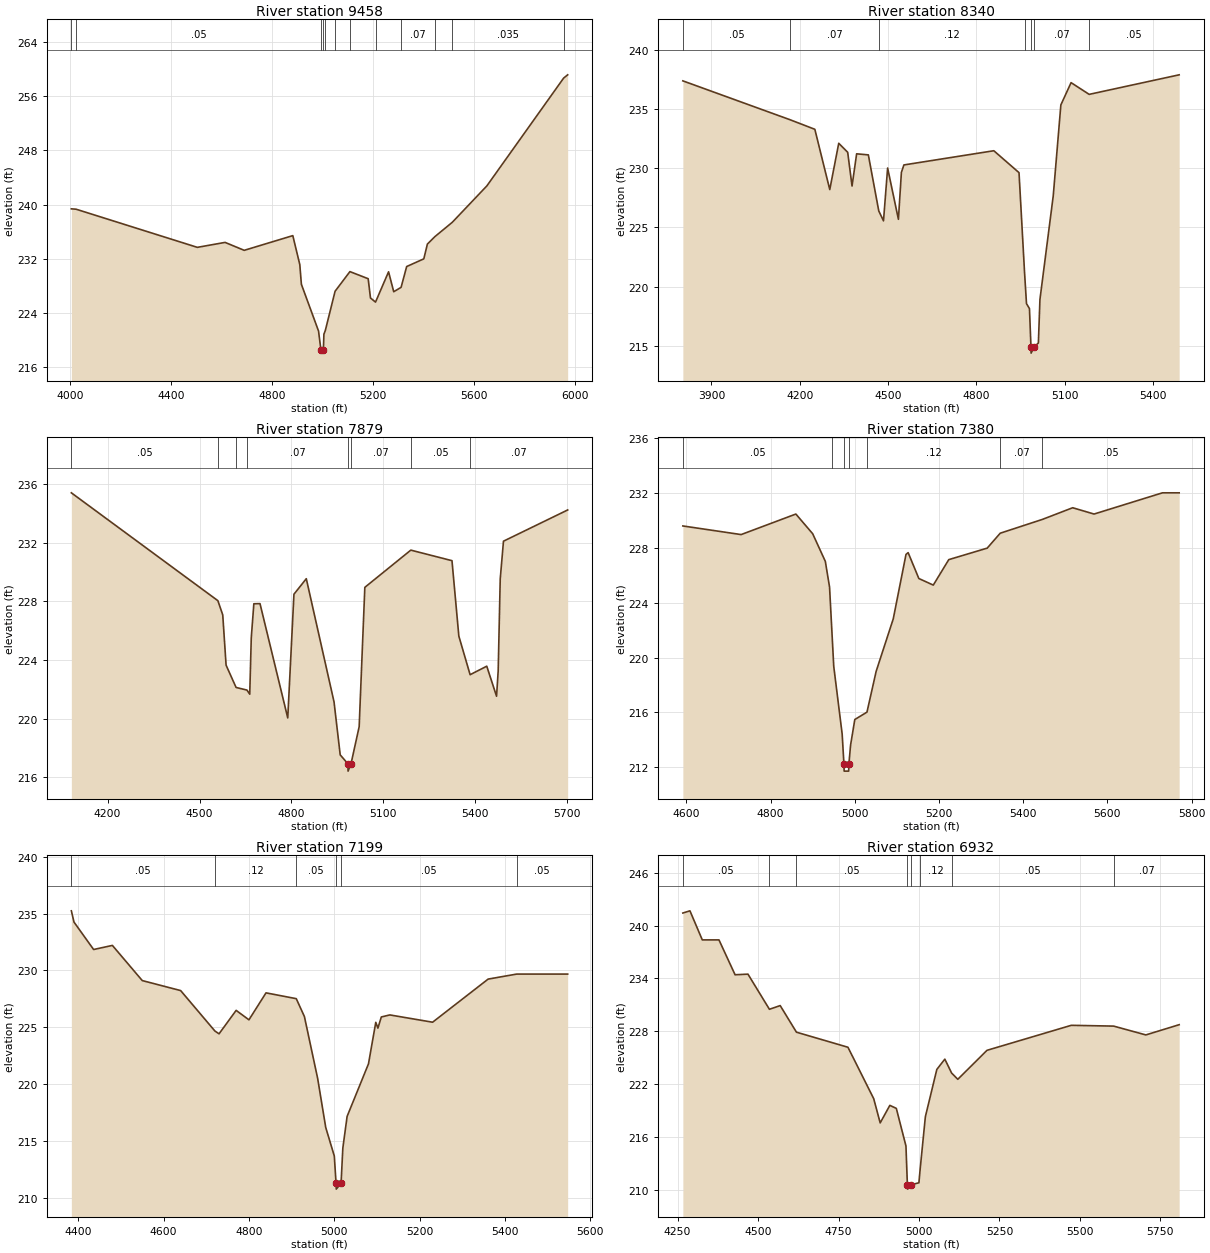
Type RM Length L Ch R = 1 ,9458    ,1118,1118,1118
BEGIN DESCRIPTION:
Mapping XS 0696cbdd
END DESCRIPTION:
XS GIS Cut Line= 3
      2473080.07     13489525.28      2473952.46     13489060.87
      2474907.31     13488843.86
#Sta/Elev= 30
  4004.7  239.37  4023.3  239.32  4504.2  233.69  4614.1  234.42    4690  233.25
  4882.6  235.42  4910.3  231.15  4916.6  228.24  4984.6  221.34  4993.9  218.58
  4994.4  218.08  5003.8  218.58  5005.9  220.88  5011.4  221.41  5050.2  227.21
    5109  230.11  5181.4  229.06  5190.5  226.22  5210.5  225.61  5262.2  230.08
  5282.7  227.14  5311.9  227.79    5334  230.86  5401.9  231.99  5416.1  234.17
  5445.5  235.26  5514.9  237.39  5651.9  242.76  5956.3  258.67  5972.2  259.15
#Mann= 12 ,-1 , 0
  4004.7    .035       0  4023.3     .05       0  4993.9     .05       0
  5003.8     .05       0  5011.4     .07       0  5050.2     .12       0
    5109     .07       0  5210.5     .05       0  5311.9     .07       0
  5445.5     .05       0  5514.9    .035       0  5956.3     .07       0
Bank Sta=4993.9,5003.8
XS Rating Curve= 0 ,0
Exp/Cntr=0.3,0.1

Type RM Length L Ch R = 1 ,8340    ,461,461,461
BEGIN DESCRIPTION:
Mapping XS 703a8608
END DESCRIPTION:
XS GIS Cut Line= 4
      2473292.73      13489785.7      2474243.26     13489625.11
      2474612.18     13489677.19      2474961.86     13489690.14
#Sta/Elev= 30
  3802.9  237.38    4168  234.09  4251.4  233.29  4302.1   228.2  4332.6  232.11
    4363  231.35  4377.8   228.5  4393.4  231.22  4433.2  231.13  4468.6   226.4
  4484.7  225.56  4498.7  230.02  4535.4  225.69  4545.5  229.65    4554  230.28
  4859.6  231.48  4945.2  229.63    4964   221.2  4970.6  218.57  4980.7  218.15
  4985.8  214.89  4986.3  214.39  4995.8  214.89    5011  215.25  5016.3  218.92
  5061.5  227.67  5087.4  235.35  5122.1  237.23  5183.6  236.24  5489.4  237.89
#Mann= 7 ,-1 , 0
  3802.9     .05       0    4168     .07       0  4468.6     .12       0
    4964     .07       0  4985.8     .05       0  4995.8     .07       0
  5183.6     .05       0
Bank Sta=4985.8,4995.8
XS Rating Curve= 0 ,0
Exp/Cntr=0.3,0.1

Type RM Length L Ch R = 1 ,7879    ,499,499,499
BEGIN DESCRIPTION:
Mapping XS 55d56d97
END DESCRIPTION:
XS GIS Cut Line= 4
       2473563.4     13490198.24      2474493.04     13490088.87
      2474709.19     13490096.68      2475154.48      13490239.9
#Sta/Elev= 30
  4081.7   235.4    4560  228.04  4575.9  227.07  4586.8  223.64  4619.4  222.12
  4654.9  221.94    4664  221.66    4669   225.5  4677.4  227.83  4697.5  227.84
  4788.1  220.04  4808.3  228.48  4848.6  229.54  4939.2  221.13  4959.3  217.52
  4984.5  216.91    4985  216.41  4994.6  216.91  5021.2  219.44  5039.7  228.95
  5189.8  231.49  5324.2  230.77  5346.6  225.62  5383.4  222.99  5437.7  223.57
  5469.7  221.52    5475  223.25  5481.7  229.53  5492.3   232.1  5701.8  234.23
#Mann= 8 ,-1 , 0
  4081.7     .05       0    4560     .07       0  4619.4     .12       0
  4654.9     .07       0  4984.5     .05       0  4994.6     .07       0
  5189.8     .05       0  5383.4     .07       0
Bank Sta=4984.5,4994.6
XS Rating Curve= 0 ,0
Exp/Cntr=0.3,0.1

Type RM Length L Ch R = 1 ,7380    ,181,181,181
BEGIN DESCRIPTION:
Mapping XS 0647fc77
END DESCRIPTION:
XS GIS Cut Line= 3
      2473866.57     13490500.21      2474283.28     13490500.21
      2475034.16       13490370.
#Sta/Elev= 30
  4591.6  229.61    4730  228.98    4860  230.48    4900  229.04    4930  227.02
    4940  225.15  4945.6   221.9    4950  219.35    4970   214.4  4974.2   212.2
  4974.7   211.7  4985.4   211.7  4985.9   212.2    4990  213.61    5000  215.47
  5028.9  216.01  5050.7  218.99  5091.3  222.82  5121.6  227.53  5126.7  227.66
  5152.1  225.77  5186.4  225.29  5223.2  227.15  5314.5  227.99  5345.4  229.08
  5445.7  230.09  5517.5  230.94  5568.3  230.48  5730.7  232.03  5770.4  232.03
#Mann= 7 ,-1 , 0
  4591.6     .05       0  4945.6     .07       0  4974.2     .05       0
  4985.9     .07       0  5028.9     .12       0  5345.4     .07       0
  5445.7     .05       0
Bank Sta=4974.2,4985.9
XS Rating Curve= 0 ,0
Exp/Cntr=0.3,0.1

Type RM Length L Ch R = 1 ,7199    ,267,267,267
BEGIN DESCRIPTION:
Mapping XS 38ef11a5
END DESCRIPTION:
XS GIS Cut Line= 3
      2473608.84      13490681.2      2474186.14     13490668.18
      2474771.07     13490633.52
#Sta/Elev= 30
  4383.7  235.24  4389.9  234.25  4435.9  231.84  4479.9   232.2  4549.9  229.11
  4639.9  228.23  4720.1  224.68  4729.9  224.43    4770  226.49    4800  225.66
    4840  228.03  4910.9  227.52    4930  225.95  4961.1   220.5    4980   216.2
  5000.1  213.69  5004.2  211.28  5004.7  210.78  5015.9  211.28  5020.1  214.39
  5030.1  217.17  5080.2  221.79  5097.3  225.44  5102.3  224.93  5110.3  225.91
  5130.3  226.09  5230.5  225.45  5360.7  229.24  5427.5  229.68  5547.1  229.68
#Mann= 6 ,-1 , 0
  4383.7     .05       0  4720.1     .12       0  4910.9     .05       0
  5004.2     .05       0  5015.9     .05       0  5427.5     .05       0
Bank Sta=5004.2,5015.9
XS Rating Curve= 0 ,0
Exp/Cntr=0.3,0.1

Type RM Length L Ch R = 1 ,6932    ,292,292,292
BEGIN DESCRIPTION:
Mapping XS ecb75a25
END DESCRIPTION:
XS GIS Cut Line= 3
      2473443.06     13490964.02      2474158.29     13490918.88
      2474977.77     13490818.18
#Sta/Elev= 30
  4266.3  241.43  4288.3  241.68  4326.7  238.38  4378.5  238.38  4428.6  234.42
  4468.6  234.49  4535.3   230.5  4568.8  230.92  4619.3   227.9  4779.3  226.19
  4859.4  220.35  4879.5   217.6  4909.5  219.59  4929.6  219.25  4959.6  214.98
    4964  210.58  4964.5  210.08  4975.8  210.58  4999.8   210.8  5003.8  212.38
  5019.9   218.3  5055.5  223.67  5080.4  224.84  5101.5  223.26  5120.7  222.55
  5211.4  225.84  5473.3  228.68    5605  228.59  5705.1  227.59  5808.6  228.75
#Mann= 8 ,-1 , 0
  4266.3     .05       0  4535.3     .07       0  4619.3     .05       0
    4964     .05       0  4975.8     .05       0  5003.8     .12       0
  5101.5     .05       0    5605     .07       0
Bank Sta=4964,4975.8
XS Rating Curve= 0 ,0
Exp/Cntr=0.3,0.1

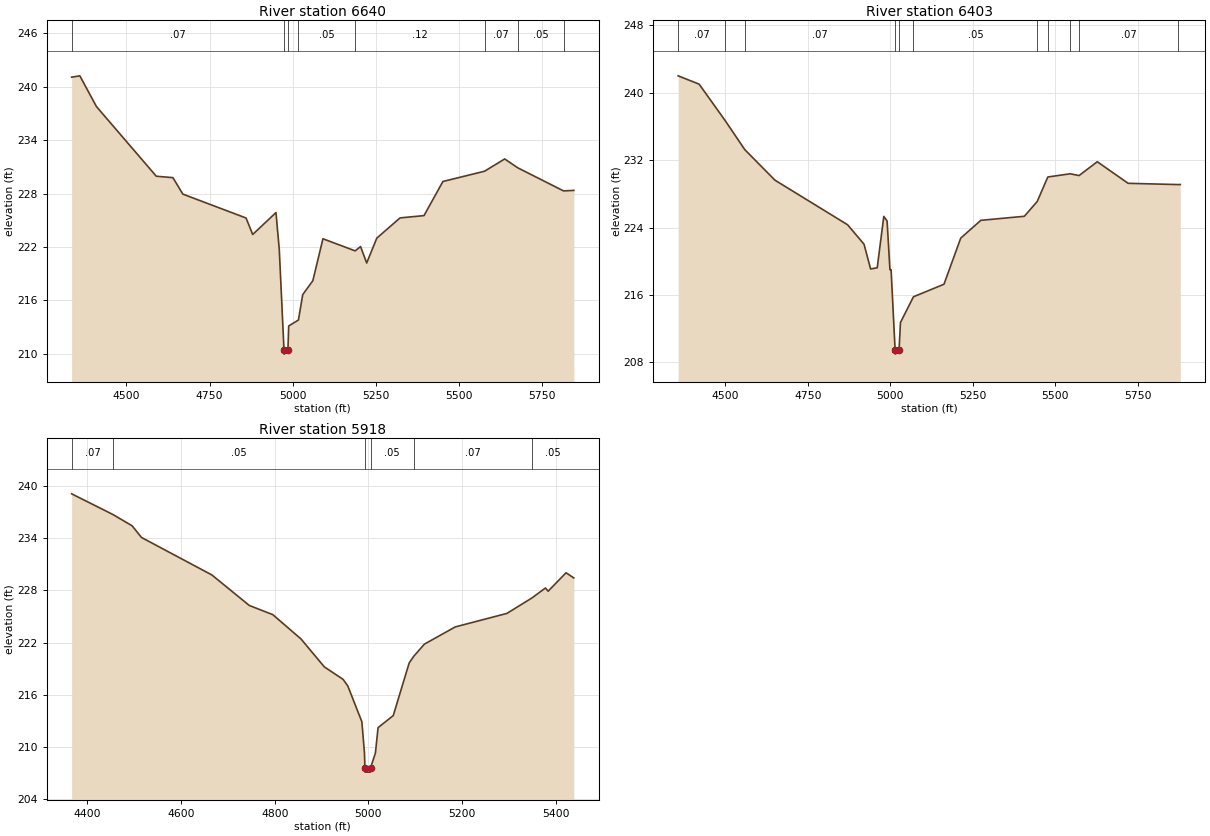
Type RM Length L Ch R = 1 ,6640    ,237,237,237
BEGIN DESCRIPTION:
Mapping XS 1e9c8c35
END DESCRIPTION:
XS GIS Cut Line= 3
      2473460.42     13491186.24      2474116.62     13491193.19
      2474960.18      13491057.8
#Sta/Elev= 30
  4335.3  241.06  4359.9  241.21  4409.9  237.76  4589.9  229.94  4639.9  229.78
  4669.9  227.93  4859.9  225.25  4879.9   223.4  4949.9  225.86  4959.9   221.7
    4974  210.47  4974.5  209.97  4985.9  210.47  4988.2  213.13  5017.5   213.8
  5030.4  216.65  5060.8  218.21  5091.2  222.92  5188.1  221.56  5204.3  222.05
  5222.8   220.2  5253.2  222.99  5323.1  225.26  5395.2  225.52  5452.1  229.35
  5577.3   230.5  5637.9  231.88  5677.4  230.88    5815  228.29  5845.9  228.35
#Mann= 8 ,-1 , 0
  4335.3     .07       0    4974     .05       0  4985.9     .07       0
  5017.5     .05       0  5188.1     .12       0  5577.3     .07       0
  5677.4     .05       0    5815     .07       0
Bank Sta=4974,4985.9
XS Rating Curve= 0 ,0
Exp/Cntr=0.3,0.1

Type RM Length L Ch R = 1 ,6403    ,485,485,485
BEGIN DESCRIPTION:
Mapping XS 32dd9d15
END DESCRIPTION:
XS GIS Cut Line= 3
      2473481.16      13491429.3      2474127.04      13491429.3
      2474990.78     13491276.67
#Sta/Elev= 30
  4356.6     242  4420.4  241.01  4500.2  236.64  4558.7  233.25  4650.4  229.62
  4870.4  224.34  4920.4  222.03  4940.4  219.09  4960.4  219.23  4980.4  225.33
  4990.4  224.77    4999     219  5002.5     219  5014.7  209.49  5015.2  208.99
  5026.7  209.49  5030.9  212.74  5070.3  215.79  5162.9  217.28  5213.7  222.75
  5274.6  224.86  5406.6  225.34  5445.6  227.09  5477.8     230  5545.8  230.38
  5572.6  230.17  5627.8  231.81  5721.4  229.25  5873.6   229.1  5879.6  229.11
#Mann= 11 ,-1 , 0
  4356.6     .07       0  4500.2     .05       0  4558.7     .07       0
  5014.7     .05       0  5026.7     .07       0  5070.3     .05       0
  5445.6     .12       0  5477.8     .05       0  5545.8     .12       0
  5572.6     .07       0  5873.6     .12       0
Bank Sta=5014.7,5026.7
XS Rating Curve= 0 ,0
Exp/Cntr=0.3,0.1

Type RM Length L Ch R = 1 ,5918    ,233,233,233
BEGIN DESCRIPTION:
Mapping XS f400553e
END DESCRIPTION:
XS GIS Cut Line= 3
      2473706.04     13491871.74      2474331.02     13491841.36
      2474726.02       13491633.
#Sta/Elev= 30
  4366.4  239.09  4454.7  236.71  4495.5  235.42  4515.5  234.08  4665.7  229.78
  4745.8  226.27  4795.9  225.22  4855.9  222.44    4906  219.22    4946  217.79
  4956.1  217.03  4986.1  212.92  4991.6  209.37  4992.6  207.64  4993.1  207.14
  5004.2  207.14  5004.7  207.64    5015  209.33  5020.7  212.25  5053.1  213.63
  5087.1  219.67  5097.2  220.46  5119.5  221.83  5185.5  223.81  5295.7  225.36
  5348.8  227.12  5378.1  228.28  5383.8  227.91  5422.1  230.03  5438.7  229.43
#Mann= 6 ,-1 , 0
  4366.4     .07       0  4454.7     .05       0  4992.6     .05       0
  5004.7     .05       0  5097.2     .07       0  5348.8     .05       0
Bank Sta=4992.6,5004.7
XS Rating Curve= 0 ,0
Exp/Cntr=0.3,0.1