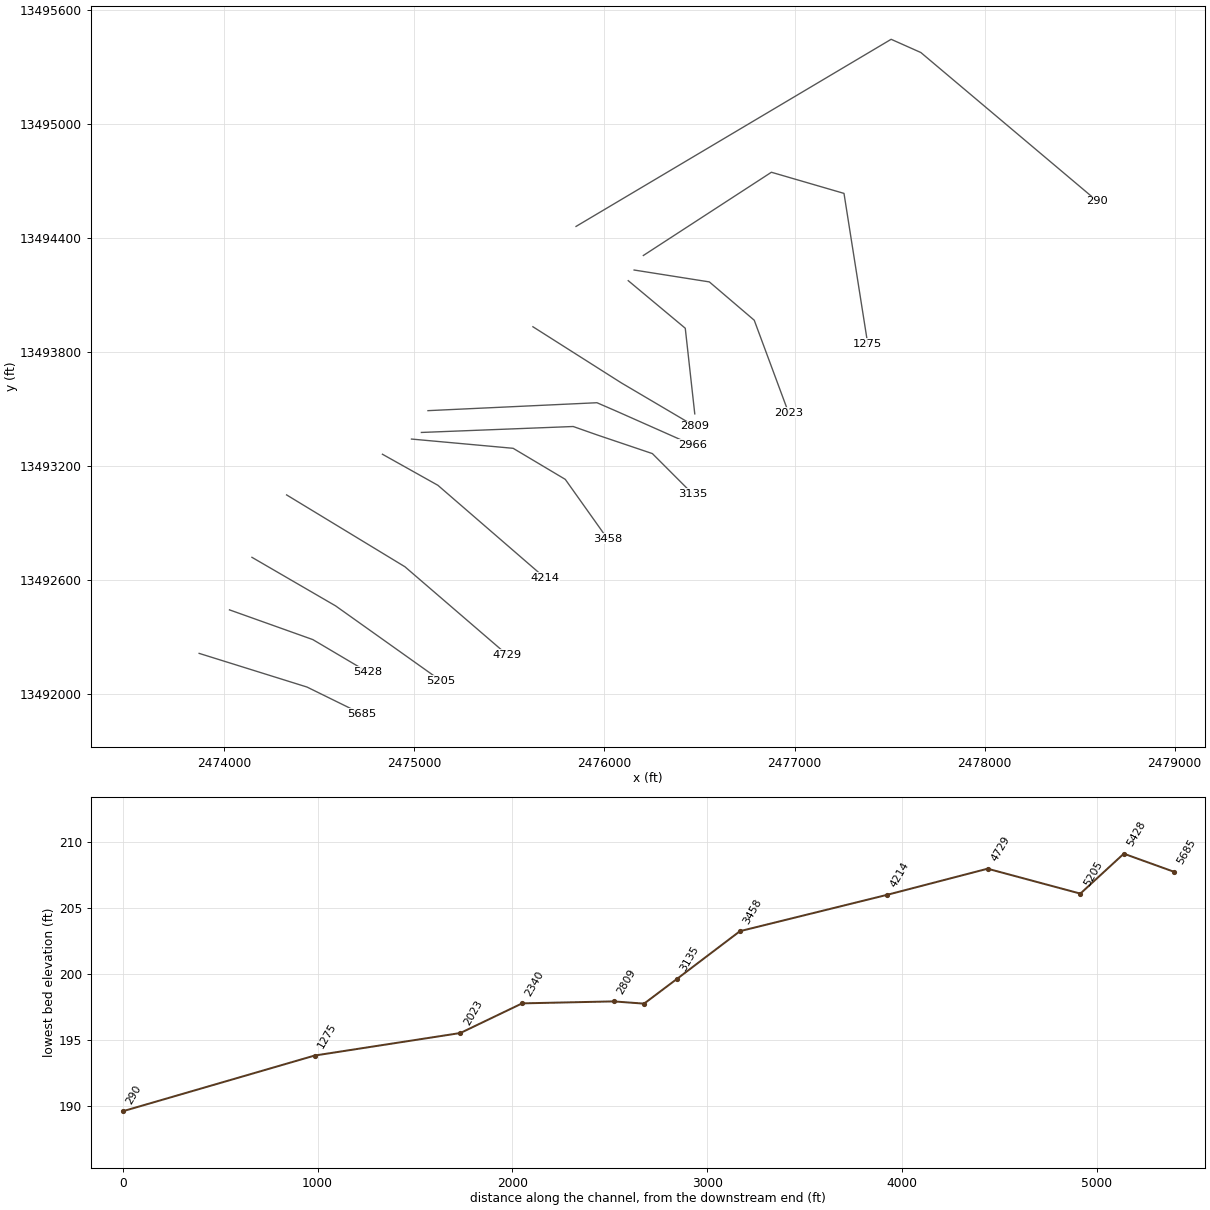
HEC-RAS study HOG CREEK.prj: HOG CREEK Base Level Engineering

--- HOG CREEK.g01 (geometry) --- (continued)

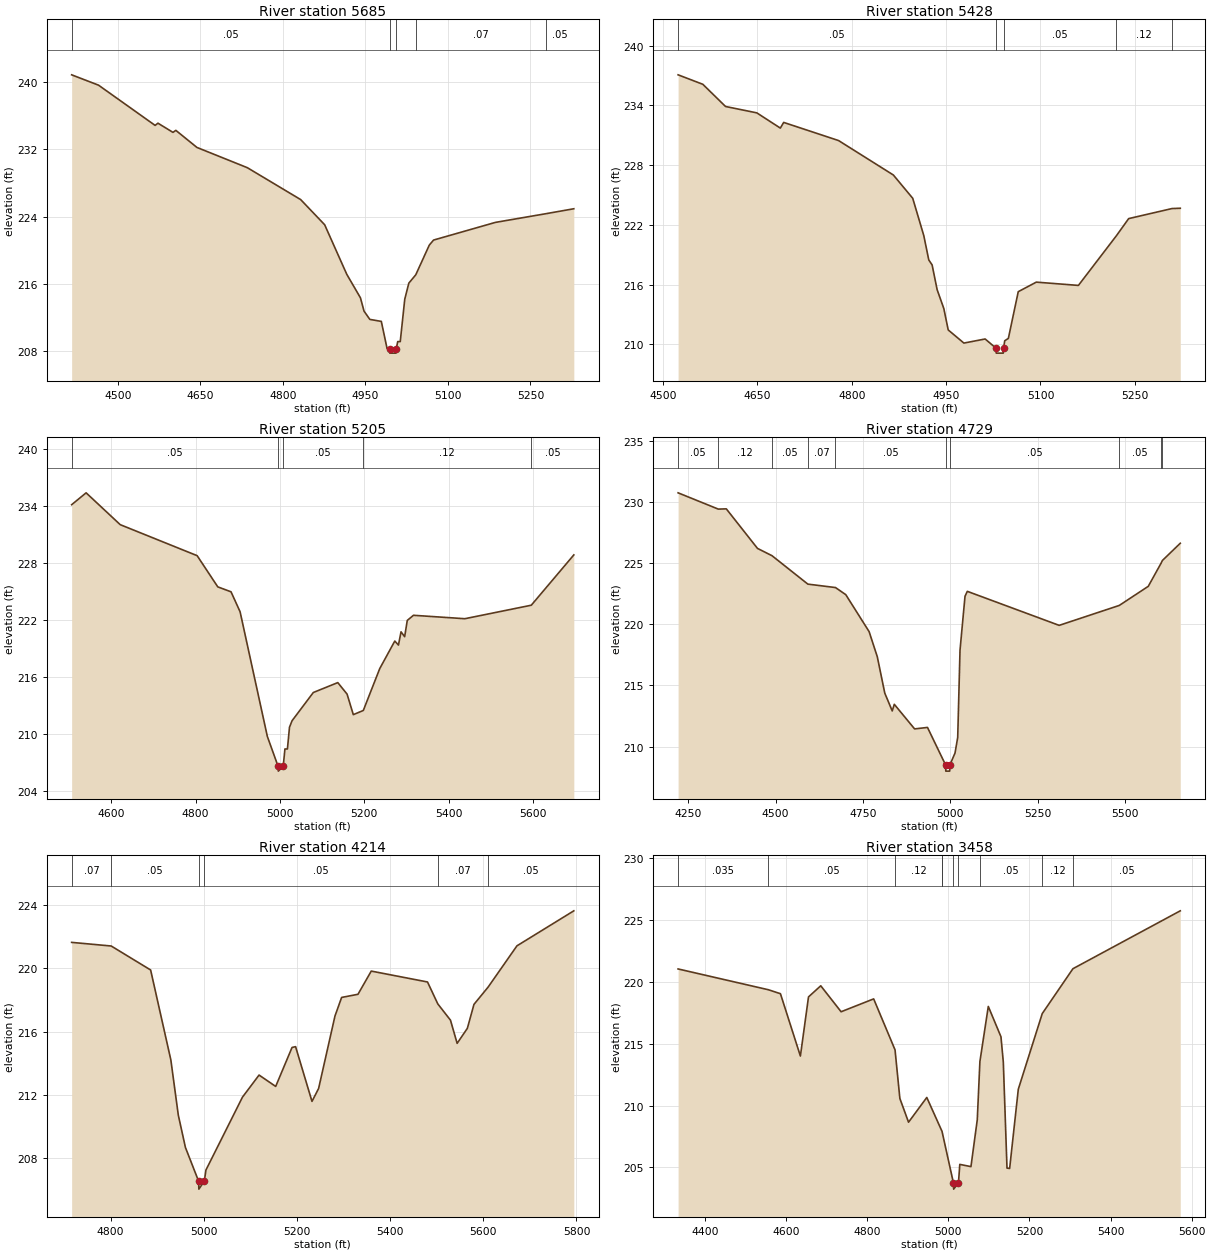
Type RM Length L Ch R = 1 ,5685    ,257,257,257
BEGIN DESCRIPTION:
Mapping XS c62afcd6
END DESCRIPTION:
XS GIS Cut Line= 3
      2473867.59     13492215.92      2474435.27     13492038.84
      2474720.86     13491898.64
#Sta/Elev= 30
    4416  240.84  4464.9  239.61  4567.7  234.83  4572.9  235.09  4600.2     234
  4605.4  234.24  4643.7  232.21  4735.4   229.8  4832.3  226.01  4875.9  223.02
  4916.1  217.13  4940.9  214.34  4947.5  212.75    4958  211.77  4978.9  211.53
  4989.4  208.29  4993.9  208.26  4994.4  207.76  5005.5  207.76    5006  208.26
  5008.7  209.13  5013.3  209.13  5021.5  214.17  5028.9  216.08  5041.5  217.07
  5066.1   220.6  5073.9   221.2  5186.3   223.3  5277.8  224.33  5328.8  224.92
#Mann= 5 ,-1 , 0
    4416     .05       0  4993.9     .05       0    5006     .05       0
  5041.5     .07       0  5277.8     .05       0
Bank Sta=4993.9,5006
XS Rating Curve= 0 ,0
Exp/Cntr=0.3,0.1

Type RM Length L Ch R = 1 ,5428    ,223,223,223
BEGIN DESCRIPTION:
Mapping XS 2c44b113
END DESCRIPTION:
XS GIS Cut Line= 3
      2474027.18     13492444.66      2474465.57     13492288.41
        2474752.     13492119.15
#Sta/Elev= 30
  4524.1  237.08  4563.4  236.13  4599.5   233.9  4649.2  233.26  4686.6  231.73
  4691.9   232.3  4779.1  230.48  4866.2  227.02    4897  224.68  4914.6  220.93
  4922.5  218.49  4927.8  217.99  4935.8   215.5  4946.4  213.61  4953.4  211.46
  4978.3  210.14  5012.1  210.55  5029.3  209.63  5029.8  209.13  5040.9  209.13
  5041.4  209.63  5043.2  210.37    5049  210.61  5064.7   215.3  5093.4  216.26
  5160.3  215.93  5220.7  220.92  5240.2  222.64  5309.1  223.65  5322.2  223.68
#Mann= 5 ,-1 , 0
  4524.1     .05       0  5029.3     .05       0  5041.4     .05       0
  5220.7     .12       0  5309.1     .07       0
Bank Sta=5029.3,5041.4
XS Rating Curve= 0 ,0
Exp/Cntr=0.3,0.1

Type RM Length L Ch R = 1 ,5205    ,476,476,476
BEGIN DESCRIPTION:
Mapping XS 33723f8c
END DESCRIPTION:
XS GIS Cut Line= 3
      2474145.34     13492720.79      2474585.44     13492465.58
      2475141.18     13492070.85
#Sta/Elev= 30
  4506.3  234.12  4540.6  235.37  4621.5  232.02  4803.8  228.76  4852.7  225.48
  4884.1  224.96  4905.6  222.86  4970.2  209.75  4995.7   206.6  4996.2   206.1
  5007.8   206.6  5011.9  208.43  5017.8  208.43  5022.7  210.72  5028.8   211.4
  5079.2  214.37  5137.2  215.41  5159.2   214.2    5174  212.04  5197.7  212.48
  5236.7  216.89  5272.3  219.78    5281  219.36  5287.1  220.75  5295.7  220.24
  5301.9  221.95  5316.6  222.49  5438.4  222.13  5595.9  223.55  5696.7  228.84
#Mann= 5 ,-1 , 0
  4506.3     .05       0  4995.7     .05       0  5007.8     .05       0
  5197.7     .12       0  5595.9     .05       0
Bank Sta=4995.7,5007.8
XS Rating Curve= 0 ,0
Exp/Cntr=0.3,0.1

Type RM Length L Ch R = 1 ,4729    ,515,515,515
BEGIN DESCRIPTION:
Mapping XS ce51daf6
END DESCRIPTION:
XS GIS Cut Line= 3
      2474327.61     13493048.92      2474950.03     13492671.31
      2475487.83     13492208.85
#Sta/Elev= 30
  4220.9  230.73  4335.9   229.4  4358.9  229.42  4448.1  226.19  4489.8  225.59
  4592.3  223.27  4671.4  222.99  4700.8  222.41  4767.6  219.39    4791  217.34
  4812.5  214.36  4833.8  212.91  4839.7  213.45  4897.8  211.44  4934.7  211.56
  4986.6  208.49  4987.1  207.99  4998.2  207.99  4998.7  208.49  5013.5  209.47
  5021.2  210.74  5027.8  217.87  5042.1  222.28  5048.7  222.68  5311.6   219.9
  5483.7  221.53  5566.6  223.09  5603.5  224.99    5607   225.2  5658.2  226.61
#Mann= 10 ,-1 , 0
  4220.9     .05       0  4335.9     .12       0  4489.8     .05       0
  4592.3     .07       0  4671.4     .05       0  4986.6     .05       0
  4998.7     .05       0  5483.7     .05       0  5603.5     .12       0
    5607     .05       0
Bank Sta=4986.6,4998.7
XS Rating Curve= 0 ,0
Exp/Cntr=0.3,0.1

Type RM Length L Ch R = 1 ,4214    ,756,756,756
BEGIN DESCRIPTION:
Mapping XS e71914c6
END DESCRIPTION:
XS GIS Cut Line= 3
      2474831.86     13493262.65      2475123.56     13493099.44
      2475686.06     13492613.33
#Sta/Elev= 30
  4716.6  221.65  4801.5  221.42  4886.1   219.9  4929.5   214.2  4945.5   210.7
  4960.8  208.65  4989.1  206.51  4989.6  206.01  5001.3  206.51  5004.8  207.22
  5083.2  211.84  5118.8  213.24  5154.5  212.52  5189.6  214.99  5197.2  215.04
  5232.4  211.57  5246.6  212.39  5281.7  216.98    5296  218.16  5331.1  218.36
  5359.6  219.83  5480.3  219.14  5502.4  217.75  5529.6  216.72  5543.9  215.25
  5565.8   216.2    5580  217.72  5610.5  218.82  5672.2  221.43  5794.3  223.65
#Mann= 6 ,-1 , 0
  4716.6     .07       0  4801.5     .05       0  4989.1     .05       0
  5001.3     .05       0  5502.4     .07       0  5610.5     .05       0
Bank Sta=4989.1,5001.3
XS Rating Curve= 0 ,0
Exp/Cntr=0.3,0.1

Type RM Length L Ch R = 1 ,3458    ,323,323,323
BEGIN DESCRIPTION:
Mapping XS 8b12ead7
END DESCRIPTION:
XS GIS Cut Line= 4
      2474984.68     13493342.49       2475519.4     13493293.88
       2475793.7     13493130.69      2476015.25     13492819.13
#Sta/Elev= 30
  4333.6  221.05  4556.2  219.37    4586  219.05  4635.2  214.01  4655.2  218.79
  4685.4  219.69  4735.6  217.59  4815.9  218.63  4868.6  214.51  4880.5  210.58
  4901.9  208.66  4946.9  210.66  4984.6  207.91  4984.8  207.87  5012.6  203.75
  5013.1  203.25    5025  203.75  5028.3  205.25  5055.8  205.07  5071.4  208.86
  5077.9  213.57  5098.6  218.02  5129.8  215.57  5135.6  213.53  5144.7  204.95
  5151.2  204.92  5172.6  211.33  5231.6  217.44  5307.3  221.07    5572  225.75
#Mann= 10 ,-1 , 0
  4333.6    .035       0  4556.2     .05       0  4868.6     .12       0
  4984.6     .05       0  4984.8     .12       0  5012.6     .05       0
    5025     .12       0  5077.9     .05       0  5231.6     .12       0
  5307.3     .05       0
Bank Sta=5012.6,5025
XS Rating Curve= 0 ,0
Exp/Cntr=0.3,0.1

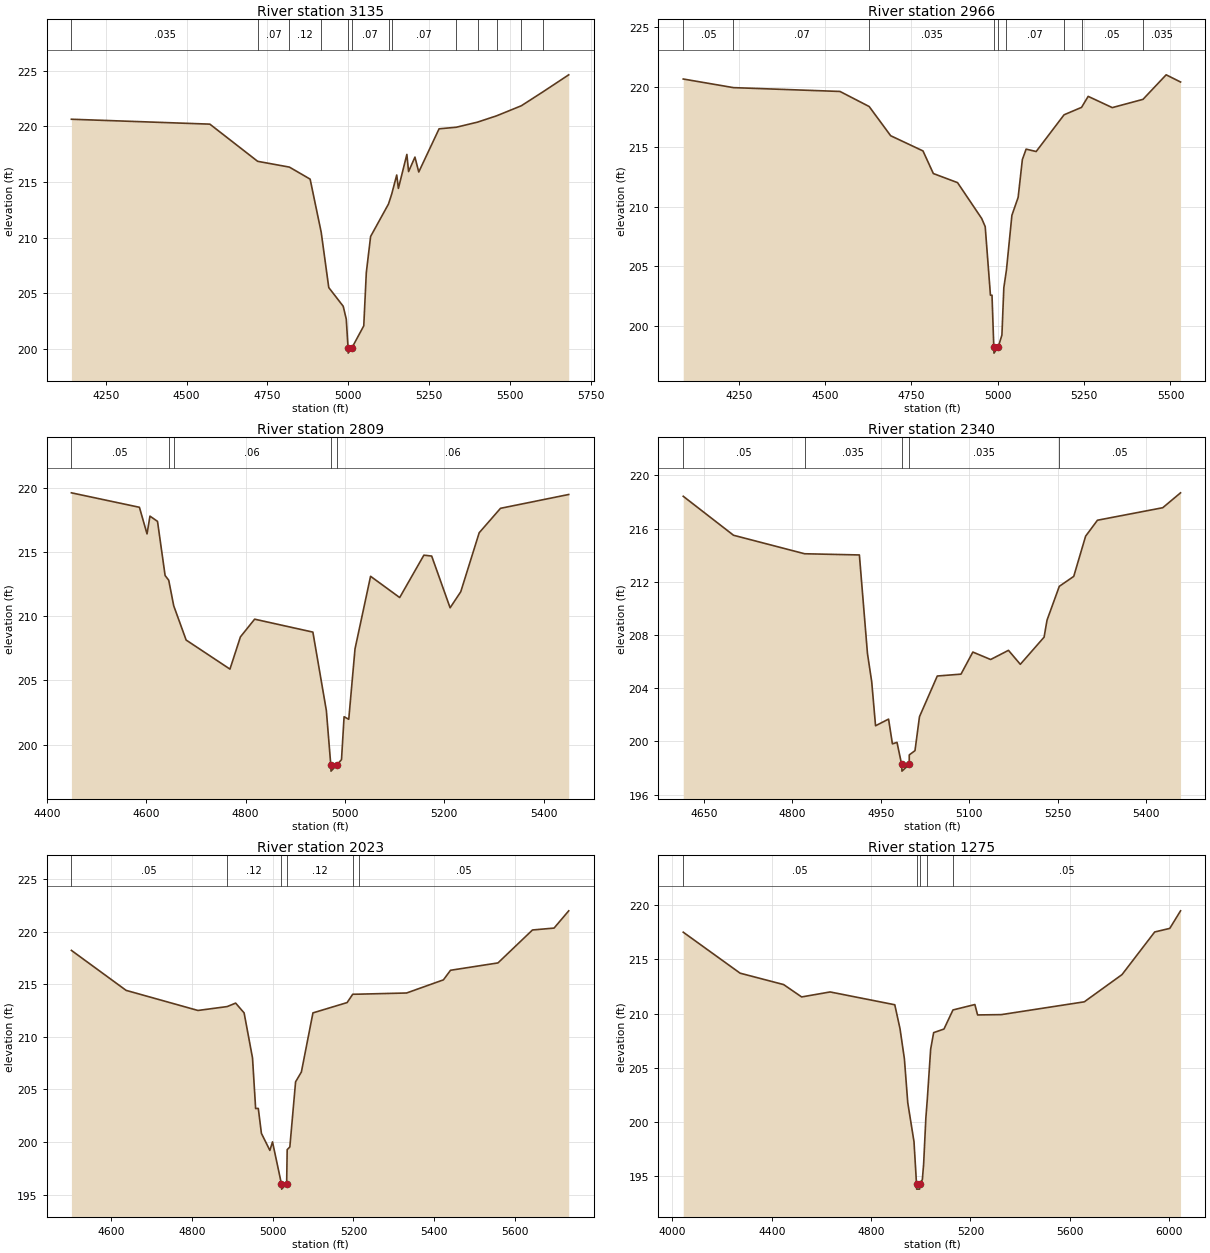
Type RM Length L Ch R = 1 ,3135    ,169,169,169
BEGIN DESCRIPTION:
Mapping XS 31a0fff5
END DESCRIPTION:
XS GIS Cut Line= 5
      2475036.79     13493377.22      2475835.37     13493408.47
      2475963.84     13493363.33      2476252.04      13493266.1
      2476463.87     13493054.27
#Sta/Elev= 30
  4143.3  220.64  4571.8   220.2  4719.7  216.86    4818  216.34  4882.1  215.26
  4916.3   210.5  4939.8  205.52  4984.5  203.84    4994  202.68  4999.4  200.13
  4999.9  199.63  5011.9  200.13  5048.1  202.08    5056  206.87  5069.3  210.11
  5124.7  213.03  5134.6  213.92  5150.1  215.63  5155.3  214.43  5181.5  217.48
  5186.8  215.94  5206.5  217.24  5218.3   215.9  5281.2  219.78  5334.2  219.92
  5400.1  220.38  5459.5  220.95  5535.7  221.85  5602.6   223.1  5682.4  224.63
#Mann= 13 ,-1 , 0
  4143.3    .035       0  4719.7     .07       0    4818     .12       0
  4916.3     .07       0  4999.4     .05       0  5011.9     .07       0
  5124.7    .035       0  5134.6     .07       0  5334.2    .035       0
  5400.1     .07       0  5459.5    .035       0  5535.7     .07       0
  5602.6    .035       0
Bank Sta=4999.4,5011.9
XS Rating Curve= 0 ,0
Exp/Cntr=0.3,0.1

Type RM Length L Ch R = 1 ,2966    ,157,157,157
BEGIN DESCRIPTION:
Mapping XS 0df79571
END DESCRIPTION:
XS GIS Cut Line= 4
      2475071.51      13493491.8      2475960.37     13493533.47
      2476064.54     13493488.33      2476463.87     13493311.23
#Sta/Elev= 30
    4089  220.66  4234.4  219.94    4543  219.62  4627.5  218.36  4689.7  215.92
  4783.3  214.65  4813.3  212.76  4883.4     212  4953.4     209  4963.5  208.32
  4978.7  202.59  4983.2  202.59  4988.4  198.25  4988.9  197.75  5001.1  198.25
  5011.9  199.26  5017.4  203.21    5025   204.7  5040.8  209.27  5058.9  210.77
  5071.1  213.93    5082   214.8  5111.1   214.6  5191.9  217.67  5242.5  218.29
  5261.7  219.21  5331.5  218.27  5420.4  218.96  5487.5  221.01  5529.2  220.41
#Mann= 9 ,-1 , 0
    4089     .05       0  4234.4     .07       0  4627.5    .035       0
  4988.4    .035       0  5001.1    .035       0    5025     .07       0
  5191.9    .035       0  5242.5     .05       0  5420.4    .035       0
Bank Sta=4988.4,5001.1
XS Rating Curve= 0 ,0
Exp/Cntr=0.3,0.1

Type RM Length L Ch R = 1 ,2809    ,469,469,469
BEGIN DESCRIPTION:
Mapping XS 1554ce07
END DESCRIPTION:
XS GIS Cut Line= 3
      2475623.54     13493932.79      2476088.84     13493637.63
      2476476.43     13493409.23
#Sta/Elev= 30
  4449.5  219.66  4586.4  218.53  4601.7  216.45  4607.6  217.84  4622.8  217.43
  4638.1   213.2  4645.4  212.83  4655.4  210.84  4680.4  208.16  4768.6  205.89
  4789.7  208.41  4818.3  209.79  4935.5  208.78  4962.6  202.66  4971.5  198.42
    4972  197.92  4984.2  198.42  4993.1  198.82  4998.3  202.17  5007.7  201.97
  5020.3  207.47  5051.6  213.14  5110.2  211.48  5158.9  214.79  5174.6  214.72
  5211.7  210.68  5233.1  211.93  5270.2  216.54  5313.1  218.45  5450.4  219.53
#Mann= 5 ,-1 , 0
  4449.5     .05       0  4645.4     .12       0  4655.4     .06       0
  4971.5     .05       0  4984.2     .06       0
Bank Sta=4971.5,4984.2
XS Rating Curve= 0 ,0
Exp/Cntr=0.3,0.1

Type RM Length L Ch R = 1 ,2340    ,317,317,317
BEGIN DESCRIPTION:
HOG CREEK 2.0
END DESCRIPTION:
XS GIS Cut Line= 3
      2476125.01     13494174.99        2476425.       13493925.
        2476475.     13493474.97
#Sta/Elev= 30
  4614.8  218.43  4700.1   215.5  4820.6  214.11  4913.5  214.02  4927.2  206.61
  4934.4  204.49  4940.9  201.18    4963  201.68  4969.5  199.82  4977.3  199.93
  4985.2  198.27  4985.7  197.77    4998  198.27  4998.1  198.99  5007.8  199.31
  5015.4  201.86  5045.6  204.92  5085.8  205.06  5105.9  206.72  5136.1  206.16
  5166.3  206.85  5186.4   205.8  5226.7  207.84  5231.7  209.12  5252.5  211.66
    5277  212.41  5297.1  215.43  5317.2  216.63  5427.9  217.57  5458.1  218.69
#Mann= 5 ,-1 , 0
  4614.8     .05       0  4820.6    .035       0  4985.2    .035       0
    4998    .035       0  5252.5     .05       0
Bank Sta=4985.2,4998
XS Rating Curve= 0 ,0
Exp/Cntr=0.3,0.1

Type RM Length L Ch R = 1 ,2023    ,748,748,748
BEGIN DESCRIPTION:
Mapping XS ed5186a8
END DESCRIPTION:
XS GIS Cut Line= 4
      2476155.95     13494231.04      2476551.75     13494168.55
      2476787.86     13493967.16      2476968.42     13493481.04
#Sta/Elev= 30
  4502.6  218.21  4637.9  214.41  4815.5   212.5  4887.8  212.87  4908.7   213.2
  4929.6  212.27  4950.4  207.99  4958.1  203.18  4964.7  203.19  4972.4  200.82
  4993.3   199.2  4999.8  200.01  5021.9  196.02  5022.4  195.52  5034.8  196.02
  5036.1  199.27  5042.7  199.53  5056.9  205.72  5071.2  206.65  5099.8  212.27
  5184.3  213.25  5198.1  214.04  5213.8  214.05  5331.3  214.16  5422.4  215.41
    5440  216.32  5557.3  217.02  5642.6  220.15    5696  220.33  5732.2  221.97
#Mann= 6 ,-1 , 0
  4502.6     .05       0  4887.8     .12       0  5021.9     .05       0
  5034.8     .12       0  5198.1    .035       0  5213.8     .05       0
Bank Sta=5021.9,5034.8
XS Rating Curve= 0 ,0
Exp/Cntr=0.3,0.1

Type RM Length L Ch R = 1 ,1275    ,985,985,985
BEGIN DESCRIPTION:
Mapping XS 60211ccd
END DESCRIPTION:
XS GIS Cut Line= 4
      2476204.51     13494307.42      2476878.14     13494744.94
      2477260.08     13494633.82      2477385.08     13493842.15
#Sta/Elev= 30
  4043.7   217.5  4272.8  213.72    4448  212.67  4520.5  211.53  4635.2  211.99
  4895.5  210.81  4916.6   208.6  4934.2  205.83  4947.8  201.78  4972.9  198.18
    4983  194.31  4983.5  193.81  4995.4  193.81  4995.9  194.31  5006.5  194.68
  5011.7  196.12  5020.7  200.39  5026.5   202.1    5040  206.72    5052  208.24
  5093.6  208.57  5129.8  210.33    5218  210.83    5229  209.87  5324.5   209.9
  5658.6  211.08  5810.5  213.59  5942.1  217.52  6002.8  217.85  6046.2  219.47
#Mann= 5 ,-1 , 0
  4043.7     .05       0    4983     .05       0  4995.9     .05       0
  5026.5    .035       0  5129.8     .05       0
Bank Sta=4983,4995.9
XS Rating Curve= 0 ,0
Exp/Cntr=0.3,0.1

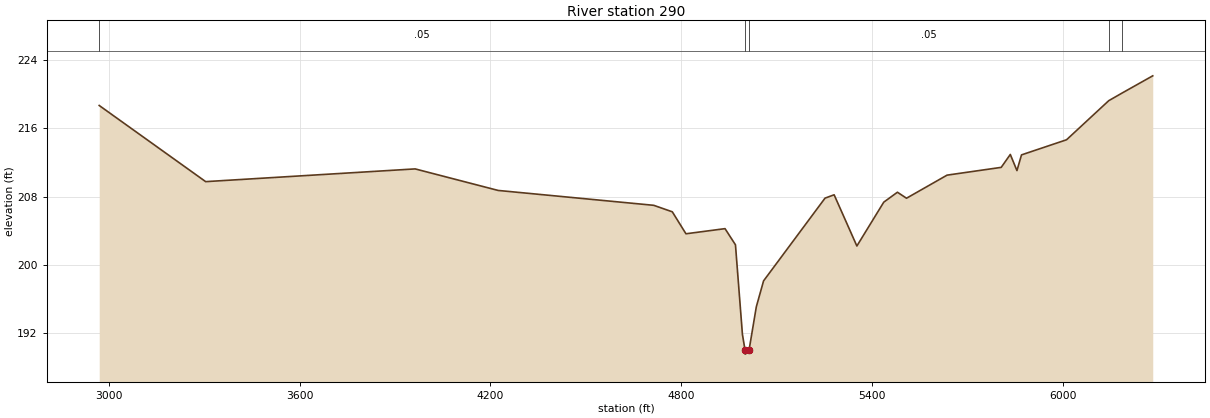
Type RM Length L Ch R = 1 ,290     ,0,0,0
BEGIN DESCRIPTION:
HOG CREEK 1.0
END DESCRIPTION:
XS GIS Cut Line= 4
      2475850.35     13494460.21       2477508.1     13495443.79
      2477664.35     13495374.34      2478593.38     13494592.19
#Sta/Elev= 30
  2969.7  218.67  3304.5  209.76  3963.2  211.25  4224.3  208.73  4713.5  206.99
  4771.9  206.23  4814.8  203.66  4937.7  204.26  4970.5  202.37  4992.4  191.89
  5000.5  190.08    5001  189.58  5013.4  190.08  5036.1  195.12  5058.9  198.15
  5252.2  207.83  5280.8  208.22  5352.3  202.23  5436.9  207.36  5479.8  208.52
  5508.4  207.82  5635.9  210.52  5806.2  211.43  5834.8  212.94  5855.7  211.05
    5870  212.89  6011.7  214.66  6144.3  219.23  6185.1   220.1  6282.7  222.14
#Mann= 5 ,-1 , 0
  2969.7     .05       0  5000.5     .05       0  5013.4     .05       0
  6144.3    .035       0  6185.1     .05       0
Bank Sta=5000.5,5013.4
XS Rating Curve= 0 ,0
Exp/Cntr=0.3,0.1

Chan Stop Cuts=-1
Use User Specified Reach Order=0
Composite Channel Slope=5