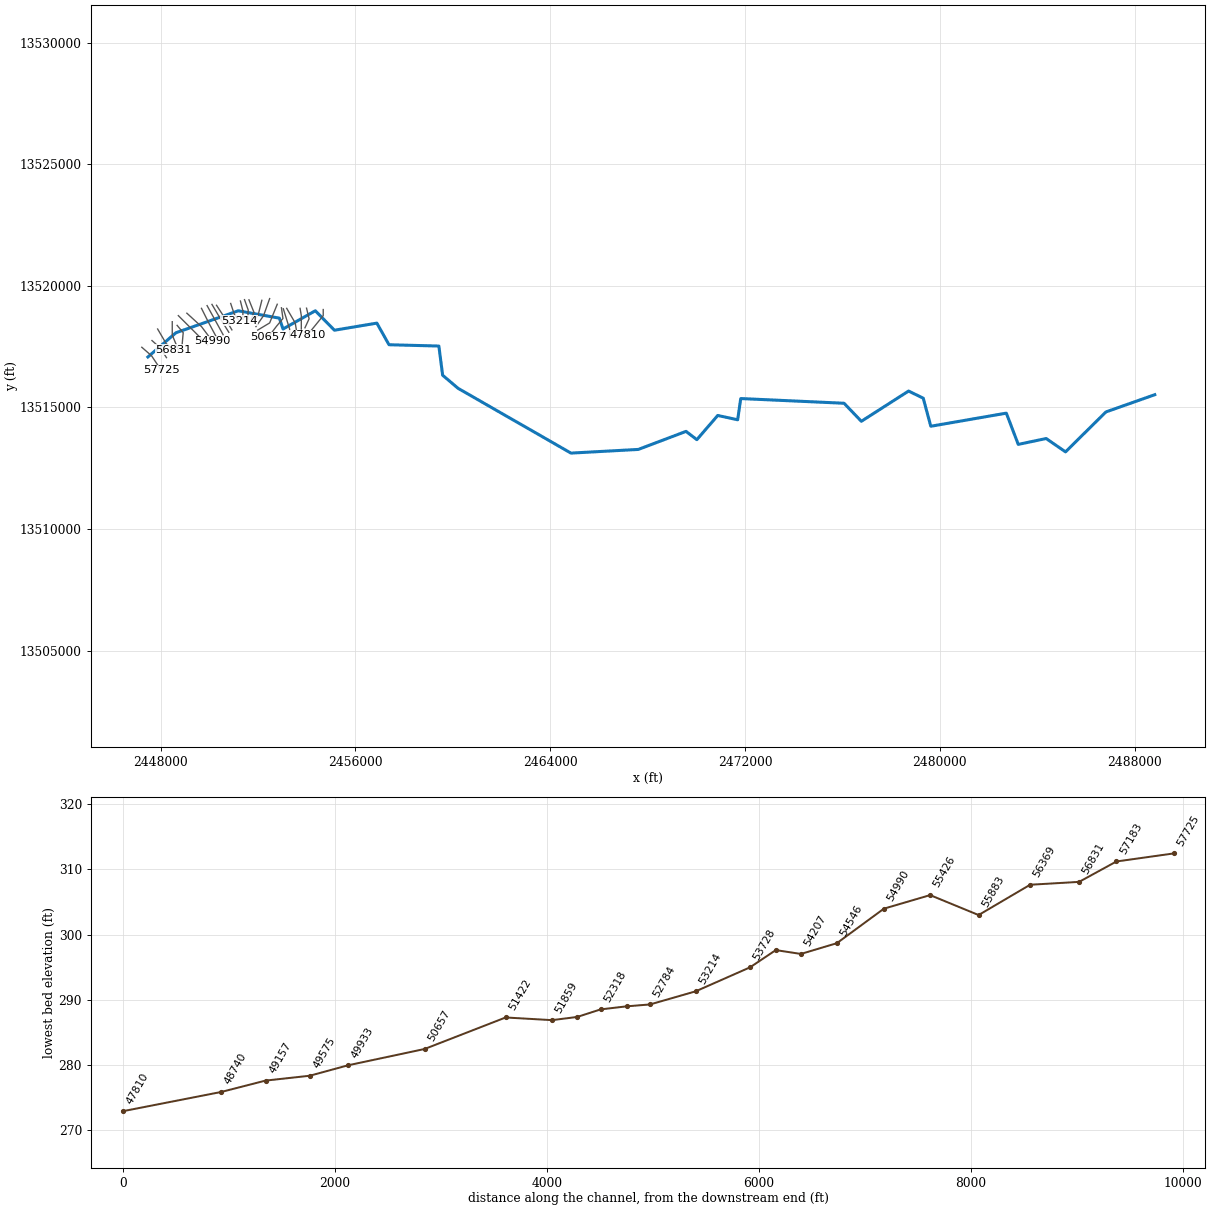
--- HOOSIER CREEK.prj (project) ---

Proj Title=HOOSIER CREEK Base Level Engineering
Current Plan=p01
Default Exp/Contr=0.3,0.1
English Units
Geom File=g01
Flow File=f01
Plan File=p01
Y Axis Title=Elevation
X Axis Title(PF)=Main Channel Distance
X Axis Title(XS)=Station
BEGIN DESCRIPTION:
HOOSIER CREEK
END DESCRIPTION:
DSS Export Rating Curves= 0
DSS Export Rating Curve Sorted= 0
DSS Export Volume Flow Curves= 0
DXF OffsetX= 0
DXF OffsetY= 0
DXF ScaleX= 1
DXF ScaleY= 10

--- HOOSIER CREEK.p01 (plan) ---

Plan Title=Multiple Run
Program Version=4.10
Short Identifier=Multiple
Geom File=g01
Flow File=f01
Subcritical Flow
K Sum by GR= 0
Std Step Tol= 0.01
Critical Tol= 0.01
Num of Std Step Trials= 20
Max Error Tol= 0.3
Flow Tol Ratio= 0.001
Split Flow NTrial= 30
Split Flow Tol= 0.02
Split Flow Ratio= 0.02
Log Output Level= 0
Friction Slope Method= 1
Unsteady Friction Slope Method= 2
Unsteady Bridges Friction Slope Method= 1
Parabolic Critical Depth
Global Vel Dist= 1 , 1 , 1
Global Log Level= 0
CheckData=True
Encroach Param=-1 ,0,0, 0
BEGIN DESCRIPTION:
Multiple Run
END DESCRIPTION:
Computation Interval=1HOUR
Output Interval=1HOUR
Run HTab= 0
Run UNet= 0
Run PostProcess= 0
Run WQNet= 0
UNET Theta= 1
UNET Theta Warmup= 1
UNET ZTol= 0.02
UNET ZSATol= 0.05
UNET MxIter= 20
UNET MaxInSteps= 0
UNET DtIC= 0
UNET DtMin= 0
UNET MaxCRTS= 20
UNET WFStab= 2
UNET SFStab= 1
UNET WFX= 1
UNET SFX= 1
UNET DSS MLevel= 4
UNET DZMax Abort= 100
UNET Convert EG Bridges= 0
UNET Use Existing IB Tables=-1
UNET Froude Reduction=False
UNET Froude Limit= 1
UNET Froude Power= 10
UNET Time Slicing=0,0, 5
UNET Junction Losses=0
Instantaneous Interval=1HOUR
Write IC File= 0
Write IC File at Sim End=0
Echo Input=False
Echo Parameters=False
Echo Output=False
Write Detailed= 0
WQ AD Non Conservative
WQ ULTIMATE=-1
WQ Max Comp Step=1HOUR
WQ Output Interval=15MIN
WQ Output Selected Increments= 0
WQ Output face flow=0
WQ Output face velocity=0
WQ Output face area=0
WQ Output face dispersion=0
WQ Output cell volume=0
WQ Output cell surface area=0
WQ Output cell continuity=0
WQ Output cumulative cell continuity=0
WQ Output face conc=0
WQ Output face dconc_dx=0
WQ Output face courant=0
WQ Output face peclet=0
WQ Output face adv mass=0
WQ Output face disp mass=0
WQ Output cell mass=0
WQ Output cell source sink temp=0
WQ Output cell source sink nsm=0
WQ Output MaxMinRange=-1
WQ Daily Max Min Mean=-1
WQ Daily Range=0
WQ Daily Time=0
WQ Create Restart=0
WQ Fixed Restart=0
WQ System Summary=0
WQ Use Fixed Temperature=0
Sorting and Armoring Iterations= 10
XS Update Threshold= 0.02
Hydraulics Update Threshold= 0.02
Energy Slope Method= 1
Volume Change Method= 0
XS Weighting Method= 0
Number of US Weighted Cross Sections= 1
Number of DS Weighted Cross Sections= 1
Upstream XS Weight=0.25
Main XS Weight=0.5
Downstream XS Weight=0.25
Number of DS XS's Weighted with US Boundary= 1
Upstream Boundary Weight= 1
Weight of XSs Associated with US Boundary= 0
Number of US XS's Weighted with DS Boundary= 1
Downstream Boundary Weight= 0.5
Weight of XSs Associated with DS Boundary= 0.5
Sediment Output Level= 4
Mass or Volume Output= 0
Output Increment Type= 1
Profile and TS Output Increment= 10
XS Output Flag= 0
XS Output Increment= 10
Disregard all LS=0
Disregard all Conn=0
Disregard all Breaches=0
Disregard all Pumps=0

--- HOOSIER CREEK.f01 (steady flow) ---

Flow Title=Multiple
Program Version=4.10
Number of Profiles= 7
Profile Names=10-year,25-year,50-year,1pct_min,100-year,1pct_plu,500-year
River Rch & RM=HOOSIER CREEK,Reach-1         ,57725
     560     896    1197     775    1545    3084    2549
River Rch & RM=HOOSIER CREEK,Reach-1         ,57183
     680    1098    1476     959    1914    3820    3189
River Rch & RM=HOOSIER CREEK,Reach-1         ,54546
     941    1548    2106    1384    2762    5511    4707
River Rch & RM=HOOSIER CREEK,Reach-1         ,52097
     956    1573    2138    1405    2804    5594    4773
River Rch & RM=HOOSIER CREEK,Reach-1         ,49933
    1226    2038    2791    1845    3682    7346    6347
River Rch & RM=HOOSIER CREEK,Reach-1         ,45637
    1312    2188    3003    1989    3968    7917    6863
River Rch & RM=HOOSIER CREEK,Reach-1         ,44797
    1542    2590    3571    2374    4737    9453    8264
River Rch & RM=HOOSIER CREEK,Reach-1         ,40851
    1689    2846    3933    2619    5226   10427    9146
River Rch & RM=HOOSIER CREEK,Reach-1         ,37249
    2100    3570    4962    3323    6630   13228   11728
River Rch & RM=HOOSIER CREEK,Reach-1         ,34056
    2301    3927    5471    3672    7326   14618   13019
River Rch & RM=HOOSIER CREEK,Reach-1         ,32898
    2423    4142    5777    3881    7743   15449   13784
River Rch & RM=HOOSIER CREEK,Reach-1         ,30574
    2583    4424    6180    4156    8292   16545   14796
River Rch & RM=HOOSIER CREEK,Reach-1         ,28519
    2763    4738    6623    4455    8890   17737   15875
River Rch & RM=HOOSIER CREEK,Reach-1         ,24363
    2762    4734    6616    4450    8878   17715   15847
River Rch & RM=HOOSIER CREEK,Reach-1         ,23909
    2951    5070    7096    4779    9536   19027   17068
River Rch & RM=HOOSIER CREEK,Reach-1         ,21206
    3125    5378    7535    5079   10134   20220   18168
River Rch & RM=HOOSIER CREEK,Reach-1         ,16092
    3275    5610    7839    5268   10512   20973   18723
River Rch & RM=HOOSIER CREEK,Reach-1         ,7806
    3524    6059    8486    5716   11405   22757   20409
River Rch & RM=HOOSIER CREEK,Reach-1         ,6672
    3605    6200    8686    5852   11676   23297   20899
River Rch & RM=HOOSIER CREEK,Reach-1         ,3307
    3671    6316    8850    5963   11897   23737   21299
Boundary for River Rch & Prof#=HOOSIER CREEK,Reach-1         , 1
Up Type= 0
Dn Type= 3
Dn Slope=0.00206
Boundary for River Rch & Prof#=HOOSIER CREEK,Reach-1         , 2
Up Type= 0
Dn Type= 3
Dn Slope=0.00206
Boundary for River Rch & Prof#=HOOSIER CREEK,Reach-1         , 3
Up Type= 0
Dn Type= 3
Dn Slope=0.00206
Boundary for River Rch & Prof#=HOOSIER CREEK,Reach-1         , 4
Up Type= 0
Dn Type= 3
Dn Slope=0.00206
Boundary for River Rch & Prof#=HOOSIER CREEK,Reach-1         , 5
Up Type= 0
Dn Type= 3
Dn Slope=0.00206
Boundary for River Rch & Prof#=HOOSIER CREEK,Reach-1         , 6
Up Type= 0
Dn Type= 3
Dn Slope=0.00206
Boundary for River Rch & Prof#=HOOSIER CREEK,Reach-1         , 7
Up Type= 0
Dn Type= 3
Dn Slope=0.00206
DSS Import GetInterval= 0
DSS Import GetPeak= 0
DSS Import FillOption= 0

--- HOOSIER CREEK.g01 (geometry) ---

Geom Title=Existing Conditions
Program Version=4.10

River Reach=HOOSIER CREEK   ,Reach-1
Reach XY= 30
        2447475.       13517075.      2448622.55     13518069.53
      2451185.28     13518974.01       2452873.5     13518671.54
        2453025.       13518225.        2454350.     13518975.41
      2455135.45     13518175.53      2456878.31       13518467.
      2457376.48     13517578.61        2459425.       13517525.
      2459578.53     13516326.45      2460211.27      13515788.2
      2464849.89     13513124.68      2467614.57     13513276.05
      2469575.09     13514017.72      2470018.88     13513676.82
      2470876.65     13514671.89      2471695.16     13514494.63
      2471821.68     13515366.96       2476064.5      13515173.8
      2476774.97     13514432.48      2478714.81     13515675.46
      2479316.84     13515381.05      2479626.73     13514228.31
      2482728.42     13514767.21      2483218.94     13513483.14
      2484364.38     13513724.41      2485159.78     13513175.51
      2486818.93     13514816.89        2488825.       13515525.

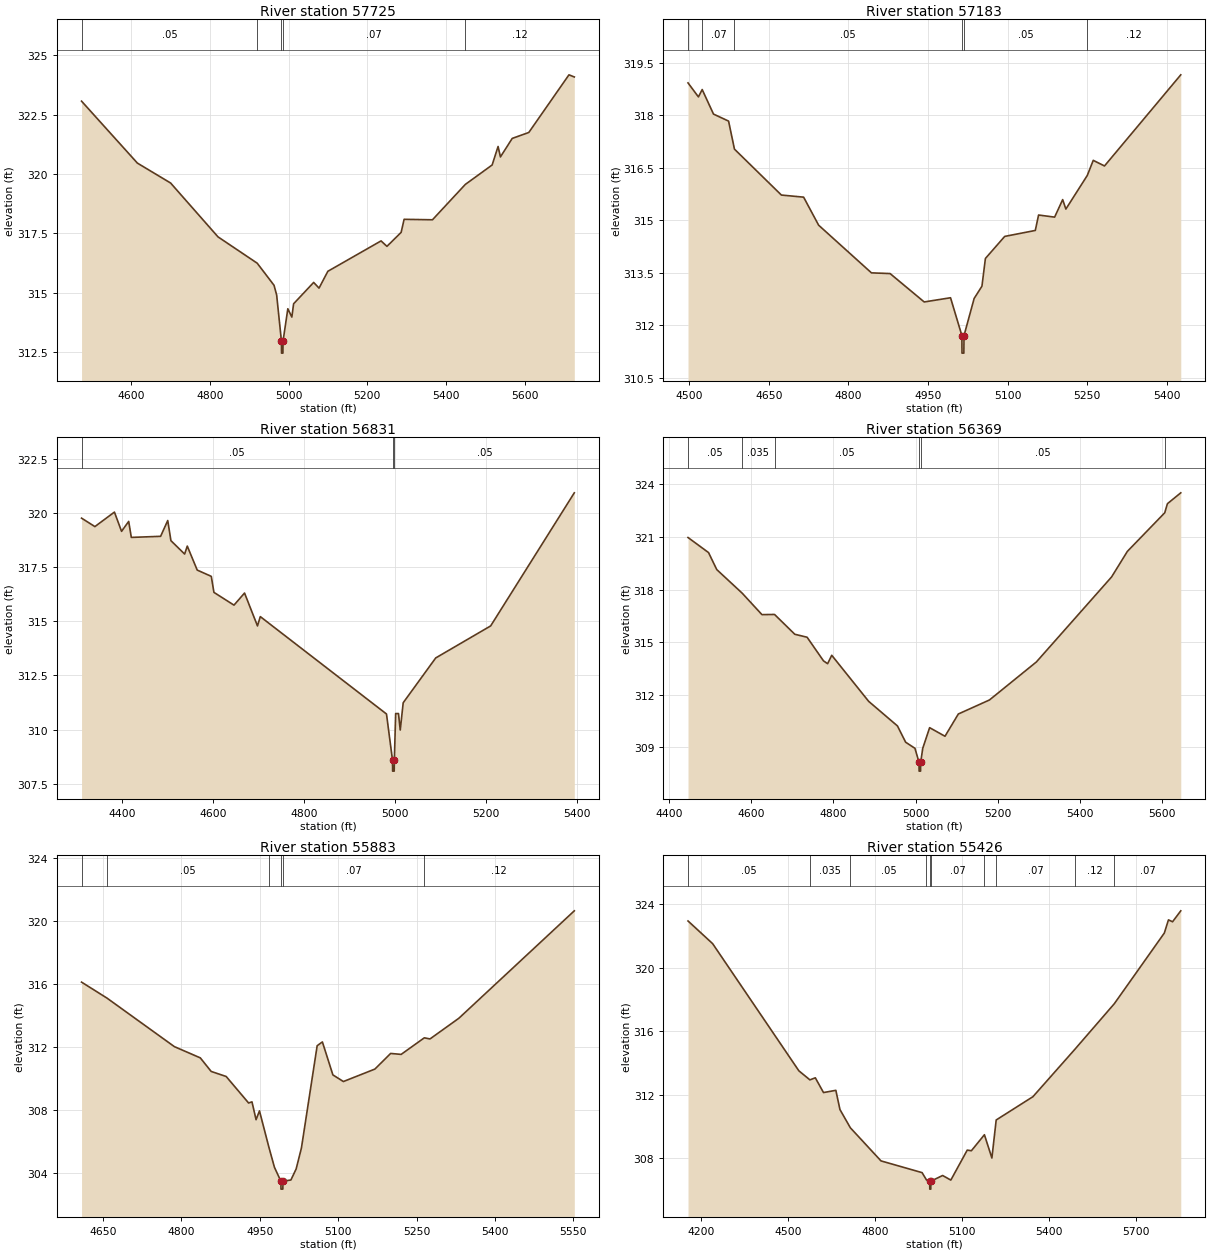
Type RM Length L Ch R = 1 ,57725   ,542,542,542
BEGIN DESCRIPTION:
HOOSIER CREEK 106.0
END DESCRIPTION:
XS GIS Cut Line= 3
      2447224.97     13517475.03        2447625.       13517125.
      2448025.02     13516524.97
#Sta/Elev= 30
  4473.6  323.07  4615.5  320.46    4700  319.62  4820.5  317.35  4920.2  316.24
  4962.9  315.31  4969.6   314.9  4981.8  312.95    4982  312.45  4985.5  312.45
  4985.8  312.95    4998  314.32  5008.2  313.97  5012.7  314.53  5063.7  315.43
  5077.3  315.19  5099.8   315.9    5235  317.18    5250  316.95  5286.1  317.54
  5293.6  318.09  5365.7  318.07  5449.2  319.56  5517.4  320.38  5532.5  321.16
  5538.5  320.72  5568.5   321.5  5610.6  321.75  5712.7  324.18  5726.3  324.09
#Mann= 5 ,-1 , 0
  4473.6     .05       0  4920.2     .07       0  4981.8     .05       0
  4985.8     .07       0  5449.2     .12       0
Bank Sta=4981.8,4985.8
XS Rating Curve= 0 ,0
Exp/Cntr=0.3,0.1

Type RM Length L Ch R = 1 ,57183   ,352,352,352
BEGIN DESCRIPTION:
Mapping XS 8a9b8dea
END DESCRIPTION:
XS GIS Cut Line= 3
      2447642.81     13517750.73      2447986.98     13517442.41
      2448237.34       13517049.
#Sta/Elev= 30
  4497.7  318.92  4517.3  318.52  4524.4  318.73  4545.7  318.03  4574.1  317.83
  4585.2  317.03  4673.6  315.72  4715.5  315.66  4743.8  314.86  4843.3   313.5
  4878.4  313.48  4942.7  312.67  4992.3  312.79  5013.7  311.71  5013.9  311.21
  5017.4  311.21  5017.7  311.71  5036.8  312.77  5051.5  313.12    5058  313.91
  5094.4  314.54    5152  314.71  5158.2  315.15  5188.4  315.09  5203.6  315.59
  5209.6  315.32    5250  316.28  5261.2  316.71  5282.4  316.55  5426.1  319.15
#Mann= 6 ,-1 , 0
  4497.7     .05       0  4524.4     .07       0  4585.2     .05       0
  5013.7     .05       0  5017.7     .05       0    5250     .12       0
Bank Sta=5013.7,5017.7
XS Rating Curve= 0 ,0
Exp/Cntr=0.3,0.1

Type RM Length L Ch R = 1 ,56831   ,462,462,462
BEGIN DESCRIPTION:
HOOSIER CREEK 104.0
END DESCRIPTION:
XS GIS Cut Line= 3
        2447875.       13518225.        2448225.       13517625.
      2448524.97     13517375.02
#Sta/Elev= 30
    4310  319.77  4339.4  319.38  4382.4  320.05  4398.1  319.16  4413.8  319.62
  4419.6  318.88  4484.1  318.93  4499.8  319.66  4506.8  318.73    4537  318.11
  4542.8  318.48  4564.7  317.37  4595.7  317.08  4601.5  316.34  4645.7  315.75
  4668.9  316.31  4697.4  314.79  4703.6  315.22  4981.5  310.72  4994.8  308.58
    4995  308.08  4998.5  308.08  4998.8  308.58  5001.7  310.74  5007.9  310.74
  5011.8  309.98  5018.3  311.24  5089.9  313.31  5210.9  314.79  5395.1  320.94
#Mann= 3 ,-1 , 0
    4310     .05       0  4994.8     .05       0  4998.8     .05       0
Bank Sta=4994.8,4998.8
XS Rating Curve= 0 ,0
Exp/Cntr=0.3,0.1

Type RM Length L Ch R = 1 ,56369   ,486,486,486
BEGIN DESCRIPTION:
HOOSIER CREEK 103.0
END DESCRIPTION:
XS GIS Cut Line= 3
        2448475.     13518524.97        2448475.       13517975.
      2448725.01     13517374.97
#Sta/Elev= 30
  4445.9  320.97  4495.9  320.11  4515.9  319.14    4578  317.79  4625.9  316.57
  4656.6  316.58  4705.9  315.45  4735.9  315.28  4775.9  313.93  4785.9  313.77
  4795.9  314.25  4885.9  311.62  4955.9  310.22  4975.9  309.29  4998.6  308.94
  5008.5  308.14  5008.7  307.64  5012.2  307.64  5012.5  308.14  5017.5  308.94
  5034.3  310.12  5071.7  309.63  5104.2   310.9    5180   311.7  5294.3  313.87
  5477.4  318.72  5515.9  320.18  5606.8  322.38  5613.4   322.9  5645.9  323.52
#Mann= 6 ,-1 , 0
  4445.9     .05       0    4578    .035       0  4656.6     .05       0
  5008.5     .05       0  5012.5     .05       0  5606.8     .07       0
Bank Sta=5008.5,5012.5
XS Rating Curve= 0 ,0
Exp/Cntr=0.3,0.1

Type RM Length L Ch R = 1 ,55883   ,457,457,457
BEGIN DESCRIPTION:
HOOSIER CREEK 102.0
END DESCRIPTION:
XS GIS Cut Line= 3
      2448674.97     13518375.03        2448925.       13518075.
        2448875.     13517525.02
#Sta/Elev= 30
  4609.1  316.11  4657.7   315.1  4786.8  312.02  4836.3  311.31  4857.1  310.45
  4885.8  310.13  4928.7  308.45  4935.2  308.52    4943  307.39  4949.5  307.95
  4967.6  305.64  4978.2  304.37  4990.5  303.49  4990.7  302.99  4994.2  302.99
  4994.5  303.49  5009.7  303.57  5019.7  304.27  5029.8   305.6  5059.9  312.08
  5069.9  312.32    5090  310.23  5110.1  309.81  5170.4   310.6  5200.5  311.59
  5220.6  311.53  5264.9  312.58  5275.8  312.51    5331  313.82  5551.9  320.63
#Mann= 6 ,-1 , 0
  4609.1    .035       0  4657.7     .05       0  4967.6     .07       0
  4990.5     .05       0  4994.5     .07       0  5264.9     .12       0
Bank Sta=4990.5,4994.5
XS Rating Curve= 0 ,0
Exp/Cntr=0.3,0.1

Type RM Length L Ch R = 1 ,55426   ,436,436,436
BEGIN DESCRIPTION:
HOOSIER CREEK 101.0
END DESCRIPTION:
XS GIS Cut Line= 3
      2448725.03     13518774.97        2449325.       13518175.
      2449924.99     13517575.01
#Sta/Elev= 30
  4156.3  322.96  4241.1  321.53  4538.1  313.51  4576.1  312.94  4594.7  313.07
  4622.9  312.14  4665.4  312.28  4679.5  311.07  4715.3  309.92  4820.9  307.83
  4962.4  307.09  4977.5  306.63  4988.6  306.55  4988.9  306.05  4992.4  306.05
  4992.6  306.55  5033.1  306.91  5061.4  306.62  5117.9  308.51  5132.1  308.47
  5177.1  309.48  5202.8  308.01  5217.6  310.41  5344.2  311.88  5488.7  314.87
  5624.3  317.74  5796.7   322.2  5810.9  323.03    5825  322.91  5853.3   323.6
#Mann= 10 ,-1 , 0
  4156.3     .05       0  4576.1    .035       0  4715.3     .05       0
  4977.5     .07       0  4988.6     .05       0  4992.6     .07       0
  5177.1    .035       0  5217.6     .07       0  5488.7     .12       0
  5624.3     .07       0
Bank Sta=4988.6,4992.6
XS Rating Curve= 0 ,0
Exp/Cntr=0.3,0.1

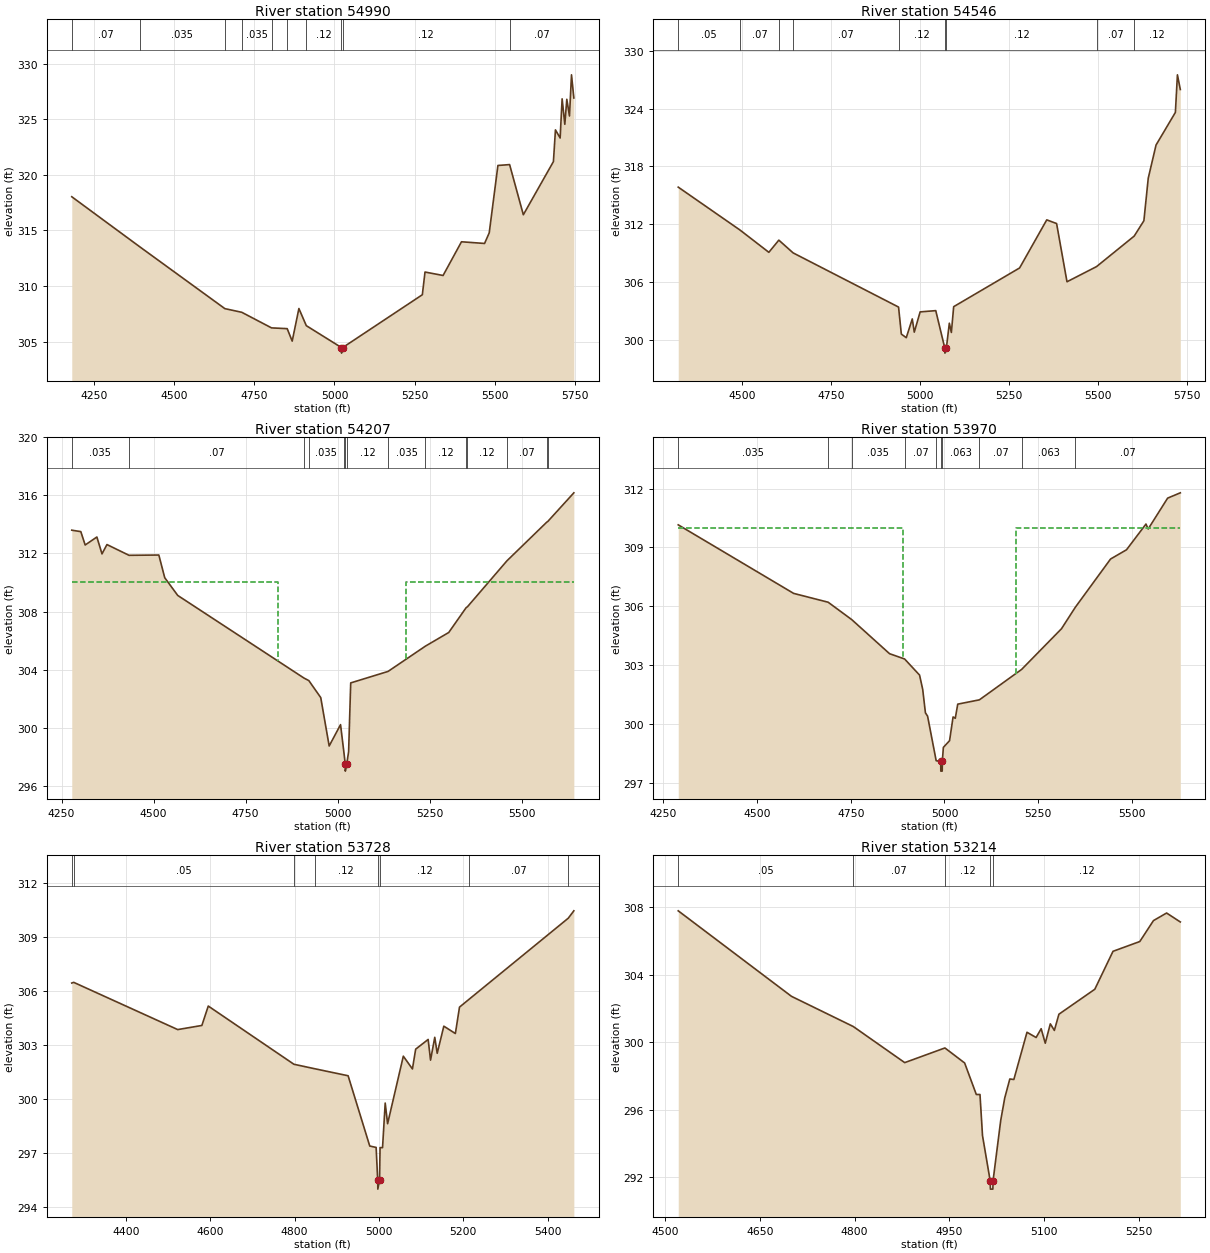
Type RM Length L Ch R = 1 ,54990   ,444,444,444
BEGIN DESCRIPTION:
HOOSIER CREEK 100.0
END DESCRIPTION:
XS GIS Cut Line= 3
      2449075.04     13518874.97        2449675.       13518325.
      2450125.01     13517724.99
#Sta/Elev= 30
  4181.7  318.03    4393  313.54  4658.6  307.97  4711.3  307.64  4803.9  306.24
  4852.7  306.17  4868.3  305.05  4889.2  307.98  4912.2  306.44  5021.7  304.47
    5022  303.97  5025.7  304.47  5273.7  309.22    5282  311.26  5338.3  310.95
  5395.6  313.98  5467.5  313.83    5482  314.78  5509.1  320.84  5545.5  320.92
  5588.3  316.41    5682  321.19  5688.3  324.04  5702.9  323.31  5709.1  326.83
  5717.5  324.54  5723.7  326.79    5732  325.29  5738.3  328.99  5745.6  326.91
#Mann= 10 ,-1 , 0
  4181.7     .07       0    4393    .035       0  4658.6     .05       0
  4711.3    .035       0  4803.9     .12       0  4852.7    .035       0
  4912.2     .12       0  5021.7     .05       0  5025.7     .12       0
  5545.5     .07       0
Bank Sta=5021.7,5025.7
XS Rating Curve= 0 ,0
Exp/Cntr=0.3,0.1

Type RM Length L Ch R = 1 ,54546   ,339,339,339
BEGIN DESCRIPTION:
HOOSIER CREEK 99.0
END DESCRIPTION:
XS GIS Cut Line= 3
      2449675.02     13519074.96        2449975.       13518475.
      2450324.99     13517825.02
#Sta/Elev= 30
  4321.8  315.86  4495.4  311.41  4576.1  309.11  4604.1  310.37  4644.2  309.05
  4940.1  303.44  4947.9  300.64  4961.8  300.27  4978.6  302.21  4984.2  300.84
  5000.7  302.94  5044.5  303.07    5070  299.17  5070.2  298.67  5074.2  299.17
  5082.6  301.77  5088.3  300.81  5094.8  303.48  5279.8  307.49    5356  312.47
  5383.6  312.09  5412.8  306.06  5495.7  307.63  5601.4  310.79  5628.6  312.38
  5640.8  316.78  5662.7  320.22    5717   323.6  5722.7  327.49  5730.8  325.97
#Mann= 9 ,-1 , 0
  4321.8     .05       0  4495.4     .07       0  4604.1    .035       0
  4644.2     .07       0  4940.1     .12       0    5070     .05       0
  5074.2     .12       0  5495.7     .07       0  5601.4     .12       0
Bank Sta=5070,5074.2
XS Rating Curve= 0 ,0
Exp/Cntr=0.3,0.1

Type RM Length L Ch R = 1 ,54207   ,237,237,237
BEGIN DESCRIPTION:
HOOSIER CREEK 98.0
END DESCRIPTION:
XS GIS Cut Line= 3
      2449905.46     13519186.83      2450255.13      13518554.7
      2450563.51      13517992.3
#Sta/Elev= 30
  4277.6   313.6  4302.2   313.5    4314  312.58  4345.8  313.13  4359.7  311.97
  4373.2  312.61  4433.2  311.87  4514.1  311.89  4530.1  310.33  4565.4  309.11
  4908.6  303.42  4921.5  303.25  4953.9  302.08  4976.8  298.75  5007.7  300.22
  5016.8  298.31  5020.4  297.52  5020.6  297.02  5024.6  297.52  5029.6  298.36
  5035.3  303.09  5136.7  303.88  5238.2  305.62  5301.6  306.56  5348.9  308.27
  5352.4  308.33  5459.6  311.49  5568.2  314.16  5570.3  314.19  5641.4  316.17
#Mann= 14 ,-1 , 0
  4277.6    .035       0  4433.2     .07       0  4908.6     .12       0
  4921.5    .035       0  5016.8     .12       0  5020.4    .035       0
  5024.6     .12       0  5136.7    .035       0  5238.2     .12       0
  5348.9     .07       0  5352.4     .12       0  5459.6     .07       0
  5568.2    .035       0  5570.3     .07       0
#XS Ineff= 2 ,-1
    4278    4839     310    5186    5641     310
Permanent Ineff=
       F       F
Bank Sta=5020.4,5024.6
XS Rating Curve= 0 ,0
Exp/Cntr=0.3,0.1

Type RM Length L Ch R = 1 ,53970   ,242,242,242
BEGIN DESCRIPTION:
HOOSIER CREEK 97.0
END DESCRIPTION:
XS GIS Cut Line= 3
      2450105.18     13519237.09        2450465.     13518625.02
      2450797.86     13518091.31
#Sta/Elev= 30
    4290  310.15  4597.7  306.66  4689.8  306.21    4753  305.32  4853.5  303.59
  4893.7  303.32  4933.6   302.5    4942  301.77  4949.2  300.58    4955  300.41
  4977.9  298.14    4990  298.11  4990.3  297.61    4994  297.61  4994.3  298.11
  4997.1  298.82  5013.6  299.16    5023  300.37  5028.9   300.3  5035.4  301.02
  5093.2  301.24  5205.9  302.79  5312.1  304.86  5348.9  305.95    5443  308.41
  5485.5  308.88  5537.4  310.19  5543.3  309.94  5595.2  311.51    5629  311.78
#Mann= 10 ,-1 , 0
    4290    .035       0  4689.8     .07       0    4753    .035       0
  4893.7     .07       0  4977.9    .063       0    4990     .05       0
  4994.3    .063       0  5093.2     .07       0  5205.9    .063       0
  5348.9     .07       0
#XS Ineff= 2 ,-1
    4290    4890     310    5190    5629     310
Permanent Ineff=
       F       F
Bank Sta=4990,4994.3
XS Rating Curve= 0 ,0
Exp/Cntr=0.3,0.1

Type RM Length L Ch R = 1 ,53728   ,514,514,514
BEGIN DESCRIPTION:
Mapping XS 2932d416
END DESCRIPTION:
XS GIS Cut Line= 3
      2450292.66     13519200.67      2450693.71     13518586.07
       2450922.9      13518190.2
#Sta/Elev= 30
  4271.1  306.44  4275.6  306.48  4522.5  303.85  4579.8  304.08    4595  305.16
  4798.2  301.92  4847.7  301.67  4926.8  301.28  4978.1  297.37  4993.3  297.29
    4997  295.47  4997.3  294.97  5001.4  295.47  5002.6  297.28  5008.5  297.28
  5014.8  299.76  5020.5  298.61  5057.8  302.37  5079.4  301.66  5087.1  302.76
  5116.7   303.3  5122.4  302.15  5132.4  303.42  5138.2  302.53  5153.9  304.04
  5181.3  303.63  5191.1   305.1  5214.5  305.55  5449.2  310.05  5462.4  310.46
#Mann= 8 ,-1 , 0
  4271.1    .035       0  4275.6     .05       0  4798.2     .07       0
  4847.7     .12       0    4997     .05       0  5001.4     .12       0
  5214.5     .07       0  5449.2    .035       0
Bank Sta=4997,5001.4
XS Rating Curve= 0 ,0
Exp/Cntr=0.3,0.1

Type RM Length L Ch R = 1 ,53214   ,430,430,430
BEGIN DESCRIPTION:
HOOSIER CREEK 96.0
END DESCRIPTION:
XS GIS Cut Line= 3
      2450875.01     13519274.96        2451025.       13518825.
      2451225.03     13518574.97
#Sta/Elev= 30
  4520.8  307.78    4700  302.71  4797.8  300.92  4879.2  298.78  4942.8  299.65
    4974  298.76  4992.5  296.89  4998.3  296.89  5002.3  294.45  5014.4  291.78
  5014.8  291.28  5018.7  291.28    5019  291.78  5031.1  295.35  5037.5  296.69
  5045.5  297.81  5051.9  297.78  5072.7  300.58  5087.1  300.27  5095.1  300.79
  5101.6  299.93  5109.6  301.08    5116  300.69  5123.2  301.65    5180  303.13
  5208.8  305.38  5251.2  305.96  5272.8   307.2  5293.6  307.65  5315.3  307.12
#Mann= 5 ,-1 , 0
  4520.8     .05       0  4797.8     .07       0  4942.8     .12       0
  5014.4     .05       0    5019     .12       0
Bank Sta=5014.4,5019
XS Rating Curve= 0 ,0
Exp/Cntr=0.3,0.1

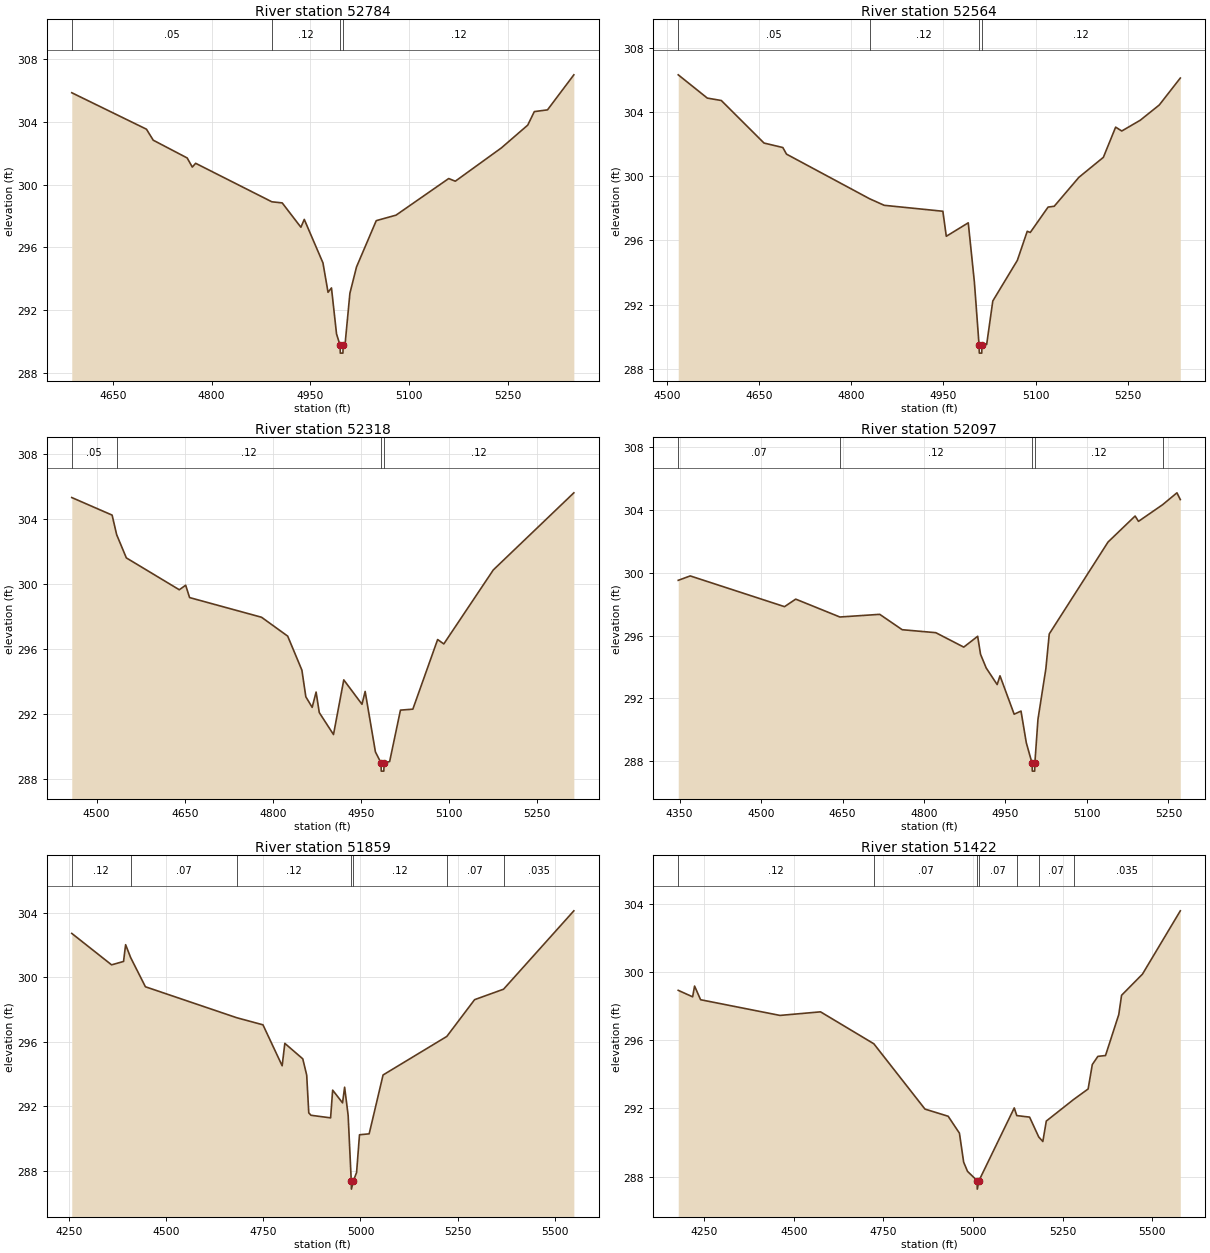
Type RM Length L Ch R = 1 ,52784   ,220,220,220
BEGIN DESCRIPTION:
HOOSIER CREEK 95.0
END DESCRIPTION:
XS GIS Cut Line= 3
        2451275.       13519375.        2451375.       13518975.
        2451375.     13518625.01
#Sta/Elev= 30
  4587.7  305.84  4701.1  303.52  4711.4  302.82  4762.9  301.69  4770.7  301.11
  4775.8  301.35  4891.5   298.9  4907.2  298.83  4935.6  297.28  4940.7  297.78
  4969.1  295.01  4976.8  293.14    4982  293.42  4989.7  290.49  4995.1  289.77
  4995.4  289.27  4999.4  289.27  4999.8  289.77  5002.5  289.77    5010  293.08
    5020  294.75    5050   297.7    5080  298.05    5160  300.38    5170  300.21
    5240  302.33    5280  303.78    5290  304.64    5310  304.75    5350  306.98
#Mann= 4 ,-1 , 0
  4587.7     .05       0  4891.5     .12       0  4995.1     .05       0
  4999.8     .12       0
Bank Sta=4995.1,4999.8
XS Rating Curve= 0 ,0
Exp/Cntr=0.3,0.1

Type RM Length L Ch R = 1 ,52564   ,246,246,246
BEGIN DESCRIPTION:
Mapping XS f0e5a473
END DESCRIPTION:
XS GIS Cut Line= 3
      2451442.75     13519431.13      2451595.53     13519004.06
      2451578.18     13518639.75
#Sta/Elev= 30
  4517.7  306.32  4565.1  304.87  4587.9  304.72  4657.5  302.07  4688.2  301.79
  4694.1  301.38  4829.5   298.6  4853.4  298.19    4949  297.82  4954.6  296.26
  4990.4   297.1  5000.4   293.4    5008  289.48  5008.4  288.98  5012.4  288.98
  5012.7  289.48  5020.4  289.52  5030.4  292.23  5070.4  294.76  5086.5  296.57
  5091.5   296.5  5120.5  298.08  5130.5  298.13  5170.6  299.93  5210.6  301.18
  5230.6  303.06  5240.6  302.82  5270.7  303.49  5301.7  304.44    5336  306.12
#Mann= 4 ,-1 , 0
  4517.7     .05       0  4829.5     .12       0    5008     .05       0
  5012.7     .12       0
Bank Sta=5008,5012.7
XS Rating Curve= 0 ,0
Exp/Cntr=0.3,0.1

Type RM Length L Ch R = 1 ,52318   ,221,221,221
BEGIN DESCRIPTION:
HOOSIER CREEK 94.0
END DESCRIPTION:
XS GIS Cut Line= 3
      2451624.99     13519425.02        2451825.       13518925.
      2451724.99     13518624.97
#Sta/Elev= 30
  4457.6  305.33  4526.3  304.25    4534  303.05  4550.5  301.62  4640.7  299.66
  4651.5  299.94  4658.2  299.18  4780.7  297.97  4825.2  296.81  4849.4  294.72
  4856.1  293.08  4866.9  292.43  4873.6  293.37    4879  292.11  4903.2  290.76
  4920.7  294.12  4951.7  292.62  4957.1  293.41  4974.6  289.69  4984.2  289.01
  4984.5  288.51  4988.9  288.51  4989.3  289.01  4998.8   289.1  5017.2  292.26
  5038.3  292.32  5080.5   296.6    5091  296.33  5175.3  300.88  5312.4  305.62
#Mann= 4 ,-1 , 0
  4457.6     .05       0    4534     .12       0  4984.2     .05       0
  4989.3     .12       0
Bank Sta=4984.2,4989.3
XS Rating Curve= 0 ,0
Exp/Cntr=0.3,0.1

Type RM Length L Ch R = 1 ,52097   ,238,238,238
BEGIN DESCRIPTION:
Mapping XS 5099b60e
END DESCRIPTION:
XS GIS Cut Line= 3
      2452154.55     13519404.79      2452000.48     13518792.83
      2451823.09      13518559.2
#Sta/Elev= 30
  4347.5  299.52  4369.6   299.8  4543.2  297.84  4563.8  298.32  4645.1  297.18
  4718.5  297.35  4759.8  296.37  4821.7  296.18  4873.2  295.26  4898.8  295.95
  4904.1   294.8  4914.5  293.93  4934.7  292.87  4939.9  293.43    4966  290.98
  4978.6  291.18  4988.4  289.15    4999  287.85  4999.4  287.35  5003.8  287.35
  5004.1  287.85  5009.8  290.65  5024.4  293.89  5030.6   296.1  5138.8  301.96
  5188.7  303.62  5194.9  303.28  5239.2  304.34  5265.7   305.1  5271.9  304.67
#Mann= 5 ,-1 , 0
  4347.5     .07       0  4645.1     .12       0    4999     .05       0
  5004.1     .12       0  5239.2     .07       0
Bank Sta=4999,5004.1
XS Rating Curve= 0 ,0
Exp/Cntr=0.3,0.1

Type RM Length L Ch R = 1 ,51859   ,437,437,437
BEGIN DESCRIPTION:
HOOSIER CREEK 93.0
END DESCRIPTION:
XS GIS Cut Line= 3
      2452475.01     13519475.02        2452225.       13518775.
      2451911.51     13518324.09
#Sta/Elev= 30
  4256.8  302.72  4359.3  300.77  4390.1  300.98  4395.4  302.02  4408.4  301.22
  4446.4  299.41  4681.5  297.49    4749  297.05  4798.4  294.51  4805.3   295.9
  4851.5  294.94  4861.6  293.93  4866.9  291.59  4872.7  291.44  4923.1  291.28
  4928.4     293  4953.9  292.21  4959.2  293.18  4968.3  291.43  4976.3  287.36
  4976.7  286.86  4981.5  287.36    4990  287.89  4997.5  290.23  5022.4  290.29
  5058.2  293.94  5222.3  296.33  5293.8  298.61  5368.4  299.26  5549.3  304.12
#Mann= 7 ,-1 , 0
  4256.8     .12       0  4408.4     .07       0  4681.5     .12       0
  4976.3     .05       0  4981.5     .12       0  5222.3     .07       0
  5368.4    .035       0
Bank Sta=4976.3,4981.5
XS Rating Curve= 0 ,0
Exp/Cntr=0.3,0.1

Type RM Length L Ch R = 1 ,51422   ,765,765,765
BEGIN DESCRIPTION:
HOOSIER CREEK 92.0
END DESCRIPTION:
XS GIS Cut Line= 3
      2452786.94     13519242.84        2452475.       13518475.
      2451984.42     13518180.65
#Sta/Elev= 30
  4177.8  298.92    4218  298.54  4223.4  299.17  4240.2  298.37  4461.7  297.45
  4574.8  297.66  4723.5  295.79  4866.3  291.96    4931  291.54  4962.4  290.55
  4974.2  288.85    4985  288.31  5011.7  287.77  5012.2  287.27    5017  287.77
  5115.4  292.03  5122.4  291.58  5158.2  291.49  5183.6  290.33  5195.1  290.06
  5204.8  291.26  5280.8  292.52  5321.5  293.14  5333.1  294.57  5348.7  295.05
    5370   295.1    5407   297.5  5414.8  298.63  5473.1  299.87  5578.7  303.58
#Mann= 7 ,-1 , 0
  4177.8     .12       0  4723.5     .07       0  5011.7     .05       0
    5017     .07       0  5122.4    .035       0  5183.6     .07       0
  5280.8    .035       0
Bank Sta=5011.7,5017
XS Rating Curve= 0 ,0
Exp/Cntr=0.3,0.1

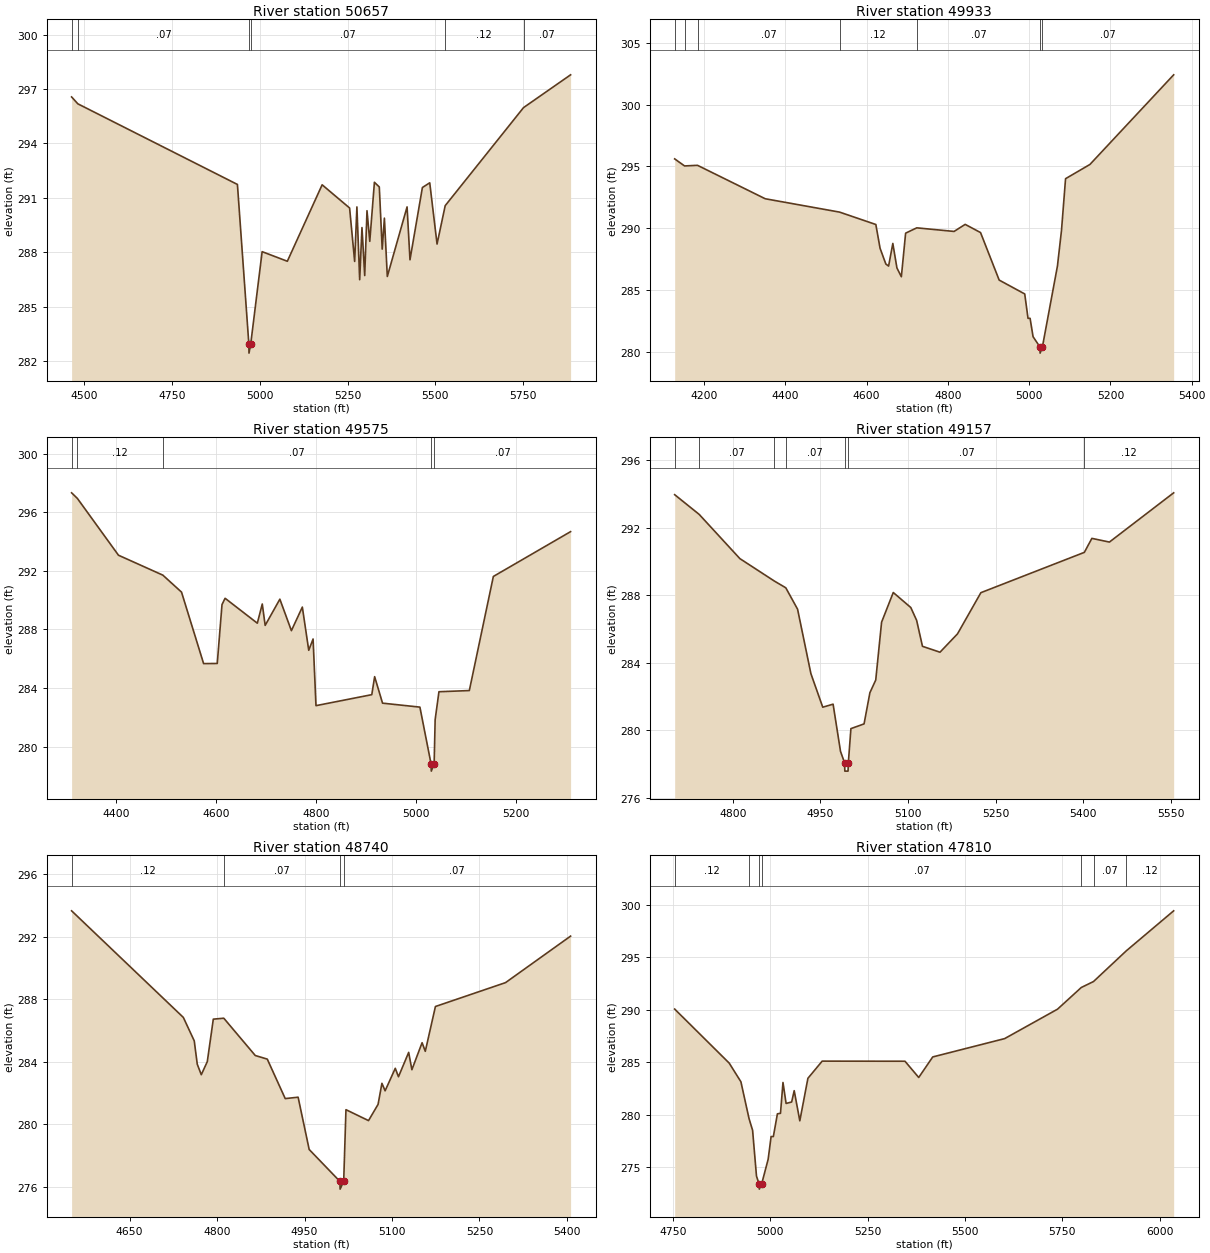
Type RM Length L Ch R = 1 ,50657   ,724,724,724
BEGIN DESCRIPTION:
Mapping XS 70a3a28c
END DESCRIPTION:
XS GIS Cut Line= 4
      2452959.67     13519097.39      2453020.44     13518656.83
      2452751.34     13518331.31      2452417.33     13517891.31
#Sta/Elev= 30
  4465.1  296.57  4482.8  296.19  4936.8  291.74  4969.3  282.93  4969.7  282.43
  4974.6  282.93  5007.1  288.03  5078.8   287.5  5177.8  291.72  5255.9  290.44
  5270.3  287.49  5276.7   290.5  5284.6  286.48  5291.1  289.36  5298.9  286.71
  5305.4  290.29  5313.3   288.6  5326.5  291.86  5340.4   291.6  5348.7  288.17
  5354.9  289.88  5363.2  286.66  5419.4   290.5  5427.7  287.58    5463  291.57
  5483.9  291.83  5504.7  288.45  5527.9  290.57  5750.7  295.98  5884.6  297.79
#Mann= 6 ,-1 , 0
  4465.1     .12       0  4482.8     .07       0  4969.3     .05       0
  4974.6     .07       0  5527.9     .12       0  5750.7     .07       0
Bank Sta=4969.3,4974.6
XS Rating Curve= 0 ,0
Exp/Cntr=0.3,0.1

Type RM Length L Ch R = 1 ,49933   ,358,358,358
BEGIN DESCRIPTION:
HOOSIER CREEK 90.0
END DESCRIPTION:
XS GIS Cut Line= 3
      2453036.19     13519057.85      2453295.18     13518224.57
      2453302.54     13517868.94
#Sta/Elev= 30
  4127.4  295.61  4151.7  295.04  4183.6  295.09  4350.3  292.39  4533.4  291.31
  4622.6  290.31    4633  288.39  4647.2  287.12    4654  286.95  4664.4  288.78
  4674.5   286.8  4685.4  286.09  4695.9  289.61  4723.3  290.04  4815.2  289.75
  4842.5  290.32  4880.3  289.66  4926.2  285.82  4989.1   284.7  4997.2  282.73
  5002.3  282.73  5009.6  281.25  5026.5  280.42    5027  279.92  5032.6  280.42
  5069.6  286.95  5079.6  289.83  5089.6  294.01  5149.6  295.16  5355.7   302.4
#Mann= 7 ,-1 , 0
  4127.4     .07       0  4151.7     .12       0  4183.6     .07       0
  4533.4     .12       0  4723.3     .07       0  5026.5     .05       0
  5032.6     .07       0
Bank Sta=5026.5,5032.6
XS Rating Curve= 0 ,0
Exp/Cntr=0.3,0.1

Type RM Length L Ch R = 1 ,49575   ,418,418,418
BEGIN DESCRIPTION:
HOOSIER CREEK 89.0
END DESCRIPTION:
XS GIS Cut Line= 3
      2453175.01     13519074.99        2453525.       13518475.
      2453574.99     13518175.05
#Sta/Elev= 30
  4311.4  297.33  4322.9  296.95  4405.2  293.07    4494  291.71  4531.4  290.55
  4575.6  285.67  4602.9  285.68  4612.4   289.7  4618.6  290.13  4683.1  288.43
    4693  289.74  4698.8  288.28  4728.2  290.07  4751.3  287.92  4773.2  289.53
    4786  286.58  4794.7  287.35  4800.5   282.8  4912.2  283.55  4917.9  284.78
  4933.7  282.97  5008.5   282.7  5030.8  278.83  5031.3  278.33    5037  278.83
    5039  281.84  5046.6  283.75  5107.4  283.83  5155.5  291.62  5310.1  294.68
#Mann= 5 ,-1 , 0
  4311.4     .07       0  4322.9     .12       0    4494     .07       0
  5030.8     .05       0    5037     .07       0
Bank Sta=5030.8,5037
XS Rating Curve= 0 ,0
Exp/Cntr=0.3,0.1

Type RM Length L Ch R = 1 ,49157   ,417,417,417
BEGIN DESCRIPTION:
HOOSIER CREEK 88.0
END DESCRIPTION:
XS GIS Cut Line= 3
      2453724.99     13519075.05        2453775.       13518775.
        2453775.     13518224.99
#Sta/Elev= 30
  4700.6  293.97  4742.6   292.8  4812.2  290.18  4871.2  288.85  4890.8  288.45
    4911  287.18  4933.8  283.36  4954.1  281.37  4971.8  281.55  4984.5  278.75
  4991.4  278.08  4991.9  277.58  4997.4  277.58  4997.9  278.08  5002.3   280.1
  5024.8  280.38  5034.8  282.23  5044.8  282.98  5054.8  286.41  5074.8  288.17
  5104.8  287.28  5114.8  286.52  5124.8  284.98  5154.8  284.63  5184.8  285.72
  5224.8  288.16  5401.9  290.55  5414.8  291.38  5444.8  291.16  5554.8  294.08
#Mann= 7 ,-1 , 0
  4700.6     .12       0  4742.6     .07       0  4871.2     .12       0
  4890.8     .07       0  4991.4     .05       0  4997.9     .07       0
  5401.9     .12       0
Bank Sta=4991.4,4997.9
XS Rating Curve= 0 ,0
Exp/Cntr=0.3,0.1

Type RM Length L Ch R = 1 ,48740   ,930,930,930
BEGIN DESCRIPTION:
HOOSIER CREEK 87.0
END DESCRIPTION:
XS GIS Cut Line= 3
      2453990.06     13519081.37      2454095.09     13518644.21
        2453925.       13518275.
#Sta/Elev= 30
  4550.4  293.67  4742.1  286.84  4760.8  285.34    4766  283.84  4772.9  283.17
  4783.2  284.01  4793.5  286.73  4811.5  286.79  4865.5   284.4  4886.1  284.17
  4916.9  281.64    4939  281.73    4958  278.38  5010.6  276.34  5011.1  275.84
  5017.2  276.34  5021.1  280.93  5059.8  280.23  5076.2  281.27  5082.8  282.62
  5088.3  282.14  5105.7  283.58  5111.2  283.04  5128.7   284.6  5134.2  283.49
  5151.7  285.22  5157.2  284.67  5174.6  287.54  5294.9  289.07  5406.5  292.05
#Mann= 4 ,-1 , 0
  4550.4     .12       0  4811.5     .07       0  5010.6     .05       0
  5017.2     .07       0
Bank Sta=5010.6,5017.2
XS Rating Curve= 0 ,0
Exp/Cntr=0.3,0.1

Type RM Length L Ch R = 1 ,47810   ,467,467,467
BEGIN DESCRIPTION:
HOOSIER CREEK 86.0
END DESCRIPTION:
XS GIS Cut Line= 3
        2454675.     13519025.05        2454675.       13518775.
      2454025.01     13517975.02
#Sta/Elev= 30
  4754.7  290.07  4894.7  284.91  4924.7  283.13  4945.6  279.61  4954.7   278.5
  4964.7  274.12  4971.4  273.38  4971.9  272.88    4978  273.38  4994.7  275.74
  5002.2   277.9    5008   277.9  5018.4  280.07  5026.3  280.12  5032.7  283.06
  5040.7  281.06    5055   281.2  5061.5  282.28  5075.9   279.4  5096.7  283.46
  5133.3   285.1  5345.9  285.09  5381.1  283.54  5417.1   285.5  5601.7  287.25
  5737.4  290.06  5798.4  292.13  5829.8   292.7  5913.9  295.63  6035.5  299.45
#Mann= 7 ,-1 , 0
  4754.7     .12       0  4945.6     .07       0  4971.4     .05       0
    4978     .07       0  5798.4     .12       0  5829.8     .07       0
  5913.9     .12       0
Bank Sta=4971.4,4978
XS Rating Curve= 0 ,0
Exp/Cntr=0.3,0.1