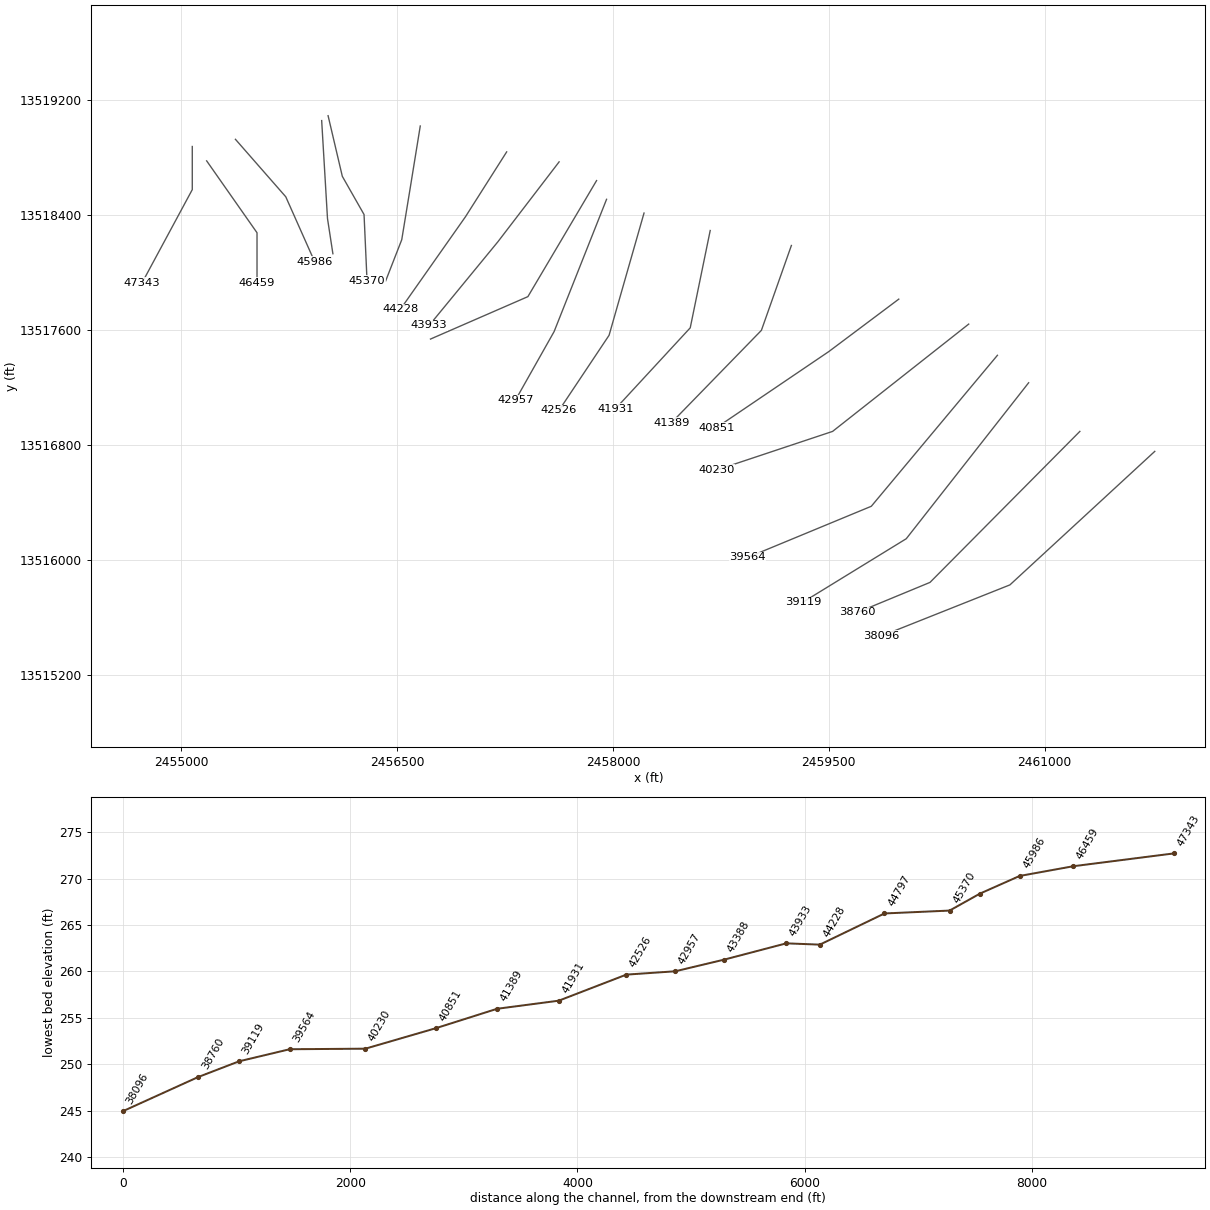
HEC-RAS study HOOSIER CREEK.prj: HOOSIER CREEK Base Level Engineering

--- HOOSIER CREEK.g01 (geometry) --- (continued)

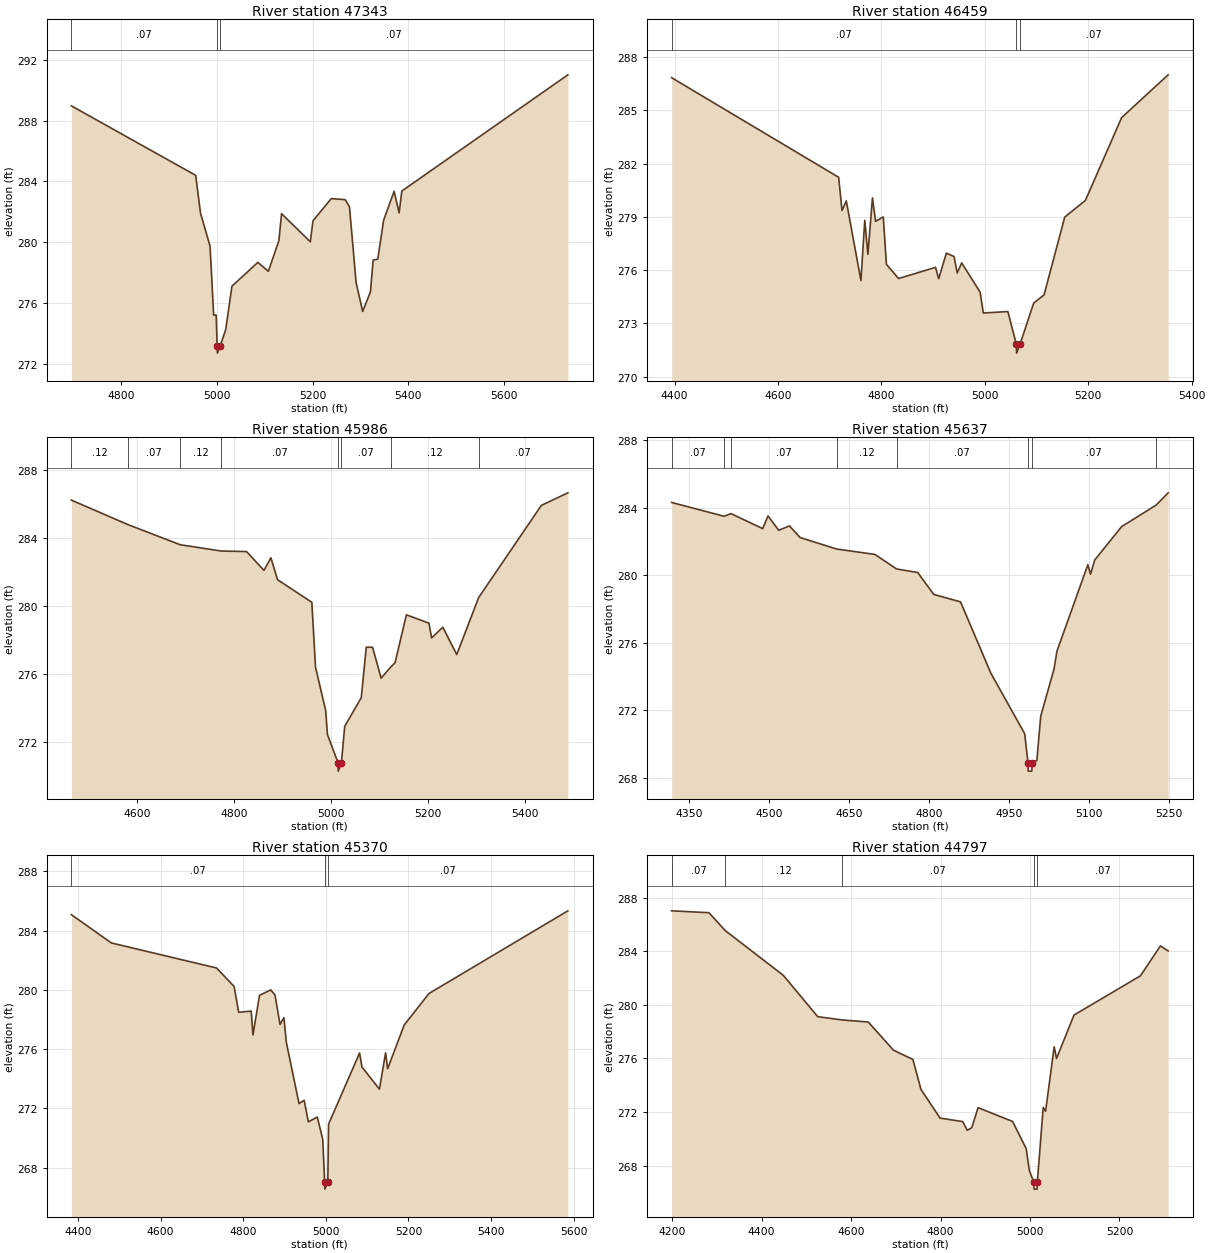
Type RM Length L Ch R = 1 ,47343   ,884,884,884
BEGIN DESCRIPTION:
HOOSIER CREEK 85.0
END DESCRIPTION:
XS GIS Cut Line= 3
        2455075.     13518874.99        2455075.       13518575.
      2454725.02     13517925.03
#Sta/Elev= 30
  4695.8  288.97  4955.8   284.4  4965.8  281.92  4985.8  279.74  4993.3  275.21
  4998.6  275.21  5000.6  273.21  5001.1  272.71  5007.3  273.21  5018.5  274.26
  5031.5  277.11  5085.8  278.68  5107.7  278.09  5129.7   280.1  5135.3  281.88
  5195.4  280.03    5201  281.41  5239.2  282.87  5268.4   282.8  5277.3  282.33
  5291.1  277.36  5304.9  275.45  5321.1  276.73  5326.8  278.83  5336.5  278.89
  5348.7  281.45  5370.6  283.35  5381.1  281.93  5386.8  283.37    5734  291.01
#Mann= 3 ,-1 , 0
  4695.8     .07       0  5000.6     .05       0  5007.3     .07       0
Bank Sta=5000.6,5007.3
XS Rating Curve= 0 ,0
Exp/Cntr=0.3,0.1

Type RM Length L Ch R = 1 ,46459   ,473,473,473
BEGIN DESCRIPTION:
HOOSIER CREEK 84.0
END DESCRIPTION:
XS GIS Cut Line= 3
      2455174.98     13518775.02        2455525.       13518275.
        2455525.     13517924.96
#Sta/Elev= 30
  4394.1  286.84  4717.2  281.23  4723.7  279.36    4732   279.9  4760.3  275.42
  4767.7  278.81  4773.8  276.89  4782.6  280.07  4788.7  278.75  4803.5     279
  4809.6  276.33  4833.1  275.53  4904.6  276.16  4910.7  275.52  4925.6  276.96
  4940.4  276.77  4946.5  275.84  4955.2  276.41  4990.9  274.76    4997  273.59
  5044.5  273.67  5060.9  271.83  5061.4  271.33    5068  271.83  5094.5  274.15
  5114.5  274.61  5154.5  278.99  5194.5  279.93  5264.5  284.59  5354.5     287
#Mann= 3 ,-1 , 0
  4394.1     .07       0  5060.9     .05       0    5068     .07       0
Bank Sta=5060.9,5068
XS Rating Curve= 0 ,0
Exp/Cntr=0.3,0.1

Type RM Length L Ch R = 1 ,45986   ,349,349,349
BEGIN DESCRIPTION:
HOOSIER CREEK 83.0
END DESCRIPTION:
XS GIS Cut Line= 3
      2455374.99     13518925.01        2455725.       13518525.
      2455925.01     13518074.97
#Sta/Elev= 30
  4464.5  286.25  4581.9   284.8    4689  283.62  4773.9  283.25  4825.7  283.22
  4861.7  282.11    4876  282.85  4889.7  281.56  4960.4  280.23    4968  276.41
  4988.9  273.86  4992.7  272.43  5014.4  270.78  5014.9  270.28  5021.5  270.78
  5028.2  272.92  5062.4  274.61  5072.6  277.58  5085.6  277.58  5103.4  275.76
  5122.7   276.4  5132.1  276.67  5155.4  279.49  5201.9     279  5207.4  278.13
  5230.6  278.76  5259.3  277.15  5304.5  280.51  5433.8  285.94  5488.5  286.68
#Mann= 8 ,-1 , 0
  4464.5     .12       0  4581.9     .07       0    4689     .12       0
  4773.9     .07       0  5014.4     .05       0  5021.5     .07       0
  5122.7     .12       0  5304.5     .07       0
Bank Sta=5014.4,5021.5
XS Rating Curve= 0 ,0
Exp/Cntr=0.3,0.1

Type RM Length L Ch R = 1 ,45637   ,267,267,267
BEGIN DESCRIPTION:
HOOSIER CREEK 82.0
END DESCRIPTION:
XS GIS Cut Line= 3
      2455974.44     13519055.33      2456014.86     13518374.43
      2456052.43     13518129.09
#Sta/Elev= 30
  4317.9   284.3  4416.4  283.48  4429.1  283.64  4488.5  282.75  4498.5   283.5
  4518.6  282.65  4538.6  282.91  4558.7  282.22  4627.1  281.54  4698.9  281.22
  4739.3  280.36    4779  280.15  4809.1  278.85  4859.2  278.41  4916.1  274.18
  4979.4   270.6  4985.6  268.88  4986.1  268.38  4992.8  268.38  4993.3  268.88
  5002.2  269.01  5009.5  271.64  5034.4  274.43  5039.9  275.49  5097.8  280.61
  5102.8  280.05  5110.7  280.89  5161.1  282.87  5225.6  284.14  5248.2  284.87
#Mann= 8 ,-1 , 0
  4317.9     .07       0  4416.4     .12       0  4429.1     .07       0
  4627.1     .12       0  4739.3     .07       0  4985.6     .05       0
  4993.3     .07       0  5225.6     .12       0
Bank Sta=4985.6,4993.3
XS Rating Curve= 0 ,0
Exp/Cntr=0.3,0.1

Type RM Length L Ch R = 1 ,45370   ,573,573,573
BEGIN DESCRIPTION:
Mapping XS 818b2ff7
END DESCRIPTION:
XS GIS Cut Line= 4
      2456019.01     13519089.27      2456117.98     13518667.36
      2456269.02     13518401.74      2456289.81     13517939.13
#Sta/Elev= 30
  4383.9  285.08  4480.8  283.17  4735.5  281.48  4777.9  280.23  4788.9  278.49
  4819.3  278.57  4823.5  276.96  4839.4  279.64  4866.8     280  4876.9  279.65
    4889  277.67  4898.5  278.13  4904.3  276.46    4935  272.33  4947.5  272.55
  4957.6  271.09  4979.2  271.42  4992.5  269.91    4997  267.05  4997.5  266.55
  5004.7  267.05  5006.6  270.94  5081.6  275.74  5087.3   274.8  5129.6   273.3
  5144.6  275.75  5149.6  274.68  5189.6  277.63  5249.7  279.76  5585.9  285.34
#Mann= 3 ,-1 , 0
  4383.9     .07       0    4997     .05       0  5004.7     .07       0
Bank Sta=4997,5004.7
XS Rating Curve= 0 ,0
Exp/Cntr=0.3,0.1

Type RM Length L Ch R = 1 ,44797   ,569,569,569
BEGIN DESCRIPTION:
Mapping XS 75dfa547
END DESCRIPTION:
XS GIS Cut Line= 4
      2456659.74     13519017.48      2456588.55     13518577.92
      2456531.05     13518226.58      2456418.85     13517938.88
#Sta/Elev= 30
  4198.7  287.01  4282.2  286.87  4318.4  285.54  4448.3   282.2  4525.4  279.11
  4578.9  278.87  4638.4  278.71  4694.7  276.61  4738.1  275.92  4756.1  273.69
  4798.9  271.54  4849.6  271.28  4859.7  270.63  4869.9  270.83  4883.9  272.32
  4961.1  271.29  4991.5  269.26  4998.3  267.66  5008.5  266.74    5009  266.24
  5015.8  266.24  5016.3  266.74  5029.5  272.33  5034.8  272.05    5054  276.86
  5059.3  275.99  5098.3  279.23  5246.9  282.16  5291.5  284.39  5308.8  284.02
#Mann= 5 ,-1 , 0
  4198.7     .07       0  4318.4     .12       0  4578.9     .07       0
  5008.5     .05       0  5016.3     .07       0
Bank Sta=5008.5,5016.3
XS Rating Curve= 0 ,0
Exp/Cntr=0.3,0.1

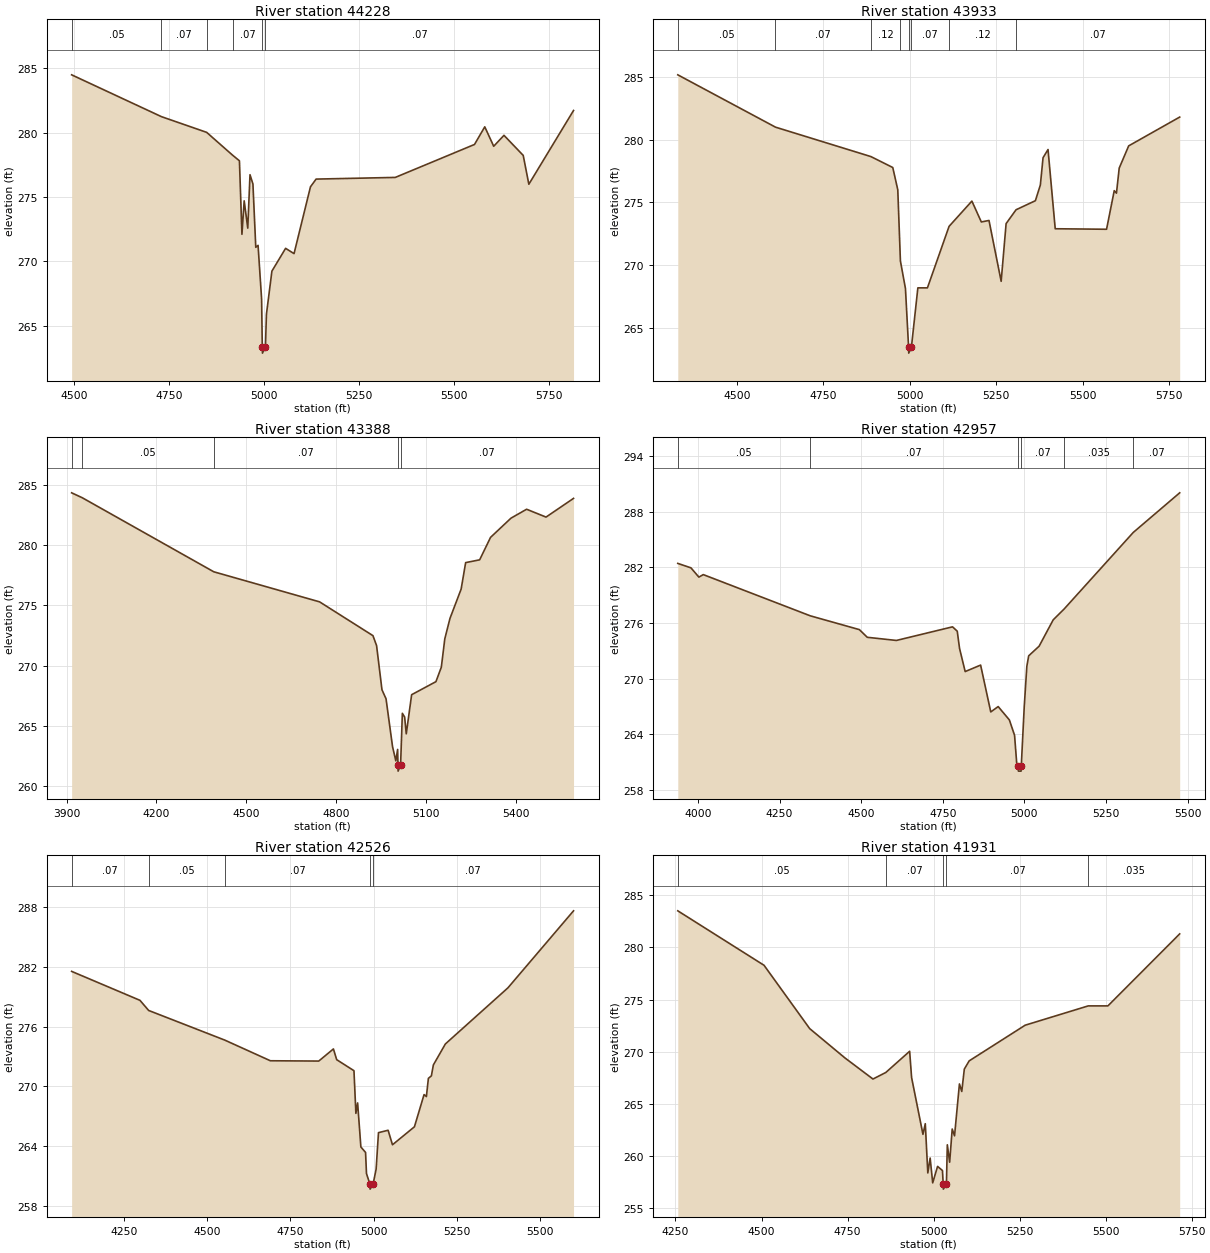
Type RM Length L Ch R = 1 ,44228   ,295,295,295
BEGIN DESCRIPTION:
Mapping XS 9502d692
END DESCRIPTION:
XS GIS Cut Line= 3
      2457260.33     13518837.49      2456973.88     13518386.11
      2456522.49     13517743.75
#Sta/Elev= 30
  4494.2   284.5  4730.4  281.25  4849.3  280.03  4917.3  278.26  4935.4  277.82
    4942  272.11  4947.9  274.71  4957.3  272.59  4963.2  276.74  4970.9  276.02
  4978.4   271.1  4984.4  271.25  4993.7  267.09  4995.5  263.38    4996  262.88
  5003.8  263.38  5006.4   265.9  5020.8  269.25  5056.8  271.02    5079  270.61
  5122.2   275.8    5137   276.4  5345.2  276.53  5553.5  279.09  5580.5  280.46
    5604  278.95    5631   279.8  5681.6  278.24  5696.4     276  5813.9  281.73
#Mann= 6 ,-1 , 0
  4494.2     .05       0  4730.4     .07       0  4849.3     .12       0
  4917.3     .07       0  4995.5     .05       0  5003.8     .07       0
Bank Sta=4995.5,5003.8
XS Rating Curve= 0 ,0
Exp/Cntr=0.3,0.1

Type RM Length L Ch R = 1 ,43933   ,545,545,545
BEGIN DESCRIPTION:
Mapping XS 3ecf0339
END DESCRIPTION:
XS GIS Cut Line= 3
      2457624.89     13518768.02      2457199.57      13518212.5
      2456722.14      13517630.9
#Sta/Elev= 30
  4328.8  285.15  4611.4  280.99  4887.4  278.65  4950.8  277.78  4965.3  276.01
  4972.9  270.35  4987.5  268.15  4996.5  263.52    4997  263.02  5004.8  263.52
  5023.4  268.21  5051.1  268.21  5113.7   273.1  5179.7  275.11    5207  273.45
  5229.2  273.57  5264.4  268.73  5278.7  273.32  5307.5  274.42  5363.4  275.14
  5377.8  276.39  5385.6  278.56    5400  279.21  5420.8  272.91  5569.3  272.87
  5591.6  275.94    5598  275.74  5605.9  277.73  5633.3   279.5  5780.9  281.79
#Mann= 8 ,-1 , 0
  4328.8     .05       0  4611.4     .07       0  4887.4     .12       0
  4972.9     .07       0  4996.5     .05       0  5004.8     .07       0
  5113.7     .12       0  5307.5     .07       0
Bank Sta=4996.5,5004.8
XS Rating Curve= 0 ,0
Exp/Cntr=0.3,0.1

Type RM Length L Ch R = 1 ,43388   ,431,431,431
BEGIN DESCRIPTION:
Mapping XS 696277d9
END DESCRIPTION:
XS GIS Cut Line= 3
      2457885.34     13518637.86      2457407.91     13517830.56
      2456730.85     13517535.43
#Sta/Elev= 30
    3917  284.32  3952.7  283.91  4391.8  277.78  4745.2  275.29  4923.5  272.49
  4935.6  271.67  4953.6  268.01  4967.2  267.26    4989  263.29  4999.9  262.12
  5005.9  263.07    5007  261.77  5007.5  261.27  5015.8  261.77  5021.7  266.06
  5029.3  265.75  5034.8  264.36  5052.7   267.6  5133.9  268.68  5151.9  269.88
  5163.5  272.23  5180.8  273.92  5218.1  276.35  5233.1  278.54  5279.9  278.77
  5316.3  280.63  5384.5  282.22  5436.8  282.96  5501.6  282.31  5593.5  283.86
#Mann= 5 ,-1 , 0
    3917     .07       0  3952.7     .05       0  4391.8     .07       0
    5007     .05       0  5015.8     .07       0
Bank Sta=5007,5015.8
XS Rating Curve= 0 ,0
Exp/Cntr=0.3,0.1

Type RM Length L Ch R = 1 ,42957   ,431,431,431
BEGIN DESCRIPTION:
Mapping XS 79cd8efa
END DESCRIPTION:
XS GIS Cut Line= 3
      2457954.77      13518507.6       2457590.2      13517587.5
      2457321.12      13517110.1
#Sta/Elev= 30
  3938.2  282.44  3978.5  281.96  4002.8  280.96  4016.3  281.23  4344.1  276.78
  4494.5  275.29  4518.8  274.46    4608  274.12    4780  275.59  4794.4  275.12
  4801.5  273.25  4818.7  270.76    4866  271.46  4897.1   266.4  4919.8  266.98
  4954.1  265.54    4970  263.88  4976.7  260.81  4981.3  260.51  4981.8  260.01
    4990  260.01  4990.5  260.51  4999.6  266.94  5007.6  271.33  5013.3  272.46
  5045.2   273.5  5088.5  276.35    5122  277.52  5333.6  285.78  5475.9  290.06
#Mann= 6 ,-1 , 0
  3938.2     .05       0  4344.1     .07       0  4981.3     .05       0
  4990.5     .07       0    5122    .035       0  5333.6     .07       0
Bank Sta=4981.3,4990.5
XS Rating Curve= 0 ,0
Exp/Cntr=0.3,0.1

Type RM Length L Ch R = 1 ,42526   ,595,595,595
BEGIN DESCRIPTION:
Mapping XS 04a83c6a
END DESCRIPTION:
XS GIS Cut Line= 3
       2458215.2     13518412.15      2457972.14     13517561.46
      2457624.92     13517040.62
#Sta/Elev= 30
  4091.3  281.55  4296.9  278.64  4323.1  277.62  4552.1  274.64  4689.5  272.56
  4835.1  272.53  4879.3  273.75  4889.1  272.67  4941.1  271.56  4946.9  267.27
  4952.1  268.32  4961.9  263.89    4976  263.34  4978.8  261.21  4989.2  260.15
  4989.7  259.65  4998.6  260.15  5007.8  261.66  5014.9  265.33  5043.9  265.57
    5057  264.11  5123.1  265.92  5152.1  269.16  5159.1  268.96  5165.1  270.79
  5174.1  271.04  5180.1  272.14  5216.2  274.25  5404.4  279.89    5602  287.64
#Mann= 5 ,-1 , 0
  4091.3     .07       0  4323.1     .05       0  4552.1     .07       0
  4989.2     .05       0  4998.6     .07       0
Bank Sta=4989.2,4998.6
XS Rating Curve= 0 ,0
Exp/Cntr=0.3,0.1

Type RM Length L Ch R = 1 ,41931   ,542,542,542
BEGIN DESCRIPTION:
Mapping XS eeb92918
END DESCRIPTION:
XS GIS Cut Line= 3
      2458675.27     13518290.61      2458536.38     13517613.54
      2458015.85     13517049.63
#Sta/Elev= 30
  4256.7  283.51  4507.4  278.29  4640.1  272.22  4742.2  269.42  4823.9  267.39
  4861.3  268.02  4930.5  270.05  4936.2  267.53  4969.2  262.09    4976  263.11
  4983.3  258.39  4990.1  259.82  4997.5  257.44  5011.7  259.02  5025.9  258.62
    5028  257.34  5028.5  256.84  5037.4  257.34    5040  261.09  5046.8  259.42
  5054.2   262.6    5061  261.95  5075.2  266.92    5082   266.2  5089.4  268.34
  5103.5  269.13  5266.3  272.55  5449.6   274.4  5506.7   274.4  5715.3   281.3
#Mann= 5 ,-1 , 0
  4256.7     .05       0  4861.3     .07       0    5028     .05       0
  5037.4     .07       0  5449.6    .035       0
Bank Sta=5028,5037.4
XS Rating Curve= 0 ,0
Exp/Cntr=0.3,0.1

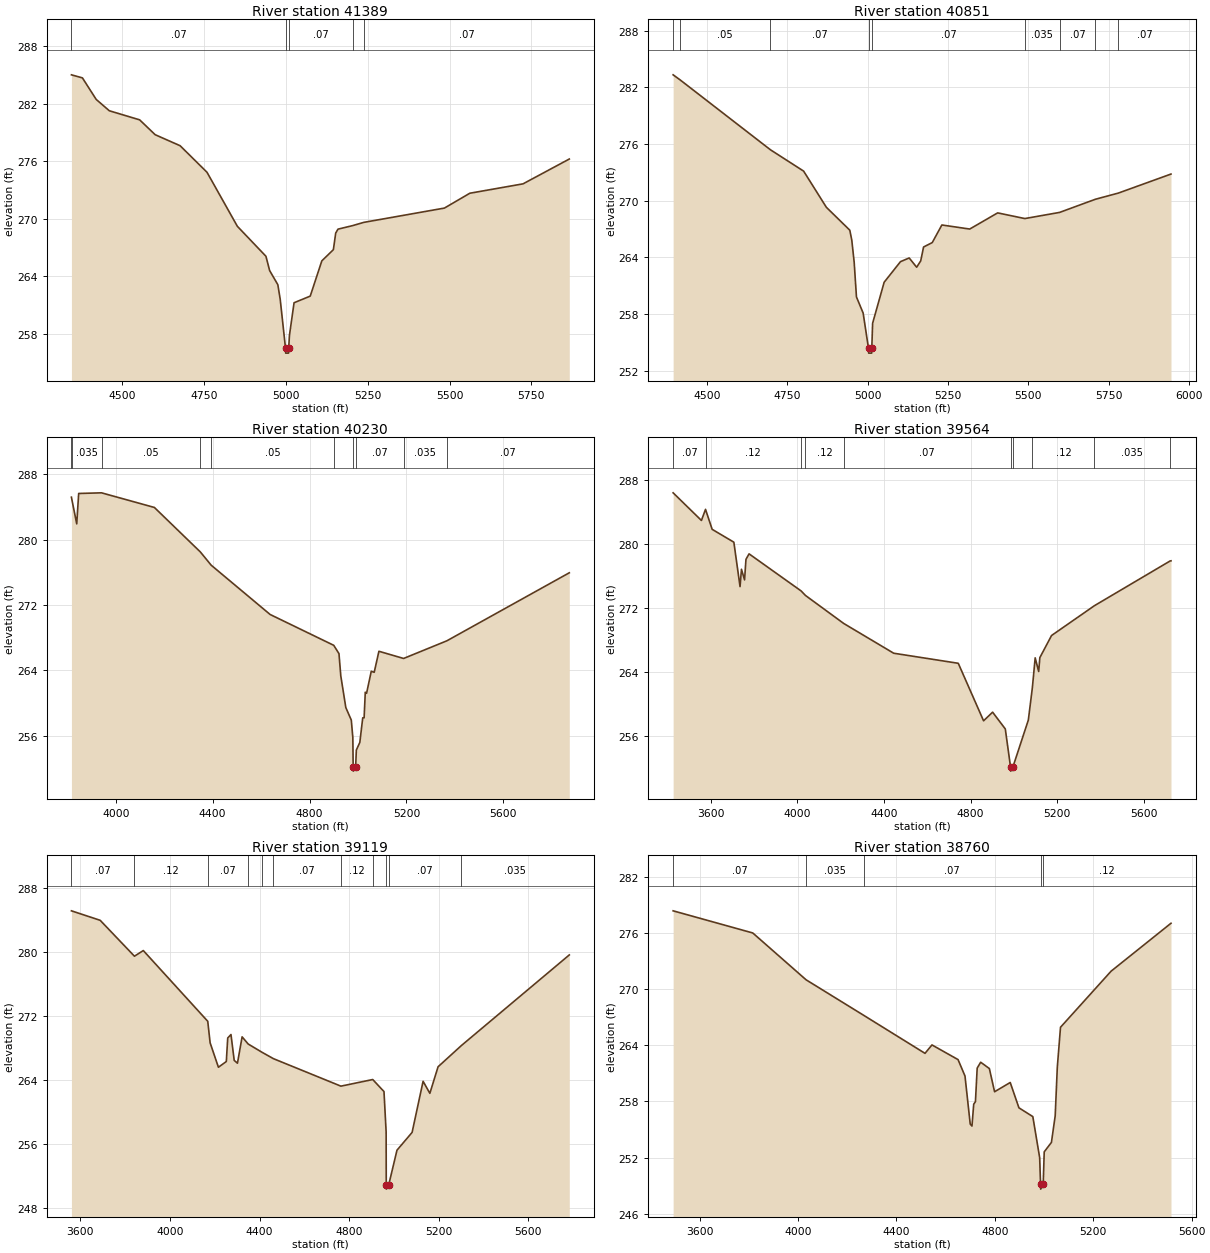
Type RM Length L Ch R = 1 ,41389   ,538,538,538
BEGIN DESCRIPTION:
Mapping XS 90bfda31
END DESCRIPTION:
XS GIS Cut Line= 3
       2459239.5     13518186.44      2459031.17     13517596.18
      2458406.16     13516953.81
#Sta/Elev= 30
    4344  285.02  4377.6   284.7  4419.8  282.45  4459.8  281.27  4552.6  280.32
    4600  278.77  4676.3  277.62  4758.5  274.85  4851.3  269.21  4938.7  266.08
    4950  264.59  4975.1  263.11  4982.3   261.6  4998.6  256.47  4999.1  255.97
  5007.7  255.97  5008.2  256.47  5010.6  257.83  5024.7  261.23  5074.1  261.92
  5109.6   265.6  5144.9  266.77    5152   268.5    5159  268.91  5203.8  269.28
  5238.1  269.62  5484.4  271.11  5562.1  272.66  5724.8  273.64  5866.2  276.23
#Mann= 5 ,-1 , 0
    4344     .07       0  4998.6     .05       0  5008.2     .07       0
  5203.8    .035       0  5238.1     .07       0
Bank Sta=4998.6,5008.2
XS Rating Curve= 0 ,0
Exp/Cntr=0.3,0.1

Type RM Length L Ch R = 1 ,40851   ,621,621,621
BEGIN DESCRIPTION:
Mapping XS dd795f4b
END DESCRIPTION:
XS GIS Cut Line= 3
      2459986.03     13517813.19      2459499.92     13517448.61
      2458719.35     13516919.56
#Sta/Elev= 30
    4394  283.33  4415.9  282.79    4697   275.4  4800.4  273.14  4871.3  269.31
  4944.2  266.89  4950.4  265.84  4957.8  263.52    4965  259.82  4985.8  258.12
  5002.5  254.38    5003  253.88  5012.2  253.88  5012.7  254.38  5015.3  257.04
  5051.2  261.38  5102.1  263.56  5129.2  263.95  5152.5  262.97  5165.1  263.64
    5174  265.11  5201.1  265.58    5231  267.44  5317.8  267.01  5404.7  268.72
  5489.4  268.12  5597.6  268.77    5709  270.16    5781  270.82  5944.6  272.83
#Mann= 9 ,-1 , 0
    4394    .035       0  4415.9     .05       0    4697     .07       0
  5002.5     .05       0  5012.7     .07       0  5489.4    .035       0
  5597.6     .07       0    5709    .035       0    5781     .07       0
Bank Sta=5002.5,5012.7
XS Rating Curve= 0 ,0
Exp/Cntr=0.3,0.1

Type RM Length L Ch R = 1 ,40230   ,666,666,666
BEGIN DESCRIPTION:
Mapping XS b937d869
END DESCRIPTION:
XS GIS Cut Line= 3
      2460472.16     13517639.59      2459525.96     13516893.06
      2458719.33     13516624.18
#Sta/Elev= 30
  3817.1  285.18  3818.8   284.9    3839  281.91    3847  285.63  3941.3  285.71
  4159.6  283.92  4349.3  278.48  4394.1  276.86  4637.4  270.83    4900  267.06
  4921.7  266.04  4929.2  263.32    4950  259.44  4972.5  257.92  4978.9   255.8
  4980.3  252.17  4980.8  251.67  4990.5  252.17  4993.4  254.25  5007.8  255.18
  5019.8  258.19  5025.5  258.19  5030.3  261.32  5035.6  261.19    5055  263.88
  5067.2  263.76  5086.6  266.33  5188.5  265.45  5367.2  267.61  5872.6  275.93
#Mann= 10 ,-1 , 0
  3817.1     .07       0  3818.8    .035       0  3941.3     .05       0
  4349.3    .035       0  4394.1     .05       0    4900     .07       0
  4980.3     .05       0  4990.5     .07       0  5188.5    .035       0
  5367.2     .07       0
Bank Sta=4980.3,4990.5
XS Rating Curve= 0 ,0
Exp/Cntr=0.3,0.1

Type RM Length L Ch R = 1 ,39564   ,445,445,445
BEGIN DESCRIPTION:
Mapping XS cdfb512b
END DESCRIPTION:
XS GIS Cut Line= 3
      2460671.77     13517422.54      2459795.06     13516372.22
      2458935.68     13516016.32
#Sta/Elev= 30
  3426.7  286.45  3557.3  282.99  3576.2  284.38  3606.8  281.88    3707  280.27
  3735.6  274.71  3742.1  276.88  3756.4  275.55  3762.9  278.12  3777.2  278.81
  4017.4  274.17  4037.7   273.6  4214.5  270.09  4444.9  266.37    4743  265.11
  4859.8  257.91  4901.5  258.99  4960.1  256.89  4984.4  252.11  4984.9  251.61
    4995  252.11  5066.5  258.01  5085.2  262.09    5098  265.79  5114.2  264.08
  5119.6  265.82  5173.7  268.59  5371.5  272.32    5721  277.92    5725  277.94
#Mann= 10 ,-1 , 0
  3426.7     .07       0  3576.2     .12       0  4017.4     .07       0
  4037.7     .12       0  4214.5     .07       0  4984.4     .05       0
    4995     .07       0  5085.2     .12       0  5371.5    .035       0
    5721     .07       0
Bank Sta=4984.4,4995
XS Rating Curve= 0 ,0
Exp/Cntr=0.3,0.1

Type RM Length L Ch R = 1 ,39119   ,359,359,359
BEGIN DESCRIPTION:
Mapping XS 746f7c65
END DESCRIPTION:
XS GIS Cut Line= 3
      2460888.78     13517231.56      2460038.12     13516146.53
       2459318.8     13515704.54
#Sta/Elev= 30
  3559.9   285.2  3688.3  284.01  3841.3  279.51  3880.8  280.22  4168.6  271.35
  4179.2  268.65  4216.2  265.59  4251.5  266.31  4257.8  269.26  4272.3  269.69
  4286.7  266.45  4301.2   266.1    4322   269.4  4349.2   268.5  4411.3  267.46
  4461.5  266.67  4763.2  263.22  4905.3  264.05  4955.5  262.54  4965.1  257.47
  4965.6  250.81  4966.1  250.31  4976.3  250.81  5013.5  255.19    5081  257.42
  5130.1  263.83  5160.3  262.32    5197  265.65  5300.7   268.3  5782.9  279.67
#Mann= 11 ,-1 , 0
  3559.9     .07       0  3841.3     .12       0  4168.6     .07       0
  4349.2     .12       0  4411.3    .035       0  4461.5     .07       0
  4763.2     .12       0  4905.3     .07       0  4965.6     .05       0
  4976.3     .07       0  5300.7    .035       0
Bank Sta=4965.6,4976.3
XS Rating Curve= 0 ,0
Exp/Cntr=0.3,0.1

Type RM Length L Ch R = 1 ,38760   ,664,664,664
BEGIN DESCRIPTION:
Mapping XS ae9df6e4
END DESCRIPTION:
XS GIS Cut Line= 3
      2461244.73     13516893.08      2460203.05     13515842.71
      2459700.03     13515634.56
#Sta/Elev= 30
  3492.3   278.4    3816  276.03  4032.7  271.02  4266.2  267.23  4516.1  263.15
  4544.4  264.05  4650.4  262.48  4678.7  260.72  4699.9  255.58    4707  255.37
  4714.1  257.71  4721.1  257.98  4728.2  261.57  4742.4   262.2  4777.7  261.52
  4798.9  259.04  4862.5  260.03  4897.9  257.32  4954.4  256.38  4982.2  251.99
  4985.8  249.12  4986.3  248.62  4996.5  249.12  5000.7  252.61    5030  253.62
  5045.3  256.46  5053.9  261.67  5066.9  265.94  5272.5  271.94    5516  277.07
#Mann= 5 ,-1 , 0
  3492.3     .07       0  4032.7    .035       0  4266.2     .07       0
  4985.8     .05       0  4996.5     .12       0
Bank Sta=4985.8,4996.5
XS Rating Curve= 0 ,0
Exp/Cntr=0.3,0.1

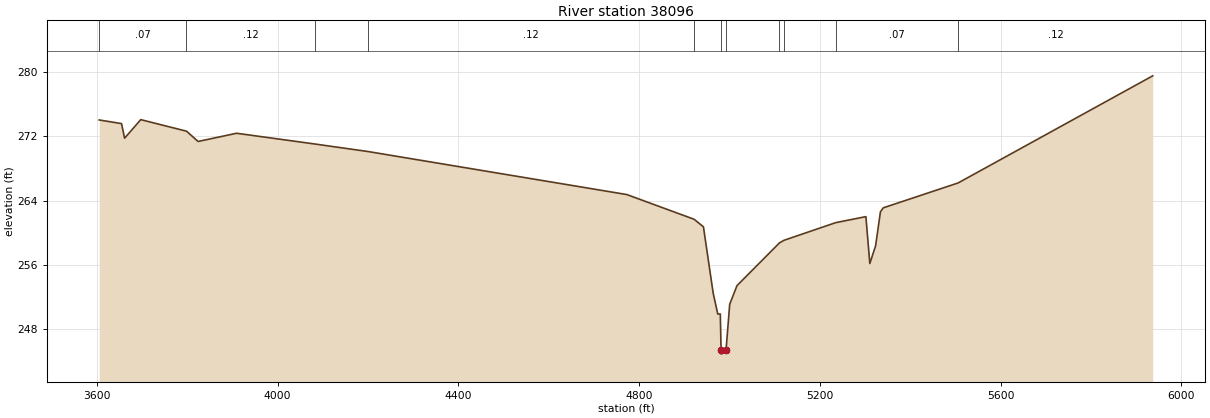
Type RM Length L Ch R = 1 ,38096   ,328,328,328
BEGIN DESCRIPTION:
Mapping XS 2b7f97e4
END DESCRIPTION:
XS GIS Cut Line= 3
      2461765.53     13516754.16       2460758.6     13515825.35
      2459865.17     13515469.71
#Sta/Elev= 30
  3605.3     274  3654.7  273.55  3661.5  271.74  3697.2  274.04  3798.4  272.61
  3824.2  271.33  3909.3  272.35  4083.3  271.01  4200.3  270.08  4772.9  264.74
  4921.9  261.67  4942.5  260.73    4964  252.51  4974.2  249.91  4979.8  249.91
  4981.5  245.43    4982  244.93  4992.5  245.43  5000.6  251.12  5016.7  253.43
  5110.7  258.74  5120.7  259.06  5235.1  261.25    5302     262  5310.7  256.18
  5323.5  258.38  5334.2   262.6  5340.4  263.09  5506.1  266.18  5936.8  279.48
#Mann= 11 ,-1 , 0
  3605.3     .07       0  3798.4     .12       0  4083.3     .07       0
  4200.3     .12       0  4921.9     .07       0  4981.5     .05       0
  4992.5     .07       0  5110.7      .1       0  5120.7     .12       0
  5235.1     .07       0  5506.1     .12       0
Bank Sta=4981.5,4992.5
XS Rating Curve= 0 ,0
Exp/Cntr=0.3,0.1