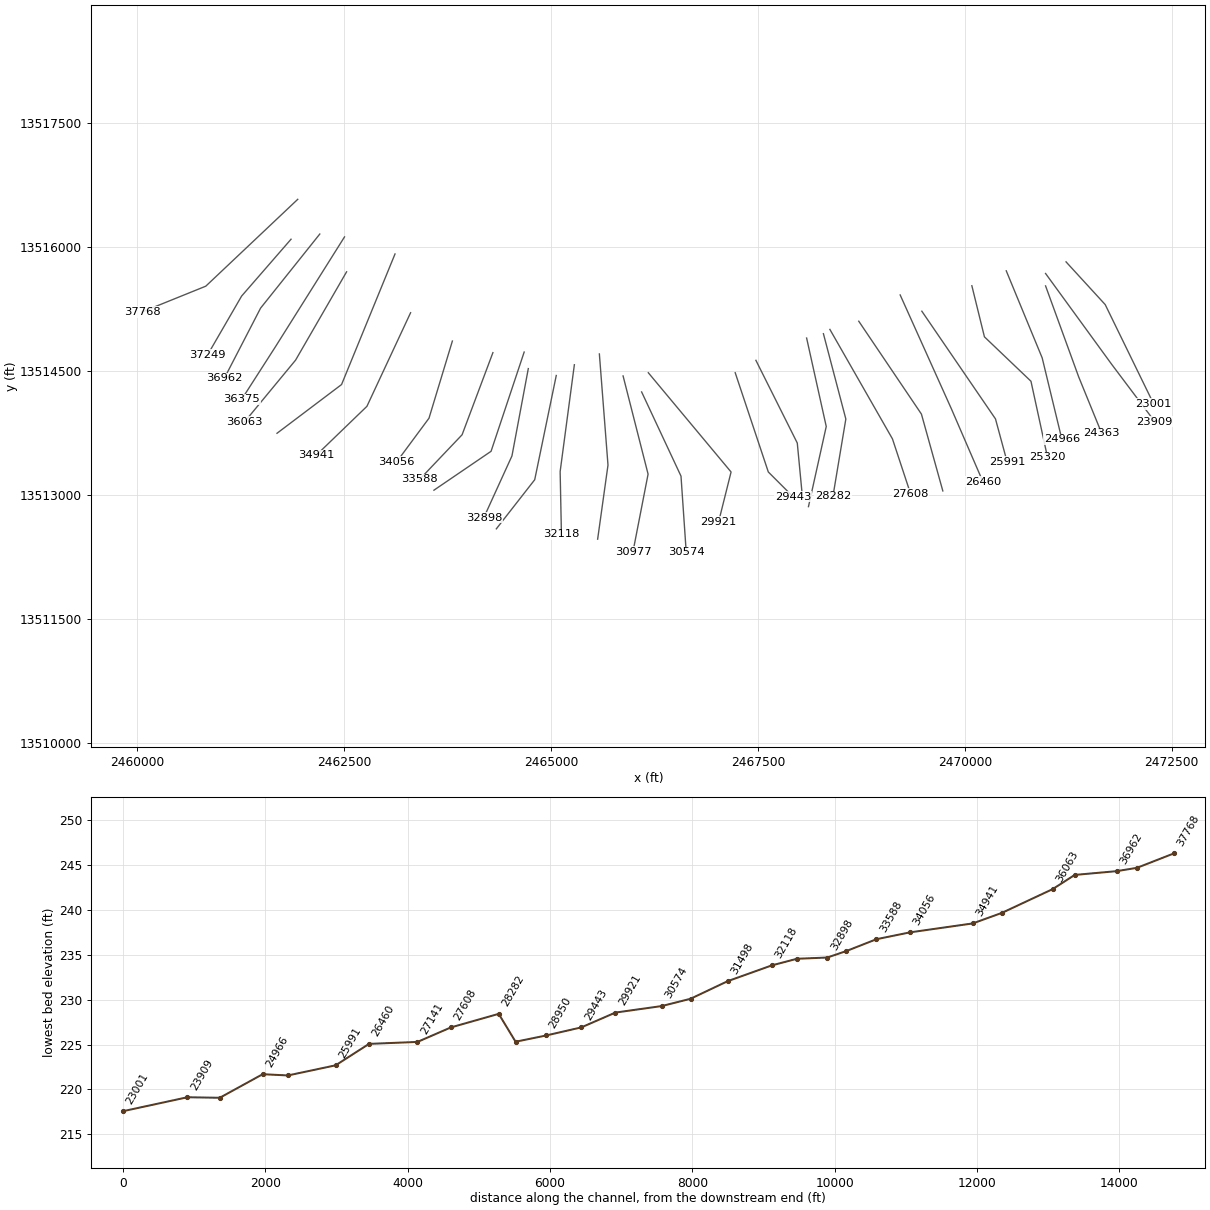
HEC-RAS study HOOSIER CREEK.prj: HOOSIER CREEK Base Level Engineering

--- HOOSIER CREEK.g01 (geometry) --- (continued)

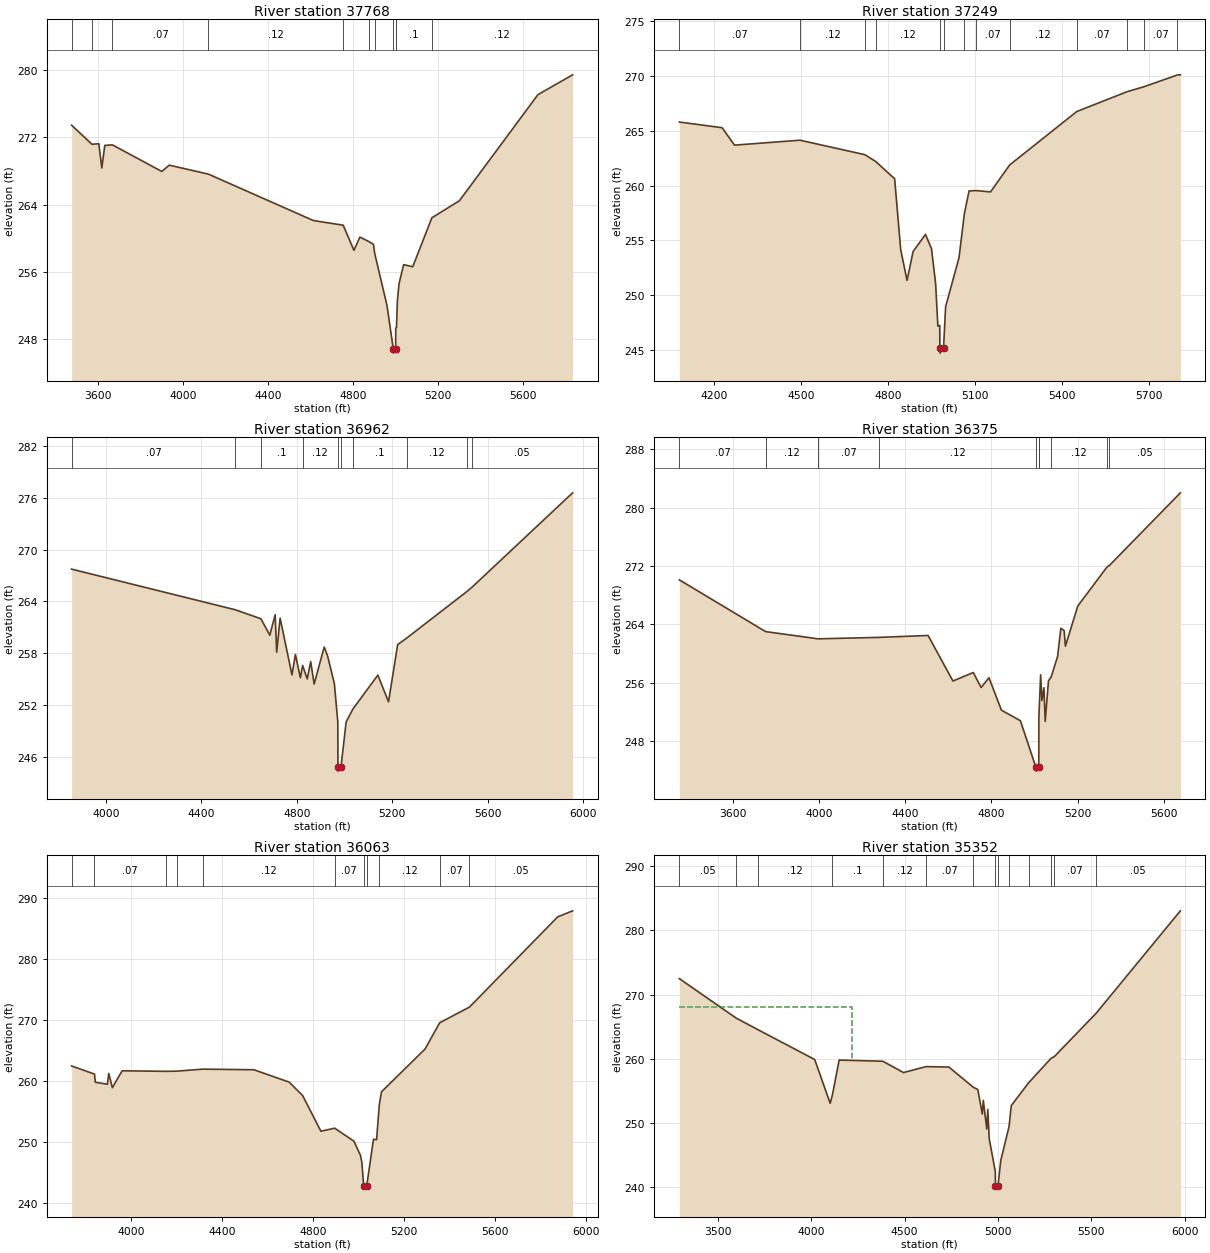
Type RM Length L Ch R = 1 ,37768   ,519,519,519
BEGIN DESCRIPTION:
Mapping XS 1c305c9c
END DESCRIPTION:
XS GIS Cut Line= 3
      2461939.15     13516571.86      2460828.05     13515521.53
      2460056.63      13515209.5
#Sta/Elev= 30
  3473.7  273.46  3569.6  271.19  3601.9  271.25  3616.1  268.37  3630.2  271.05
  3665.8  271.12  3898.8  267.95    3934   268.7  4118.6  267.63  4613.3   262.1
  4753.5  261.55  4804.2  258.56  4832.5  260.13  4873.5  259.61  4896.4  259.27
  4901.5  258.26    4960  251.98  4989.7  246.81  4990.2  246.31  5000.7  246.81
  5001.3  249.29  5004.8  249.37    5009  252.53  5016.7  254.58  5038.6  256.85
  5081.4   256.6  5171.5  262.43  5301.3  264.46  5671.4   277.1  5834.8  279.46
#Mann= 11 ,-1 , 0
  3473.7     .07       0  3569.6     .12       0  3665.8     .07       0
  4118.6     .12       0  4753.5      .1       0  4873.5     .12       0
  4901.5     .07       0  4989.7     .05       0  5000.7     .07       0
  5004.8      .1       0  5171.5     .12       0
Bank Sta=4989.7,5000.7
XS Rating Curve= 0 ,0
Exp/Cntr=0.3,0.1

Type RM Length L Ch R = 1 ,37249   ,287,287,287
BEGIN DESCRIPTION:
Mapping XS f1ac96be
END DESCRIPTION:
XS GIS Cut Line= 3
       2461858.4     13516089.64      2461261.21     13515402.17
       2460851.5     13514693.86
#Sta/Elev= 30
  4079.3   265.8  4226.9  265.28  4269.7  263.69  4495.7  264.14  4719.4  262.82
  4756.3  262.21  4822.3  260.62  4843.2  254.14  4865.1  251.34  4885.9  253.97
  4928.7  255.54  4949.5  254.23  4963.8  251.01  4971.4  247.16    4978  247.23
  4978.3   245.2  4978.8   244.7  4991.1   245.2  4998.2  248.94  5044.4  253.41
  5063.1  257.46  5079.1  259.51  5103.4  259.54  5153.1  259.42  5219.2  261.88
  5450.9  266.76  5624.5  268.57  5682.5  269.02  5798.3   270.1  5808.2  270.11
#Mann= 13 ,-1 , 0
  4079.3     .07       0  4495.7     .12       0  4719.4      .1       0
  4756.3     .12       0  4978.3     .05       0  4991.1     .12       0
  5063.1      .1       0  5103.4     .07       0  5219.2     .12       0
  5450.9     .07       0  5624.5     .12       0  5682.5     .07       0
  5798.3     .05       0
Bank Sta=4978.3,4991.1
XS Rating Curve= 0 ,0
Exp/Cntr=0.3,0.1

Type RM Length L Ch R = 1 ,36962   ,587,587,587
BEGIN DESCRIPTION:
Mapping XS c9ceaaae
END DESCRIPTION:
XS GIS Cut Line= 3
      2462205.68     13516152.21      2461490.37     13515256.34
      2461053.11     13514409.58
#Sta/Elev= 30
    3856  267.73  4542.1  263.02  4649.3  261.98  4686.5  260.08    4709  262.45
  4715.4  258.11  4729.8  262.05  4779.4  255.48  4793.8  257.85  4814.6  255.14
  4824.1  256.57  4843.4  255.01  4857.9  257.01  4872.3  254.42  4914.5   258.7
  4928.3   257.7  4957.1  254.47  4971.5  250.02  4972.1  244.83  4972.6  244.33
  4984.9  244.83  5006.4  250.03  5035.2  251.54  5139.3  255.45    5184  252.36
  5222.3  258.99    5260  259.74  5511.6  265.12  5532.4   265.6  5955.4  276.57
#Mann= 10 ,-1 , 0
    3856     .07       0  4542.1     .12       0  4649.3      .1       0
  4824.1     .12       0  4972.1     .05       0  4984.9     .12       0
  5035.2      .1       0    5260     .12       0  5511.6     .07       0
  5532.4     .05       0
Bank Sta=4972.1,4984.9
XS Rating Curve= 0 ,0
Exp/Cntr=0.3,0.1

Type RM Length L Ch R = 1 ,36375   ,312,312,312
BEGIN DESCRIPTION:
Mapping XS 2eccf98c
END DESCRIPTION:
XS GIS Cut Line= 3
      2462504.26     13516117.44      2461670.93     13514791.06
      2461261.21     13514152.18
#Sta/Elev= 30
    3352  270.11  3752.6  263.02    3996  262.03  4278.6  262.23  4506.5  262.49
  4621.9  256.25  4716.2  257.42  4752.7  255.36  4789.2   256.7  4846.9  252.26
  4935.1  250.81  5007.1  244.41  5007.6  243.91  5020.4  244.41  5020.7  251.26
  5021.8  252.03    5029   257.1  5034.9  253.58  5044.2  255.34  5050.1  250.72
  5065.3  256.28  5077.6  256.79  5107.6  259.62  5122.8  263.48    5138  263.17
  5143.9  261.03  5201.4  266.53    5337  271.87  5348.4  272.09  5677.4  282.03
#Mann= 10 ,-1 , 0
    3352     .07       0  3752.6     .12       0    3996     .07       0
  4278.6     .12       0  5007.1     .05       0  5020.4     .12       0
  5021.8     .07       0  5077.6     .12       0    5337     .07       0
  5348.4     .05       0
Bank Sta=5007.1,5020.4
XS Rating Curve= 0 ,0
Exp/Cntr=0.3,0.1

Type RM Length L Ch R = 1 ,36063   ,711,711,711
BEGIN DESCRIPTION:
Mapping XS b8cfdd6b
END DESCRIPTION:
XS GIS Cut Line= 3
      2462529.45     13515695.17      2461913.12     13514627.43
      2461296.81     13513880.92
#Sta/Elev= 30
  3738.4   262.5    3839  261.17  3842.8  259.83  3895.9   259.5  3901.7  261.27
  3917.4  258.94  3960.5  261.71  4153.3  261.62  4199.6  261.65  4314.7  261.98
  4539.2  261.88  4694.3  259.85  4753.2  257.65  4833.6   251.8  4893.9  252.31
  4978.5  250.18  5007.2  247.86  5013.7  246.66  5021.4  242.82  5021.9  242.32
  5034.7  242.82  5064.5  250.49  5078.1  250.41  5090.2  256.18  5099.7  258.27
  5291.2  265.28  5355.3  269.58  5486.2  272.15  5873.6  286.93  5939.3  287.92
#Mann= 11 ,-1 , 0
  3738.4     .12       0    3839     .07       0  4153.3     .12       0
  4199.6     .07       0  4314.7     .12       0  4893.9     .07       0
  5021.4     .05       0  5034.7     .07       0  5090.2     .12       0
  5355.3     .07       0  5486.2     .05       0
Bank Sta=5021.4,5034.7
XS Rating Curve= 0 ,0
Exp/Cntr=0.3,0.1

Type RM Length L Ch R = 1 ,35352   ,411,411,411
BEGIN DESCRIPTION:
Mapping XS 3a22769b
END DESCRIPTION:
XS GIS Cut Line= 3
      2463114.55     13515911.22      2462468.67     13514332.29
       2461688.7     13513742.98
#Sta/Elev= 30
  3293.4  272.48  3598.9  266.31    3714  264.53  4018.6  259.87  4101.4  253.05
  4113.7  254.41  4149.4  259.79  4383.7   259.6    4494  257.84    4615  258.77
  4737.1   258.7  4867.6  255.56    4892   255.2    4916  251.38  4921.4  253.51
    4940  249.05  4945.4   252.1  4953.2  247.52  4985.6  242.44  4986.7  240.18
  4987.2  239.68  5000.1  240.18    5015  244.14  5059.4  249.43  5071.2  252.69
  5163.6  256.23  5284.2  260.05  5301.6  260.32  5525.5  267.07  5976.9  283.04
#Mann= 14 ,-1 , 0
  3293.4     .05       0  3598.9     .07       0    3714     .12       0
  4113.7      .1       0  4383.7     .12       0    4615     .07       0
  4867.6     .12       0  4986.7     .05       0  5000.1     .12       0
  5059.4      .1       0  5163.6     .07       0  5284.2     .12       0
  5301.6     .07       0  5525.5     .05       0
#XS Ineff= 2 , 0
       0  4218.5     268               0
Permanent Ineff=
       F       F
Bank Sta=4986.7,5000.1
XS Rating Curve= 0 ,0
Exp/Cntr=0.3,0.1

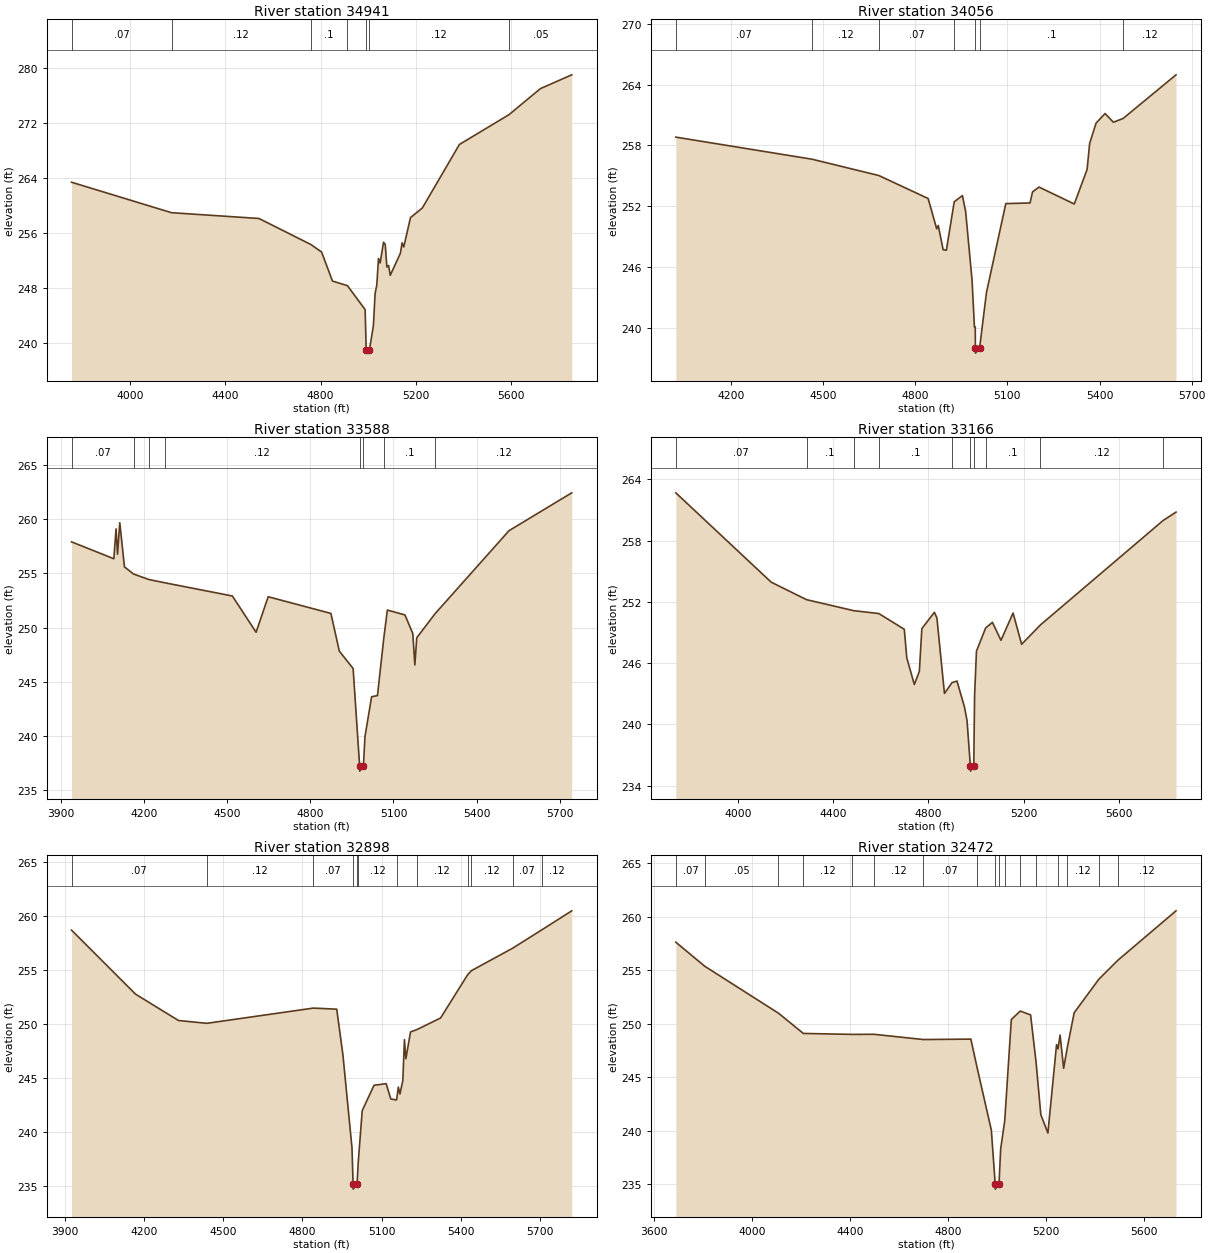
Type RM Length L Ch R = 1 ,34941   ,885,885,885
BEGIN DESCRIPTION:
Mapping XS ab2131df
END DESCRIPTION:
XS GIS Cut Line= 3
      2463302.85     13515200.74       2462775.1     13514068.84
      2462164.72     13513479.28
#Sta/Elev= 30
  3755.6  263.35  4174.9  258.92  4541.5  258.08  4759.5  254.29  4804.1   253.2
  4849.8  248.98  4912.5  248.31  4986.7  244.83  4991.2     239  4991.7   238.5
  5004.8     239  5021.3  242.49  5028.5  247.17  5035.5  248.37  5042.7  252.27
  5049.6  251.61  5063.8  254.62    5071  254.33  5077.9  251.02  5085.1  251.24
  5092.1  249.82  5134.5  253.02  5141.7  254.54  5148.7  253.94    5177  258.21
  5226.6  259.61    5382  268.84  5590.1  273.18  5721.6  276.96  5853.1  278.97
#Mann= 7 ,-1 , 0
  3755.6     .07       0  4174.9     .12       0  4759.5      .1       0
  4912.5     .12       0  4991.2     .05       0  5004.8     .12       0
  5590.1     .05       0
Bank Sta=4991.2,5004.8
XS Rating Curve= 0 ,0
Exp/Cntr=0.3,0.1

Type RM Length L Ch R = 1 ,34056   ,468,468,468
BEGIN DESCRIPTION:
HOOSIER CREEK 57.0
END DESCRIPTION:
XS GIS Cut Line= 3
      2463807.64     13514858.32        2463525.       13513925.
      2463136.09     13513399.43
#Sta/Elev= 30
  4020.1  258.82  4463.9  256.64  4681.3  255.03  4841.9  252.76  4869.6  249.77
  4874.8   250.1  4890.8   247.7  4901.2  247.66  4926.8  252.44  4953.5  253.05
  4963.9  251.48  4984.8  244.72  4992.7  240.06  4995.3  240.06  4995.7     238
  4996.2   237.5  5009.4     238  5031.8  243.49  5094.8  252.26  5173.7  252.32
  5181.9  253.42    5203  253.89  5317.8  252.22  5359.5  255.63  5367.9  258.21
  5388.7   260.2    5418  261.15  5445.1  260.29  5476.7  260.66  5649.1  264.97
#Mann= 7 ,-1 , 0
  4020.1     .07       0  4463.9     .12       0  4681.3     .07       0
  4926.8      .1       0  4995.7     .05       0  5009.4      .1       0
  5476.7     .12       0
Bank Sta=4995.7,5009.4
XS Rating Curve= 0 ,0
Exp/Cntr=0.3,0.1

Type RM Length L Ch R = 1 ,33588   ,422,422,422
BEGIN DESCRIPTION:
HOOSIER CREEK 56.0
END DESCRIPTION:
XS GIS Cut Line= 3
      2464297.23     13514717.72        2463925.       13513725.
      2463413.36     13513186.94
#Sta/Elev= 30
  3939.8  257.92  4092.2  256.36  4100.2  259.12  4105.5  256.78  4113.6  259.69
  4130.5  255.61  4163.1  254.95  4218.7  254.44  4275.9  254.14  4519.4  252.92
  4604.9  249.57  4648.5  252.85  4874.5  251.31  4904.8  247.83  4954.6  246.22
    4978  237.24  4978.5  236.74  4991.7  237.24  4997.3  239.93  5021.2  243.61
  5042.3  243.72  5064.9  248.97  5077.9  251.62  5141.4  251.17  5169.7  249.45
    5177  246.55  5183.9  249.06  5250.2  251.29  5516.3  258.95  5742.5  262.45
#Mann= 8 ,-1 , 0
  3939.8     .07       0  4163.1     .12       0  4218.7     .07       0
  4275.9     .12       0    4978     .05       0  4991.7     .12       0
  5064.9      .1       0  5250.2     .12       0
Bank Sta=4978,4991.7
XS Rating Curve= 0 ,0
Exp/Cntr=0.3,0.1

Type RM Length L Ch R = 1 ,33166   ,268,268,268
BEGIN DESCRIPTION:
HOOSIER CREEK 55.0
END DESCRIPTION:
XS GIS Cut Line= 3
        2464675.     13514724.99        2464275.       13513525.
      2463584.79     13513054.71
#Sta/Elev= 30
  3739.2  262.67  4139.7  253.92  4287.9  252.21  4486.4  251.13  4591.4  250.85
  4698.4  249.31    4709   246.5  4740.6   243.9  4761.7  245.19  4772.2  249.38
  4824.9  250.97  4835.4  250.42  4867.1  243.03    4899  244.09  4919.8  244.24
  4951.4  241.67  4961.9  240.37  4975.9  235.92  4976.4  235.42  4990.1  235.92
  4993.6  242.83  5001.5  247.17  5040.1  249.44  5068.5  249.99  5104.4  248.23
  5155.2   250.9  5191.1  247.84  5269.8  249.73  5785.1  259.96  5839.3  260.78
#Mann= 10 ,-1 , 0
  3739.2     .07       0  4287.9      .1       0  4486.4     .12       0
  4591.4      .1       0    4899     .12       0  4975.9     .05       0
  4990.1     .12       0  5040.1      .1       0  5269.8     .12       0
  5785.1     .07       0
Bank Sta=4975.9,4990.1
XS Rating Curve= 0 ,0
Exp/Cntr=0.3,0.1

Type RM Length L Ch R = 1 ,32898   ,426,426,426
BEGIN DESCRIPTION:
HOOSIER CREEK 54.0
END DESCRIPTION:
XS GIS Cut Line= 3
      2464724.99     13514524.97      2464527.55     13513469.27
      2464187.47     13512723.01
#Sta/Elev= 30
    3926  258.69  4167.9  252.77  4330.9  250.32  4438.1  250.06  4841.5  251.47
  4930.2  251.37  4953.5  247.16  4987.9  238.54  4992.1   235.2  4992.6   234.7
  5007.1   235.2  5011.7  237.21  5026.7  241.97  5071.3  244.32  5117.4  244.47
  5134.9  243.05  5156.7  242.96  5163.5  244.15  5169.5  243.51  5180.5  244.76
  5186.5  248.55    5192  246.78  5209.6  249.26  5234.8  249.49  5323.4  250.55
  5425.4  254.54  5439.7  254.93  5595.8  257.01  5705.6   258.7  5820.1  260.48
#Mann= 12 ,-1 , 0
    3926     .07       0  4438.1     .12       0  4841.5     .07       0
  4992.1     .05       0  5007.1     .07       0  5011.7     .12       0
  5156.7      .1       0  5234.8     .12       0  5425.4     .07       0
  5439.7     .12       0  5595.8     .07       0  5705.6     .12       0
Bank Sta=4992.1,5007.1
XS Rating Curve= 0 ,0
Exp/Cntr=0.3,0.1

Type RM Length L Ch R = 1 ,32472   ,354,354,354
BEGIN DESCRIPTION:
Mapping XS 6be22fa3
END DESCRIPTION:
XS GIS Cut Line= 3
      2465062.85     13514441.62      2464802.44     13513181.25
      2464338.87     13512587.47
#Sta/Elev= 30
  3688.6  257.62  3806.9  255.37  4107.4  250.99  4208.7   249.1  4409.2  249.01
  4496.7  249.02  4698.4  248.53    4892  248.57  4917.5  245.91  4975.6  240.07
  4991.3  235.06  4991.8  234.56    5007  235.06  5013.6   238.3  5030.2  240.94
  5057.1   250.4  5093.5  251.19  5135.7  250.83  5158.1  246.41  5177.4  241.52
  5206.3   239.8  5241.6  248.06  5247.6  247.65    5256  248.95  5270.5  245.84
  5286.1  247.85  5313.4  251.03    5414  254.16  5491.5  255.93  5728.9  260.55
#Mann= 17 ,-1 , 0
  3688.6     .07       0  3806.9     .05       0  4107.4     .07       0
  4208.7     .12       0  4409.2     .07       0  4496.7     .12       0
  4698.4     .07       0  4917.5     .12       0  4991.3     .05       0
    5007     .12       0  5030.2     .07       0  5093.5      .1       0
  5158.1     .12       0  5247.6      .1       0  5286.1     .12       0
    5414     .07       0  5491.5     .12       0
Bank Sta=4991.3,5007
XS Rating Curve= 0 ,0
Exp/Cntr=0.3,0.1

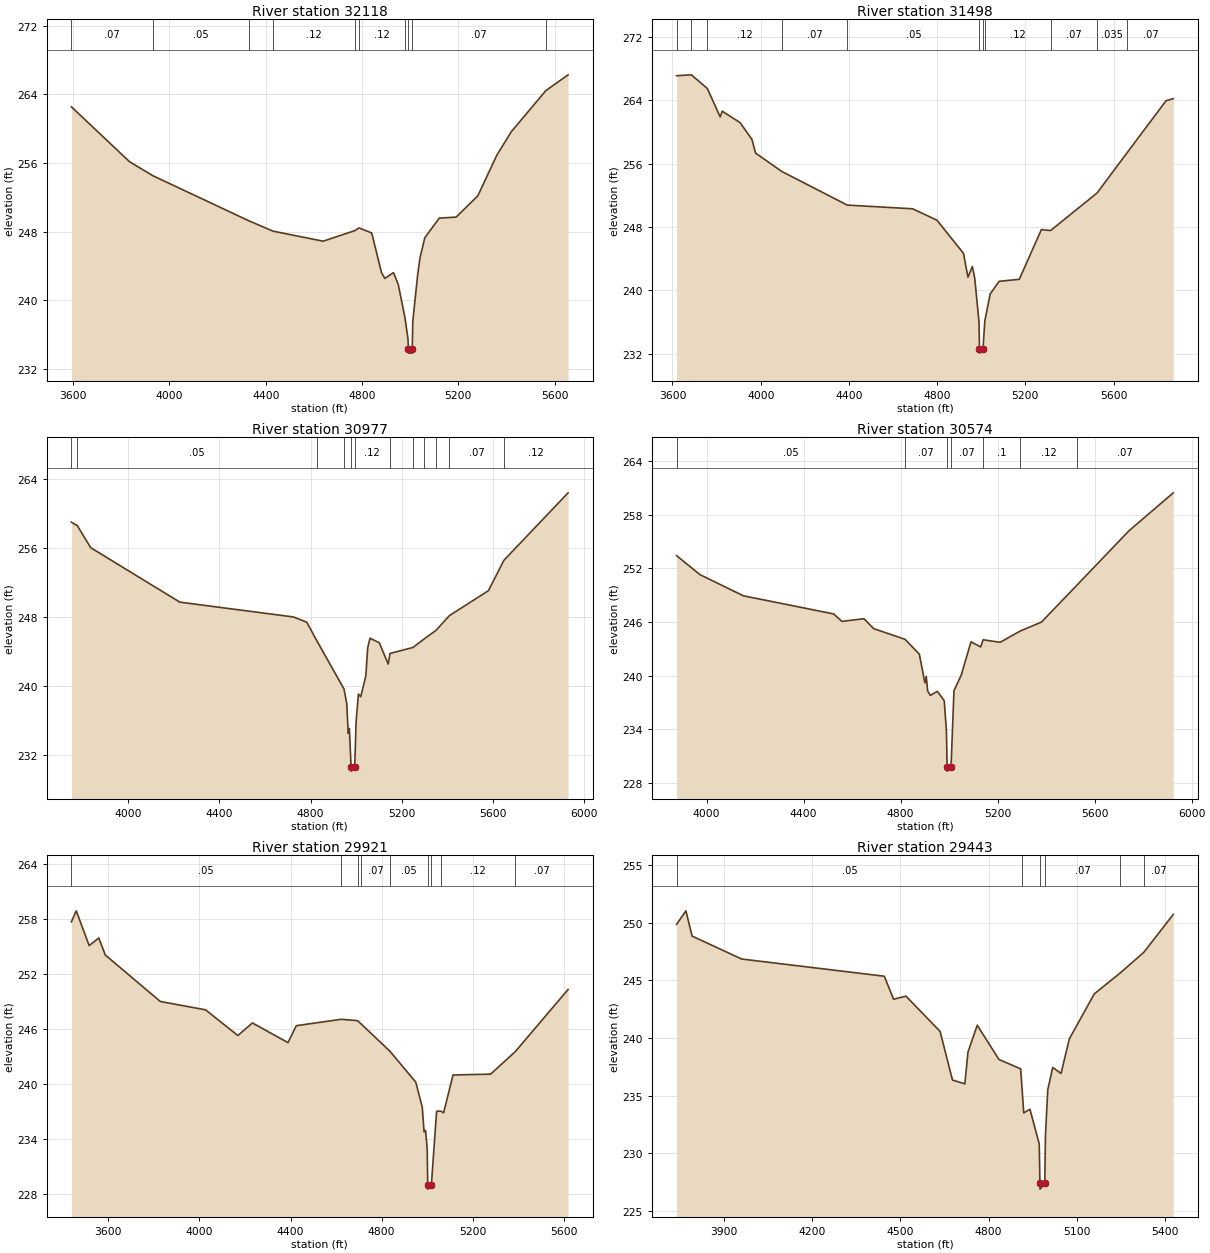
Type RM Length L Ch R = 1 ,32118   ,620,620,620
BEGIN DESCRIPTION:
Mapping XS 6a34f936
END DESCRIPTION:
XS GIS Cut Line= 3
       2465281.6     13514571.86      2465109.73     13513280.21
      2465125.35     13512519.91
#Sta/Elev= 30
  3592.7  262.56  3834.5  256.15  3931.9  254.51  4330.8  249.25  4430.6  248.05
  4638.7  246.88  4771.2  248.12  4787.2  248.43  4840.5  247.84  4880.8  243.23
  4894.7  242.54    4931  243.21    4951  241.79  4978.2     238    4991   235.5
  4993.1  234.32  4993.6  233.82  5008.3  233.82  5008.8  234.32    5011   237.5
    5031  242.89    5041  244.94    5061  247.29    5121  249.57    5191  249.69
    5281  252.16    5361  256.96  5421.1  259.68  5563.5  264.44  5656.2  266.29
#Mann= 10 ,-1 , 0
  3592.7     .07       0  3931.9     .05       0  4330.8     .07       0
  4430.6     .12       0  4771.2     .07       0  4787.2     .12       0
  4978.2     .07       0  4993.1     .05       0  5008.8     .07       0
  5563.5    .035       0
Bank Sta=4993.1,5008.8
XS Rating Curve= 0 ,0
Exp/Cntr=0.3,0.1

Type RM Length L Ch R = 1 ,31498   ,521,521,521
BEGIN DESCRIPTION:
Mapping XS 17f18328
END DESCRIPTION:
XS GIS Cut Line= 3
      2465583.69     13514702.04      2465687.86     13513358.33
      2465562.86     13512462.55
#Sta/Elev= 30
  3618.7   267.1  3685.6  267.21  3757.9  265.49  3816.3   261.9  3825.5  262.62
  3906.6  261.17  3960.4  259.05  3976.8  257.33  4094.7  255.02  4392.4  250.76
  4688.9  250.29  4799.3  248.85  4919.6  244.66  4939.7  241.65  4959.7     243
  4970.6  241.51    4990  235.96  4992.1  232.56  4992.6  232.06    5008  232.56
  5016.3  236.15  5040.5  239.52  5080.9  241.13  5172.4  241.38  5272.7  247.66
  5314.4  247.54  5525.7   252.3  5662.7  257.42  5838.1  263.94  5870.9   264.2
#Mann= 11 ,-1 , 0
  3618.7     .12       0  3685.6     .07       0  3757.9     .12       0
  4094.7     .07       0  4392.4     .05       0  4992.1     .05       0
    5008     .05       0  5016.3     .12       0  5314.4     .07       0
  5525.7    .035       0  5662.7     .07       0
Bank Sta=4992.1,5008
XS Rating Curve= 0 ,0
Exp/Cntr=0.3,0.1

Type RM Length L Ch R = 1 ,30977   ,403,403,403
BEGIN DESCRIPTION:
Mapping XS 68b2f520
END DESCRIPTION:
XS GIS Cut Line= 3
      2465870.16     13514436.42      2466172.23     13513248.96
      2465989.97     13512311.59
#Sta/Elev= 30
  3750.3  259.02    3776  258.63  3835.1  256.06  4226.4  249.73    4725  248.01
  4783.6   247.4  4829.4  245.16    4947  239.64    4959  237.95  4965.4   234.5
  4970.5  235.06    4978   230.6  4978.5   230.1  4993.9   230.6    5000  235.83
  5010.2  239.05  5020.4  238.74  5042.7  241.16  5050.9  244.42  5061.1  245.54
  5101.9  245.01    5141  242.54    5149  243.77    5250  244.47  5297.5  245.43
    5351  246.46  5409.8  248.17  5580.7  251.06  5648.8  254.59  5930.5  262.43
#Mann= 12 ,-1 , 0
  3750.3     .12       0    3776     .05       0  4829.4     .07       0
    4947     .12       0    4978     .05       0  4993.9     .12       0
    5149      .1       0    5250     .12       0  5297.5     .07       0
    5351     .12       0  5409.8     .07       0  5648.8     .12       0
Bank Sta=4978,4993.9
XS Rating Curve= 0 ,0
Exp/Cntr=0.3,0.1

Type RM Length L Ch R = 1 ,30574   ,653,653,653
BEGIN DESCRIPTION:
HOOSIER CREEK 49.0
END DESCRIPTION:
XS GIS Cut Line= 3
      2466094.27     13514242.73      2466570.03     13513224.94
      2466633.31     13512302.71
#Sta/Elev= 30
  3876.5  253.42  3973.3  251.29  4152.6  248.92  4523.7   246.9  4558.4  246.06
    4649  246.36  4689.1  245.25  4818.6  244.05  4877.4  242.38  4900.3  239.17
  4905.8   239.9  4911.6  238.27  4922.7  237.77  4951.5  238.23  4979.9  237.18
  4988.9  233.85  4991.9  229.79  4992.4  229.29  5008.1  229.79    5020  238.29
  5050.1  240.04  5090.2  243.77  5130.2   243.2  5140.2     244  5210.4  243.72
  5293.8  244.99  5380.8  245.98  5528.5  250.16  5741.7  256.21  5924.4  260.46
#Mann= 7 ,-1 , 0
  3876.5     .05       0  4818.6     .07       0  4991.9     .05       0
  5008.1     .07       0  5140.2      .1       0  5293.8     .12       0
  5528.5     .07       0
Bank Sta=4991.9,5008.1
XS Rating Curve= 0 ,0
Exp/Cntr=0.3,0.1

Type RM Length L Ch R = 1 ,29921   ,478,478,478
BEGIN DESCRIPTION:
HOOSIER CREEK 48.0
END DESCRIPTION:
XS GIS Cut Line= 3
      2466174.98     13514475.03        2467175.       13513275.
      2467024.99     13512674.95
#Sta/Elev= 30
  3437.9  257.69  3459.4  258.89    3516   255.1  3558.3  255.93    3587  254.07
  3828.4  249.01    4027   248.1  4168.8   245.3  4232.6  246.67  4388.8  244.53
  4425.3  246.37  4622.5  247.07  4694.2  246.92  4710.5  246.55  4835.9   243.6
  4949.9  240.22  4978.5  237.46  4986.3  234.78  4992.8  234.96    5000  232.98
  5002.2  229.06  5002.7  228.56  5018.4  229.06  5041.2  237.04  5058.5  237.07
  5072.1  236.88  5113.4     241  5278.3  241.09  5386.1  243.53  5618.5  250.32
#Mann= 9 ,-1 , 0
  3437.9     .05       0  4622.5     .07       0  4694.2     .05       0
  4710.5     .07       0  4835.9     .05       0  5002.2     .05       0
  5018.4     .05       0  5058.5     .12       0  5386.1     .07       0
Bank Sta=5002.2,5018.4
XS Rating Curve= 0 ,0
Exp/Cntr=0.3,0.1

Type RM Length L Ch R = 1 ,29443   ,493,493,493
BEGIN DESCRIPTION:
HOOSIER CREEK 47.0
END DESCRIPTION:
XS GIS Cut Line= 3
      2467224.99     13514475.04        2467625.       13513275.
      2467924.99     13512975.01
#Sta/Elev= 30
  3738.9  249.87  3770.6  251.04  3791.6  248.85  3960.3  246.86  4445.2  245.37
  4476.8  243.38    4519  243.64  4634.9  240.59  4677.1  236.37  4719.2  236.04
  4729.8  238.79  4761.4  241.12  4835.2  238.15    4909  237.34    4914  235.52
  4919.5  233.52  4940.6  233.83  4972.2  230.83  4974.5  227.41    4975  226.91
    4991  227.41  4993.3  231.55  5001.2  235.52    5018  237.46  5046.3  236.94
  5074.6  239.94  5159.4  243.84  5246.5  245.63  5327.7  247.44  5428.1  250.73
#Mann= 6 ,-1 , 0
  3738.9     .05       0    4914     .07       0  4974.5     .05       0
    4991     .07       0  5246.5    .035       0  5327.7     .07       0
Bank Sta=4974.5,4991
XS Rating Curve= 0 ,0
Exp/Cntr=0.3,0.1

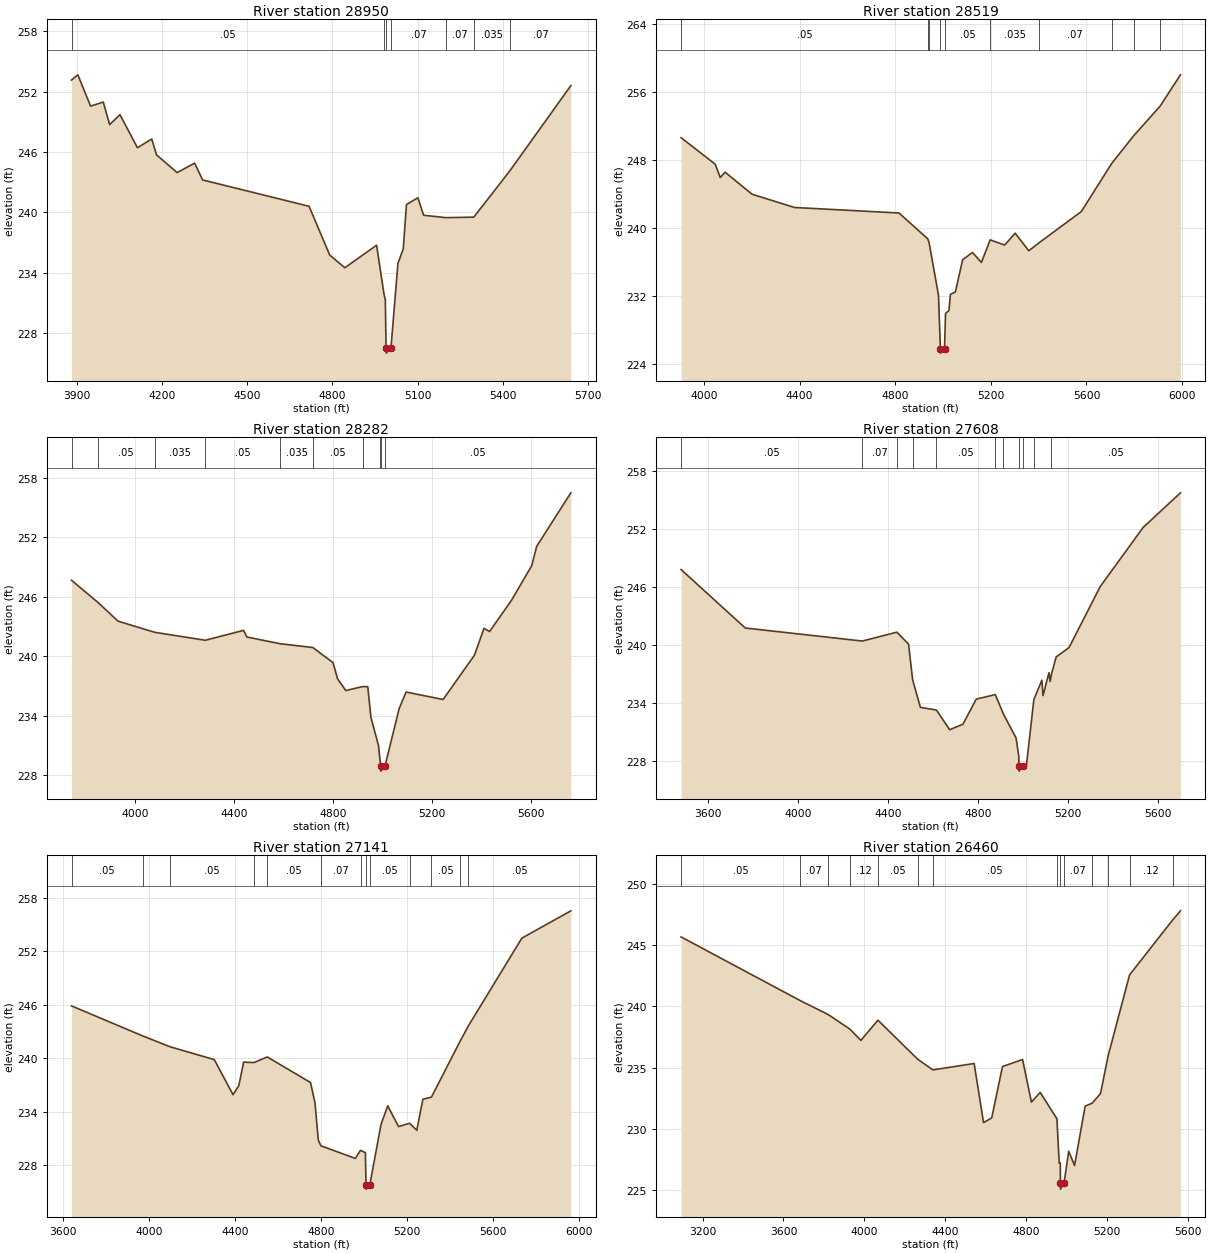
Type RM Length L Ch R = 1 ,28950   ,431,431,431
BEGIN DESCRIPTION:
HOOSIER CREEK 46.0
END DESCRIPTION:
XS GIS Cut Line= 3
      2467475.01     13514624.98        2467975.       13513625.
      2468035.56     13512989.19
#Sta/Elev= 30
    3882  253.16  3904.3  253.68  3949.1  250.57  3993.8  250.97  4016.1  248.73
  4052.5  249.72    4114  246.43  4164.3   247.3  4181.1  245.72  4253.7  243.96
  4315.2   244.9  4343.2  243.23  4717.7  240.61  4790.4  235.76  4843.5   234.5
  4955.3  236.74  4980.7  231.99    4986  231.29  4988.6  226.51  4989.1  226.01
  5005.8  226.51  5030.2  234.91    5049  236.37  5060.3  240.78  5100.5  241.46
  5120.6  239.72  5198.5  239.48  5297.2  239.53  5423.7  244.12  5638.7  252.61
#Mann= 7 ,-1 , 0
    3882     .05       0  4980.7     .07       0  4988.6     .05       0
  5005.8     .07       0  5198.5     .07       0  5297.2    .035       0
  5423.7     .07       0
Bank Sta=4988.6,5005.8
XS Rating Curve= 0 ,0
Exp/Cntr=0.3,0.1

Type RM Length L Ch R = 1 ,28519   ,237,237,237
BEGIN DESCRIPTION:
HOOSIER CREEK 45.0
END DESCRIPTION:
XS GIS Cut Line= 3
      2468087.71      13514894.7        2468325.       13513825.
      2468110.12     13512855.94
#Sta/Elev= 30
  3904.7  250.65  4047.8  247.52  4068.3  245.96  4088.8  246.59  4201.4     244
  4378.9  242.44    4816  241.79  4936.2  238.75  4941.7  238.33  4981.2  232.12
  4989.2  225.81  4989.7  225.31  5006.4  225.81  5010.6  229.98  5024.8  230.31
  5031.1  232.24  5051.6  232.49  5082.3   236.3  5123.3  237.15  5160.6  235.97
  5197.2  238.63    5258  238.02  5301.6  239.41  5358.9  237.35  5400.5  238.26
  5578.5  241.96  5705.3  247.61  5796.7  250.85  5908.6  254.38    5993  258.04
#Mann= 10 ,-1 , 0
  3904.7     .05       0  4936.2     .07       0  4941.7     .05       0
  4989.2     .05       0  5006.4     .05       0  5197.2    .035       0
  5400.5     .07       0  5705.3    .035       0  5796.7     .07       0
  5908.6    .035       0
Bank Sta=4989.2,5006.4
XS Rating Curve= 0 ,0
Exp/Cntr=0.3,0.1

Type RM Length L Ch R = 1 ,28282   ,674,674,674
BEGIN DESCRIPTION:
Mapping XS e639490b
END DESCRIPTION:
XS GIS Cut Line= 3
      2468290.83     13514946.79      2468561.68      13513915.5
      2468405.59     13512978.98
#Sta/Elev= 30
  3743.6  247.66  3849.5  245.44  3931.6  243.53    4080  242.41  4283.6  241.61
  4438.2  242.61  4451.3  241.94  4585.9  241.26  4717.7  240.88  4799.1  239.36
  4817.8  237.71  4850.9  236.54  4918.3  236.94  4939.4  236.93  4952.3  233.83
  4982.7  231.01  4989.2  229.48  4991.6  228.92  4992.1  228.42  5008.9  228.92
  5066.1  234.72  5094.2  236.39  5243.6  235.64  5370.3  240.11  5408.5  242.81
  5431.1  242.49    5520  245.65  5601.1  249.12  5621.4  251.08  5759.3  256.47
#Mann= 10 ,-1 , 0
  3743.6    .035       0  3849.5     .05       0    4080    .035       0
  4283.6     .05       0  4585.9    .035       0  4717.7     .05       0
  4918.3    .035       0  4989.2     .05       0  4991.6     .05       0
  5008.9     .05       0
Bank Sta=4991.6,5008.9
XS Rating Curve= 0 ,0
Exp/Cntr=0.3,0.1

Type RM Length L Ch R = 1 ,27608   ,467,467,467
BEGIN DESCRIPTION:
HOOSIER CREEK 44.0
END DESCRIPTION:
XS GIS Cut Line= 3
      2468368.98     13514998.81        2469125.       13513675.
      2469342.92      13513014.5
#Sta/Elev= 30
  3479.5  247.79  3764.9  241.73  4285.3  240.38  4438.6   241.3  4490.7  240.07
    4509  236.36  4543.3  233.51  4614.8  233.23  4673.5  231.19  4732.6  231.76
  4791.6  234.36  4876.4  234.83  4912.8   232.8  4968.7  230.34  4980.9  228.44
  4981.5   227.4    4982   226.9    4999   227.4  5014.5  227.44  5047.9  234.32
  5083.4  236.33  5088.6  234.73  5115.1   237.1  5120.4  236.19  5125.7   236.9
  5146.9  238.73  5204.1   239.7  5342.7  246.02  5533.2  252.14  5699.5  255.74
#Mann= 11 ,-1 , 0
  3479.5     .05       0  4285.3     .07       0  4438.6     .05       0
    4509     .07       0  4614.8     .05       0  4876.4     .07       0
  4912.8     .05       0  4981.5     .05       0    4999     .05       0
  5047.9     .07       0  5125.7     .05       0
Bank Sta=4981.5,4999
XS Rating Curve= 0 ,0
Exp/Cntr=0.3,0.1

Type RM Length L Ch R = 1 ,27141   ,681,681,681
BEGIN DESCRIPTION:
HOOSIER CREEK 43.0
END DESCRIPTION:
XS GIS Cut Line= 3
      2468717.92      13515097.8        2469475.       13513975.
      2469733.56     13513045.69
#Sta/Elev= 30
  3641.5  245.88  3971.5  242.51  4098.6  241.29  4304.6  239.84  4391.5   235.9
  4418.6  236.93  4440.9  239.56  4488.5  239.51  4550.5  240.14  4751.3  237.27
  4772.3  234.97  4787.3  230.83  4799.2  230.16  4959.5  228.74  4983.5  229.65
  5006.1  229.39  5009.1  225.79  5009.6  225.29  5026.8  225.79  5078.7  232.56
  5109.9  234.65  5160.1  232.32  5211.4  232.69  5244.8   231.9  5273.1  235.39
    5313  235.63  5443.4  241.79  5484.8  243.65  5732.7  253.49  5960.3  256.56
#Mann= 13 ,-1 , 0
  3641.5     .05       0  3971.5     .07       0  4098.6     .05       0
  4488.5     .07       0  4550.5     .05       0  4799.2     .07       0
  4983.5     .05       0  5009.1     .05       0  5026.8     .05       0
  5211.4     .07       0    5313     .05       0  5443.4     .12       0
  5484.8     .05       0
Bank Sta=5009.1,5026.8
XS Rating Curve= 0 ,0
Exp/Cntr=0.3,0.1

Type RM Length L Ch R = 1 ,26460   ,469,469,469
BEGIN DESCRIPTION:
Mapping XS d68e5fa0
END DESCRIPTION:
XS GIS Cut Line= 3
      2469218.07     13515415.65      2469838.04     13514036.27
      2470217.24     13513158.69
#Sta/Elev= 30
  3093.9  245.67  3681.3  240.48  3820.9  239.33  3927.6  238.15  3982.7  237.22
  4066.8  238.87  4264.2  235.67  4338.7  234.81  4542.5  235.33  4588.9   230.5
  4629.4  230.89  4682.6  235.08  4781.9  235.66  4825.5  232.18    4869  232.97
  4951.7  230.81  4962.9   227.2  4968.3  227.21    4969  225.57  4969.5  225.07
  4986.9  225.57  5009.9  228.16  5038.8     227  5091.2  231.85  5125.9  232.09
  5167.2  232.88  5204.7  235.95  5310.8  242.57  5525.5  247.09  5562.2   247.8
#Mann= 14 ,-1 , 0
  3093.9     .05       0  3681.3     .07       0  3820.9     .05       0
  3927.6     .12       0  4066.8     .05       0  4264.2     .07       0
  4338.7     .05       0  4951.7     .07       0    4969     .05       0
  4986.9     .07       0  5125.9     .05       0  5204.7     .07       0
  5310.8     .12       0  5525.5     .05       0
Bank Sta=4969,4986.9
XS Rating Curve= 0 ,0
Exp/Cntr=0.3,0.1

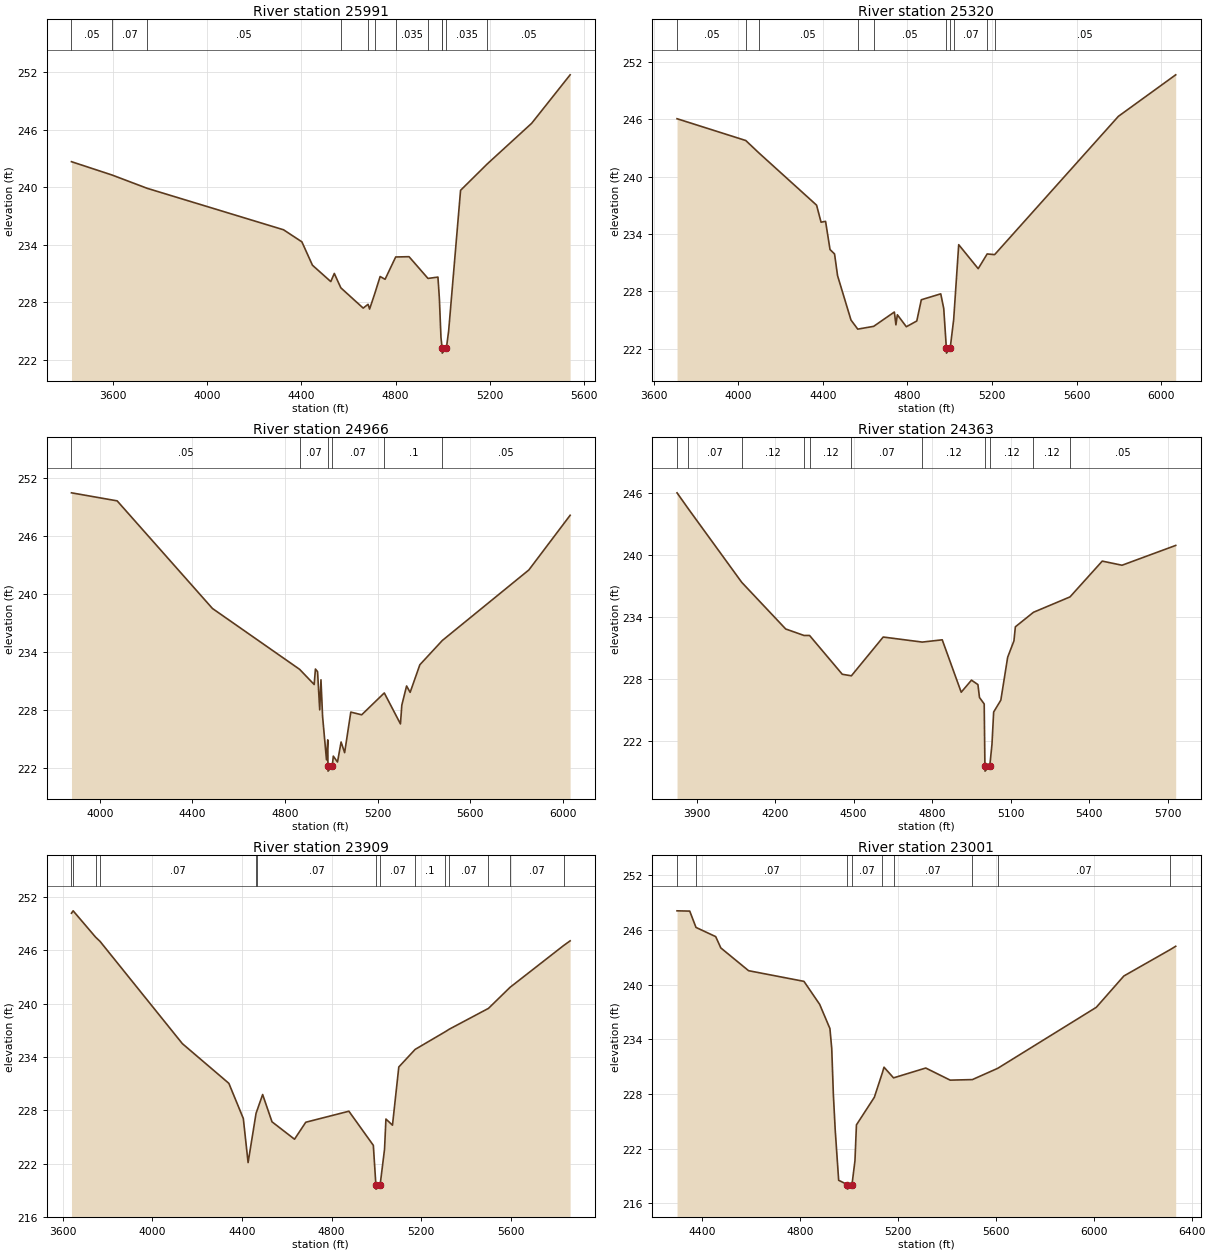
Type RM Length L Ch R = 1 ,25991   ,671,671,671
BEGIN DESCRIPTION:
Mapping XS ddff3da5
END DESCRIPTION:
XS GIS Cut Line= 3
        2469480.     13515218.96      2470369.73     13513916.91
      2470510.39     13513397.53
#Sta/Elev= 30
    3425  242.67  3596.9  241.28  3746.1  239.89  4324.5  235.56  4402.3   234.3
  4447.1  231.86  4524.9  230.15  4539.8     231  4567.5   229.5  4662.4  227.38
  4683.1  227.78  4689.5  227.28  4710.7  228.84  4734.2  230.68  4755.2  230.39
  4800.2  232.72  4856.8  232.75  4937.2  230.48  4979.4  230.62  4985.5  228.39
  4992.2  224.33  4996.4  223.36  4997.2  223.18  4997.7  222.68  5015.1  223.18
  5024.7  224.97  5075.4  239.68  5189.2  242.45    5377  246.68  5540.1  251.74
#Mann= 12 ,-1 , 0
    3425     .05       0  3596.9     .07       0  3746.1     .05       0
  4567.5     .07       0  4683.1     .05       0  4710.7     .07       0
  4800.2    .035       0  4937.2     .07       0  4996.4    .035       0
  4997.2    .035       0  5015.1    .035       0  5189.2     .05       0
Bank Sta=4997.2,5015.1
XS Rating Curve= 0 ,0
Exp/Cntr=0.3,0.1

Type RM Length L Ch R = 1 ,25320   ,354,354,354
BEGIN DESCRIPTION:
Mapping XS 89943b0c
END DESCRIPTION:
XS GIS Cut Line= 4
      2470084.28     13515527.03      2470236.23     13514909.09
      2470798.49     13514372.16      2470999.07     13513450.33
#Sta/Elev= 30
  3711.2  246.06  4036.2  243.78  4096.9  242.51  4370.9  237.02    4392  235.24
  4413.3  235.33  4434.4  232.38  4455.8  231.92    4470  229.65  4533.5  225.01
  4565.4  224.06  4640.7  224.35  4738.5  225.85  4745.8  224.51  4752.7  225.56
  4795.2  224.31  4844.5  224.91  4865.9  227.13  4957.8  227.75  4971.9  226.22
  4984.4  222.05  4984.9  221.55  5002.3  222.05  5018.9  225.07  5042.7  232.89
  5134.8  230.38  5177.2  231.92  5212.5  231.85  5797.5  246.31  6068.4  250.65
#Mann= 10 ,-1 , 0
  3711.2     .05       0  4036.2     .07       0  4096.9     .05       0
  4565.4     .07       0  4640.7     .05       0  4984.4     .05       0
  5002.3     .05       0  5018.9     .07       0  5177.2      .1       0
  5212.5     .05       0
Bank Sta=4984.4,5002.3
XS Rating Curve= 0 ,0
Exp/Cntr=0.3,0.1

Type RM Length L Ch R = 1 ,24966   ,603,603,603
BEGIN DESCRIPTION:
Mapping XS 21f054be
END DESCRIPTION:
XS GIS Cut Line= 3
      2470499.93      13515707.3      2470933.96     13514654.76
      2471172.36     13513668.69
#Sta/Elev= 30
  3877.5  250.45  4074.7  249.62  4486.1   238.5  4862.5  232.21  4925.4  230.64
  4930.8  232.24    4940  231.97  4949.3  228.02  4954.7  231.13  4961.7  227.34
  4978.6  222.85  4984.1  224.92  4984.8  222.19  4985.3  221.69  5003.4  222.19
    5008  223.24  5026.1  222.63  5041.6   224.7  5056.9   223.6  5083.5  227.79
  5130.5  227.51  5228.1  229.77  5297.9  226.57  5303.8  228.51  5324.4  230.49
  5339.7  229.83  5381.6  232.68  5478.6  235.19  5852.3  242.48  6030.5  248.13
#Mann= 6 ,-1 , 0
  3877.5     .05       0  4862.5     .07       0  4984.8     .05       0
  5003.4     .07       0  5228.1      .1       0  5478.6     .05       0
Bank Sta=4984.8,5003.4
XS Rating Curve= 0 ,0
Exp/Cntr=0.3,0.1

Type RM Length L Ch R = 1 ,24363   ,454,454,454
BEGIN DESCRIPTION:
HOOSIER CREEK 37.0
END DESCRIPTION:
XS GIS Cut Line= 3
      2470974.99     13515525.02        2471375.       13514425.
      2471652.11     13513745.21
#Sta/Elev= 30
  3825.4  246.04  3868.3   244.5  4072.6  237.36  4240.4  232.84  4310.6  232.21
  4331.6  232.21  4456.5  228.45  4491.3   228.3  4612.8  232.06  4762.1  231.57
  4838.3  231.79  4910.8  226.71    4950  227.88  4974.6  227.45  4980.6   226.2
  4998.6  225.57  5001.3  219.56  5001.8  219.06  5019.9  219.56  5028.3  221.67
  5034.7  224.79  5062.1  225.94  5088.2   230.1  5112.2  231.69  5117.6  233.05
  5186.8  234.46  5326.3  235.95  5449.5  239.42    5525  239.02    5730  240.94
#Mann= 11 ,-1 , 0
  3825.4     .05       0  3868.3     .07       0  4072.6     .12       0
  4310.6     .07       0  4331.6     .12       0  4491.3     .07       0
  4762.1     .12       0  5001.3     .05       0  5019.9     .12       0
  5186.8     .12       0  5326.3     .05       0
Bank Sta=5001.3,5019.9
XS Rating Curve= 0 ,0
Exp/Cntr=0.3,0.1

Type RM Length L Ch R = 1 ,23909   ,908,908,908
BEGIN DESCRIPTION:
HOOSIER CREEK 36.0
END DESCRIPTION:
XS GIS Cut Line= 3
      2470975.01     13515674.99        2471775.       13514575.
      2472294.46     13513884.13
#Sta/Elev= 30
  3639.6  250.18  3647.1  250.45  3747.4  247.48  3767.1  247.01  4134.2   235.5
  4341.7  231.03  4406.2  227.07  4427.5  222.11    4463  227.65  4467.7  227.99
  4492.4  229.77  4534.1   226.7  4634.6  224.74  4684.8  226.65  4877.2  227.89
  4986.2  224.05  4997.5  219.62    4998  219.12  5016.6  219.62  5036.2  223.61
  5042.4  227.01  5071.6  226.32  5099.8  232.87  5172.7  234.85  5307.1  236.84
  5325.3  237.13  5499.9  239.47  5595.7  241.83  5835.4  246.55  5864.1  247.07
#Mann= 14 ,-1 , 0
  3639.6     .05       0  3647.1     .07       0  3747.4     .05       0
  3767.1     .07       0    4463     .12       0  4467.7     .07       0
  4997.5     .05       0  5016.6     .07       0  5172.7      .1       0
  5307.1     .12       0  5325.3     .07       0  5499.9      .1       0
  5595.7     .07       0  5835.4     .05       0
Bank Sta=4997.5,5016.6
XS Rating Curve= 0 ,0
Exp/Cntr=0.3,0.1

Type RM Length L Ch R = 1 ,23001   ,330,330,330
BEGIN DESCRIPTION:
Mapping XS 1e275f45
END DESCRIPTION:
XS GIS Cut Line= 3
      2471222.43     13515815.52       2471695.5     13515299.05
      2472281.43     13514096.82
#Sta/Elev= 30
  4297.1   248.1    4349  248.07  4374.5  246.28  4455.1  245.27    4476  244.03
  4589.5  241.53  4815.8  240.36  4879.9  237.84  4921.9  235.18  4929.3  232.98
    4936  227.91  4943.4  224.09  4957.6  218.53  4992.9  218.06  4993.4  217.56
  5012.1  218.06  5024.2  220.68  5030.2  224.61  5103.4  227.64  5136.2  230.33
  5142.9  230.94  5181.9  229.77  5313.5  230.85  5413.3  229.52  5504.1  229.58
  5607.8  230.82  6010.4  237.51  6123.1  240.95  6311.6  243.83  6334.9  244.21
#Mann= 9 ,-1 , 0
  4297.1     .05       0  4374.5     .07       0  4992.9     .05       0
  5012.1     .07       0  5136.2     .12       0  5181.9     .07       0
  5504.1     .12       0  5607.8     .07       0  6311.6     .05       0
Bank Sta=4992.9,5012.1
XS Rating Curve= 0 ,0
Exp/Cntr=0.3,0.1