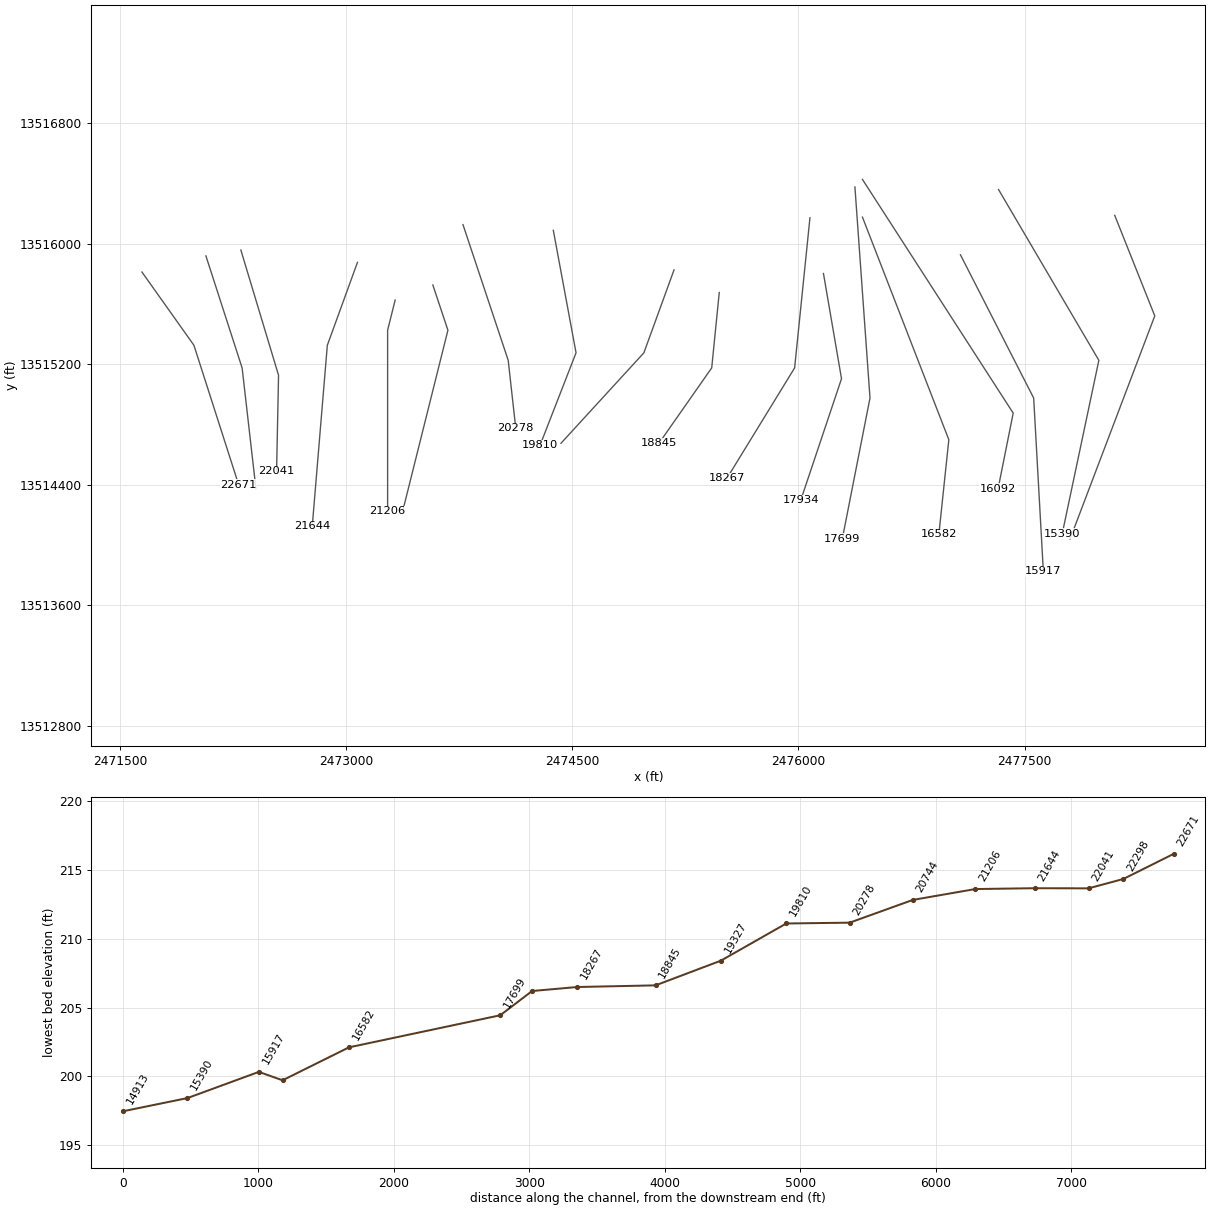
HEC-RAS study HOOSIER CREEK.prj: HOOSIER CREEK Base Level Engineering

--- HOOSIER CREEK.g01 (geometry) --- (continued)

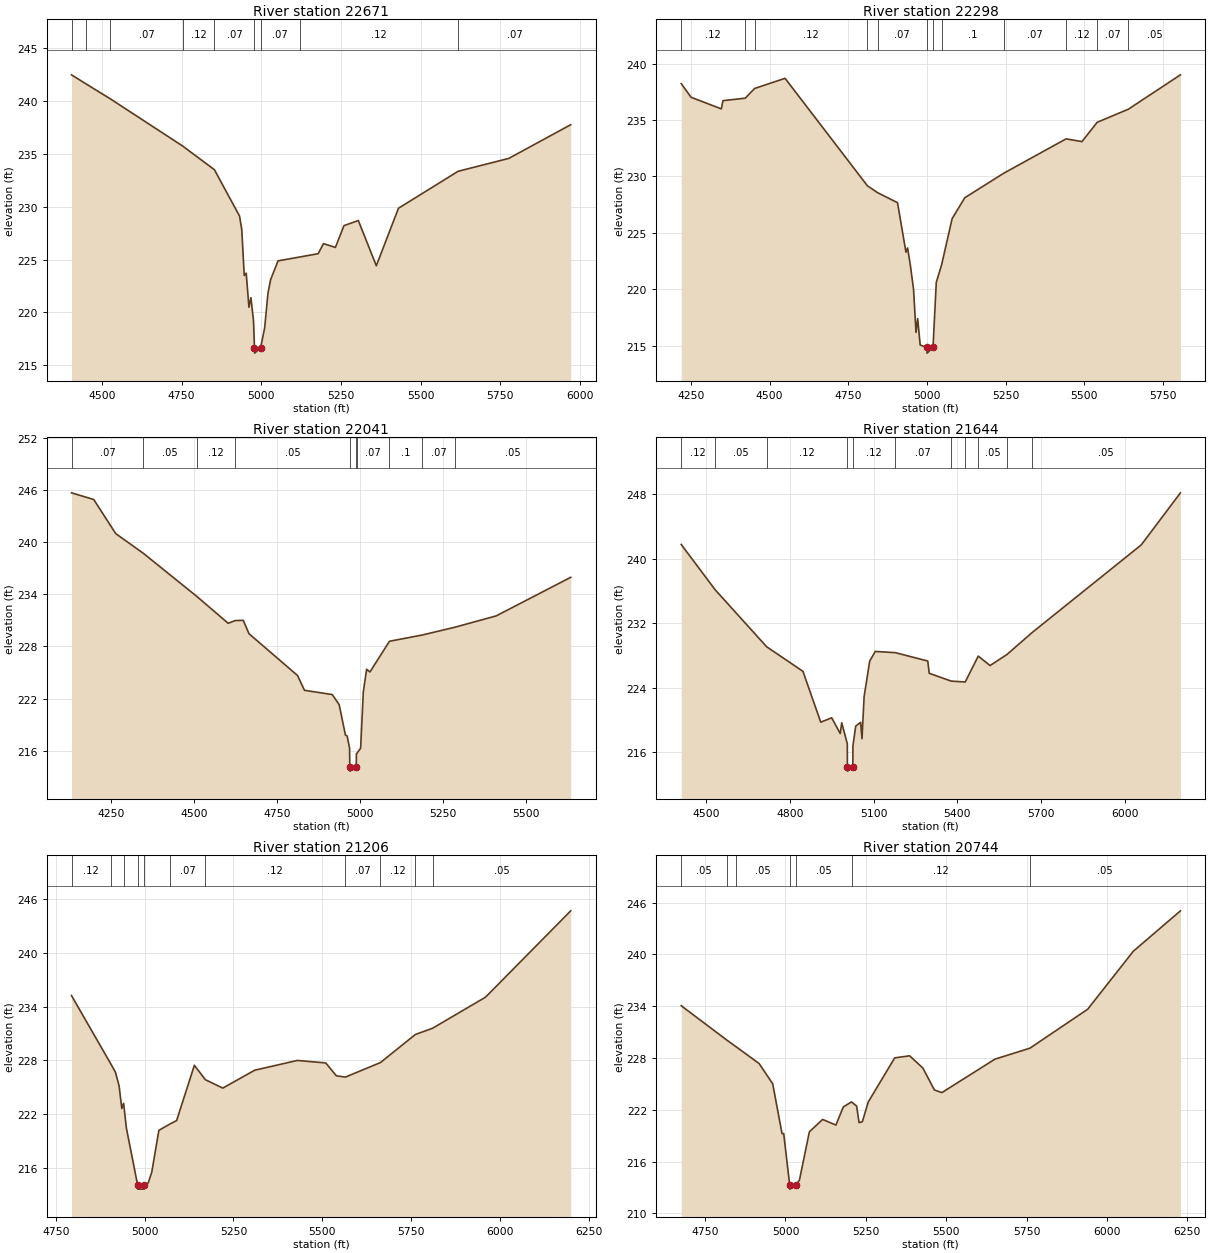
Type RM Length L Ch R = 1 ,22671   ,373,373,373
BEGIN DESCRIPTION:
HOOSIER CREEK 35.0
END DESCRIPTION:
XS GIS Cut Line= 3
      2471645.15     13515810.93      2471990.04     13515325.11
       2472286.8     13514400.04
#Sta/Elev= 30
  4404.2  242.44  4448.9   241.6  4525.2  240.19    4753  235.72  4852.9  233.48
  4931.8   229.1  4938.8  227.81  4946.5  223.49  4952.7  223.71  4961.3  220.49
  4967.4   221.4  4975.6  219.22  4978.7  216.66  4979.2  216.16  4997.9  216.66
  5010.6  218.55  5021.1  221.84  5029.5  223.11  5052.6  224.87  5121.2  225.24
  5178.6  225.55  5195.3   226.5  5232.7  226.14  5259.6   228.2  5304.7  228.68
  5361.2  224.41  5430.7  229.84  5617.9  233.33  5777.3  234.55  5971.5  237.73
#Mann= 9 ,-1 , 0
  4404.2     .07       0  4448.9     .12       0  4525.2     .07       0
    4753     .12       0  4852.9     .07       0  4978.7     .05       0
  4997.9     .07       0  5121.2     .12       0  5617.9     .07       0
Bank Sta=4978.7,4997.9
XS Rating Curve= 0 ,0
Exp/Cntr=0.3,0.1

Type RM Length L Ch R = 1 ,22298   ,257,257,257
BEGIN DESCRIPTION:
HOOSIER CREEK 34.0
END DESCRIPTION:
XS GIS Cut Line= 3
      2472069.66     13515917.65      2472309.84      13515174.6
       2472401.4     13514373.92
#Sta/Elev= 30
  4219.1  238.23  4250.4  237.02  4346.5  235.99  4351.8  236.72  4422.5  236.94
  4452.3   237.8  4549.1   238.7  4810.9  229.17  4843.2  228.56  4906.6  227.67
  4933.4  223.28  4938.6  223.66    4947   222.2  4957.5     220  4965.4  216.17
  4970.7  217.39  4978.6  215.05    5000  214.83  5000.5  214.33  5019.4  214.83
  5029.8   220.6  5046.8  222.17  5080.1  226.25  5120.4  228.11  5244.6  230.29
  5442.4  233.33  5492.8  233.09  5541.3   234.8  5640.2  235.96  5805.9  239.01
#Mann= 12 ,-1 , 0
  4219.1     .12       0  4422.5     .07       0  4452.3     .12       0
  4810.9     .05       0  4843.2     .07       0    5000     .05       0
  5019.4     .07       0  5046.8      .1       0  5244.6     .07       0
  5442.4     .12       0  5541.3     .07       0  5640.2     .05       0
Bank Sta=5000,5019.4
XS Rating Curve= 0 ,0
Exp/Cntr=0.3,0.1

Type RM Length L Ch R = 1 ,22041   ,397,397,397
BEGIN DESCRIPTION:
Mapping XS 1663305b
END DESCRIPTION:
XS GIS Cut Line= 3
      2472301.44     13515956.68      2472551.43       13515126.
      2472538.41     13514490.62
#Sta/Elev= 30
  4131.1  245.67  4198.1   244.9  4264.2  240.98  4346.8  238.73  4508.1  233.76
  4602.8  230.66  4623.9  230.97  4648.2     231  4665.5  229.46  4811.7  224.65
  4832.5  222.95  4916.1  222.46    4937   221.3  4955.8   217.8    4961  217.69
  4968.3  216.29    4969  214.15  4969.5  213.65  4988.4  214.15  4988.8  215.64
  4989.4  215.65  5001.6  216.29  5009.6  222.75  5019.6  225.37  5029.6  225.06
  5088.4  228.59    5187  229.31  5285.7  230.21  5409.7  231.51  5634.1  235.95
#Mann= 10 ,-1 , 0
  4131.1     .07       0  4346.8     .05       0  4508.1     .12       0
  4623.9     .05       0    4969     .05       0  4988.4     .05       0
  4989.4     .07       0  5088.4      .1       0    5187     .07       0
  5285.7     .05       0
Bank Sta=4969,4988.4
XS Rating Curve= 0 ,0
Exp/Cntr=0.3,0.1

Type RM Length L Ch R = 1 ,21644   ,438,438,438
BEGIN DESCRIPTION:
HOOSIER CREEK 33.0
END DESCRIPTION:
XS GIS Cut Line= 3
        2473075.     13515875.01        2472875.       13515325.
        2472775.       13514125.
#Sta/Elev= 30
  4410.2  241.78  4531.4  236.18  4716.1   229.1  4846.5  226.04  4910.3  219.73
  4949.6  220.28  4980.1  218.32  4985.5  219.66  5005.5  217.06  5005.8  214.16
  5006.3  213.66  5025.3  214.16  5025.5  216.76  5035.6  219.24  5053.1  219.72
  5058.2  217.68  5065.7   222.9  5085.8  227.32  5105.8  228.51  5177.4  228.36
    5294  227.32    5299   225.8  5377.9  224.83  5428.1  224.72  5474.9  227.93
  5517.2  226.76  5577.7  228.13  5667.4  230.84  6059.1  241.73  6199.6  248.19
#Mann= 11 ,-1 , 0
  4410.2     .12       0  4531.4     .05       0  4716.1     .12       0
  5005.8     .05       0  5025.3     .12       0  5177.4     .07       0
  5377.9      .1       0  5428.1     .07       0  5474.9     .05       0
  5577.7     .07       0  5667.4     .05       0
Bank Sta=5005.8,5025.3
XS Rating Curve= 0 ,0
Exp/Cntr=0.3,0.1

Type RM Length L Ch R = 1 ,21206   ,462,462,462
BEGIN DESCRIPTION:
HOOSIER CREEK 32.0
END DESCRIPTION:
XS GIS Cut Line= 3
      2473324.99     13515624.96        2473275.       13515425.
        2473275.     13514225.01
#Sta/Elev= 30
  4793.8  235.23  4904.3  227.61  4917.5  226.67  4927.8  225.15  4935.5  222.61
  4940.6  223.19  4942.9  222.37  4948.4  220.42  4979.9   214.1  4980.4   213.6
  4998.9   213.6  4999.4   214.1  5009.9  214.29  5019.9   215.5  5039.9  220.17
  5072.2   220.9  5089.9  221.26  5139.9  227.44  5170.8  225.83  5219.9  224.89
  5309.9  226.89  5429.9  227.98  5509.9   227.7  5539.9  226.26  5565.2  226.12
  5663.8  227.74  5762.3  230.88  5810.9  231.58  5959.9  235.05  6199.9   244.7
#Mann= 11 ,-1 , 0
  4793.8     .12       0  4904.3     .07       0  4942.9     .12       0
  4979.9     .05       0  4999.4     .12       0  5072.2     .07       0
  5170.8     .12       0  5565.2     .07       0  5663.8     .12       0
  5762.3     .07       0  5810.9     .05       0
Bank Sta=4979.9,4999.4
XS Rating Curve= 0 ,0
Exp/Cntr=0.3,0.1

Type RM Length L Ch R = 1 ,20744   ,466,466,466
BEGIN DESCRIPTION:
HOOSIER CREEK 31.0
END DESCRIPTION:
XS GIS Cut Line= 3
        2473575.       13515725.        2473675.       13515425.
      2473374.99     13514224.96
#Sta/Elev= 30
  4675.6  234.05  4817.1  230.08  4847.3  229.27    4918  227.35  4960.2  225.01
  4989.2  219.24  4994.4  219.24    5013  213.31  5013.5  212.81  5032.5  213.31
  5043.4  213.86  5074.3  219.45  5115.5  220.88  5156.8  220.23  5179.9  222.33
  5205.4  222.91  5221.2  222.43  5228.9  220.51  5239.2  220.62  5257.3  222.89
  5339.7  228.01  5386.1  228.25  5427.3  226.84  5463.4  224.29  5486.6  223.99
  5651.5  227.86  5760.3  229.13  5940.1  233.64  6081.9  240.35  6228.8  245.04
#Mann= 7 ,-1 , 0
  4675.6     .05       0  4817.1     .12       0  4847.3     .05       0
    5013     .05       0  5032.5     .05       0  5205.4     .12       0
  5760.3     .05       0
Bank Sta=5013,5032.5
XS Rating Curve= 0 ,0
Exp/Cntr=0.3,0.1

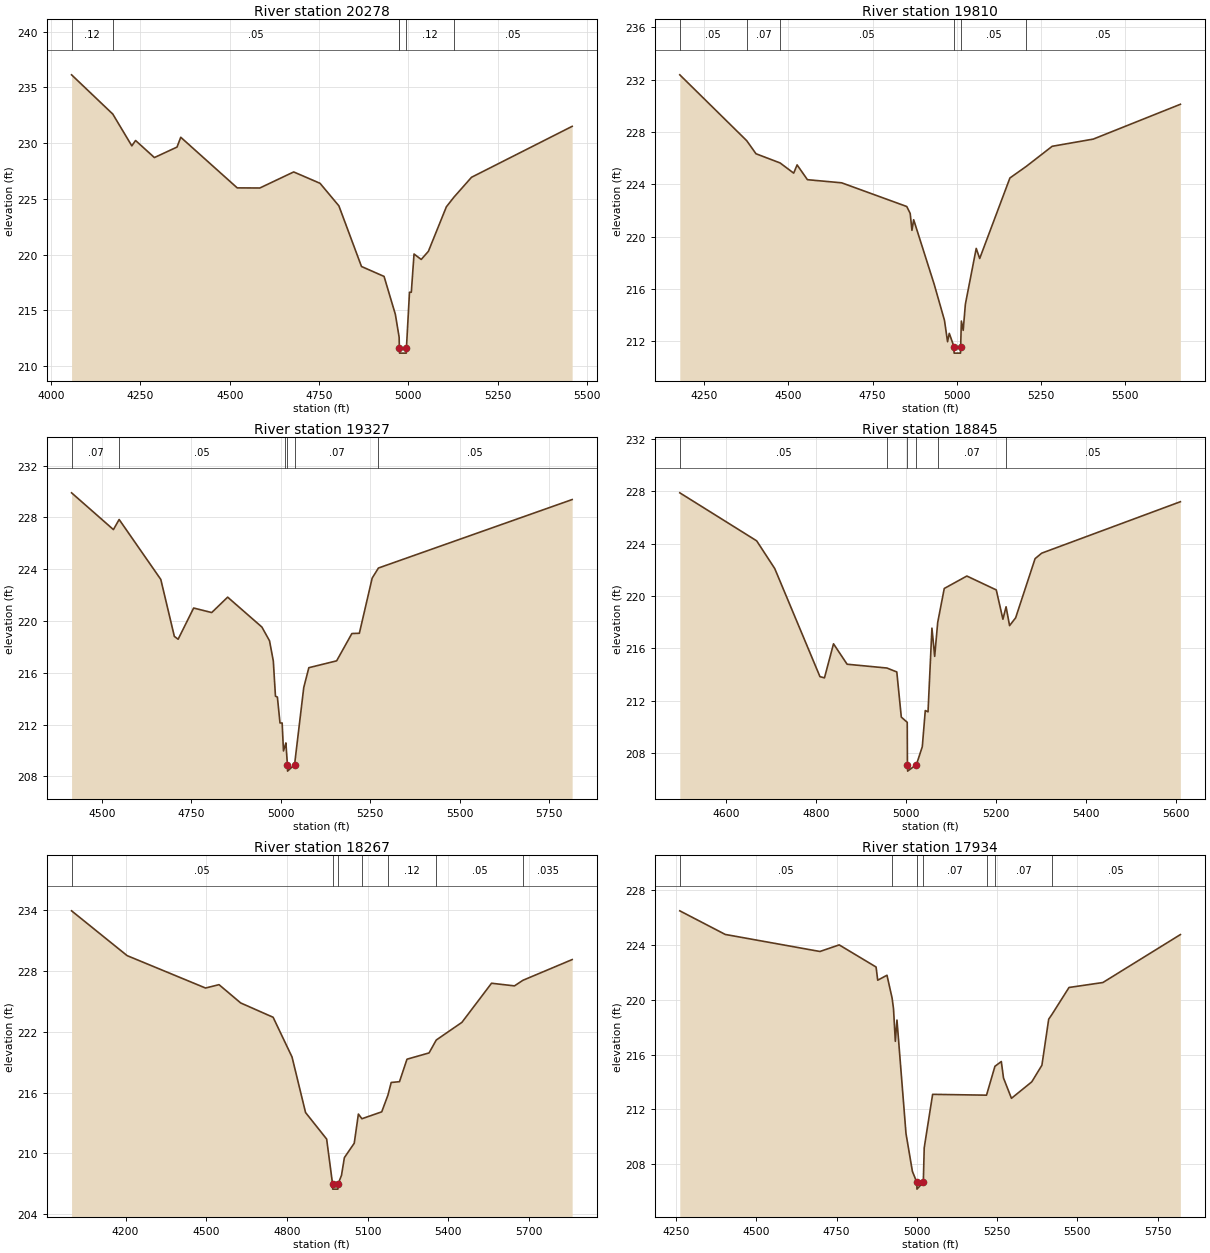
Type RM Length L Ch R = 1 ,20278   ,468,468,468
BEGIN DESCRIPTION:
HOOSIER CREEK 30.0
END DESCRIPTION:
XS GIS Cut Line= 3
        2473775.     13516125.01        2474075.       13515225.
        2474125.     13514774.96
#Sta/Elev= 30
  4057.1  236.12  4172.5   232.6  4225.8  229.75  4236.3  230.23    4289   228.7
  4352.3  229.64  4362.8  230.52  4520.9  225.98  4584.2  225.97    4679  227.41
  4752.8  226.39  4805.5  224.37  4868.8  218.93    4932  218.04  4963.6  214.64
    4973  212.82  4974.2  212.59  4974.8  211.66  4975.3  211.16  4994.2  211.16
  4994.7  211.66  5003.2  216.62  5008.3  216.62  5015.9  220.05    5036  219.56
  5056.1  220.29  5106.4  224.28  5127.7  225.15  5176.8  226.93  5458.6   231.5
#Mann= 6 ,-1 , 0
  4057.1     .12       0  4172.5     .05       0    4973     .12       0
  4974.8     .05       0  4994.7     .12       0  5127.7     .05       0
Bank Sta=4974.8,4994.7
XS Rating Curve= 0 ,0
Exp/Cntr=0.3,0.1

Type RM Length L Ch R = 1 ,19810   ,483,483,483
BEGIN DESCRIPTION:
HOOSIER CREEK 29.0
END DESCRIPTION:
XS GIS Cut Line= 3
      2474374.18     13516087.39        2474525.       13515275.
      2474285.65     13514660.33
#Sta/Elev= 30
    4178  232.36  4376.6  227.33  4404.2  226.33  4475.6  225.63  4516.1  224.85
  4526.2  225.48  4556.8  224.35  4658.5  224.11  4851.7   222.3  4861.9  221.77
  4867.1  220.48  4872.2  221.29  4933.1  216.36  4963.6  213.61  4972.8  211.97
  4977.9  212.61  4991.8   211.6  4992.3   211.1  5011.2   211.1  5011.7   211.6
  5013.8  213.55  5019.2  212.84  5025.7  214.84  5057.9   219.1  5068.2  218.33
  5157.9  224.48  5206.2  225.36  5283.3   226.9  5405.3  227.45  5663.9  230.11
#Mann= 6 ,-1 , 0
    4178     .05       0  4376.6     .07       0  4475.6     .05       0
  4991.8     .05       0  5011.7     .05       0  5206.2     .05       0
Bank Sta=4991.8,5011.7
XS Rating Curve= 0 ,0
Exp/Cntr=0.3,0.1

Type RM Length L Ch R = 1 ,19327   ,482,482,482
BEGIN DESCRIPTION:
HOOSIER CREEK 28.0
END DESCRIPTION:
XS GIS Cut Line= 3
        2475175.     13515824.99        2474975.       13515275.
      2474424.98     13514674.98
#Sta/Elev= 30
  4415.2   229.9  4532.2  227.06  4548.2  227.84  4664.6  223.21  4702.5  218.81
  4713.1  218.59  4756.4     221  4806.9  220.65  4851.5  221.84  4947.2  219.53
  4968.5  218.47  4979.1  216.91  4985.1  214.19  4990.5  214.12  4997.8  212.12
  5003.8  212.12  5007.5  209.96    5012  210.37  5014.3  210.58  5018.5   208.9
    5019   208.4  5038.5   208.9  5064.2  214.86  5078.4  216.39  5156.1  216.92
  5198.7  219.03  5219.6  219.05  5255.4  223.31  5272.9  224.09  5814.4  229.38
#Mann= 6 ,-1 , 0
  4415.2     .07       0  4548.2     .05       0    5012     .07       0
  5018.5     .05       0  5038.5     .07       0  5272.9     .05       0
Bank Sta=5018.5,5038.5
XS Rating Curve= 0 ,0
Exp/Cntr=0.3,0.1

Type RM Length L Ch R = 1 ,18845   ,578,578,578
BEGIN DESCRIPTION:
HOOSIER CREEK 27.0
END DESCRIPTION:
XS GIS Cut Line= 3
        2475475.       13515675.        2475425.       13515175.
      2475075.02     13514675.02
#Sta/Elev= 30
  4497.6  227.88  4668.5  224.21  4708.7  222.09  4809.2  213.83  4819.2  213.74
  4839.3  216.34  4869.5  214.78    4958  214.49    4980  214.19    4990  210.74
  5003.2  210.34  5003.6  207.11  5004.1  206.61  5023.6  207.11  5036.7  208.48
  5043.3  211.24  5049.4  211.14  5058.1  217.54  5064.2  215.38  5070.9  217.97
  5085.5  220.57  5135.7  221.52  5201.1  220.46  5215.9  218.22  5222.9  219.17
  5230.7  217.73  5244.2  218.33  5287.4  222.85  5302.2  223.27  5610.4   227.2
#Mann= 6 ,-1 , 0
  4497.6     .05       0    4958     .12       0  5003.6     .05       0
  5023.6     .12       0  5070.9     .07       0  5222.9     .05       0
Bank Sta=5003.6,5023.6
XS Rating Curve= 0 ,0
Exp/Cntr=0.3,0.1

Type RM Length L Ch R = 1 ,18267   ,333,333,333
BEGIN DESCRIPTION:
HOOSIER CREEK 26.0
END DESCRIPTION:
XS GIS Cut Line= 3
      2476076.68      13516170.4        2475975.       13515175.
       2475525.2     13514441.51
#Sta/Elev= 30
  3999.5  233.89    4206  229.48  4497.5  226.29  4547.7  226.62  4628.2  224.82
  4748.8  223.41  4819.1   219.5  4869.4  214.03  4947.8  211.42  4969.8  206.99
  4970.3  206.49  4989.6  206.49  4990.1  206.99    5003  207.85  5013.7  209.59
  5050.4  211.01  5065.8  213.88  5078.9  213.42  5152.6   214.1  5175.6  215.74
  5187.8  216.99  5218.6  217.07  5246.4  219.28  5328.5   219.9  5355.3  221.17
  5450.7  222.91  5560.8  226.76    5646   226.5  5677.4  227.05  5860.5  229.09
#Mann= 7 ,-1 , 0
  3999.5     .05       0  4969.8     .05       0  4990.1     .05       0
  5078.9     .07       0  5175.6     .12       0  5355.3     .05       0
  5677.4    .035       0
Bank Sta=4969.8,4990.1
XS Rating Curve= 0 ,0
Exp/Cntr=0.3,0.1

Type RM Length L Ch R = 1 ,17934   ,235,235,235
BEGIN DESCRIPTION:
Mapping XS 96f2f45c
END DESCRIPTION:
XS GIS Cut Line= 3
      2476166.29     13515801.21      2476286.07     13515103.33
      2476015.24     13514296.04
#Sta/Elev= 30
  4261.7  226.46  4403.4  224.74  4698.3   223.5  4758.3  223.98  4873.2  222.37
  4878.3  221.41  4907.2  221.77  4923.2   220.1  4927.5  219.34  4933.2  216.96
  4938.3  218.51  4966.4  210.25  4986.4  207.49  5000.1   206.7  5000.6   206.2
  5020.4   206.7  5023.2  209.21  5049.4   213.1  5217.3  213.04  5243.5  215.14
  5263.4  215.49  5270.2  214.29    5295  212.81  5358.3  214.01  5389.9  215.22
    5411  218.57  5421.5  218.93  5474.3  220.88  5579.8  221.24  5821.3  224.73
#Mann= 7 ,-1 , 0
  4261.7     .05       0  4923.2     .07       0  5000.1     .05       0
  5020.4     .07       0  5217.3     .05       0  5243.5     .07       0
  5421.5     .05       0
Bank Sta=5000.1,5020.4
XS Rating Curve= 0 ,0
Exp/Cntr=0.3,0.1

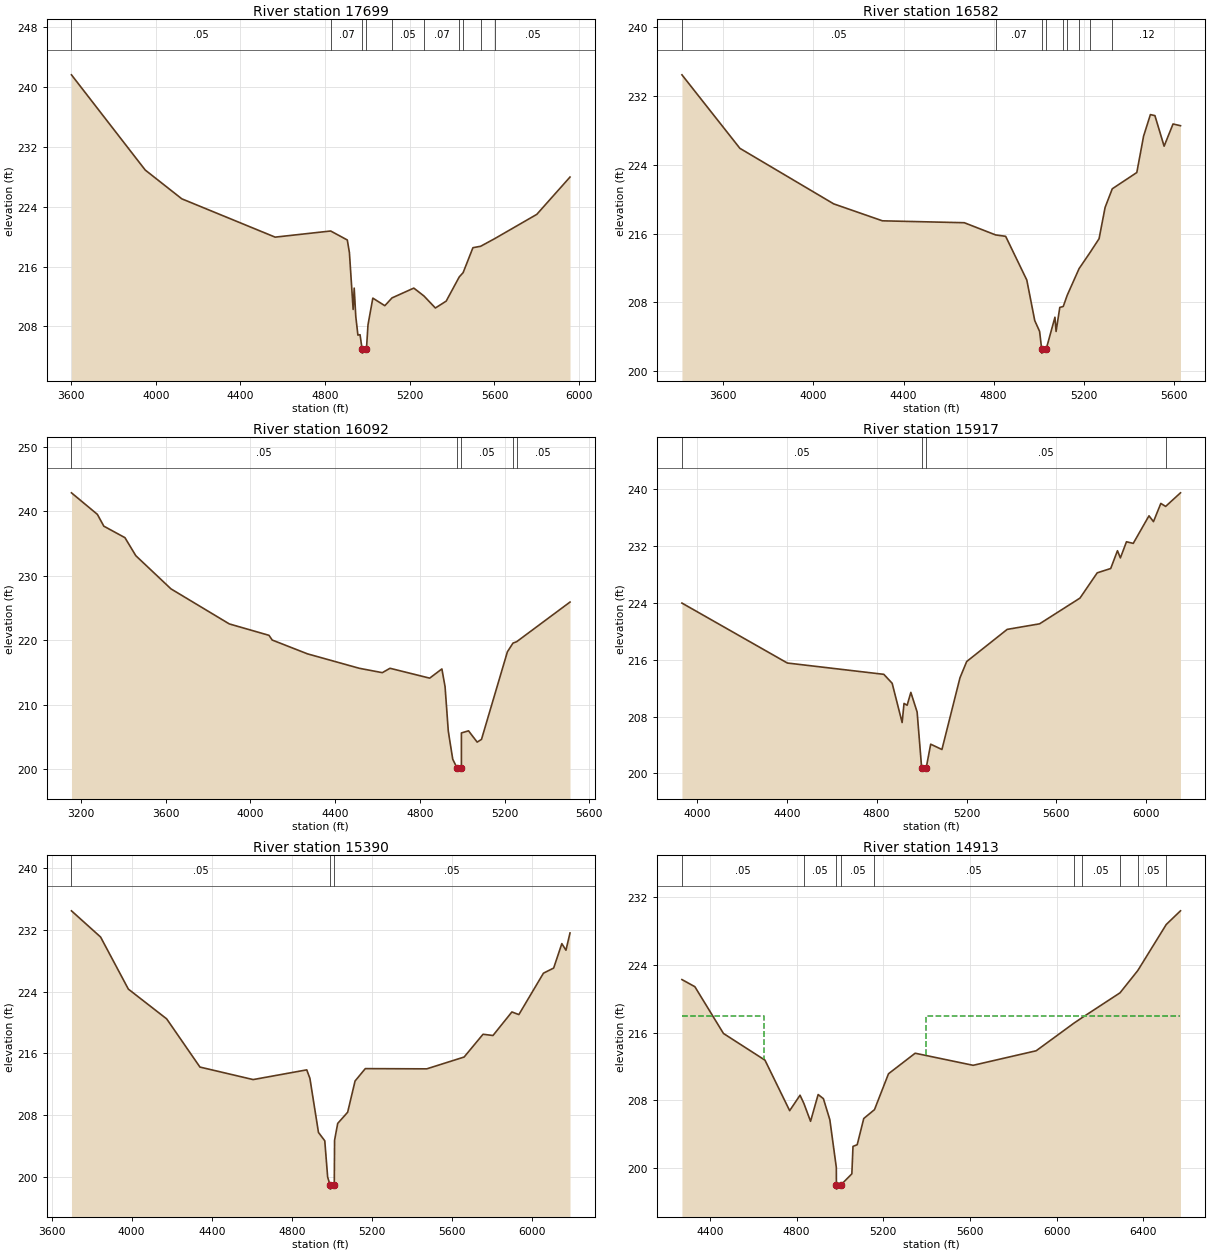
Type RM Length L Ch R = 1 ,17699   ,1117,1117,1117
BEGIN DESCRIPTION:
HOOSIER CREEK 25.0
END DESCRIPTION:
XS GIS Cut Line= 3
        2476375.     13516374.99        2476475.       13514975.
      2476291.28     13514040.86
#Sta/Elev= 30
  3601.4  241.63  3949.8  228.91  4122.7  225.06  4563.8  219.94  4826.1  220.76
  4904.7  219.56  4914.7  217.87  4932.3  210.28  4937.3  213.13  4944.8  209.33
  4954.8  206.85  4964.9   206.9  4974.8  204.94  4975.3  204.44  4995.1  204.94
  5002.5  208.22  5025.3  211.79    5082  210.78    5116  211.82    5219  213.13
  5266.7  212.08  5320.9  210.47  5371.9  211.39  5433.8  214.63  5451.9  215.19
  5498.3  218.53  5534.8  218.72  5601.2  219.74  5799.9  222.98    5957  227.97
#Mann= 10 ,-1 , 0
  3601.4     .05       0  4826.1     .07       0  4974.8     .05       0
  4995.1     .07       0    5116     .05       0  5266.7     .07       0
  5433.8     .05       0  5451.9     .07       0  5534.8     .12       0
  5601.2     .05       0
Bank Sta=4974.8,4995.1
XS Rating Curve= 0 ,0
Exp/Cntr=0.3,0.1

Type RM Length L Ch R = 1 ,16582   ,490,490,490
BEGIN DESCRIPTION:
HOOSIER CREEK 24.0
END DESCRIPTION:
XS GIS Cut Line= 3
      2476424.99     13516175.03      2476997.99     13514698.52
      2476931.91     13514072.09
#Sta/Elev= 30
  3416.2  234.44  3673.6   225.9    4090  219.45  4306.5  217.48  4669.9  217.26
  4809.1  215.84  4853.6  215.68  4947.5   210.6  4982.8  205.89  5004.3  204.64
  5013.4  202.61  5013.9  202.11  5033.9  202.61  5072.5  206.28  5077.5  204.63
    5094  207.42  5109.4  207.53  5126.7  208.82  5179.7  211.93  5227.6  213.77
  5268.4   215.4  5295.1  219.03    5327   221.2  5435.9  223.09  5466.1  227.32
  5496.3  229.82  5516.4   229.7  5557.2  226.15  5596.8  228.73  5629.9  228.53
#Mann= 9 ,-1 , 0
  3416.2     .05       0  4809.1     .07       0  5013.4     .05       0
  5033.9     .07       0  5109.4     .12       0  5126.7     .07       0
  5179.7     .12       0  5227.6     .07       0    5327     .12       0
Bank Sta=5013.4,5033.9
XS Rating Curve= 0 ,0
Exp/Cntr=0.3,0.1

Type RM Length L Ch R = 1 ,16092   ,175,175,175
BEGIN DESCRIPTION:
HOOSIER CREEK 23.0
END DESCRIPTION:
XS GIS Cut Line= 3
      2476424.99     13516425.02        2477425.       13514875.
        2477325.     13514375.01
#Sta/Elev= 30
  3154.9  242.88  3277.3  239.54  3307.7  237.71  3407.4  235.93  3458.8  233.13
  3625.1  227.98  3900.3  222.55  4087.8  220.78  4102.9  220.05  4269.3  217.91
  4514.1  215.67    4623  214.99  4659.3  215.67  4846.7  214.14  4904.3  215.57
  4919.3  212.81  4934.5  205.96  4940.5  204.67  4955.6  201.56  4975.7  200.22
  4976.2  199.72  4996.3  200.22  4996.5  205.64  5030.1  205.97  5070.9  204.22
  5091.3  204.64  5213.7  218.23  5240.2  219.58  5256.9  219.78  5509.4  225.94
#Mann= 5 ,-1 , 0
  3154.9     .05       0  4975.7     .05       0  4996.3     .05       0
  5240.2     .12       0  5256.9     .05       0
Bank Sta=4975.7,4996.3
XS Rating Curve= 0 ,0
Exp/Cntr=0.3,0.1

Type RM Length L Ch R = 1 ,15917   ,527,527,527
BEGIN DESCRIPTION:
HOOSIER CREEK 22.0
END DESCRIPTION:
XS GIS Cut Line= 3
      2477075.02     13515924.97      2477560.86     13514974.94
        2477625.     13513824.98
#Sta/Elev= 30
  3933.5  223.96  4402.6  215.53    4832  213.94  4869.1  212.68  4913.5  207.16
  4921.9  209.85  4935.7  209.59  4952.3   211.4  4980.2  208.64  5000.2  200.83
  5000.7  200.33  5020.8  200.83  5040.6  204.12  5090.6  203.37  5170.8  213.44
  5200.8  215.74  5381.1  220.26  5525.1  221.04    5705  224.66  5781.7  228.21
  5841.8  228.82  5871.8  231.32  5884.9  230.31  5911.9  232.58    5942  232.35
  6012.1  236.23  6032.1  235.41  6064.8  237.97  6086.2  237.55  6152.3  239.46
#Mann= 4 ,-1 , 0
  3933.5     .05       0  5000.2     .05       0  5020.8     .05       0
  6086.2     .07       0
Bank Sta=5000.2,5020.8
XS Rating Curve= 0 ,0
Exp/Cntr=0.3,0.1

Type RM Length L Ch R = 1 ,15390   ,477,477,477
BEGIN DESCRIPTION:
Mapping XS f9b31b72
END DESCRIPTION:
XS GIS Cut Line= 3
      2477327.84     13516357.82      2477993.24     13515225.27
      2477750.19     13514075.12
#Sta/Elev= 30
  3699.6  234.48  3844.9  231.09  3983.6  224.34  4175.1  220.48  4341.1  214.24
  4606.8  212.62  4874.3  213.88    4890  212.79  4932.9  205.77  4964.3  204.69
  4978.7  199.99  4991.1  198.93  4991.6  198.43  5011.7  198.93  5013.2  204.76
  5028.8  206.94  5078.5  208.39  5115.6  212.44  5166.7  214.04  5473.4  214.01
    5660  215.54  5754.4  218.49  5804.1  218.33  5898.5  221.38  5933.3  221.04
    6056   226.4  6107.1  227.07  6147.9  230.23  6168.4  229.38  6188.7  231.61
#Mann= 3 ,-1 , 0
  3699.6     .05       0  4991.1     .05       0  5011.7     .05       0
Bank Sta=4991.1,5011.7
XS Rating Curve= 0 ,0
Exp/Cntr=0.3,0.1

Type RM Length L Ch R = 1 ,14913   ,143,143,143
BEGIN DESCRIPTION:
Mapping XS 2af1e0eb
END DESCRIPTION:
XS GIS Cut Line= 3
      2478098.55     13516186.71       2478364.2       13515520.
      2477802.45     13514040.65
#Sta/Elev= 30
  4271.1  222.28  4330.6  221.44  4462.7   215.9  4654.2  212.74  4768.1  206.76
    4816  208.59  4833.6  207.62  4864.5   205.5  4899.5  208.67  4923.8  208.18
  4953.5  205.68  4983.4  200.03  4983.7  197.97  4984.2  197.47  5004.5  197.97
    5055  199.28  5060.3  202.53  5079.7  202.73  5109.9  205.83  5159.4  206.88
  5224.1  211.13  5347.1  213.56  5614.5  212.13  5905.4  213.85    6079  217.11
  6116.5  217.76  6292.2  220.71  6374.2  223.35  6505.5   228.8  6571.2  230.42
#Mann= 10 ,-1 , 0
  4271.1     .05       0  4833.6     .05       0  4983.7     .05       0
  5004.5     .05       0  5159.4     .05       0    6079    .035       0
  6116.5     .05       0  6292.2    .035       0  6374.2     .05       0
  6505.5    .035       0
#XS Ineff= 2 , 0
       0    4648     218  5395.1       0     218
Permanent Ineff=
       F       F
Bank Sta=4983.7,5004.5
XS Rating Curve= 0 ,0
Exp/Cntr=0.3,0.1