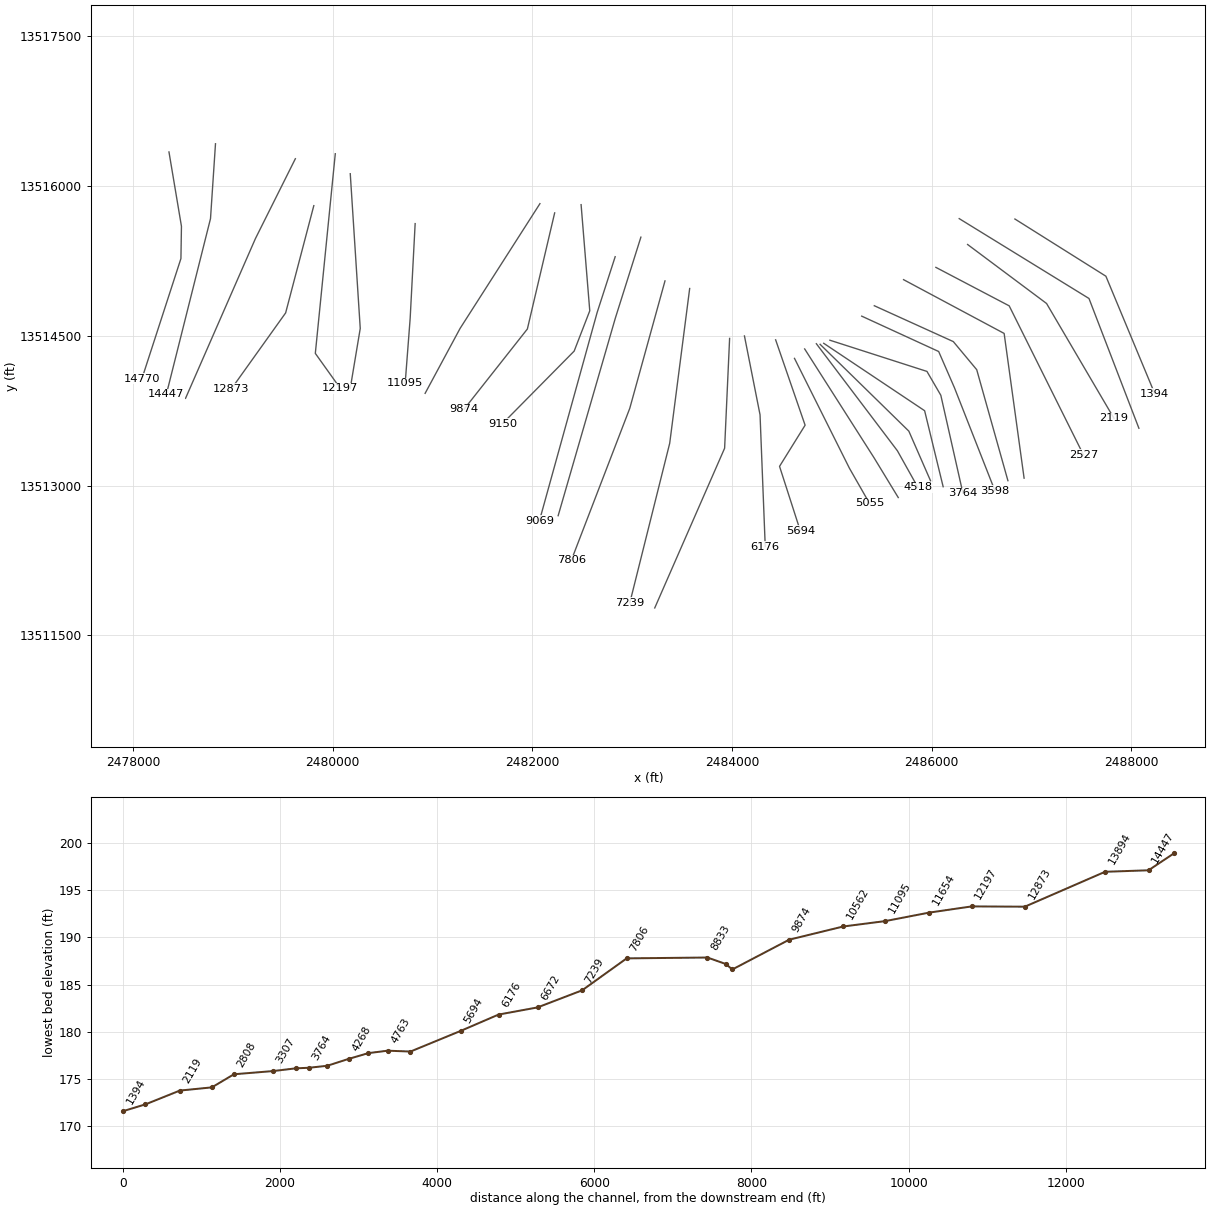
HEC-RAS study HOOSIER CREEK.prj: HOOSIER CREEK Base Level Engineering

--- HOOSIER CREEK.g01 (geometry) --- (continued)

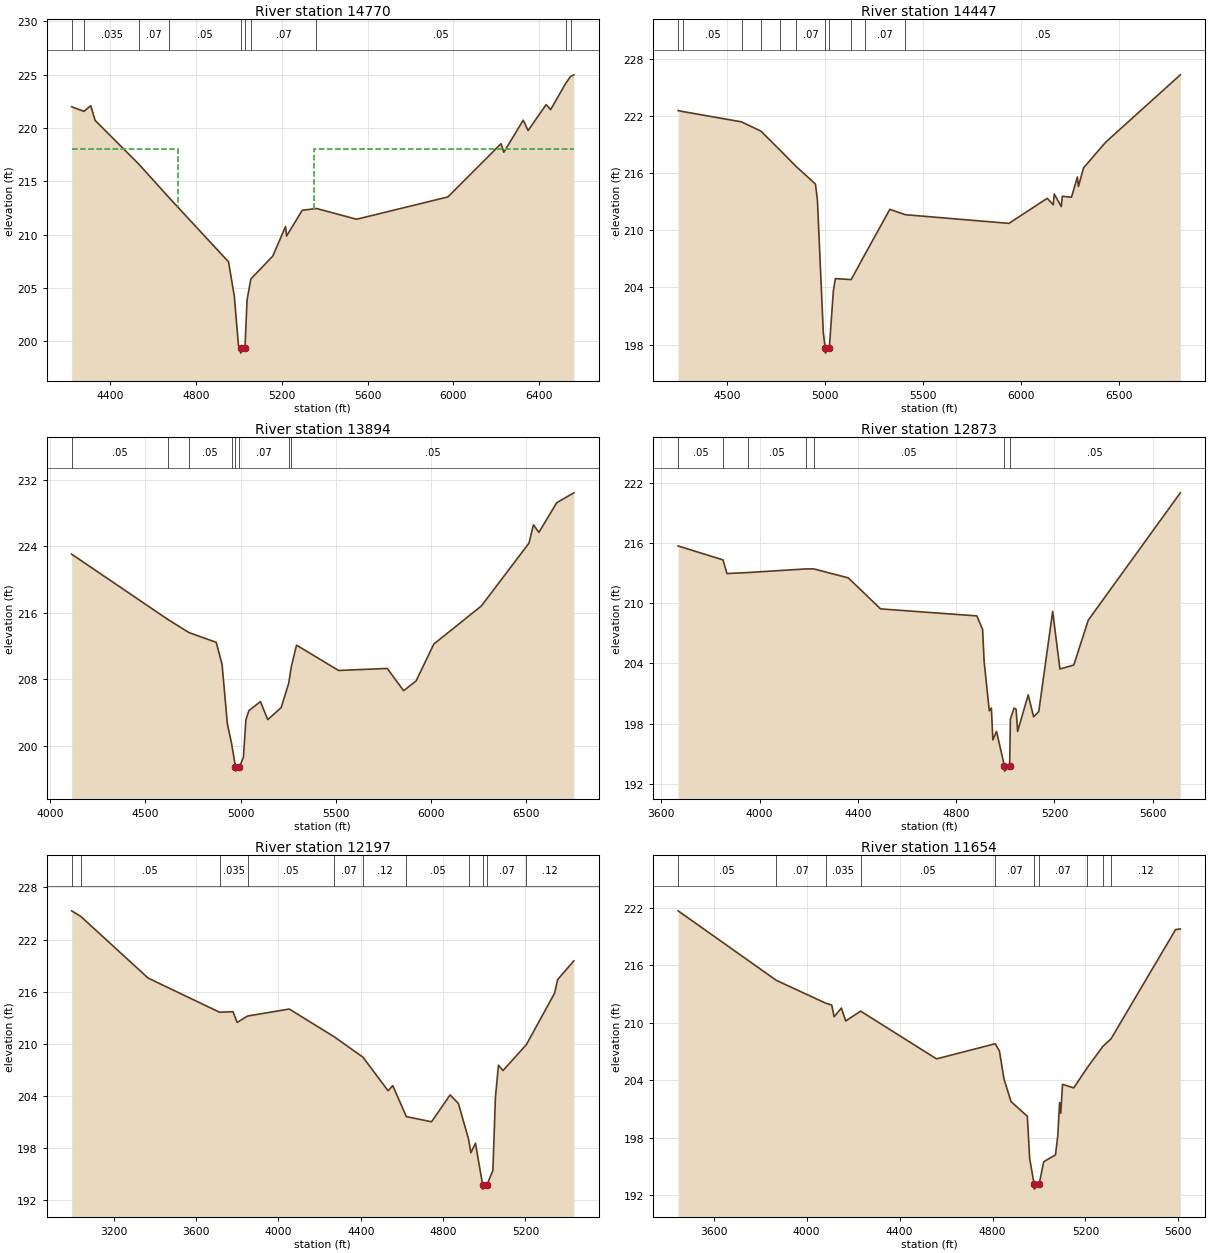
Type RM Length L Ch R = 1 ,14770   ,323,323,323
BEGIN DESCRIPTION:
Mapping XS cb3a509a
END DESCRIPTION:
XS GIS Cut Line= 4
      2478358.98     13516342.95      2478483.99     13515598.13
      2478478.78     13515275.21      2478088.14     13514072.04
#Sta/Elev= 30
  4219.5  221.99  4276.8  221.56  4308.7  222.09    4329  220.71  4533.6   216.6
  4674.7  213.46  4951.6  207.46  4978.8   204.2  4997.9  199.61  5007.5  199.41
    5008  198.91  5028.3  199.41  5037.9  203.88  5055.5  205.85  5157.9     208
  5217.5  210.77  5222.5  209.88  5295.3  212.29  5361.9  212.46  5548.9  211.45
  5974.9  213.54  6223.1  218.53  6235.9  217.73  6326.5  220.73  6349.3  219.76
  6433.4  222.19  6454.4  221.72  6525.3   224.2  6547.7  224.83  6562.7  224.98
#Mann= 10 ,-1 , 0
  4219.5     .07       0  4276.8    .035       0  4533.6     .07       0
  4674.7     .05       0  5007.5     .05       0  5028.3     .05       0
  5055.5     .07       0  5361.9     .05       0  6525.3     .07       0
  6547.7     .05       0
#XS Ineff= 2 , 0
       0    4714     218  5350.5       0     218
Permanent Ineff=
       F       F
Bank Sta=5007.5,5028.3
XS Rating Curve= 0 ,0
Exp/Cntr=0.3,0.1

Type RM Length L Ch R = 1 ,14447   ,553,553,553
BEGIN DESCRIPTION:
HOOSIER CREEK 21.0
END DESCRIPTION:
XS GIS Cut Line= 3
        2478825.     13516425.03        2478775.       13515675.
      2478332.96     13513915.88
#Sta/Elev= 30
  4248.4  222.55  4275.5  222.43  4572.4  221.36  4671.4  220.39  4770.4  218.37
  4852.1  216.67    4950  214.84    4960  213.17  4990.1  199.28    5000  197.62
  5000.5  197.12  5020.8  197.62  5041.3  203.61  5051.6  204.93  5132.6  204.83
  5203.6   207.5    5330  212.19  5408.6  211.63  5938.4  210.72  6134.3  213.35
  6164.8  212.66  6169.9   213.8  6205.9  212.48  6211.1  213.56    6258  213.46
  6288.2  215.58  6293.4  214.59  6319.9  216.55  6433.3  219.24  6813.9  226.29
#Mann= 11 ,-1 , 0
  4248.4     .12       0  4275.5     .05       0  4572.4    .035       0
  4671.4     .07       0  4770.4     .05       0  4852.1     .07       0
    5000     .05       0  5020.8     .07       0  5132.6     .05       0
  5203.6     .07       0  5408.6     .05       0
Bank Sta=5000,5020.8
XS Rating Curve= 0 ,0
Exp/Cntr=0.3,0.1

Type RM Length L Ch R = 1 ,13894   ,1021,1021,1021
BEGIN DESCRIPTION:
HOOSIER CREEK 20.0
END DESCRIPTION:
XS GIS Cut Line= 3
      2479624.99     13516274.99        2479225.       13515475.
      2478525.02     13513875.04
#Sta/Elev= 30
  4111.7  223.07  4617.2  215.22    4729  213.63    4872  212.46  4902.7   209.8
  4930.6  202.65  4952.6   200.3  4973.3  197.46  4973.8  196.96  4994.2  197.46
  5015.1  198.63  5027.9  203.13  5043.9  204.24  5104.4  205.33  5142.9  203.16
  5213.1  204.59  5252.9  207.52  5266.9  209.53  5294.2  212.12  5515.6  209.07
  5771.3  209.32  5857.5  206.64    5923  207.81  6016.2  212.25  6266.4  216.84
  6516.7   224.4  6540.1   226.6  6568.9  225.69  6662.5  229.26  6752.5  230.45
#Mann= 8 ,-1 , 0
  4111.7     .05       0  4617.2    .035       0    4729     .05       0
  4952.6     .07       0  4973.3     .05       0  4994.2     .07       0
  5252.9     .07       0  5266.9     .05       0
Bank Sta=4973.3,4994.2
XS Rating Curve= 0 ,0
Exp/Cntr=0.3,0.1

Type RM Length L Ch R = 1 ,12873   ,676,676,676
BEGIN DESCRIPTION:
Mapping XS a66e6e3f
END DESCRIPTION:
XS GIS Cut Line= 3
      2479809.83     13515804.91      2479527.71     13514730.72
       2478985.2     13513971.19
#Sta/Elev= 30
  3668.3  215.69    3851   214.3  3867.1  212.94  3952.7  213.04  4187.6   213.4
  4220.8   213.4  4360.9  212.51  4492.3  209.42  4884.3  208.72  4907.7  207.36
  4913.8   204.2  4934.7  199.27  4943.3  199.54  4949.4  196.37  4964.2  197.22
  4996.6  193.76  4997.1  193.26  5017.7  193.76  5020.7  198.43  5035.5  199.54
    5044  199.43  5050.2  197.21  5093.2  200.86  5115.3  198.67  5136.2  199.19
  5192.8  209.17  5222.3  203.43  5278.8  203.83  5337.8   208.3  5712.3  220.98
#Mann= 7 ,-1 , 0
  3668.3     .05       0    3851    .035       0  3952.7     .05       0
  4187.6    .035       0  4220.8     .05       0  4996.6     .05       0
  5017.7     .05       0
Bank Sta=4996.6,5017.7
XS Rating Curve= 0 ,0
Exp/Cntr=0.3,0.1

Type RM Length L Ch R = 1 ,12197   ,543,543,543
BEGIN DESCRIPTION:
HOOSIER CREEK 19.0
END DESCRIPTION:
XS GIS Cut Line= 3
        2480025.     13516324.97        2479825.       13514325.
      2480075.02     13513974.97
#Sta/Elev= 30
  2995.1  225.31  3039.3  224.67  3366.9  217.57    3714  213.64    3779  213.71
  3799.1  212.47  3850.5  213.21  4052.8  214.01  4271.8   210.8  4410.1  208.48
  4532.7  204.61  4555.3   205.2  4621.5  201.63  4743.7  201.04  4834.2  204.13
  4874.4  203.14  4923.8  199.03  4934.7  197.47  4957.3  198.57    4992  193.79
  4992.5  193.29  5013.1  193.79  5041.9  195.44  5054.2  203.84  5068.9  207.55
  5091.1  206.93    5205  209.93  5341.8  215.84  5356.5   217.4  5435.2  219.55
#Mann= 11 ,-1 , 0
  2995.1    .035       0  3039.3     .05       0    3714    .035       0
  3850.5     .05       0  4271.8     .07       0  4410.1     .12       0
  4621.5     .05       0  4923.8     .07       0    4992     .05       0
  5013.1     .07       0    5205     .12       0
Bank Sta=4992,5013.1
XS Rating Curve= 0 ,0
Exp/Cntr=0.3,0.1

Type RM Length L Ch R = 1 ,11654   ,559,559,559
BEGIN DESCRIPTION:
HOOSIER CREEK 18.0
END DESCRIPTION:
XS GIS Cut Line= 3
        2480175.     13516124.97        2480275.       13514575.
      2480174.99     13513974.97
#Sta/Elev= 30
  3446.8  221.71  3869.2  214.45    4082  212.06  4108.1  211.86  4118.2  210.64
  4149.5  211.55  4168.3   210.2  4232.3  211.23  4559.1  206.24  4811.6  207.82
  4829.6  207.08  4849.7  204.11  4879.7  201.78  4949.9  200.24  4959.9  195.82
  4979.4  193.13  4979.9  192.63  5000.6  193.13  5020.3  195.49    5071  196.21
  5081.1  198.23  5088.7  201.67  5093.8  200.56  5101.4  203.58  5149.5  203.21
  5208.6  205.35  5274.8  207.54  5310.2  208.34    5588  219.75  5608.3  219.82
#Mann= 10 ,-1 , 0
  3446.8     .05       0  3869.2     .07       0    4082    .035       0
  4232.3     .05       0  4811.6     .07       0  4979.4     .05       0
  5000.6     .07       0  5208.6     .12       0  5274.8     .07       0
  5310.2     .12       0
Bank Sta=4979.4,5000.6
XS Rating Curve= 0 ,0
Exp/Cntr=0.3,0.1

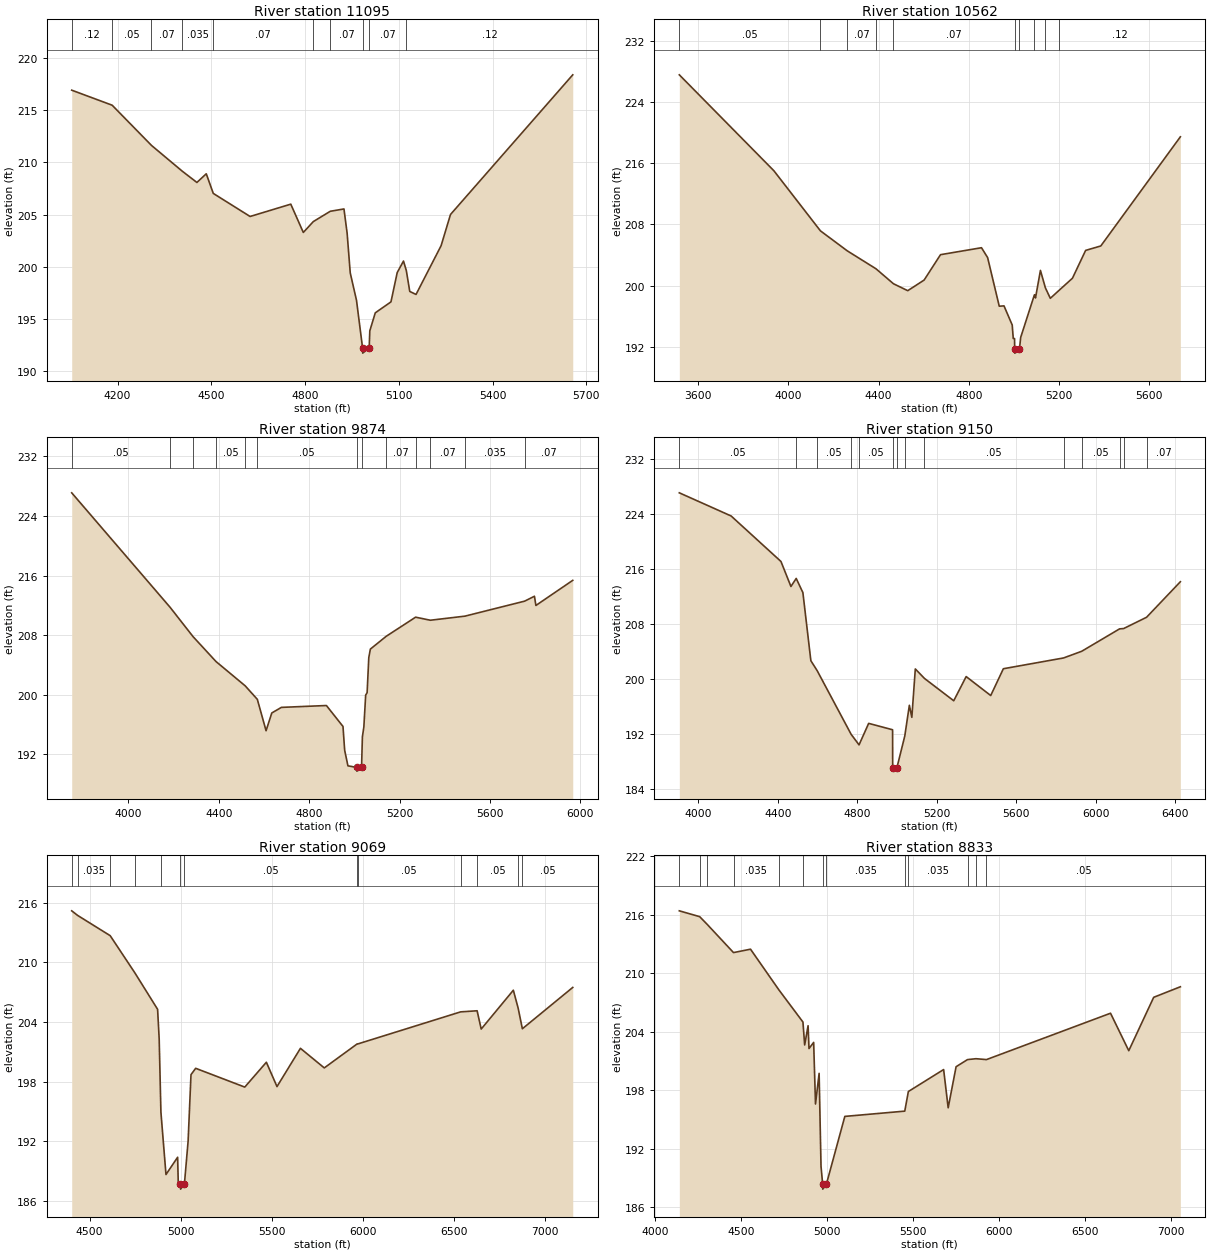
Type RM Length L Ch R = 1 ,11095   ,533,533,533
BEGIN DESCRIPTION:
HOOSIER CREEK 17.0
END DESCRIPTION:
XS GIS Cut Line= 3
        2480825.     13515625.04        2480775.       13514675.
        2480725.     13514024.98
#Sta/Elev= 30
  4053.3  216.92  4182.7  215.48  4308.5  211.63  4407.4  209.15  4453.9  208.08
  4483.9  208.91  4506.3  207.03  4624.1  204.82  4754.3     206  4794.4  203.29
  4826.4  204.33  4880.8  205.32  4924.5  205.54  4934.6  203.22  4944.6  199.41
  4964.6  196.79    4984  192.23  4984.5  191.73  5005.2  192.23  5007.2  193.87
  5024.7  195.59  5074.9  196.64  5094.9  199.45    5115  200.55  5124.1  199.63
    5135  197.64  5155.1  197.35  5235.3  202.02  5265.4  205.01  5656.6  218.39
#Mann= 10 ,-1 , 0
  4053.3     .12       0  4182.7     .05       0  4308.5     .07       0
  4407.4    .035       0  4506.3     .07       0  4826.4     .12       0
  4880.8     .07       0    4984     .05       0  5005.2     .07       0
  5124.1     .12       0
Bank Sta=4984,5005.2
XS Rating Curve= 0 ,0
Exp/Cntr=0.3,0.1

Type RM Length L Ch R = 1 ,10562   ,688,688,688
BEGIN DESCRIPTION:
HOOSIER CREEK 16.0
END DESCRIPTION:
XS GIS Cut Line= 3
      2482074.99     13515824.99        2481275.       13514575.
        2480925.     13513925.01
#Sta/Elev= 30
  3515.9  227.57  3935.3  215.02  4141.7  207.16  4260.9  204.54  4388.4  202.19
  4465.5  200.24    4529  199.33  4601.7  200.72  4674.4  204.04  4856.2  204.95
  4883.3  203.66  4934.9   197.3    4956  197.34  4992.4  194.84    4997  193.07
  5002.8  193.07  5003.2  191.66  5003.7  191.16  5024.4  191.66    5030  193.22
    5091   198.8  5095.7  198.38  5117.6  201.98  5139.6   199.7  5161.4  198.33
  5199.7  199.36  5259.6  200.96    5318   204.6  5385.3  205.18  5738.2  219.46
#Mann= 10 ,-1 , 0
  3515.9     .05       0  4141.7    .035       0  4260.9     .07       0
  4388.4     .12       0  4465.5     .07       0  5003.2     .05       0
  5024.4     .07       0    5091     .12       0  5139.6     .07       0
  5199.7     .12       0
Bank Sta=5003.2,5024.4
XS Rating Curve= 0 ,0
Exp/Cntr=0.3,0.1

Type RM Length L Ch R = 1 ,9874    ,724,724,724
BEGIN DESCRIPTION:
Mapping XS af0ea126
END DESCRIPTION:
XS GIS Cut Line= 3
      2482222.58     13515732.46      2481949.14     13514569.27
      2481315.44      13513766.3
#Sta/Elev= 30
  3748.7  227.09  4183.8  211.75  4285.8   207.8  4387.7  204.45  4516.6   201.2
  4570.3  199.39    4609  195.18  4634.3  197.56  4676.7  198.31  4876.1  198.56
  4949.5  195.75  4956.9  192.56  4971.3  190.47  5010.4  190.26  5010.9  189.76
  5031.6  190.26  5035.4  194.38  5041.8  195.67  5049.9  199.96  5056.3  200.29
  5063.7  204.99  5070.7  206.13    5141  207.85    5271  210.41  5336.3     210
  5489.5  210.55  5753.5  212.56    5797  213.22  5803.3  211.98  5966.5  215.35
#Mann= 13 ,-1 , 0
  3748.7     .05       0  4183.8    .035       0  4285.8     .07       0
  4387.7     .05       0  4516.6     .07       0  4570.3     .05       0
  5010.4     .05       0  5031.6     .05       0    5141     .07       0
    5271     .12       0  5336.3     .07       0  5489.5    .035       0
  5753.5     .07       0
Bank Sta=5010.4,5031.6
XS Rating Curve= 0 ,0
Exp/Cntr=0.3,0.1

Type RM Length L Ch R = 1 ,9150    ,81,81,81
BEGIN DESCRIPTION:
Mapping XS f0949c07
END DESCRIPTION:
XS GIS Cut Line= 4
      2482487.33     13515814.93      2482574.14     13514751.56
      2482417.89     13514347.92      2481699.31     13513620.68
#Sta/Elev= 30
  3904.7   227.1  4165.5  223.73  4416.3  217.11  4466.5  213.47  4493.1  214.64
  4526.7  212.58  4566.8  202.67  4598.2  201.24  4769.5  191.96  4809.4  190.42
  4857.8  193.55  4978.2  192.62  4978.7   187.1  4979.2   186.6    5000   187.1
  5039.6  191.71  5062.6  196.18  5075.1  194.43  5092.6  201.47  5138.7  200.09
    5286  196.84  5348.6  200.36  5472.2   197.6  5535.8   201.5    5839  203.07
  5930.1  204.04  6120.7   207.3  6141.4  207.35  6256.7  208.99  6426.8  214.16
#Mann= 14 ,-1 , 0
  3904.7     .05       0  4493.1    .035       0  4598.2     .05       0
  4769.5    .035       0  4809.4     .05       0  4978.7     .05       0
    5000     .05       0  5039.6    .035       0  5138.7     .05       0
    5839    .035       0  5930.1     .05       0  6120.7     .12       0
  6141.4     .05       0  6256.7     .07       0
Bank Sta=4978.7,5000
XS Rating Curve= 0 ,0
Exp/Cntr=0.3,0.1

Type RM Length L Ch R = 1 ,9069    ,236,236,236
BEGIN DESCRIPTION:
Mapping XS c8a31e3e
END DESCRIPTION:
XS GIS Cut Line= 3
      2482828.68     13515293.49      2482647.92      13514734.2
      2482070.67     13512650.87
#Sta/Elev= 30
  4402.4  215.19  4434.7  214.73  4613.5  212.69  4747.8  208.98  4873.7  205.28
  4882.4  202.29  4891.9  194.93  4919.7  188.65  4983.7  190.39  4987.1   187.8
  4999.3  187.68  4999.8  187.18  5020.8  187.68  5041.2  192.02    5057   198.7
  5082.7  199.34  5352.1  197.45  5470.6  199.95  5528.9   197.5  5657.6  201.35
  5788.4  199.38  5969.3   201.8  5971.9  201.79  6536.7  205.02  6627.2  205.13
  6649.6  203.29    6826   207.2  6852.4  205.39  6875.5  203.32    7152  207.48
#Mann= 13 ,-1 , 0
  4402.4     .05       0  4434.7    .035       0  4613.5     .05       0
  4747.8    .035       0  4891.9     .05       0  4999.3     .05       0
  5020.8     .05       0  5969.3    .035       0  5971.9     .05       0
  6536.7     .07       0  6627.2     .05       0  6852.4     .07       0
  6875.5     .05       0
Bank Sta=4999.3,5020.8
XS Rating Curve= 0 ,0
Exp/Cntr=0.3,0.1

Type RM Length L Ch R = 1 ,8833    ,1027,1027,1027
BEGIN DESCRIPTION:
Mapping XS 457dfad2
END DESCRIPTION:
XS GIS Cut Line= 3
       2483086.3     13515489.44      2482830.22     13514677.78
       2482257.5     13512699.31
#Sta/Elev= 30
  4142.8  216.38  4261.2  215.78  4304.8  214.99  4457.6   212.1  4556.4  212.45
  4722.1  208.26  4860.9  204.99    4871  202.64  4890.8  204.61  4896.1  202.27
  4923.2   202.9  4933.9  196.59  4954.9  199.73    4966  190.19  4975.6  188.37
  4976.1  187.87  4997.1  188.37  5104.3  195.32  5452.5  195.86  5473.4  197.87
  5678.3  200.12  5704.7   196.2  5750.7  200.41  5817.1  201.14    5866  201.23
  5927.2  201.14  6647.9  205.89  6753.9  202.05  6898.7  207.52  7053.6   208.6
#Mann= 13 ,-1 , 0
  4142.8     .05       0  4261.2    .035       0  4304.8     .05       0
  4457.6    .035       0  4722.1     .05       0  4860.9    .035       0
  4975.6    .035       0  4997.1    .035       0  5452.5     .05       0
  5473.4    .035       0  5817.1     .05       0    5866    .035       0
  5927.2     .05       0
Bank Sta=4975.6,4997.1
XS Rating Curve= 0 ,0
Exp/Cntr=0.3,0.1

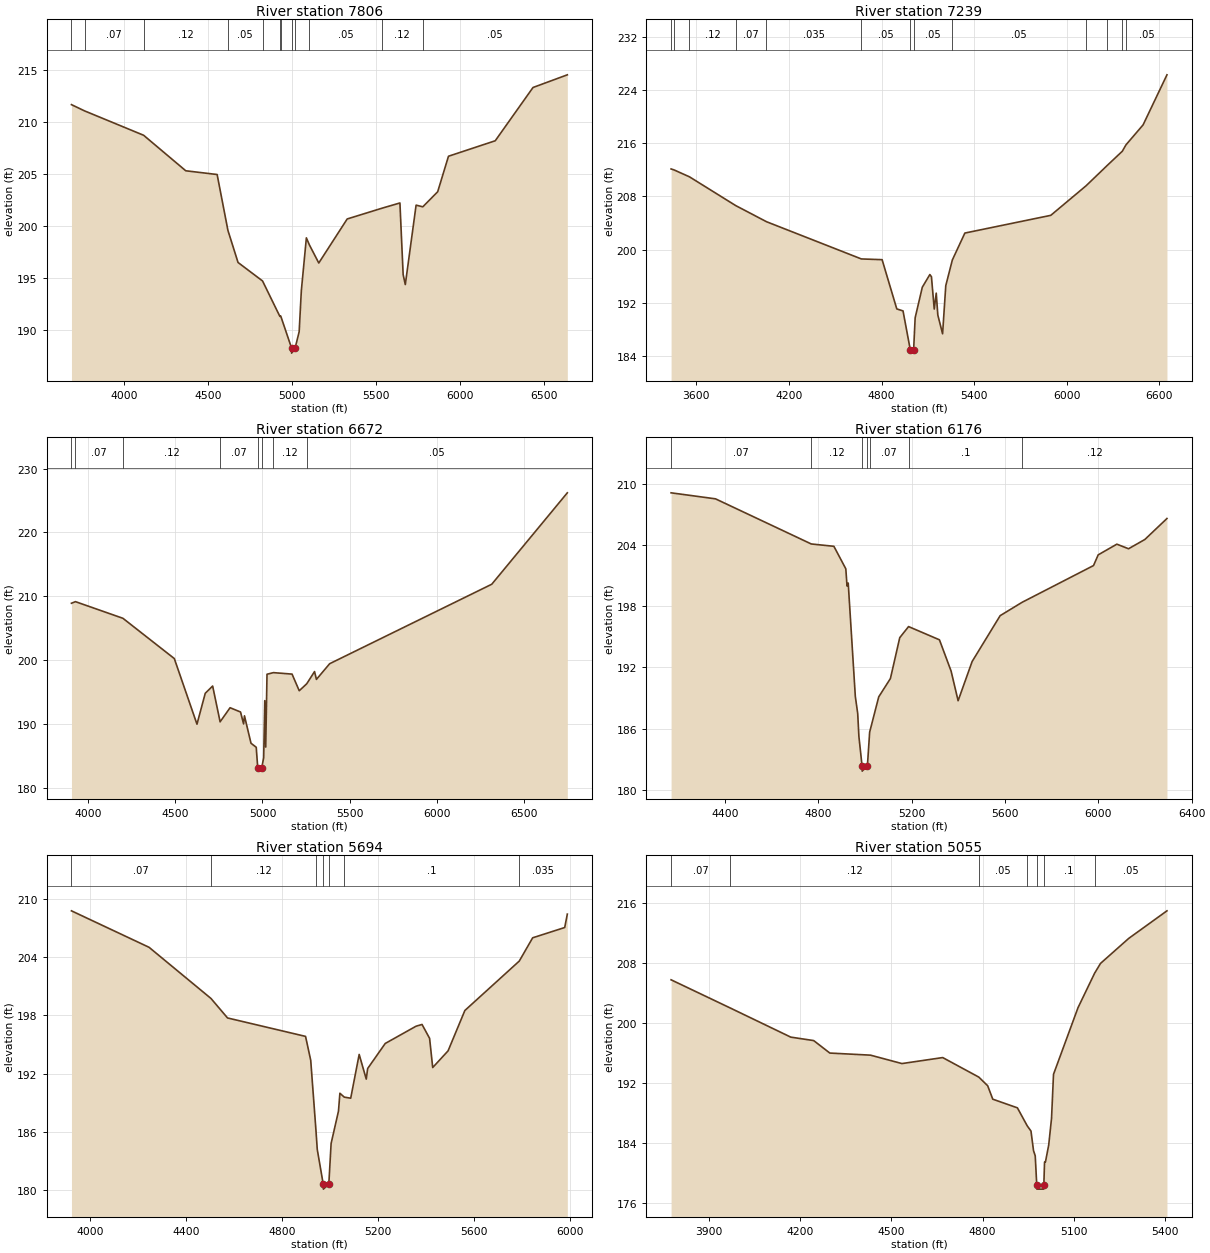
Type RM Length L Ch R = 1 ,7806    ,567,567,567
BEGIN DESCRIPTION:
HOOSIER CREEK 12.0
END DESCRIPTION:
XS GIS Cut Line= 3
      2483327.73     13515051.23        2482975.       13513775.
      2482390.23     13512254.34
#Sta/Elev= 30
  3684.4  211.71  3762.1  211.11  4114.2  208.76  4365.2  205.34    4552  204.98
  4616.3   199.6  4676.5  196.51  4822.5  194.73  4925.6  191.32  4930.9  191.35
  4995.1  188.28  4995.6  187.78  5016.7  188.28  5040.6  189.84  5053.5  193.79
  5083.5  198.88  5101.3  198.21  5157.4  196.46  5326.7   200.7  5532.8  201.73
  5640.7  202.24  5659.9  195.34  5672.7  194.38    5737  202.03    5777  201.87
  5865.6  203.32  5929.9  206.74  6208.4  208.23  6433.4  213.36  6637.7  214.58
#Mann= 12 ,-1 , 0
  3684.4    .035       0  3762.1     .07       0  4114.2     .12       0
  4616.3     .05       0  4822.5     .07       0  4925.6     .05       0
  4930.9     .07       0  4995.1     .05       0  5016.7     .07       0
  5101.3     .05       0  5532.8     .12       0    5777     .05       0
Bank Sta=4995.1,5016.7
XS Rating Curve= 0 ,0
Exp/Cntr=0.3,0.1

Type RM Length L Ch R = 1 ,7239    ,567,567,567
BEGIN DESCRIPTION:
HOOSIER CREEK 11.0
END DESCRIPTION:
XS GIS Cut Line= 3
        2483575.     13514975.01        2483375.       13513425.
        2482975.       13511825.
#Sta/Elev= 30
  3436.8  212.14  3456.2  211.99    3556  210.95  3855.3  206.62  4054.8  204.19
  4669.3  198.58  4803.7  198.47  4898.8  191.05  4939.2  190.75  4986.3  184.89
  4986.8  184.39  5007.9  184.89  5017.7  189.71  5064.1  194.32    5113  196.23
  5123.3   195.9  5141.4  191.03  5154.3  193.43  5164.6  190.13  5195.5   187.3
  5216.1  194.55  5258.6  198.42  5339.8  202.48  5896.4  205.15  6124.8   209.6
  6262.6  212.68  6359.8  214.81  6383.1  215.76  6494.3  218.78  6648.9  226.32
#Mann= 13 ,-1 , 0
  3436.8     .05       0  3456.2    .035       0    3556     .12       0
  3855.3     .07       0  4054.8    .035       0  4669.3     .05       0
  4986.3     .05       0  5007.9     .05       0  5258.6     .05       0
  6124.8    .035       0  6262.6     .05       0  6359.8    .035       0
  6383.1     .05       0
Bank Sta=4986.3,5007.9
XS Rating Curve= 0 ,0
Exp/Cntr=0.3,0.1

Type RM Length L Ch R = 1 ,6672    ,496,496,496
BEGIN DESCRIPTION:
HOOSIER CREEK 10.0
END DESCRIPTION:
XS GIS Cut Line= 3
        2483975.     13514475.01        2483925.       13513375.
      2483224.99     13511774.97
#Sta/Elev= 30
  3903.2   208.9  3926.1  209.15  4198.7  206.54  4493.8  200.23    4624  189.94
  4671.5  194.78    4714  195.92  4756.9  190.31  4814.1  192.52  4874.2  191.85
  4891.7  189.98  4896.7  191.25  4934.3  186.95  4964.3  186.32    4973  183.08
  4973.5  182.58  4995.7  183.08  5007.1  184.68  5013.3  193.63  5018.8  186.36
  5026.2  197.77  5063.2  198.02    5170  197.79  5211.3  195.18  5254.5  196.28
  5299.1  198.19    5310  196.96    5386  199.42  6316.9  211.88  6750.8  226.21
#Mann= 8 ,-1 , 0
  3903.2     .12       0  3926.1     .07       0  4198.7     .12       0
  4756.9     .07       0    4973     .05       0  4995.7     .07       0
  5063.2     .12       0  5254.5     .05       0
Bank Sta=4973,4995.7
XS Rating Curve= 0 ,0
Exp/Cntr=0.3,0.1

Type RM Length L Ch R = 1 ,6176    ,482,482,482
BEGIN DESCRIPTION:
Mapping XS 658ea887
END DESCRIPTION:
XS GIS Cut Line= 3
      2484123.63     13514499.78      2484279.87      13513709.9
      2484331.95     13512390.41
#Sta/Elev= 30
  4168.4  209.14  4358.8  208.55  4769.3  204.12  4866.3  203.89  4917.4  201.68
  4922.6  199.99  4927.7  200.28  4958.2  189.14  4968.4  187.48  4973.5  185.23
  4987.1  182.32  4987.6  181.82  5009.9  182.32  5019.6  185.65  5058.5  189.11
  5108.6  190.91  5148.6  194.92  5186.4  196.01  5318.8  194.71  5368.8  191.64
  5398.8  188.73  5458.9  192.58    5579  197.08  5672.9  198.39  5979.3     202
  5999.3  203.05  6079.3   204.1  6129.4  203.65  6199.4  204.56  6294.1  206.62
#Mann= 7 ,-1 , 0
  4168.4     .07       0  4769.3     .12       0  4987.1     .05       0
  5009.9     .12       0  5019.6     .07       0  5186.4      .1       0
  5672.9     .12       0
Bank Sta=4987.1,5009.9
XS Rating Curve= 0 ,0
Exp/Cntr=0.3,0.1

Type RM Length L Ch R = 1 ,5694    ,639,639,639
BEGIN DESCRIPTION:
Mapping XS d2344336
END DESCRIPTION:
XS GIS Cut Line= 4
      2484436.11     13514460.79      2484731.26     13513605.73
      2484475.18      13513193.4      2484682.97     13512548.39
#Sta/Elev= 30
  3923.3  208.77  4246.9  205.01    4505  199.74  4574.1  197.73  4899.4  195.83
    4921  193.36  4942.7  186.17  4948.2  184.19  4973.2  180.59  4973.7  180.09
  4996.4  180.59    5006   184.8  5036.7  188.13  5042.6  189.97  5060.9  189.57
  5087.7  189.46    5123  193.97  5152.5  191.43  5158.4  192.52  5231.6   195.1
  5360.2  196.88  5385.1  197.06  5416.6  195.63  5429.6  192.62  5493.7  194.34
  5563.7   198.5  5790.5  203.59  5846.4  205.99    5980  207.05  5990.9  208.43
#Mann= 7 ,-1 , 0
  3923.3     .07       0    4505     .12       0  4942.7     .07       0
  4973.2     .05       0  4996.4     .07       0  5060.9      .1       0
  5790.5    .035       0
Bank Sta=4973.2,4996.4
XS Rating Curve= 0 ,0
Exp/Cntr=0.3,0.1

Type RM Length L Ch R = 1 ,5055    ,292,292,292
BEGIN DESCRIPTION:
HOOSIER CREEK 8.0
END DESCRIPTION:
XS GIS Cut Line= 3
      2484625.01     13514274.98        2485175.       13513175.
      2485374.99     13512825.02
#Sta/Elev= 30
  3774.3  205.76    3969  202.01  4168.4  198.13  4243.9  197.67    4297  196.01
  4431.1  195.73  4534.5  194.61  4668.7  195.41  4787.6  192.81  4816.8  191.66
  4833.6  189.87  4914.7  188.72  4947.1  186.32  4959.4  185.63  4967.8  183.02
  4973.4  182.33  4978.5   178.4    4979   177.9  5001.2   177.9  5001.7   178.4
  5004.1   181.5    5007   181.5  5017.8  183.77  5027.1  187.32  5033.6  193.18
  5114.2  202.04    5169  206.64  5188.4  207.94  5281.3  211.27  5407.2  214.94
#Mann= 7 ,-1 , 0
  3774.3     .07       0    3969     .12       0  4787.6     .05       0
  4947.1      .1       0  4978.5     .05       0  5001.7      .1       0
    5169     .05       0
Bank Sta=4978.5,5001.7
XS Rating Curve= 0 ,0
Exp/Cntr=0.3,0.1

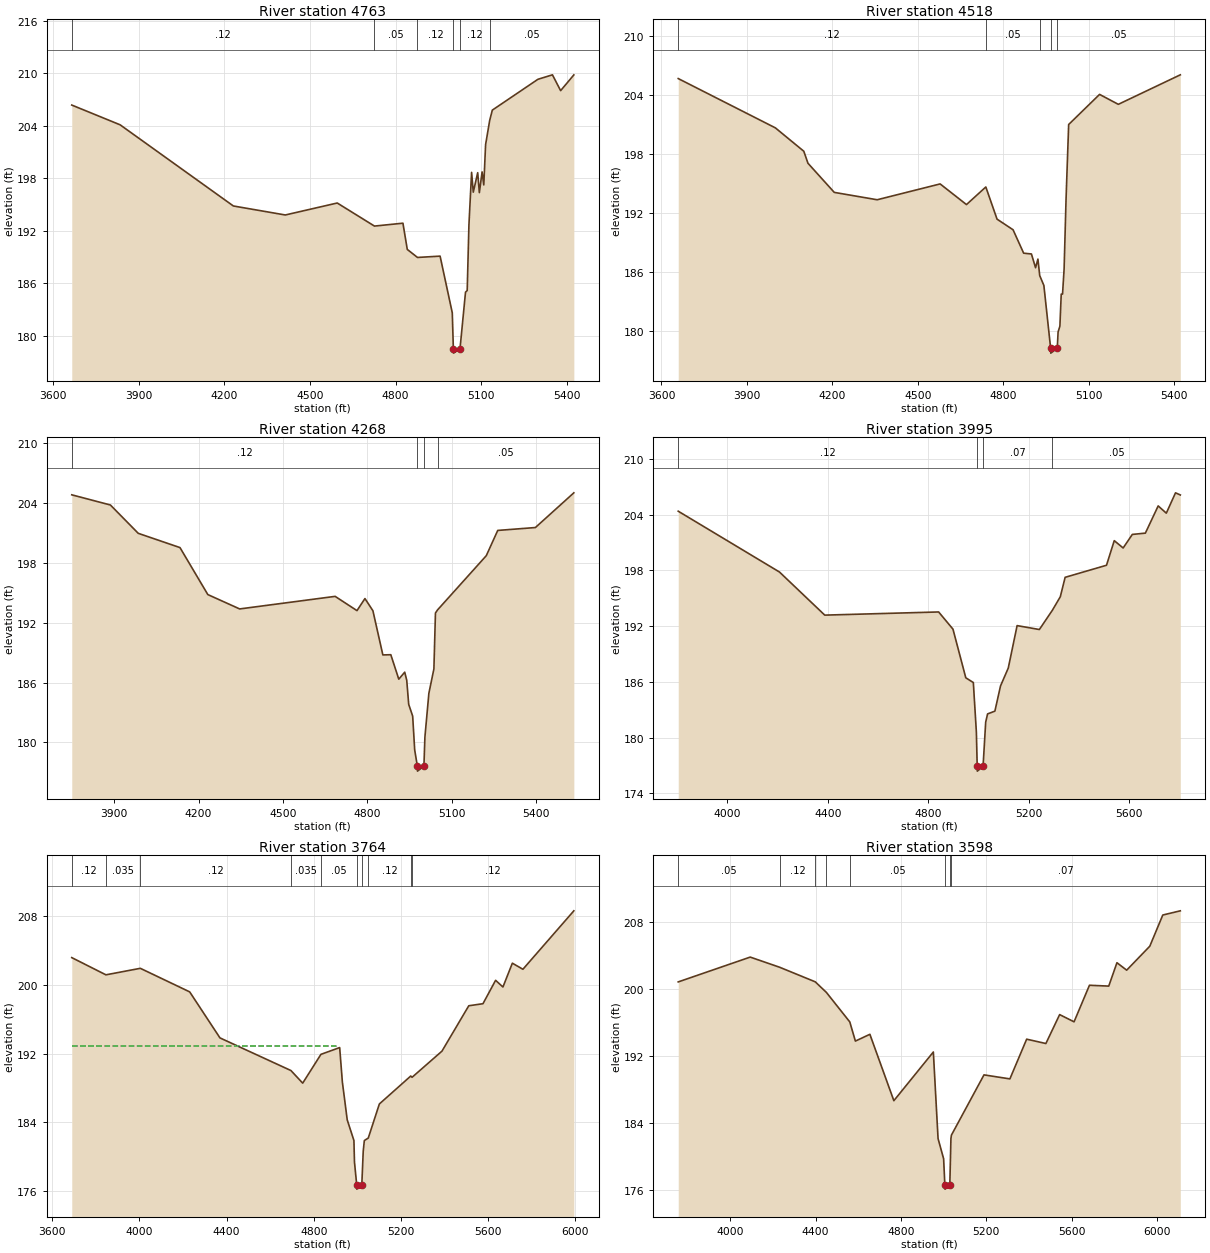
Type RM Length L Ch R = 1 ,4763    ,245,245,245
BEGIN DESCRIPTION:
Mapping XS 726e9f7b
END DESCRIPTION:
XS GIS Cut Line= 3
       2484726.9     13514369.65      2485421.36     13513280.21
      2485664.41     13512880.92
#Sta/Elev= 30
  3665.3  206.38  3834.7  204.12  4231.6  194.83  4413.6   193.8  4595.6  195.17
    4726  192.53  4825.8  192.86    4841  189.86  4876.8  188.94    4956  189.09
  4998.7  182.61  5002.5  178.49    5003  177.99  5025.8  178.49  5045.1  184.97
    5051  185.15    5057  192.63  5066.4  198.68  5072.3  196.41  5087.8  198.64
  5093.6  196.36  5103.2  198.73  5109.1  197.24  5115.5  201.86  5129.8  204.62
    5139   205.8  5298.9  209.33  5349.7  209.84  5378.4  208.03  5424.7  209.83
#Mann= 6 ,-1 , 0
  3665.3     .12       0    4726     .05       0  4876.8     .12       0
  5002.5     .05       0  5025.8     .12       0  5129.8     .05       0
Bank Sta=5002.5,5025.8
XS Rating Curve= 0 ,0
Exp/Cntr=0.3,0.1

Type RM Length L Ch R = 1 ,4518    ,250,250,250
BEGIN DESCRIPTION:
Mapping XS dd0338ab
END DESCRIPTION:
XS GIS Cut Line= 3
      2484844.11      13514421.7      2485655.74     13513349.65
      2485859.73     13512985.07
#Sta/Elev= 30
  3658.9  205.64  3999.8  200.63  4099.7  198.25  4114.3  197.03  4206.6  194.07
  4357.2  193.32  4578.2  194.93  4670.7  192.83  4738.6  194.62    4778  191.35
  4834.2  190.27  4871.4  187.89  4898.7  187.81  4913.2  186.41  4921.5  187.29
  4927.8  185.61  4942.4  184.61  4966.1  178.23  4966.6  177.73  4989.4  178.23
  4992.3  179.88  4998.6  180.47  5003.3  183.73  5007.9  183.73  5013.4  186.28
  5020.3  193.45  5029.4  200.97  5137.9  204.03  5203.7  203.02  5421.3  206.02
#Mann= 5 ,-1 , 0
  3658.9     .12       0  4738.6     .05       0  4927.8     .12       0
  4966.1     .05       0  4989.4     .05       0
Bank Sta=4966.1,4989.4
XS Rating Curve= 0 ,0
Exp/Cntr=0.3,0.1

Type RM Length L Ch R = 1 ,4268    ,273,273,273
BEGIN DESCRIPTION:
Mapping XS 24177ee0
END DESCRIPTION:
XS GIS Cut Line= 3
      2484881.59     13514415.86      2485770.46     13513546.08
      2485987.39     13513049.74
#Sta/Elev= 30
    3749  204.82  3886.4   203.8  3985.4  200.96  4133.8  199.53  4232.8  194.82
    4346  193.38  4685.5  194.64  4763.2  193.21  4791.5  194.42  4819.8   193.2
  4855.2  188.77  4883.5  188.79  4911.8  186.34  4932.9  187.04  4940.1  186.23
  4947.1  183.81  4961.2  182.64  4968.4  179.24  4977.9  177.62  4978.4  177.12
  5001.2  177.62  5004.7  180.53  5018.8  184.92  5036.7  187.37  5042.2  192.97
  5049.6  193.28    5223  198.72  5263.7  201.25  5397.6  201.54  5534.3  205.02
#Mann= 4 ,-1 , 0
    3749     .12       0  4977.9     .05       0  5001.2     .12       0
  5049.6     .05       0
Bank Sta=4977.9,5001.2
XS Rating Curve= 0 ,0
Exp/Cntr=0.3,0.1

Type RM Length L Ch R = 1 ,3995    ,231,231,231
BEGIN DESCRIPTION:
Mapping XS 249054c6
END DESCRIPTION:
XS GIS Cut Line= 3
       2484917.9     13514426.04      2485928.44     13513750.95
      2486114.05     13512989.44
#Sta/Elev= 30
  3804.5  204.38  4207.7  197.83  4387.9  193.19  4841.4  193.53  4898.4  191.68
  4949.5  186.44  4979.5  185.93  4991.6  180.59  4994.9  176.89  4995.4  176.39
  5018.2  176.89  5028.7  181.67  5036.2  182.55  5065.3  182.85  5087.7  185.56
  5118.6  187.49  5153.8  192.06  5242.4  191.64  5294.1  193.71  5325.8  195.17
    5345  197.26  5509.7  198.56  5540.6  201.21    5576  200.42  5612.5  201.88
  5664.5  202.02  5715.5  204.95  5747.9  204.17  5784.5  206.36  5803.6  206.13
#Mann= 4 ,-1 , 0
  3804.5     .12       0  4994.9     .05       0  5018.2     .07       0
  5294.1     .05       0
Bank Sta=4994.9,5018.2
XS Rating Curve= 0 ,0
Exp/Cntr=0.3,0.1

Type RM Length L Ch R = 1 ,3764    ,166,166,166
BEGIN DESCRIPTION:
Mapping XS c700b304
END DESCRIPTION:
XS GIS Cut Line= 4
      2484979.62     13514456.96      2485951.83     13514144.47
      2486090.72     13513905.75      2486312.06      13512924.9
#Sta/Elev= 30
  3690.1   203.2  3846.7  201.19  4004.6  201.95    4231   199.2  4369.8  193.83
  4695.4  190.02  4749.3  188.55    4833  191.91  4918.9   192.7  4931.3  188.68
  4953.6  184.26  4984.3  181.85  4986.8  179.34  4997.1  176.68  4997.6  176.18
  5020.4  176.68  5026.9  180.58    5032  181.85  5050.1  182.14    5101  186.12
    5245  189.38  5250.9  189.23    5388  192.28  5511.1  197.58  5576.2  197.82
  5634.1  200.55  5667.8  199.77    5711  202.55  5759.4  201.84    5993  208.66
#Mann= 10 ,-1 , 0
  3690.1     .12       0  3846.7    .035       0  4004.6     .12       0
  4695.4    .035       0    4833     .05       0  4997.1     .05       0
  5020.4     .07       0  5050.1     .12       0    5245     .12       0
  5250.9     .12       0
#XS Ineff= 2 , 0
       0    4904  192.91               0
Permanent Ineff=
       F       F
Bank Sta=4997.1,5020.4
XS Rating Curve= 0 ,0
Exp/Cntr=0.3,0.1

Type RM Length L Ch R = 1 ,3598    ,291,291,291
BEGIN DESCRIPTION:
HOOSIER CREEK 5.0
END DESCRIPTION:
XS GIS Cut Line= 4
       2485298.4     13514698.07      2486069.24      13514343.9
      2486227.19      13513981.1      2486632.94     13512948.57
#Sta/Elev= 30
    3756  200.84  4093.4   203.8  4231.2  202.59  4398.3  200.85  4450.4  199.59
  4560.1  196.07  4586.4  193.78  4654.3  194.59  4766.7  186.67  4951.8  192.48
  4973.9  182.15    5000  179.74  5005.7  176.62  5006.2  176.12    5029  176.62
  5034.2  182.15  5036.5  182.56  5189.2  189.75  5310.6  189.27  5389.2  194.01
  5479.3  193.49  5543.8  196.94  5611.4  196.08  5683.5  200.44    5774  200.34
  5812.4  203.13    5858  202.24  5966.4   205.1  6027.3  208.82  6109.4  209.32
#Mann= 8 ,-1 , 0
    3756     .05       0  4231.2     .12       0  4398.3     .05       0
  4450.4    .035       0  4560.1     .05       0  5005.7     .05       0
    5029     .07       0  5036.5     .07       0
#XS Ineff= 2 , 0
       0  4951.8  192.48               0
Permanent Ineff=
       F       F
Bank Sta=5005.7,5029
XS Rating Curve= 0 ,0
Exp/Cntr=0.3,0.1

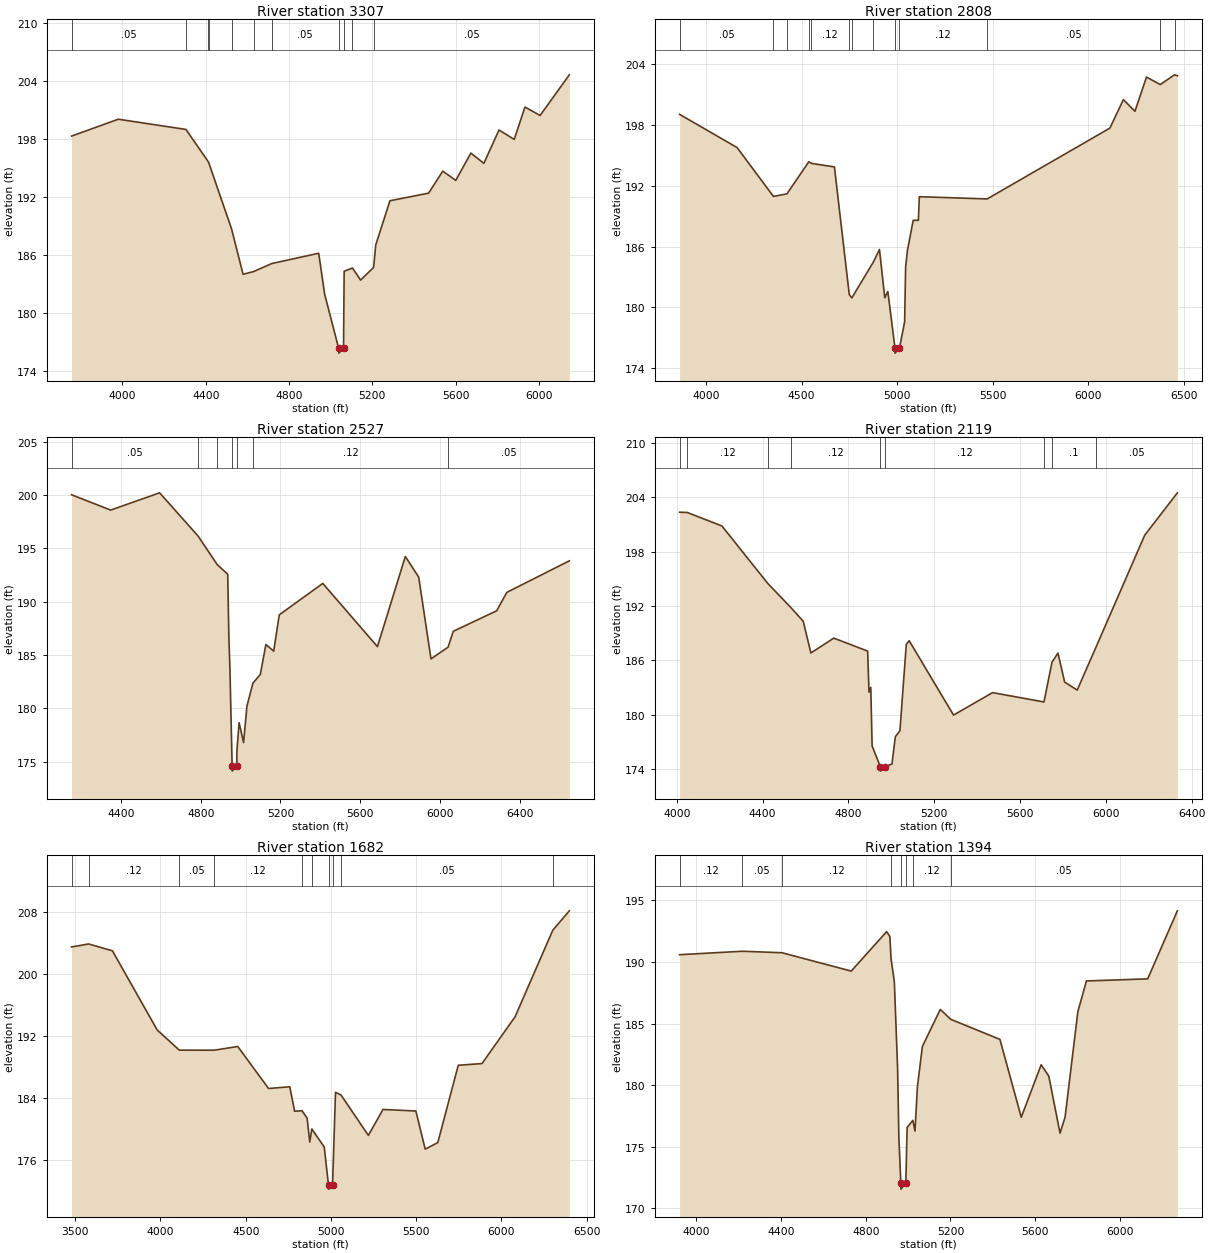
Type RM Length L Ch R = 1 ,3307    ,499,499,499
BEGIN DESCRIPTION:
Mapping XS a776668d
END DESCRIPTION:
XS GIS Cut Line= 4
      2485424.36     13514802.45      2486216.01     13514443.08
      2486450.38     13514161.83      2486762.87     13513049.91
#Sta/Elev= 30
  3755.5  198.32  3980.2  200.07  4304.9  199.01  4408.8  195.77  4414.3  195.57
  4523.7  188.72  4579.2     184  4629.6  184.28  4716.7  185.11  4942.4  186.18
  4971.1  181.93  5038.3  176.33  5038.8  175.83  5061.7  176.33  5064.6  184.31
  5104.5  184.65  5143.5   183.4  5206.1  184.71  5216.4  187.04  5284.5  191.62
  5470.4  192.41  5538.2  194.69  5600.6  193.73  5673.3  196.56  5735.6   195.5
  5808.3  198.95  5881.4  197.98    5933  201.33  6005.7  200.46    6146  204.67
#Mann= 11 ,-1 , 0
  3755.5     .05       0  4304.9     .12       0  4408.8     .05       0
  4414.3    .035       0  4523.7     .05       0  4629.6     .12       0
  4716.7     .05       0  5038.3     .05       0  5061.7     .05       0
  5104.5     .07       0  5206.1     .05       0
Bank Sta=5038.3,5061.7
XS Rating Curve= 0 ,0
Exp/Cntr=0.3,0.1

Type RM Length L Ch R = 1 ,2808    ,281,281,281
BEGIN DESCRIPTION:
HOOSIER CREEK 4.0
END DESCRIPTION:
XS GIS Cut Line= 3
      2485717.63     13515063.54        2486725.       13514525.
        2486925.     13513075.01
#Sta/Elev= 30
  3861.6  199.06  4162.6  195.78  4352.9  190.96  4423.6  191.21  4538.2  194.38
  4551.5  194.22  4672.2  193.87    4750  181.27  4763.3  180.94  4876.5  184.49
    4908  185.72  4935.8  180.95  4951.9  181.57  4989.3  175.99  4989.8  175.49
  5012.7  175.99  5039.8  178.57  5044.9  183.96  5054.4  185.61  5084.6   188.6
  5111.8   188.6  5116.8  190.93  5471.9  190.71  6114.3   197.7    6185  200.51
  6245.5  199.36  6306.1  202.74    6378     202  6452.7  202.96  6467.6  202.87
#Mann= 13 ,-1 , 0
  3861.6     .05       0  4352.9     .12       0  4423.6     .05       0
  4538.2    .035       0  4551.5     .12       0    4750     .05       0
  4763.3      .1       0  4876.5     .12       0  4989.3     .05       0
  5012.7     .12       0  5471.9     .05       0    6378     .07       0
  6452.7     .05       0
Bank Sta=4989.3,5012.7
XS Rating Curve= 0 ,0
Exp/Cntr=0.3,0.1

Type RM Length L Ch R = 1 ,2527    ,408,408,408
BEGIN DESCRIPTION:
Mapping XS 0e34ee51
END DESCRIPTION:
XS GIS Cut Line= 3
      2486041.32     13515186.65      2486775.65     13514801.25
      2487519.34     13513308.69
#Sta/Elev= 30
  4152.1  200.03  4348.2  198.59  4593.9  200.21  4787.5  196.14  4882.6  193.48
  4935.5  192.57  4941.1  186.71  4946.8  183.54  4957.5   174.6    4958   174.1
  4981.2   174.6  4981.4  175.97  4992.6  178.65    5015  176.78  5031.8   180.2
    5062  182.36  5098.9  183.17  5126.9  185.98  5166.1  185.36    5194  188.76
  5412.3  191.71  5686.5  185.78  5826.4  194.24  5893.5   192.3  5955.1  184.63
  6040.7  185.73    6067  187.22  6284.4  189.14  6335.6  190.87    6649  193.83
#Mann= 7 ,-1 , 0
  4152.1     .05       0  4787.5     .12       0  4882.6      .1       0
  4957.5     .05       0  4981.2      .1       0    5062     .12       0
  6040.7     .05       0
Bank Sta=4957.5,4981.2
XS Rating Curve= 0 ,0
Exp/Cntr=0.3,0.1

Type RM Length L Ch R = 1 ,2119    ,437,437,437
BEGIN DESCRIPTION:
HOOSIER CREEK 3.0
END DESCRIPTION:
XS GIS Cut Line= 3
        2486359.     13515415.83        2487150.       13514825.
      2487825.02     13513674.97
#Sta/Elev= 30
  4012.7  202.36  4048.2  202.33    4210  200.84  4423.9  194.49  4531.4  191.83
  4589.3  190.31  4624.8  186.81  4731.6  188.45  4889.5  187.02  4895.8  182.49
  4904.1  183.01  4910.4  176.54  4948.5  174.26    4949  173.76  4972.3  174.26
  5002.9  174.55  5018.6  177.56    5040  178.21  5069.6  187.75    5083  188.17
  5289.9  179.95  5471.9  182.43  5711.6   181.4    5749  185.79  5776.9   186.8
  5807.9   183.6  5866.5  182.71  5952.1  187.34  6181.1  199.81  6333.5   204.5
#Mann= 9 ,-1 , 0
  4012.7     .07       0  4048.2     .12       0  4423.9     .05       0
  4531.4     .12       0  4948.5     .05       0  4972.3     .12       0
  5711.6     .05       0    5749      .1       0  5952.1     .05       0
Bank Sta=4948.5,4972.3
XS Rating Curve= 0 ,0
Exp/Cntr=0.3,0.1

Type RM Length L Ch R = 1 ,1682    ,288,288,288
BEGIN DESCRIPTION:
HOOSIER CREEK 2.0
END DESCRIPTION:
XS GIS Cut Line= 3
      2486274.96     13515675.02        2487575.       13514875.
      2488074.99     13513575.02
#Sta/Elev= 30
  3478.6  203.49  3579.3  203.87  3718.3  202.99    3981  192.79  4110.8   190.2
  4315.2  190.19  4453.2  190.67  4634.1  185.26  4758.5  185.48  4786.8  182.33
  4830.1   182.4  4860.1  181.44  4875.6  178.36  4887.9  180.04  4960.7  177.72
  4985.5   172.8    4986   172.3  5009.3   172.8  5026.5  184.77  5059.3  184.41
  5219.4  179.22  5305.1  182.56  5497.9  182.36  5552.6  177.45  5626.5  178.29
  5746.5  188.25  5885.8  188.47  6079.7  194.49  6300.8  205.64  6397.9  208.14
#Mann= 10 ,-1 , 0
  3478.6     .07       0  3579.3     .12       0  4110.8     .05       0
  4315.2     .12       0  4830.1      .1       0  4887.9     .12       0
  4985.5     .05       0  5009.3     .12       0  5059.3     .05       0
  6300.8     .07       0
Bank Sta=4985.5,5009.3
XS Rating Curve= 0 ,0
Exp/Cntr=0.3,0.1

Type RM Length L Ch R = 1 ,1394    ,283,283,283
BEGIN DESCRIPTION:
Mapping XS 8e7333ab
END DESCRIPTION:
XS GIS Cut Line= 3
      2486832.92     13515671.06       2487744.4     13515098.13
      2488233.98     13513921.07
#Sta/Elev= 30
  3920.7  190.59  4216.7  190.87  4404.1  190.75  4731.5  189.26  4898.7  192.46
    4914  192.07  4919.4  190.29  4935.2  188.38  4950.5  181.41  4956.4  175.85
  4965.7  172.07  4966.2  171.57  4989.5  172.07  4995.5  176.57  5022.7  177.15
  5032.8  176.28    5044  179.84  5067.5  183.14  5152.3  186.15  5201.4  185.35
  5433.9  183.72  5534.7   177.4  5628.8  181.66  5664.8  180.74  5717.9  176.11
  5741.8  177.42  5802.1  185.97  5842.6  188.46    6132  188.63  6272.1  194.15
#Mann= 8 ,-1 , 0
  3920.7     .12       0  4216.7     .05       0  4404.1     .12       0
  4919.4      .1       0  4965.7     .05       0  4989.5      .1       0
  5022.7     .12       0  5201.4     .05       0
Bank Sta=4965.7,4989.5
XS Rating Curve= 0 ,0
Exp/Cntr=0.3,0.1