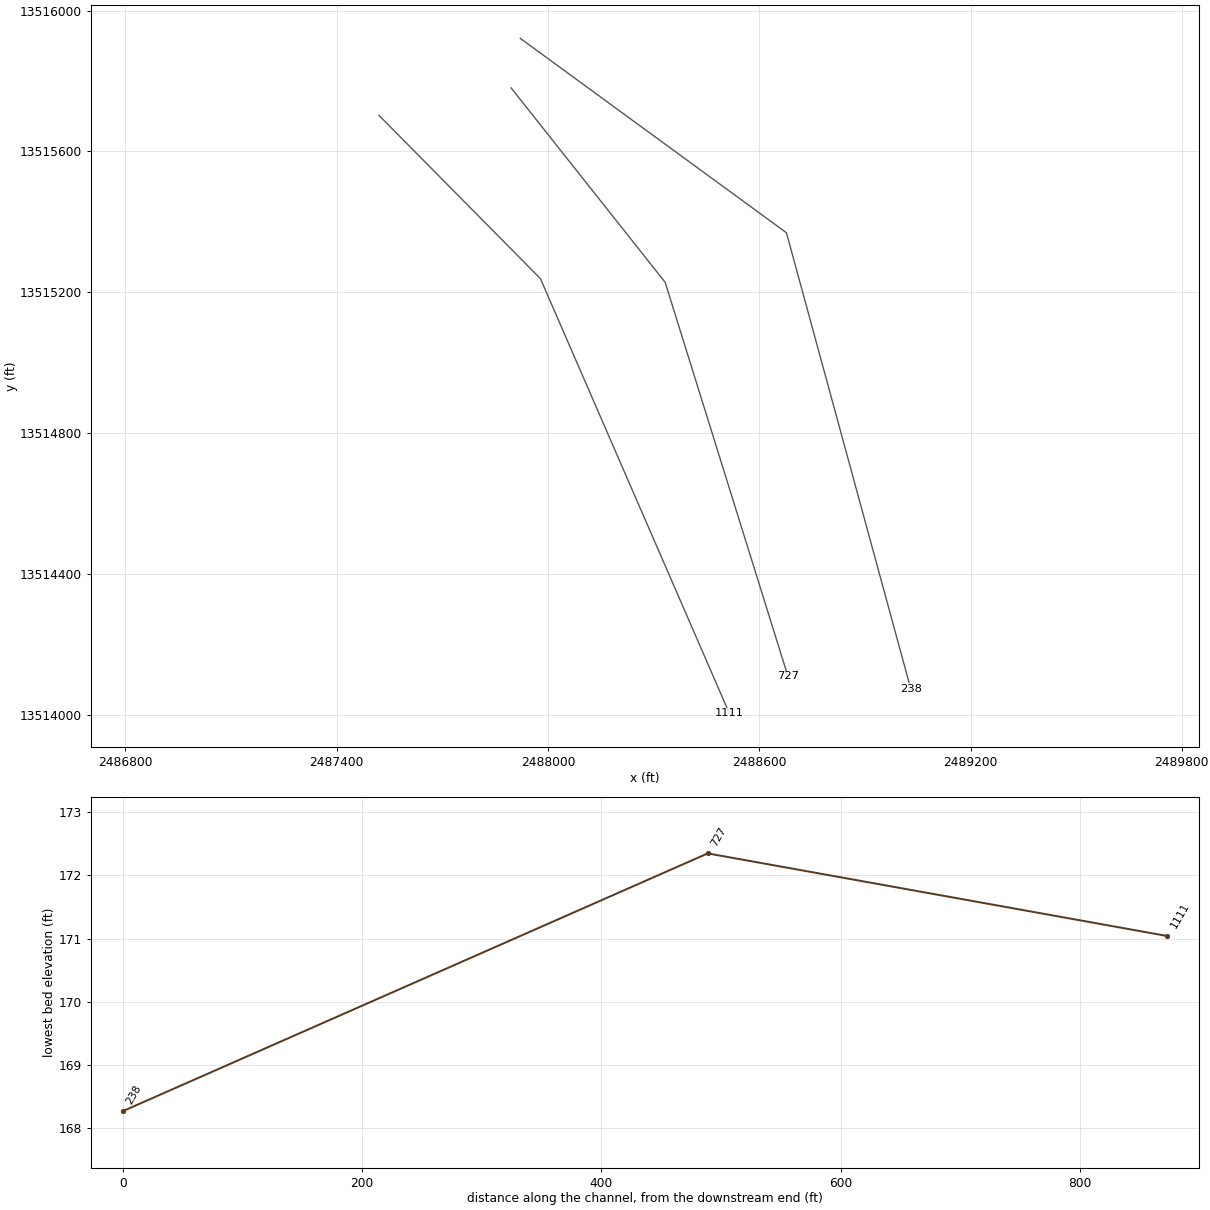
HEC-RAS study HOOSIER CREEK.prj: HOOSIER CREEK Base Level Engineering

--- HOOSIER CREEK.g01 (geometry) --- (continued)

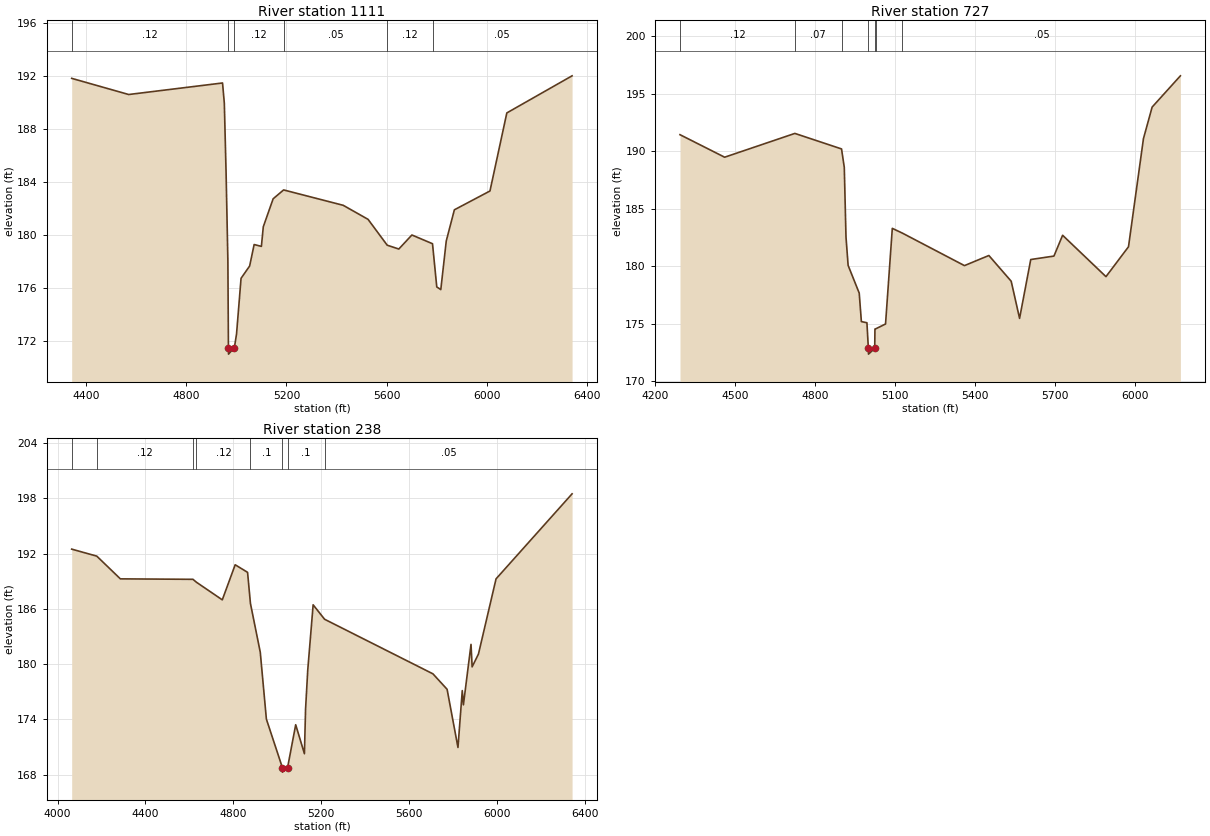
Type RM Length L Ch R = 1 ,1111    ,384,384,384
BEGIN DESCRIPTION:
Mapping XS d840fc3a
END DESCRIPTION:
XS GIS Cut Line= 3
      2487520.45     13515702.29      2487978.78     13515238.75
      2488515.25     13514004.35
#Sta/Elev= 30
  4342.5  191.85  4570.1  190.63  4944.8   191.5  4951.9  189.98    4959  184.68
  4966.1   178.1  4968.3  171.54  4968.8  171.04  4992.1  171.54  5000.7  172.56
  5018.7  176.76    5053  177.69    5071  179.31  5099.9  179.17  5107.5  180.65
  5146.8  182.76  5188.6  183.43  5426.5  182.27  5525.8  181.21  5602.2  179.26
  5648.5  178.97  5700.8  180.03  5783.1  179.37  5800.1  176.11  5816.2  175.91
    5838  179.58  5870.4  181.93  6012.5  183.35  6079.8  189.24  6340.3  192.04
#Mann= 6 ,-1 , 0
  4342.5     .12       0  4968.3     .05       0  4992.1     .12       0
  5188.6     .05       0  5602.2     .12       0  5783.1     .05       0
Bank Sta=4968.3,4992.1
XS Rating Curve= 0 ,0
Exp/Cntr=0.3,0.1

Type RM Length L Ch R = 1 ,727     ,489,489,489
BEGIN DESCRIPTION:
Mapping XS e2b8cdd9
END DESCRIPTION:
XS GIS Cut Line= 3
      2487895.44     13515780.43      2488332.95     13515228.33
      2488681.69     13514109.25
#Sta/Elev= 30
  4292.2  191.44  4459.6  189.48    4723  191.55    4898   190.2  4908.3   188.6
  4914.7  182.54  4922.7  180.07  4964.3  177.66  4972.4  175.18  4993.2  175.08
  4998.6  172.85  4999.1  172.35  5022.5  172.85  5023.3  174.53    5026  174.55
    5063  174.97  5088.4  183.29  5125.9  182.88    5359  180.05  5450.5  180.93
  5534.3  178.69  5565.7  175.46  5607.6  180.58  5694.6  180.88  5727.1  182.69
  5889.7  179.09  5974.2  181.69  6030.3   191.1  6062.8  193.84  6168.8  196.56
#Mann= 7 ,-1 , 0
  4292.2     .12       0    4723     .07       0    4898     .12       0
  4998.6     .05       0  5022.5     .12       0    5026      .1       0
  5125.9     .05       0
Bank Sta=4998.6,5022.5
XS Rating Curve= 0 ,0
Exp/Cntr=0.3,0.1

Type RM Length L Ch R = 1 ,238     ,0,0,0
BEGIN DESCRIPTION:
HOOSIER CREEK 1.0
END DESCRIPTION:
XS GIS Cut Line= 3
      2487921.45     13515921.07      2488677.33     13515369.03
      2489030.42      13514073.7
#Sta/Elev= 30
    4064  192.49  4178.3  191.73  4285.7  189.26  4616.4  189.21  4631.7   188.9
  4749.8  186.98  4808.5  190.79  4864.9  189.97    4878  186.59  4922.8  181.28
  4950.6  174.02  5023.3  168.76  5023.8  168.26  5047.2  168.76  5084.1  173.41
  5123.8  170.26    5129  175.09  5138.9  179.33  5163.5  186.44  5215.7  184.87
    5709  178.94  5773.5  177.26    5823  170.94  5842.6  177.12  5847.8  175.57
  5882.4  182.14  5887.5   179.7  5916.3  181.09  5996.4  189.26  6342.6   198.5
#Mann= 8 ,-1 , 0
    4064     .05       0  4178.3     .12       0  4616.4     .07       0
  4631.7     .12       0    4878      .1       0  5023.3     .05       0
  5047.2      .1       0  5215.7     .05       0
Bank Sta=5023.3,5047.2
XS Rating Curve= 0 ,0
Exp/Cntr=0.3,0.1

Chan Stop Cuts=-1
Use User Specified Reach Order=0
Composite Channel Slope=5