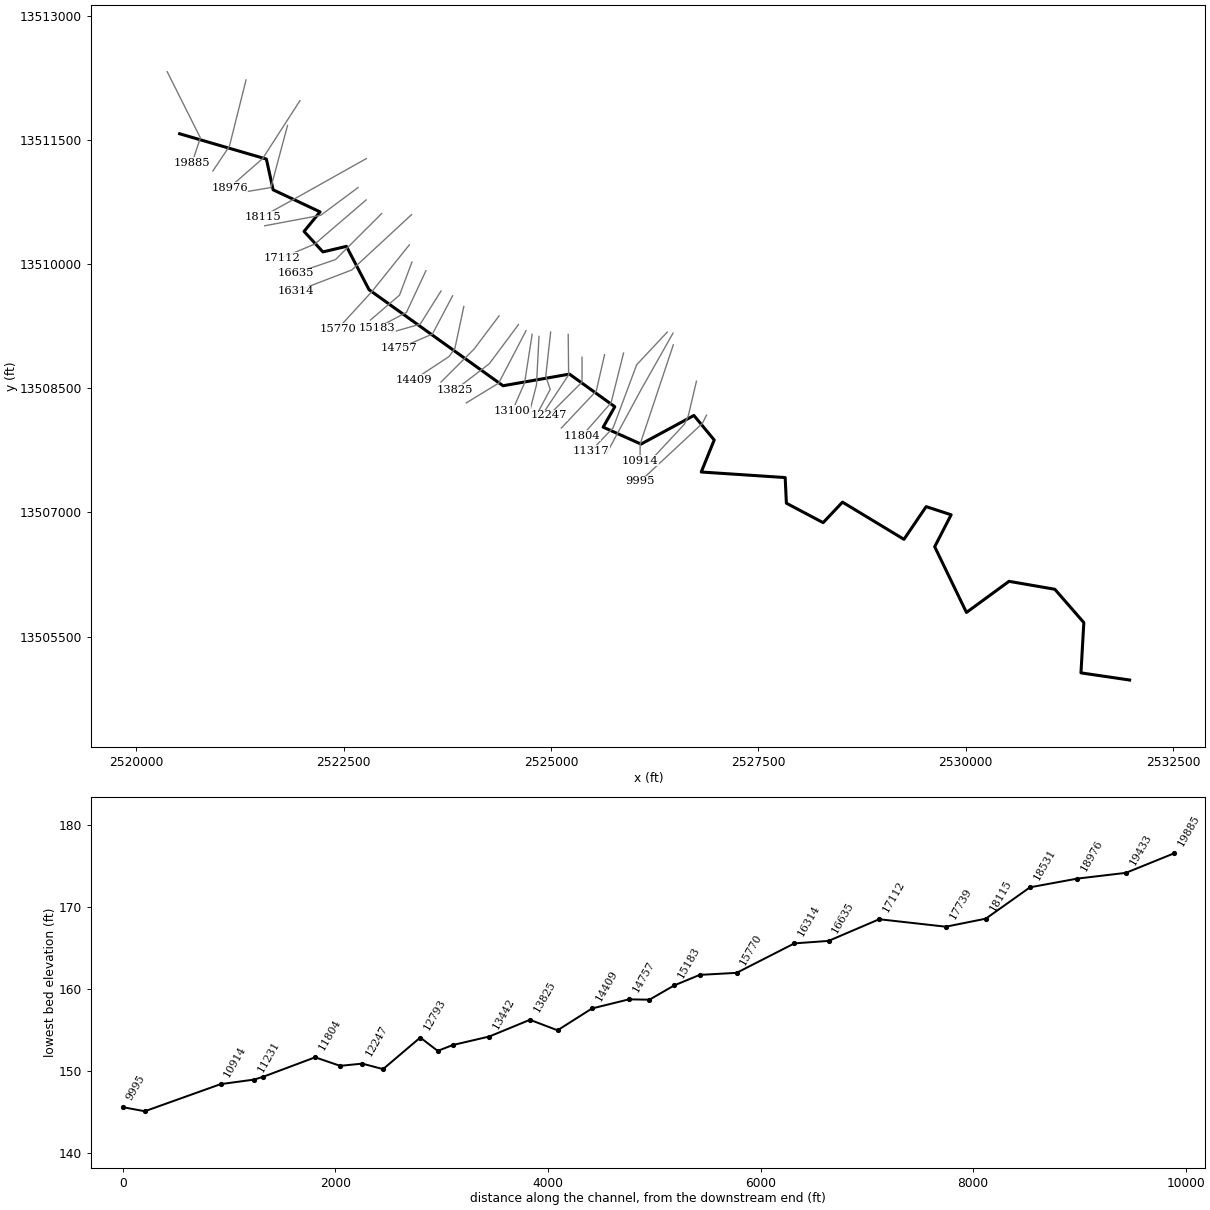
--- JOHNS CREEK.prj (project) ---

Proj Title=JOHNS CREEK Base Level Engineering
Current Plan=p01
Default Exp/Contr=0.3,0.1
English Units
Geom File=g01
Flow File=f01
Plan File=p01
Y Axis Title=Elevation
X Axis Title(PF)=Main Channel Distance
X Axis Title(XS)=Station
BEGIN DESCRIPTION:
JOHNS CREEK
END DESCRIPTION:
DSS Export Rating Curves= 0
DSS Export Rating Curve Sorted= 0
DSS Export Volume Flow Curves= 0
DXF OffsetX= 0
DXF OffsetY= 0
DXF ScaleX= 1
DXF ScaleY= 10

--- JOHNS CREEK.p01 (plan) ---

Plan Title=Multiple Run
Program Version=4.10
Short Identifier=Multiple
Geom File=g01
Flow File=f01
Subcritical Flow
K Sum by GR= 0
Std Step Tol= 0.01
Critical Tol= 0.01
Num of Std Step Trials= 20
Max Error Tol= 0.3
Flow Tol Ratio= 0.001
Split Flow NTrial= 30
Split Flow Tol= 0.02
Split Flow Ratio= 0.02
Log Output Level= 0
Friction Slope Method= 1
Unsteady Friction Slope Method= 2
Unsteady Bridges Friction Slope Method= 1
Parabolic Critical Depth
Global Vel Dist= 1 , 1 , 1
Global Log Level= 0
CheckData=True
Encroach Param=-1 ,0,0, 0
BEGIN DESCRIPTION:
Multiple Run
END DESCRIPTION:
Computation Interval=1HOUR
Output Interval=1HOUR
Run HTab= 0
Run UNet= 0
Run PostProcess= 0
Run WQNet= 0
UNET Theta= 1
UNET Theta Warmup= 1
UNET ZTol= 0.02
UNET ZSATol= 0.05
UNET MxIter= 20
UNET MaxInSteps= 0
UNET DtIC= 0
UNET DtMin= 0
UNET MaxCRTS= 20
UNET WFStab= 2
UNET SFStab= 1
UNET WFX= 1
UNET SFX= 1
UNET DSS MLevel= 4
UNET DZMax Abort= 100
UNET Convert EG Bridges= 0
UNET Use Existing IB Tables=-1
UNET Froude Reduction=False
UNET Froude Limit= 1
UNET Froude Power= 10
UNET Time Slicing=0,0, 5
UNET Junction Losses=0
Instantaneous Interval=1HOUR
Write IC File= 0
Write IC File at Sim End=0
Echo Input=False
Echo Parameters=False
Echo Output=False
Write Detailed= 0
WQ AD Non Conservative
WQ ULTIMATE=-1
WQ Max Comp Step=1HOUR
WQ Output Interval=15MIN
WQ Output Selected Increments= 0
WQ Output face flow=0
WQ Output face velocity=0
WQ Output face area=0
WQ Output face dispersion=0
WQ Output cell volume=0
WQ Output cell surface area=0
WQ Output cell continuity=0
WQ Output cumulative cell continuity=0
WQ Output face conc=0
WQ Output face dconc_dx=0
WQ Output face courant=0
WQ Output face peclet=0
WQ Output face adv mass=0
WQ Output face disp mass=0
WQ Output cell mass=0
WQ Output cell source sink temp=0
WQ Output cell source sink nsm=0
WQ Output MaxMinRange=-1
WQ Daily Max Min Mean=-1
WQ Daily Range=0
WQ Daily Time=0
WQ Create Restart=0
WQ Fixed Restart=0
WQ System Summary=0
WQ Use Fixed Temperature=0
Sorting and Armoring Iterations= 10
XS Update Threshold= 0.02
Hydraulics Update Threshold= 0.02
Energy Slope Method= 1
Volume Change Method= 0
XS Weighting Method= 0
Number of US Weighted Cross Sections= 1
Number of DS Weighted Cross Sections= 1
Upstream XS Weight=0.25
Main XS Weight=0.5
Downstream XS Weight=0.25
Number of DS XS's Weighted with US Boundary= 1
Upstream Boundary Weight= 1
Weight of XSs Associated with US Boundary= 0
Number of US XS's Weighted with DS Boundary= 1
Downstream Boundary Weight= 0.5
Weight of XSs Associated with DS Boundary= 0.5
Sediment Output Level= 4
Mass or Volume Output= 0
Output Increment Type= 1
Profile and TS Output Increment= 10
XS Output Flag= 0
XS Output Increment= 10
Disregard all LS=0
Disregard all Conn=0
Disregard all Breaches=0
Disregard all Pumps=0

--- JOHNS CREEK.f01 (steady flow) ---

Flow Title=Multiple
Number of Profiles=7
Profile Names=10-year,25-year,50-year,1pct_min,100-year,1pct_plu,500-year
River Rch & RM= JOHNS CREEK,Reach-1,19885
     687    1102    1474     954    1904    3800    3143
River Rch & RM= JOHNS CREEK,Reach-1,19433
     896    1456    1965    1282    2557    5102    4285
River Rch & RM= JOHNS CREEK,Reach-1,16635
    1055    1727    2343    1535    3063    6112    5180
River Rch & RM= JOHNS CREEK,Reach-1,14409
    1231    2027    2759    1813    3617    7217    6154
River Rch & RM= JOHNS CREEK,Reach-1,9318
    1293    2132    2905    1910    3810    7603    6490
River Rch & RM= JOHNS CREEK,Reach-1,6369
    1417    2345    3202    2109    4209    8397    7195
Boundary for River Rch & Prof#=JOHNS CREEK,Reach-1,1
Up Type=0
Dn Type=3
Dn Slope=0.005
Boundary for River Rch & Prof#=JOHNS CREEK,Reach-1,2
Up Type=0
Dn Type=3
Dn Slope=0.005
Boundary for River Rch & Prof#=JOHNS CREEK,Reach-1,3
Up Type=0
Dn Type=3
Dn Slope=0.005
Boundary for River Rch & Prof#=JOHNS CREEK,Reach-1,4
Up Type=0
Dn Type=3
Dn Slope=0.005
Boundary for River Rch & Prof#=JOHNS CREEK,Reach-1,5
Up Type=0
Dn Type=3
Dn Slope=0.005
Boundary for River Rch & Prof#=JOHNS CREEK,Reach-1,6
Up Type=0
Dn Type=3
Dn Slope=0.005
Boundary for River Rch & Prof#=JOHNS CREEK,Reach-1,7
Up Type=0
Dn Type=3
Dn Slope=0.005

--- JOHNS CREEK.g01 (geometry) ---

Geom Title=Existing Conditions
Program Version=4.10

River Reach=JOHNS CREEK     ,Reach-1
Reach XY= 30
        2520525.       13511575.      2521570.24     13511269.42
      2521651.48     13510897.87        2522217.     13510631.33
      2522024.52     13510395.17      2522251.64     13510147.44
      2522535.11      13510214.7      2522807.34     13509691.41
      2524422.56     13508530.47      2525223.41     13508671.18
      2525769.94     13508277.29      2525629.59     13508030.26
      2526085.64     13507825.55      2526723.53     13508171.47
      2526967.92       13507875.      2526811.66     13507488.33
      2527823.44     13507421.24      2527837.93     13507111.37
      2528281.05     13506876.58      2528514.25     13507124.32
      2529255.11     13506674.89      2529522.45     13507070.02
      2529823.75     13506971.49      2529625.53     13506585.68
      2530008.21     13505791.39      2530521.42     13506167.51
       2531073.5     13506071.53      2531422.94     13505669.15
      2531388.46     13505061.43        2531975.       13504975.

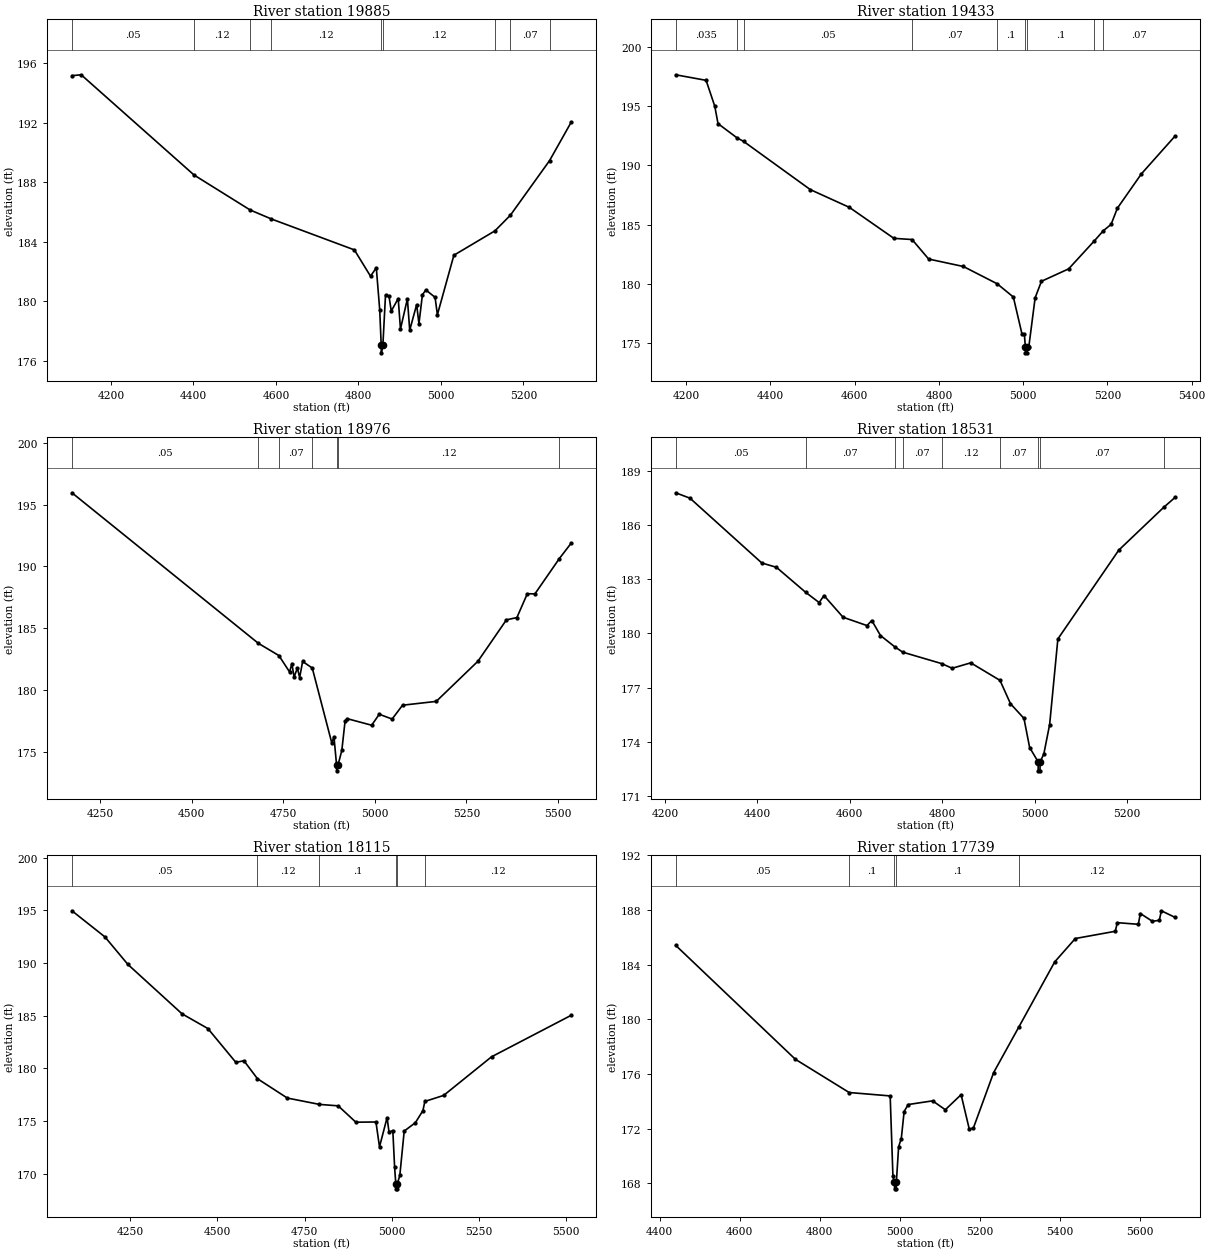
Type RM Length L Ch R = 1 ,19885   ,452,452,452
BEGIN DESCRIPTION:
JOHNS CREEK 36.0
END DESCRIPTION:
XS GIS Cut Line= 3
      2520374.98     13512325.04        2520775.       13511525.
        2520675.       13511225.
#Sta/Elev= 30
  4105.5  195.16  4127.9  195.22  4401.7  188.48  4537.7  186.13  4588.9  185.53
  4790.3  183.45  4829.5  181.68  4843.5  182.25  4851.8  179.41  4855.4  177.03
  4855.7  176.53  4859.4  177.03  4865.8   180.4  4874.2  180.35  4879.8  179.34
  4896.6  180.18  4902.1  178.13  4918.9  180.16  4924.5  178.05  4941.3  179.77
  4946.9  178.49  4955.3  180.43  4963.6  180.76    4986  180.26  4991.6  179.09
  5031.6  183.09  5131.2  184.73  5168.6  185.78  5263.6  189.45  5316.2  192.04
#Mann= 9 ,-1 , 0
  4105.5     .05       0  4401.7     .12       0  4537.7    .035       0
  4588.9     .12       0  4855.4     .05       0  4859.4     .12       0
  5131.2      .1       0  5168.6     .07       0  5263.6     .12       0
Bank Sta=4855.4,4859.4
XS Rating Curve= 0 ,0
Exp/Cntr=0.3,0.1

Type RM Length L Ch R = 1 ,19433   ,457,457,457
BEGIN DESCRIPTION:
JOHNS CREEK 35.0
END DESCRIPTION:
XS GIS Cut Line= 3
      2521325.01     13512225.02        2521125.       13511425.
        2520925.       13511125.
#Sta/Elev= 30
  4175.1  197.67  4247.3   197.2  4267.9  195.01  4275.6  193.54  4320.6  192.34
  4336.2  192.04  4494.7  187.96  4587.4  186.46  4693.1  183.84  4736.2  183.74
  4775.6  182.09    4858  181.46  4938.2     180  4976.6  178.88  4997.2  175.74
  5002.7  175.74  5005.2  174.66  5005.4  174.16  5009.1  174.16  5009.4  174.66
  5013.3  174.66  5028.3  178.81  5043.3  180.21  5107.9  181.26  5168.7  183.62
  5190.1  184.48  5208.6  185.02  5223.6  186.39  5280.7   189.3  5360.3  192.48
#Mann= 9 ,-1 , 0
  4175.1    .035       0  4320.6     .07       0  4336.2     .05       0
  4736.2     .07       0  4938.2      .1       0  5005.2     .05       0
  5009.4      .1       0  5168.7     .12       0  5190.1     .07       0
Bank Sta=5005.2,5009.4
XS Rating Curve= 0 ,0
Exp/Cntr=0.3,0.1

Type RM Length L Ch R = 1 ,18976   ,445,445,445
BEGIN DESCRIPTION:
JOHNS CREEK 34.0
END DESCRIPTION:
XS GIS Cut Line= 3
      2521974.98     13511974.96        2521525.       13511275.
      2521125.02     13510925.02
#Sta/Elev= 30
  4172.9  195.96  4681.9  183.78    4738  182.79  4767.3  181.46  4773.5  182.14
  4779.5  181.05  4788.7  181.78  4794.7     181  4802.9  182.31  4829.2  181.78
  4882.5  175.72  4888.5  176.21  4895.5  173.96  4895.8  173.46  4899.8  173.96
  4909.9  175.11  4918.8  177.48  4924.8  177.68  4991.5  177.15  5012.1  178.04
  5047.3  177.65  5075.7  178.77  5167.8  179.08  5281.7  182.33  5359.5  185.68
    5388  185.86  5416.5  187.79  5437.3  187.78  5503.8  190.63  5536.5  191.89
#Mann= 7 ,-1 , 0
  4172.9     .05       0  4681.9     .12       0    4738     .07       0
  4829.2     .12       0  4895.5     .05       0  4899.8     .12       0
  5503.8     .07       0
Bank Sta=4895.5,4899.8
XS Rating Curve= 0 ,0
Exp/Cntr=0.3,0.1

Type RM Length L Ch R = 1 ,18531   ,416,416,416
BEGIN DESCRIPTION:
JOHNS CREEK 33.0
END DESCRIPTION:
XS GIS Cut Line= 3
      2521824.99     13511674.97        2521625.       13510925.
      2521325.01       13510875.
#Sta/Elev= 30
  4223.5  187.77  4254.5  187.47  4409.8  183.89  4441.5  183.65  4504.6  182.27
    4534   181.7  4544.3  182.09  4585.7  180.89  4637.4  180.43  4647.8  180.71
  4666.6  179.88  4697.3  179.26  4714.7  178.96  4798.7  178.33  4821.8  178.07
  4861.9  178.37  4925.2   177.4  4947.9  176.11    4977   175.3  4989.3  173.69
  5007.7   172.9  5007.9   172.4  5011.7   172.4    5012   172.9    5020  173.33
  5032.6  174.96  5050.4  179.69  5182.2   184.6  5279.2  186.96  5303.8  187.51
#Mann= 9 ,-1 , 0
  4223.5     .05       0  4504.6     .07       0  4697.3     .12       0
  4714.7     .07       0  4798.7     .12       0  4925.2     .07       0
  5007.7     .05       0    5012     .07       0  5279.2     .12       0
Bank Sta=5007.7,5012
XS Rating Curve= 0 ,0
Exp/Cntr=0.3,0.1

Type RM Length L Ch R = 1 ,18115   ,376,376,376
BEGIN DESCRIPTION:
JOHNS CREEK 32.0
END DESCRIPTION:
XS GIS Cut Line= 3
      2522775.01     13511275.01        2521975.       13510825.
      2521524.97     13510574.99
#Sta/Elev= 30
  4082.6  194.95  4177.3  192.47  4243.2  189.86  4398.4  185.18  4472.7  183.78
    4553  180.57    4576  180.73    4615  179.02  4700.6  177.19  4792.4  176.59
  4846.6  176.45  4897.2   174.9  4954.9  174.92  4965.1  172.56  4986.8  175.33
  4992.5  173.95  5003.3  174.11  5008.5  170.61  5011.8  169.08  5012.2  168.58
  5016.3  168.58  5016.6  169.08  5023.4  169.86    5036  174.06    5068  174.85
  5089.7     176  5095.2  176.87  5149.2  177.44  5286.5   181.1  5515.3  185.04
#Mann= 6 ,-1 , 0
  4082.6     .05       0    4615     .12       0  4792.4      .1       0
  5011.8     .05       0  5016.6      .1       0  5095.2     .12       0
Bank Sta=5011.8,5016.6
XS Rating Curve= 0 ,0
Exp/Cntr=0.3,0.1

Type RM Length L Ch R = 1 ,17739   ,627,627,627
BEGIN DESCRIPTION:
JOHNS CREEK 31.0
END DESCRIPTION:
XS GIS Cut Line= 3
      2522674.99     13510924.99      2522226.18     13510590.41
      2521549.45     13510463.13
#Sta/Elev= 30
  4440.2  185.42  4739.5  177.08  4873.9  174.65  4976.5   174.4  4983.4  168.51
  4987.2   168.1  4987.5   167.6  4991.6   167.6    4992   168.1  4997.6  170.68
  5004.3  171.28  5011.4  173.26  5021.6  173.77  5082.6  174.04  5114.3  173.39
  5153.8  174.49  5174.2  171.98  5184.4  172.04  5235.2  176.11  5298.5  179.46
  5387.9  184.21  5439.4  185.92  5539.3  186.45  5544.4  187.08  5596.9  186.96
    5602  187.75  5632.1  187.18  5649.4  187.25  5654.5  187.95  5688.6  187.47
#Mann= 5 ,-1 , 0
  4440.2     .05       0  4873.9      .1       0  4987.2     .05       0
    4992      .1       0  5298.5     .12       0
Bank Sta=4987.2,4992
XS Rating Curve= 0 ,0
Exp/Cntr=0.3,0.1

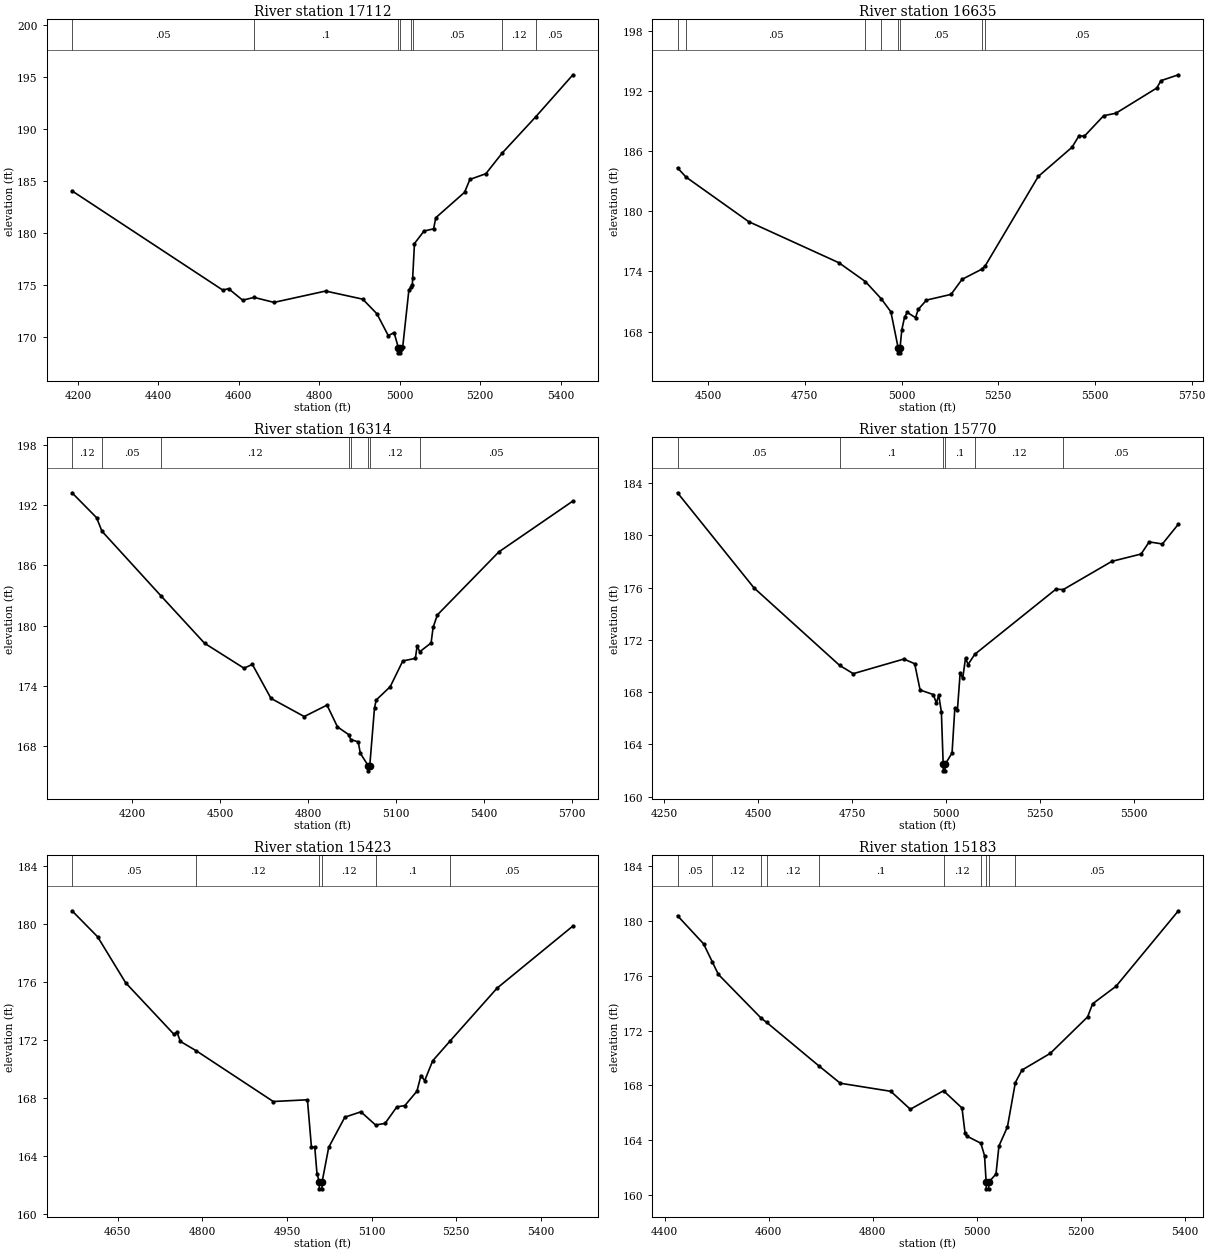
Type RM Length L Ch R = 1 ,17112   ,477,477,477
BEGIN DESCRIPTION:
Mapping XS 5e7343bd
END DESCRIPTION:
XS GIS Cut Line= 3
       2522772.9     13510775.54      2522152.22     13510241.67
      2521758.65     13510077.33
#Sta/Elev= 30
  4185.6  184.08  4560.4  174.54  4574.7  174.68  4609.8  173.57  4638.1  173.84
  4687.7  173.36    4816  174.45  4908.3  173.67  4943.4  172.27  4971.9  170.16
  4986.2  170.46  4996.8  169.01  4997.1  168.51  5001.2  168.51  5001.6  169.01
  5007.7  169.07    5023  174.55  5027.5   174.8  5031.5  175.03  5032.4   175.7
  5036.9  179.02  5060.7  180.22  5084.5  180.43  5089.9   181.5  5161.4  183.94
  5174.7  185.18  5214.4  185.73  5254.6   187.7  5338.8  191.22  5430.8  195.24
#Mann= 8 ,-1 , 0
  4185.6     .05       0  4638.1      .1       0  4996.8     .05       0
  5001.6      .1       0  5027.5     .12       0  5032.4     .05       0
  5254.6     .12       0  5338.8     .05       0
Bank Sta=4996.8,5001.6
XS Rating Curve= 0 ,0
Exp/Cntr=0.3,0.1

Type RM Length L Ch R = 1 ,16635   ,321,321,321
BEGIN DESCRIPTION:
Mapping XS 40d153e7
END DESCRIPTION:
XS GIS Cut Line= 3
      2522959.52     13510610.61      2522403.96     13510055.04
       2521922.2     13509890.11
#Sta/Elev= 30
  4420.9  184.35  4442.9  183.43  4604.8  178.98  4838.2  174.87  4906.6  172.99
  4947.6  171.27  4972.5  169.97  4991.3  166.37  4991.6  165.87  4995.8  165.87
  4996.2  166.37  5000.8  168.18  5007.9  169.44    5015  169.91  5036.2  169.38
  5043.2  170.21  5064.5  171.14  5128.1  171.71  5156.4  173.21  5208.1  174.24
  5216.8  174.59  5353.5  183.49  5440.8  186.41  5459.2  187.58  5472.1  187.49
  5522.6  189.56  5554.3  189.81    5660  192.33  5670.6  193.06  5715.8  193.65
#Mann= 8 ,-1 , 0
  4420.9     .12       0  4442.9     .05       0  4906.6      .1       0
  4947.6     .05       0  4991.3     .05       0  4996.2     .05       0
  5208.1     .12       0  5216.8     .05       0
Bank Sta=4991.3,4996.2
XS Rating Curve= 0 ,0
Exp/Cntr=0.3,0.1

Type RM Length L Ch R = 1 ,16314   ,544,544,544
BEGIN DESCRIPTION:
Mapping XS 1bc41679
END DESCRIPTION:
XS GIS Cut Line= 3
      2523320.35     13510598.02      2522599.85      13509929.6
      2521923.83     13509669.59
#Sta/Elev= 30
  3996.1  193.23  4079.9  190.75    4098  189.41  4299.4  182.97  4447.9  178.26
  4582.2  175.78  4610.6  176.16  4674.1  172.78  4787.5  170.97  4865.1  172.11
  4900.8  169.94  4938.7  169.18  4946.1  168.68  4971.7  168.45  4978.5  167.32
  5005.8  166.07  5006.2  165.57  5010.8  166.07    5027  171.84  5032.9  172.62
  5080.5  173.94  5123.4   176.5  5166.2  176.76  5172.2  177.98  5181.3  177.42
  5219.8  178.29  5226.8  179.85  5241.2  181.08  5450.8  187.35  5703.2  192.41
#Mann= 8 ,-1 , 0
  3996.1     .12       0    4098     .05       0  4299.4     .12       0
  4938.7     .05       0  4946.1     .12       0  5005.8     .05       0
  5010.8     .12       0  5181.3     .05       0
Bank Sta=5005.8,5010.8
XS Rating Curve= 0 ,0
Exp/Cntr=0.3,0.1

Type RM Length L Ch R = 1 ,15770   ,347,347,347
BEGIN DESCRIPTION:
Mapping XS f71167f6
END DESCRIPTION:
XS GIS Cut Line= 3
      2523293.72       13510233.      2522842.33     13509668.76
      2522431.18     13509218.65
#Sta/Elev= 30
  4285.2  183.27  4488.6  175.99  4716.5  170.05  4752.7  169.42  4887.2  170.54
    4916  170.18  4930.4  168.17  4965.6  167.82  4973.6  167.17    4980  167.78
    4987  166.48  4991.8  162.48  4992.2  161.98  4996.7  161.98  4997.1  162.48
  5015.4  163.35  5022.8  166.79  5029.6  166.62    5037  169.49  5043.8  169.07
  5051.2  170.62    5058  170.12  5075.7   170.9  5291.7  175.89  5311.3  175.86
  5440.4  178.02  5518.1  178.58  5539.7  179.51  5574.8  179.35  5617.4  180.87
#Mann= 6 ,-1 , 0
  4285.2     .05       0  4716.5      .1       0  4991.8     .05       0
  4997.1      .1       0  5075.7     .12       0  5311.3     .05       0
Bank Sta=4991.8,4997.1
XS Rating Curve= 0 ,0
Exp/Cntr=0.3,0.1

Type RM Length L Ch R = 1 ,15423   ,240,240,240
BEGIN DESCRIPTION:
JOHNS CREEK 27.0
END DESCRIPTION:
XS GIS Cut Line= 3
      2523324.98     13510024.95        2523175.       13509625.
      2522825.02     13509325.02
#Sta/Elev= 30
  4568.9   180.9  4614.2  179.11  4664.1  175.93  4749.5  172.39  4754.9  172.53
  4761.1  171.89  4789.1  171.25  4925.7  167.75  4986.3  167.87  4993.4   164.6
  4999.3   164.6  5003.2  162.78  5007.1  162.23  5007.5  161.73    5012  161.73
  5012.4  162.23    5024  164.59  5052.6  166.67  5081.1  167.04  5107.1  166.13
  5123.9  166.24  5144.8  167.38    5159  167.47  5180.4  168.46  5187.6  169.54
  5194.2  169.19  5208.4  170.56  5239.6  171.94  5322.6  175.57    5457  179.85
#Mann= 6 ,-1 , 0
  4568.9     .05       0  4789.1     .12       0  5007.1     .05       0
  5012.4     .12       0  5107.1      .1       0  5239.6     .05       0
Bank Sta=5007.1,5012.4
XS Rating Curve= 0 ,0
Exp/Cntr=0.3,0.1

Type RM Length L Ch R = 1 ,15183   ,233,233,233
BEGIN DESCRIPTION:
Mapping XS 10da5cf6
END DESCRIPTION:
XS GIS Cut Line= 3
      2523493.38     13509920.51      2523258.99     13509417.02
      2522899.37     13509226.38
#Sta/Elev= 30
  4424.9  180.39  4474.9  178.34  4491.5  177.04  4503.3  176.11  4585.9   172.9
  4595.9  172.61  4696.1  169.44  4737.6  168.16  4834.7  167.57  4872.2  166.26
    4936  167.61  4971.5  166.35  4977.4  164.51  4980.3  164.31  5007.7  163.78
  5014.8  162.87  5017.9  160.95  5018.3  160.45  5022.8  160.45  5023.2  160.95
  5036.8  161.53  5042.5  163.58  5058.8  164.97    5074  168.21  5086.7  169.12
  5141.1  170.34  5212.8     173  5222.5  173.96  5267.5  175.24  5387.3  180.75
#Mann= 10 ,-1 , 0
  4424.9     .05       0  4491.5     .12       0  4585.9     .07       0
  4595.9     .12       0  4696.1      .1       0    4936     .12       0
  5007.7      .1       0  5017.9     .05       0  5023.2      .1       0
    5074     .05       0
Bank Sta=5017.9,5023.2
XS Rating Curve= 0 ,0
Exp/Cntr=0.3,0.1

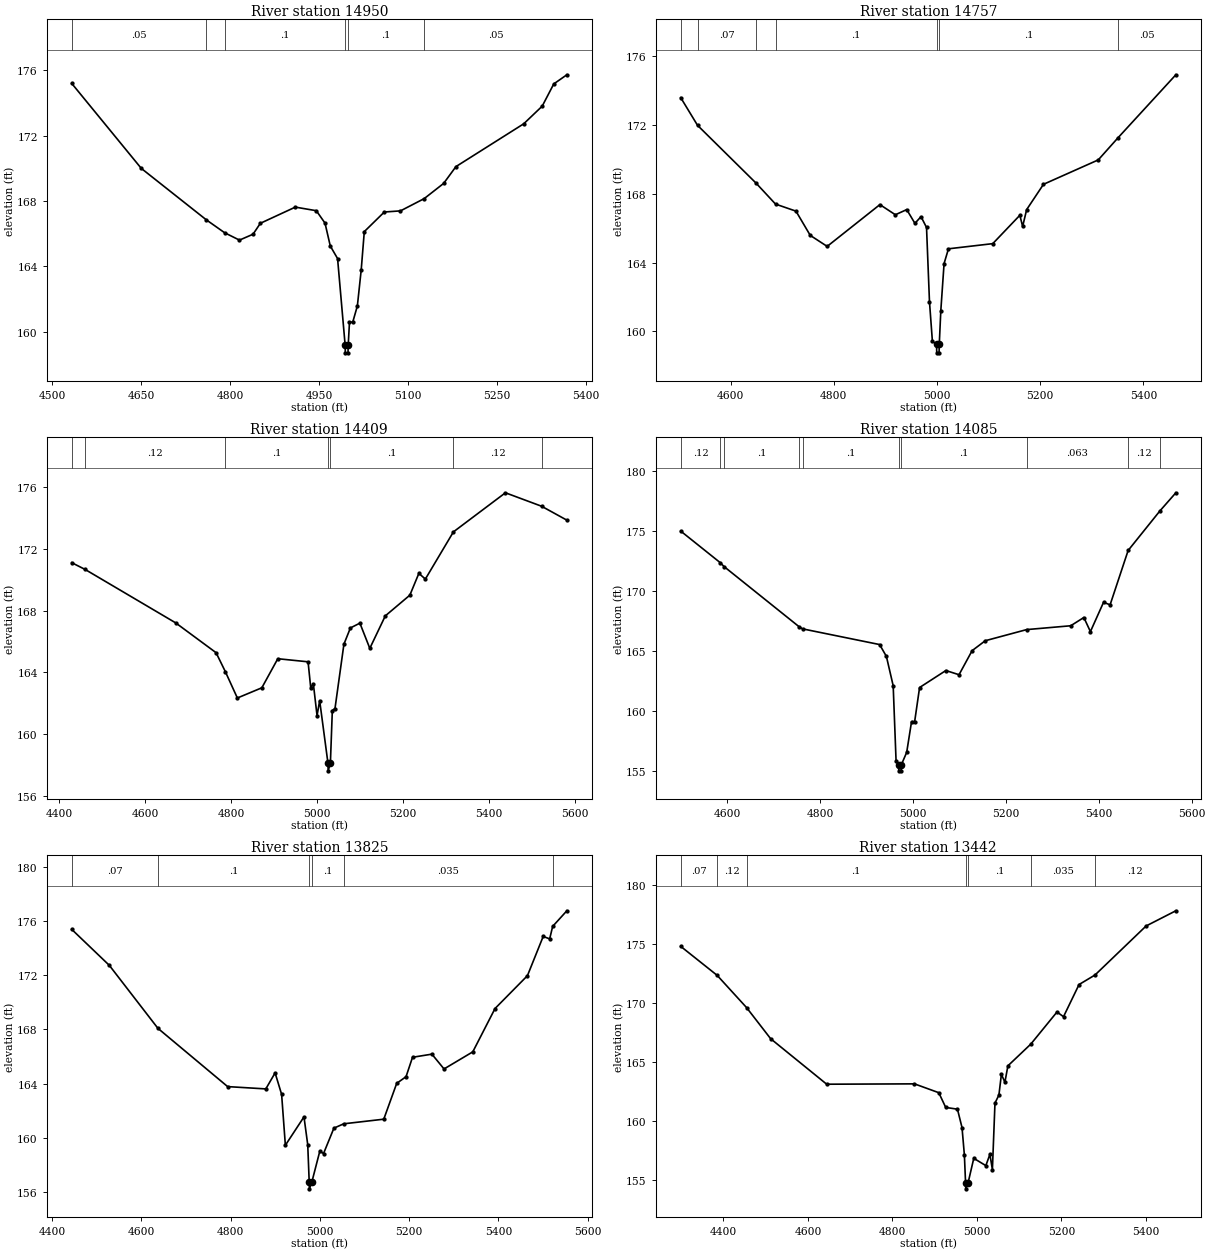
Type RM Length L Ch R = 1 ,14950   ,193,193,193
BEGIN DESCRIPTION:
JOHNS CREEK 26.0
END DESCRIPTION:
XS GIS Cut Line= 3
      2523675.02     13509675.03        2523425.       13509275.
      2523075.03     13509175.01
#Sta/Elev= 30
  4532.7   175.2  4650.1     170  4759.9  166.85  4790.8  166.06  4815.8  165.61
  4838.7  165.97  4851.1  166.64  4910.1  167.63  4945.5  167.41  4960.2  166.65
  4969.1  165.25  4981.4  164.48  4994.1  159.21  4994.5  158.71    4999  158.71
  4999.4  159.21  5001.5  160.59    5007  160.59  5014.8  161.58  5021.3  163.79
  5026.5  166.13  5060.3  167.33  5087.6   167.4  5127.6  168.15  5160.4  169.08
  5181.2  170.11  5295.6  172.73  5326.8  173.81  5346.3  175.17  5368.4  175.73
#Mann= 6 ,-1 , 0
  4532.7     .05       0  4759.9     .07       0  4790.8      .1       0
  4994.1     .05       0  4999.4      .1       0  5127.6     .05       0
Bank Sta=4994.1,4999.4
XS Rating Curve= 0 ,0
Exp/Cntr=0.3,0.1

Type RM Length L Ch R = 1 ,14757   ,348,348,348
BEGIN DESCRIPTION:
Mapping XS b67cf8f9
END DESCRIPTION:
XS GIS Cut Line= 3
      2523814.58     13509616.71       2523571.5     13509154.86
      2523169.38     13508981.53
#Sta/Elev= 30
  4503.2  173.59  4535.8  171.98  4648.9  168.63    4687   167.4  4726.6  166.99
  4754.3  165.58  4787.1  164.94  4889.3  167.37  4919.3  166.78  4941.3  167.08
  4957.2  166.28    4969  166.67  4979.7  166.04  4985.4  161.73  4991.1  159.41
  4999.1  159.25  4999.5  158.75    5004  158.75  5004.4  159.25  5007.4  161.21
  5013.7  163.94  5022.2   164.8  5108.1   165.1  5160.6  166.75    5166   166.1
  5173.8  167.08  5206.4  168.55  5312.6  169.97  5350.4  171.24    5463  174.92
#Mann= 7 ,-1 , 0
  4503.2     .05       0  4535.8     .07       0  4648.9     .12       0
    4687      .1       0  4999.1     .05       0  5004.4      .1       0
  5350.4     .05       0
Bank Sta=4999.1,5004.4
XS Rating Curve= 0 ,0
Exp/Cntr=0.3,0.1

Type RM Length L Ch R = 1 ,14409   ,324,324,324
BEGIN DESCRIPTION:
Mapping XS ae40e367
END DESCRIPTION:
XS GIS Cut Line= 4
      2523949.97     13509488.19      2523842.33     13508981.25
      2523772.89     13508884.03      2523342.83     13508599.64
#Sta/Elev= 30
  4428.9   171.1  4460.2  170.66  4670.9  167.21  4765.1  165.28  4786.6  164.06
  4814.7  162.35  4871.7  163.01  4908.9  164.89  4979.4  164.69  4985.6  163.01
  4991.7  163.27  5000.3  161.21  5006.4  162.18  5025.7  158.14  5026.2  157.64
  5031.4  158.14  5035.9  161.54  5042.1  161.67  5062.9  165.83    5078  166.88
  5100.1  167.19  5123.2  165.56  5159.3  167.66  5216.5     169  5237.5  170.41
  5252.6  170.04  5317.9  173.09  5439.1  175.62  5523.3  174.75  5582.2  173.85
#Mann= 7 ,-1 , 0
  4428.9      .1       0  4460.2     .12       0  4786.6      .1       0
  5025.7     .05       0  5031.4      .1       0  5317.9     .12       0
  5523.3      .1       0
Bank Sta=5025.7,5031.4
XS Rating Curve= 0 ,0
Exp/Cntr=0.3,0.1

Type RM Length L Ch R = 1 ,14085   ,260,260,260
BEGIN DESCRIPTION:
JOHNS CREEK 24.0
END DESCRIPTION:
XS GIS Cut Line= 3
      2524374.98     13509374.97        2524075.       13508975.
      2523674.97     13508574.97
#Sta/Elev= 30
  4500.3  175.01  4585.4  172.37  4593.4  172.05  4755.4  167.01  4762.7  166.84
  4928.4  165.53    4943  164.54  4957.6  162.09  4963.8  155.82  4969.2  155.48
  4969.7  154.98  4974.6  154.98  4975.1  155.48  4986.7  156.53  4997.1  159.09
  5003.8  159.09  5014.4  161.94    5071  163.36  5099.3  163.01  5127.5  165.02
  5155.8  165.85  5244.9  166.78  5339.7   167.1    5368  167.79  5382.1  166.61
  5410.4  169.06  5424.5  168.85  5463.3  173.39  5531.8   176.7    5566  178.21
#Mann= 10 ,-1 , 0
  4500.3     .12       0  4585.4     .07       0  4593.4      .1       0
  4755.4     .12       0  4762.7      .1       0  4969.2     .05       0
  4975.1      .1       0  5244.9    .063       0  5463.3     .12       0
  5531.8     .07       0
Bank Sta=4969.2,4975.1
XS Rating Curve= 0 ,0
Exp/Cntr=0.3,0.1

Type RM Length L Ch R = 1 ,13825   ,383,383,383
BEGIN DESCRIPTION:
Mapping XS 0551bbb4
END DESCRIPTION:
XS GIS Cut Line= 3
      2524608.83     13509269.47      2524257.26     13508796.36
      2523845.28     13508479.79
#Sta/Elev= 30
  4444.3  175.37  4528.5  172.72  4637.4  168.08  4793.5  163.79    4879  163.62
  4899.8   164.8  4914.4  163.22  4922.8  159.47  4964.5  161.56  4972.9  159.51
  4976.2  156.76  4976.7  156.26  4982.1  156.76  4999.9  159.03  5008.3  158.86
  5031.5  160.73  5053.5  161.05  5143.2  161.39  5172.2  164.03  5193.1  164.52
  5207.6  165.95    5251  166.18  5278.2  165.09  5342.6  166.35  5392.4  169.54
    5465  171.96  5500.3  174.85  5514.8  174.67  5521.5  175.59  5553.3  176.74
#Mann= 6 ,-1 , 0
  4444.3     .07       0  4637.4      .1       0  4976.2     .05       0
  4982.1      .1       0  5053.5    .035       0  5521.5     .12       0
Bank Sta=4976.2,4982.1
XS Rating Curve= 0 ,0
Exp/Cntr=0.3,0.1

Type RM Length L Ch R = 1 ,13442   ,342,342,342
BEGIN DESCRIPTION:
Mapping XS 5c1b1104
END DESCRIPTION:
XS GIS Cut Line= 3
      2524699.98     13509195.69      2524370.11     13508561.99
      2523979.74     13508323.43
#Sta/Elev= 30
  4298.8   174.8    4385  172.34  4454.5  169.61  4511.7  166.96  4644.3   163.1
    4852  163.13  4909.6  162.38    4926  161.13  4953.8  160.98  4964.6  159.42
  4970.2  157.09    4973  154.72  4973.5  154.22  4978.9  154.72  4992.4  156.81
    5021  156.19  5030.6  157.15  5036.5  155.85  5042.6   161.5  5051.9  162.18
  5057.8  163.94  5066.1  163.27  5073.2  164.66  5127.3   166.5  5189.4  169.23
  5204.8  168.83  5241.6  171.56  5279.4  172.37  5400.3  176.53  5470.7  177.82
#Mann= 7 ,-1 , 0
  4298.8     .07       0    4385     .12       0  4454.5      .1       0
    4973     .05       0  4978.9      .1       0  5127.3    .035       0
  5279.4     .12       0
Bank Sta=4973,4978.9
XS Rating Curve= 0 ,0
Exp/Cntr=0.3,0.1

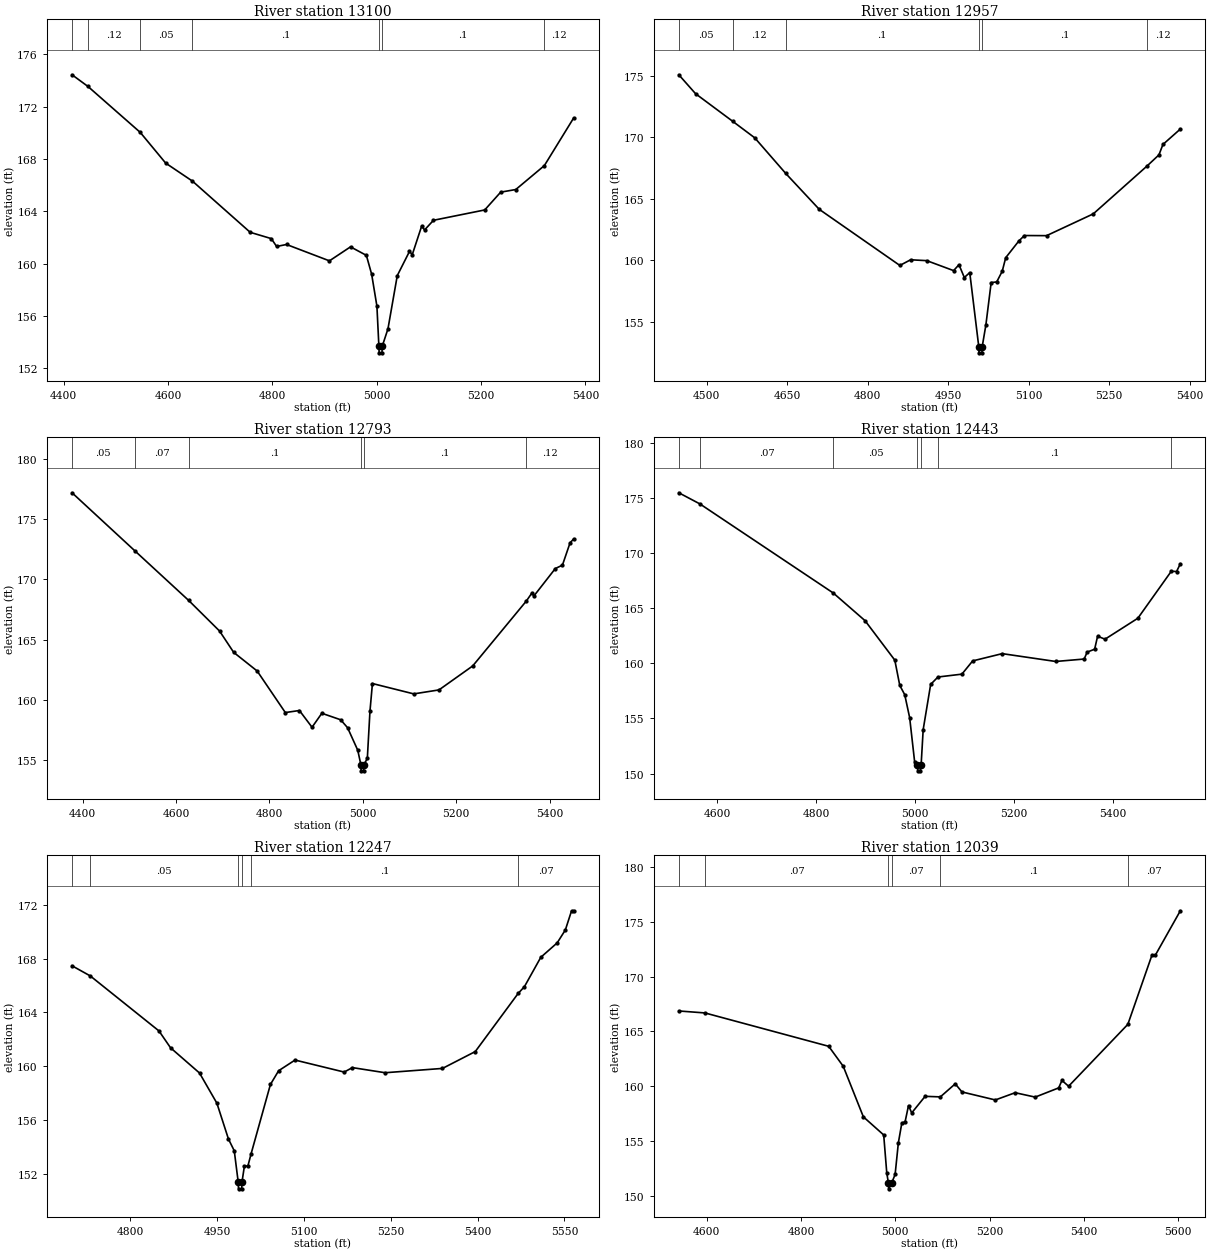
Type RM Length L Ch R = 1 ,13100   ,143,143,143
BEGIN DESCRIPTION:
Mapping XS 2f1cc2a7
END DESCRIPTION:
XS GIS Cut Line= 3
      2524773.76      13509152.3      2524682.61     13508566.33
      2524535.53     13508228.91
#Sta/Elev= 30
  4416.1  174.44  4446.5  173.55  4546.7  170.04  4595.5  167.69  4646.9  166.31
  4757.5   162.4  4797.9  161.92  4808.1  161.32  4827.1  161.47  4909.3  160.22
  4949.7  161.29  4980.1  160.64  4990.2   159.2  5000.3  156.76  5004.1  153.69
  5004.6  153.19    5010  153.19  5010.5  153.69  5021.5  155.03  5039.3  159.09
  5062.7  160.94  5068.1   160.7  5086.1  162.88  5091.6  162.58  5108.7  163.32
  5206.9  164.11  5237.5  165.47  5266.4  165.67  5321.2   167.5  5377.2  171.13
#Mann= 7 ,-1 , 0
  4416.1     .07       0  4446.5     .12       0  4546.7     .05       0
  4646.9      .1       0  5004.1     .05       0  5010.5      .1       0
  5321.2     .12       0
Bank Sta=5004.1,5010.5
XS Rating Curve= 0 ,0
Exp/Cntr=0.3,0.1

Type RM Length L Ch R = 1 ,12957   ,164,164,164
BEGIN DESCRIPTION:
Mapping XS 231ebda2
END DESCRIPTION:
XS GIS Cut Line= 3
      2524856.22     13509126.24      2524825.83     13508540.29
      2524739.51     13508203.61
#Sta/Elev= 30
  4448.4  175.06  4479.7  173.52  4548.8  171.28  4589.8  169.94  4647.7  167.04
    4710  164.13  4860.2  159.57  4880.2  160.03  4910.3  159.96  4960.3  159.15
  4970.3  159.63  4980.3  158.59  4990.4  158.99  5007.2  152.97  5007.7  152.47
  5013.1  152.47  5013.6  152.97  5020.4  154.72  5030.3  158.18  5040.6  158.23
  5050.9   159.1  5057.4   160.2  5081.9  161.56  5092.2     162  5133.5  161.99
  5220.5  163.76  5319.7  167.61  5342.8  168.55  5350.3   169.4  5382.7  170.65
#Mann= 6 ,-1 , 0
  4448.4     .05       0  4548.8     .12       0  4647.7      .1       0
  5007.2     .05       0  5013.6      .1       0  5319.7     .12       0
Bank Sta=5007.2,5013.6
XS Rating Curve= 0 ,0
Exp/Cntr=0.3,0.1

Type RM Length L Ch R = 1 ,12793   ,350,350,350
BEGIN DESCRIPTION:
Mapping XS b39e765a
END DESCRIPTION:
XS GIS Cut Line= 4
      2524996.57     13509178.89      2524937.59     13508644.54
      2524991.37     13508486.67      2524817.88     13508160.51
#Sta/Elev= 30
  4377.4  177.19  4511.3  172.39  4627.1  168.25  4693.2  165.71  4723.4  163.94
  4773.7  162.39    4834  158.94  4864.2  159.11  4891.2  157.72  4912.2  158.88
  4952.5  158.34  4967.3  157.68  4989.1  155.81  4995.8   154.6  4996.3   154.1
  5001.7   154.1  5002.2   154.6  5009.6  155.14  5015.2  159.04  5020.5  161.35
    5109  160.49    5163  160.82  5235.2  162.81  5350.2  168.21  5361.3  168.83
    5367  168.66  5412.1   170.9  5427.3  171.18  5443.6  173.03  5451.2  173.35
#Mann= 6 ,-1 , 0
  4377.4     .05       0  4511.3     .07       0  4627.1      .1       0
  4995.8     .05       0  5002.2      .1       0  5350.2     .12       0
Bank Sta=4995.8,5002.2
XS Rating Curve= 0 ,0
Exp/Cntr=0.3,0.1

Type RM Length L Ch R = 1 ,12443   ,196,196,196
BEGIN DESCRIPTION:
JOHNS CREEK 21.0
END DESCRIPTION:
XS GIS Cut Line= 3
      2525208.22     13509151.13      2525213.43     13508661.89
      2524924.99     13508224.98
#Sta/Elev= 30
  4522.7  175.47  4565.3  174.46  4834.9  166.37  4898.8  163.87  4958.9  160.29
  4968.9     158  4978.9  157.16  4988.9  155.07  4998.9  151.08  5004.7  150.75
  5005.2  150.25  5010.7  150.25  5011.2  150.75    5012  150.75  5016.2  153.99
  5031.3  158.09    5046  158.76  5094.4  159.02  5116.1  160.22  5175.8  160.88
  5283.8  160.17  5341.3  160.39  5347.3  161.02  5362.4  161.28  5368.4  162.46
  5383.4  162.19  5449.7  164.09  5517.2  168.35  5527.9  168.33  5535.5  169.03
#Mann= 7 ,-1 , 0
  4522.7     .05       0  4565.3     .07       0  4834.9     .05       0
  5004.7     .05       0  5011.2     .05       0    5046      .1       0
  5517.2     .12       0
Bank Sta=5004.7,5011.2
XS Rating Curve= 0 ,0
Exp/Cntr=0.3,0.1

Type RM Length L Ch R = 1 ,12247   ,208,208,208
BEGIN DESCRIPTION:
JOHNS CREEK 20.0
END DESCRIPTION:
XS GIS Cut Line= 3
        2525375.       13508875.        2525375.       13508575.
      2524974.99     13508174.99
#Sta/Elev= 30
    4700  167.46  4731.4  166.71    4850  162.63    4870  161.38    4920  159.51
    4950  157.27    4970  154.61    4980  153.74  4986.8  151.42  4987.3  150.92
  4992.8  150.92  4993.3  151.42  4997.5  152.61  5003.5  152.61  5008.8  153.48
  5042.4  158.66  5056.6  159.68  5084.9  160.47  5169.7  159.58  5183.9  159.91
  5240.4  159.53  5339.4  159.85    5396   161.1    5470  165.41  5480.8  165.91
  5509.1  168.09  5537.4  169.16  5551.5  170.12  5562.2  171.54  5565.7  171.54
#Mann= 6 ,-1 , 0
    4700     .07       0  4731.4     .05       0  4986.8     .05       0
  4993.3     .05       0  5008.8      .1       0    5470     .07       0
Bank Sta=4986.8,4993.3
XS Rating Curve= 0 ,0
Exp/Cntr=0.3,0.1

Type RM Length L Ch R = 1 ,12039   ,235,235,235
BEGIN DESCRIPTION:
Mapping XS f23de02e
END DESCRIPTION:
XS GIS Cut Line= 3
      2525646.14     13508904.85      2525546.32      13508466.5
      2525125.56     13508019.71
#Sta/Elev= 30
  4541.1  166.86  4596.5  166.68  4858.9  163.64  4889.7  161.82  4932.4  157.21
  4975.5  155.56    4982   152.1  4985.6  151.15  4986.1  150.65  4992.1  151.15
  4999.7  151.96  5006.6  154.85  5013.9  156.64  5020.8  156.75  5028.1  158.24
  5034.9  157.57  5063.3  159.08  5095.6  159.03  5127.2  160.22  5141.4  159.48
  5212.2  158.75  5254.2  159.41  5296.7  159.01  5346.5  159.85  5353.4  160.53
  5367.5     160  5493.1  165.64  5544.3  171.96  5551.6  171.96  5604.4  175.99
#Mann= 6 ,-1 , 0
  4541.1     .05       0  4596.5     .07       0  4985.6     .05       0
  4992.1     .07       0  5095.6      .1       0  5493.1     .07       0
Bank Sta=4985.6,4992.1
XS Rating Curve= 0 ,0
Exp/Cntr=0.3,0.1

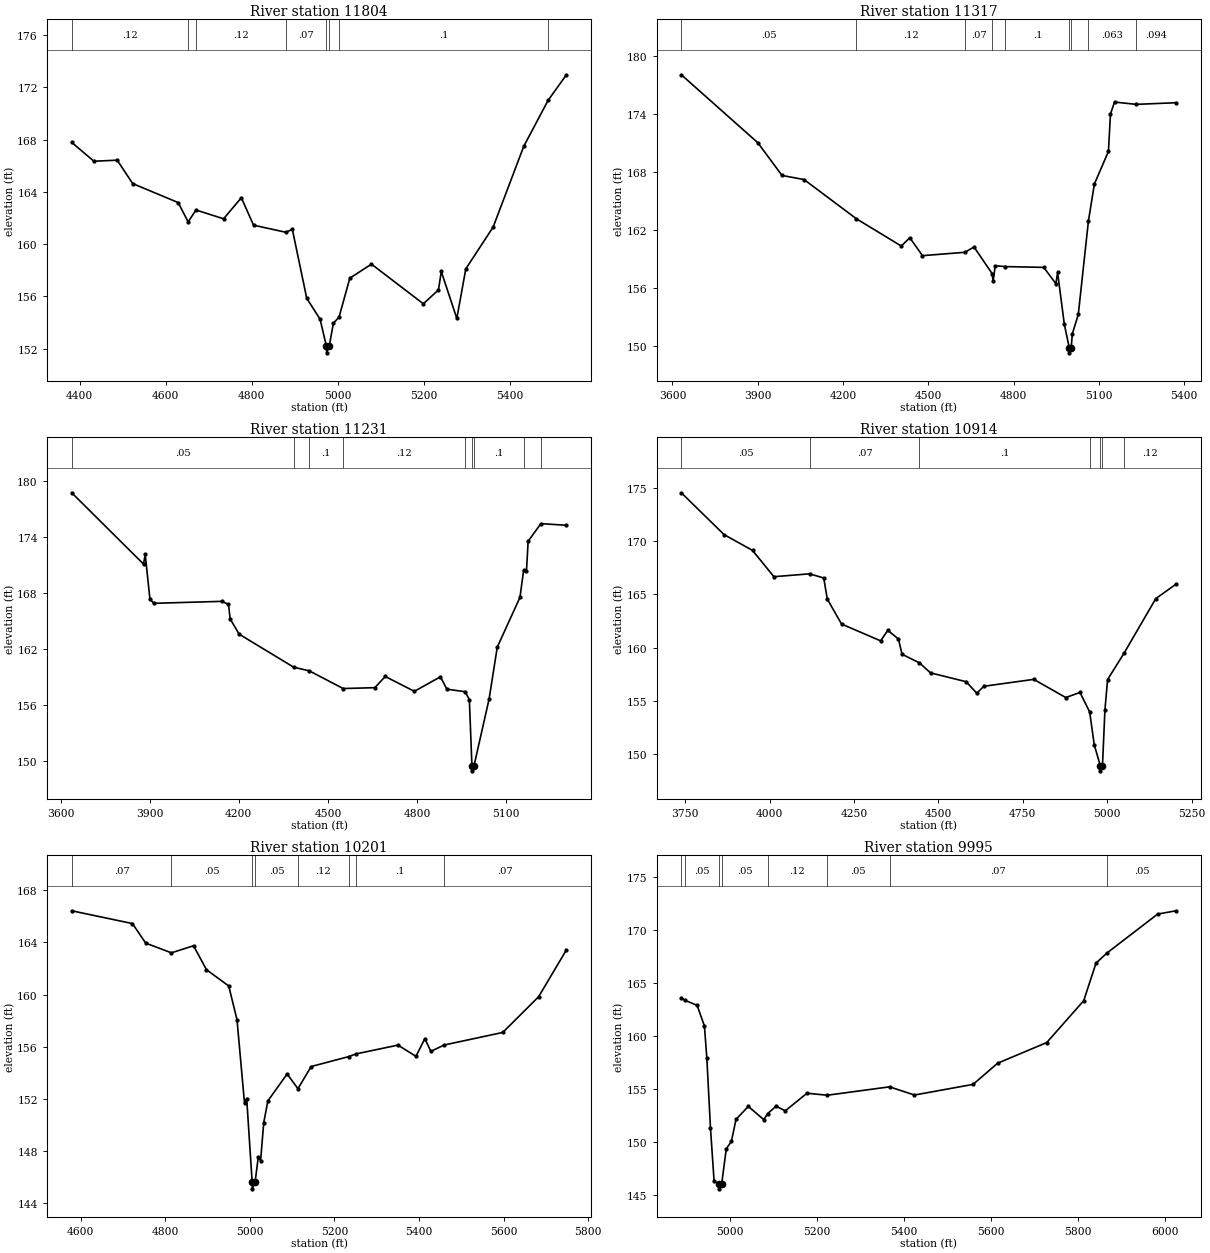
Type RM Length L Ch R = 1 ,11804   ,487,487,487
BEGIN DESCRIPTION:
JOHNS CREEK 19.0
END DESCRIPTION:
XS GIS Cut Line= 3
      2525875.01     13508925.05        2525725.       13508325.
      2525375.01     13507925.02
#Sta/Elev= 30
  4381.8  167.78  4433.4  166.34  4487.5  166.42  4523.6  164.63  4629.2  163.18
  4652.5   161.7  4670.6  162.61  4734.9  161.94  4776.1  163.55  4804.5  161.45
  4879.4  160.91  4894.7  161.13  4928.2  155.85  4959.1  154.27  4973.9  152.19
  4974.4  151.69  4980.4  152.19    4990  153.95  5003.3  154.43  5028.3   157.4
  5078.6  158.47  5199.2  155.44  5234.3   156.5  5240.9  157.91    5277  154.32
  5297.9  158.11  5361.5  161.31  5432.6  167.48  5489.3     171  5531.8  172.95
#Mann= 8 ,-1 , 0
  4381.8     .12       0  4652.5     .07       0  4670.6     .12       0
  4879.4     .07       0  4973.9     .05       0  4980.4     .07       0
  5003.3      .1       0  5489.3    .063       0
Bank Sta=4973.9,4980.4
XS Rating Curve= 0 ,0
Exp/Cntr=0.3,0.1

Type RM Length L Ch R = 1 ,11317   ,86,86,86
BEGIN DESCRIPTION:
Mapping XS 8b94ac91
END DESCRIPTION:
XS GIS Cut Line= 4
      2526401.92     13509178.72      2526033.01     13508783.77
      2525750.89     13508024.22      2525481.77     13507742.08
#Sta/Elev= 30
  3631.1  178.09  3900.3  171.06  3985.3  167.68    4063  167.25  4246.5  163.21
  4404.8  160.38  4435.1  161.23  4479.6  159.38  4628.8  159.73  4660.9  160.28
  4724.8  157.52  4728.1  156.72  4735.6  158.34  4771.3  158.25  4906.3  158.17
    4949  156.48    4955  157.64  4978.7  152.27  4996.2  149.83  4996.7  149.33
  5002.8  149.83  5006.8  151.29  5027.8   153.3  5063.3  162.93  5084.4  166.79
  5133.8  170.16    5141  174.02  5155.2  175.27  5231.5  175.03  5371.7   175.2
#Mann= 9 ,-1 , 0
  3631.1     .05       0  4246.5     .12       0  4628.8     .07       0
  4724.8     .12       0  4771.3      .1       0  4996.2     .05       0
  5002.8      .1       0  5063.3    .063       0  5231.5    .094       0
Bank Sta=4996.2,5002.8
XS Rating Curve= 0 ,0
Exp/Cntr=0.3,0.1

Type RM Length L Ch R = 1 ,11231   ,317,317,317
BEGIN DESCRIPTION:
Mapping XS 1832a1a6
END DESCRIPTION:
XS GIS Cut Line= 3
      2526471.36     13509165.69      2526089.43     13508488.63
      2525668.43      13507707.4
#Sta/Elev= 30
  3637.7  178.74  3879.3  171.11    3885  172.15  3900.9  167.37    3914  166.91
  4143.6  167.12  4165.3  166.79    4171  165.23  4201.1  163.61  4384.8  160.07
  4437.3  159.68  4551.1  157.79  4657.7  157.88  4692.7  159.08  4790.8  157.49
  4878.4  159.04  4900.3  157.72  4961.5  157.45  4975.8  156.61  4984.6  149.48
  4985.1  148.98  4991.2  149.48  5042.3  156.67  5069.8  162.22  5146.1  167.54
  5158.5  170.45    5168  170.36  5173.7  173.56  5216.7  175.44  5302.5  175.26
#Mann= 9 ,-1 , 0
  3637.7     .05       0  4384.8     .12       0  4437.3      .1       0
  4551.1     .12       0  4961.5      .1       0  4984.6     .05       0
  4991.2      .1       0  5158.5    .063       0  5216.7    .094       0
Bank Sta=4984.6,4991.2
XS Rating Curve= 0 ,0
Exp/Cntr=0.3,0.1

Type RM Length L Ch R = 1 ,10914   ,713,713,713
BEGIN DESCRIPTION:
JOHNS CREEK 17.0
END DESCRIPTION:
XS GIS Cut Line= 3
      2526475.01     13509025.04        2526075.       13507825.
        2526075.     13507624.95
#Sta/Elev= 30
  3738.6  174.56  3865.1  170.63  3949.5  169.14  4012.7  166.67  4118.4  166.94
  4160.3  166.55  4170.8  164.57    4213  162.22  4328.9  160.64    4350  161.63
  4381.6  160.81  4392.2  159.38  4443.8  158.57  4476.5  157.63  4581.9   156.8
  4613.5  155.72  4634.6  156.37  4782.2  157.02  4877.1  155.31  4919.2  155.79
  4947.8  153.96  4961.4  150.87  4979.1  148.92  4979.6  148.42  4985.8  148.92
    4993  154.15  5000.9     157  5049.8  159.49  5143.6  164.61  5203.6  165.97
#Mann= 7 ,-1 , 0
  3738.6     .05       0  4118.4     .07       0  4443.8      .1       0
  4947.8     .07       0  4979.1     .05       0  4985.8     .07       0
  5049.8     .12       0
Bank Sta=4979.1,4985.8
XS Rating Curve= 0 ,0
Exp/Cntr=0.3,0.1

Type RM Length L Ch R = 1 ,10201   ,206,206,206
BEGIN DESCRIPTION:
Mapping XS be564cd2
END DESCRIPTION:
XS GIS Cut Line= 4
      2526753.79     13508585.41      2526654.83     13508163.54
      2526607.96     13508064.59      2526180.87     13507606.24
#Sta/Elev= 30
  4578.9  166.42  4722.4  165.44  4753.9  163.94  4814.5   163.2  4866.9  163.74
  4897.3  161.91    4950  160.66  4969.6  158.07  4987.3  151.69  4992.5  152.03
  5005.4  145.62  5005.9  145.12  5012.3  145.62  5019.8  147.55  5025.4  147.29
  5032.7  150.18  5042.6  151.86  5088.1  153.92  5113.6  152.79  5144.9  154.49
  5233.8  155.25  5251.5  155.46    5350  156.13  5392.6  155.27  5413.6  156.63
  5427.7  155.65  5459.5  156.14  5597.7   157.1  5682.3  159.83  5748.2  163.42
#Mann= 8 ,-1 , 0
  4578.9     .07       0  4814.5     .05       0  5005.4     .05       0
  5012.3     .05       0  5113.6     .12       0  5233.8     .05       0
  5251.5      .1       0  5459.5     .07       0
Bank Sta=5005.4,5012.3
XS Rating Curve= 0 ,0
Exp/Cntr=0.3,0.1

Type RM Length L Ch R = 1 ,9995    ,677,677,677
BEGIN DESCRIPTION:
JOHNS CREEK 16.0
END DESCRIPTION:
XS GIS Cut Line= 3
      2526874.98     13508174.97        2526825.       13508075.
      2526074.99     13507374.99
#Sta/Elev= 30
  4888.5  163.58  4896.4  163.36  4924.8  162.88  4941.6  160.94  4947.2  157.89
  4955.5  151.35  4963.9  146.31  4974.5  146.11    4975  145.61  4981.4  146.11
  4991.9  149.38  5003.7  150.08  5014.2  152.14  5042.5  153.37  5078.2  152.12
  5086.7  152.68  5106.5  153.39  5127.5  152.95  5177.4  154.61    5224  154.42
  5367.3  155.21  5424.6  154.44  5559.4  155.44  5615.8  157.43  5728.9  159.38
  5813.9  163.32  5842.2  166.86  5867.8  167.82  5983.9  171.47  6026.2  171.78
#Mann= 8 ,-1 , 0
  4888.5     .12       0  4896.4     .05       0  4974.5     .05       0
  4981.4     .05       0  5086.7     .12       0    5224     .05       0
  5367.3     .07       0  5867.8     .05       0
Bank Sta=4974.5,4981.4
XS Rating Curve= 0 ,0
Exp/Cntr=0.3,0.1