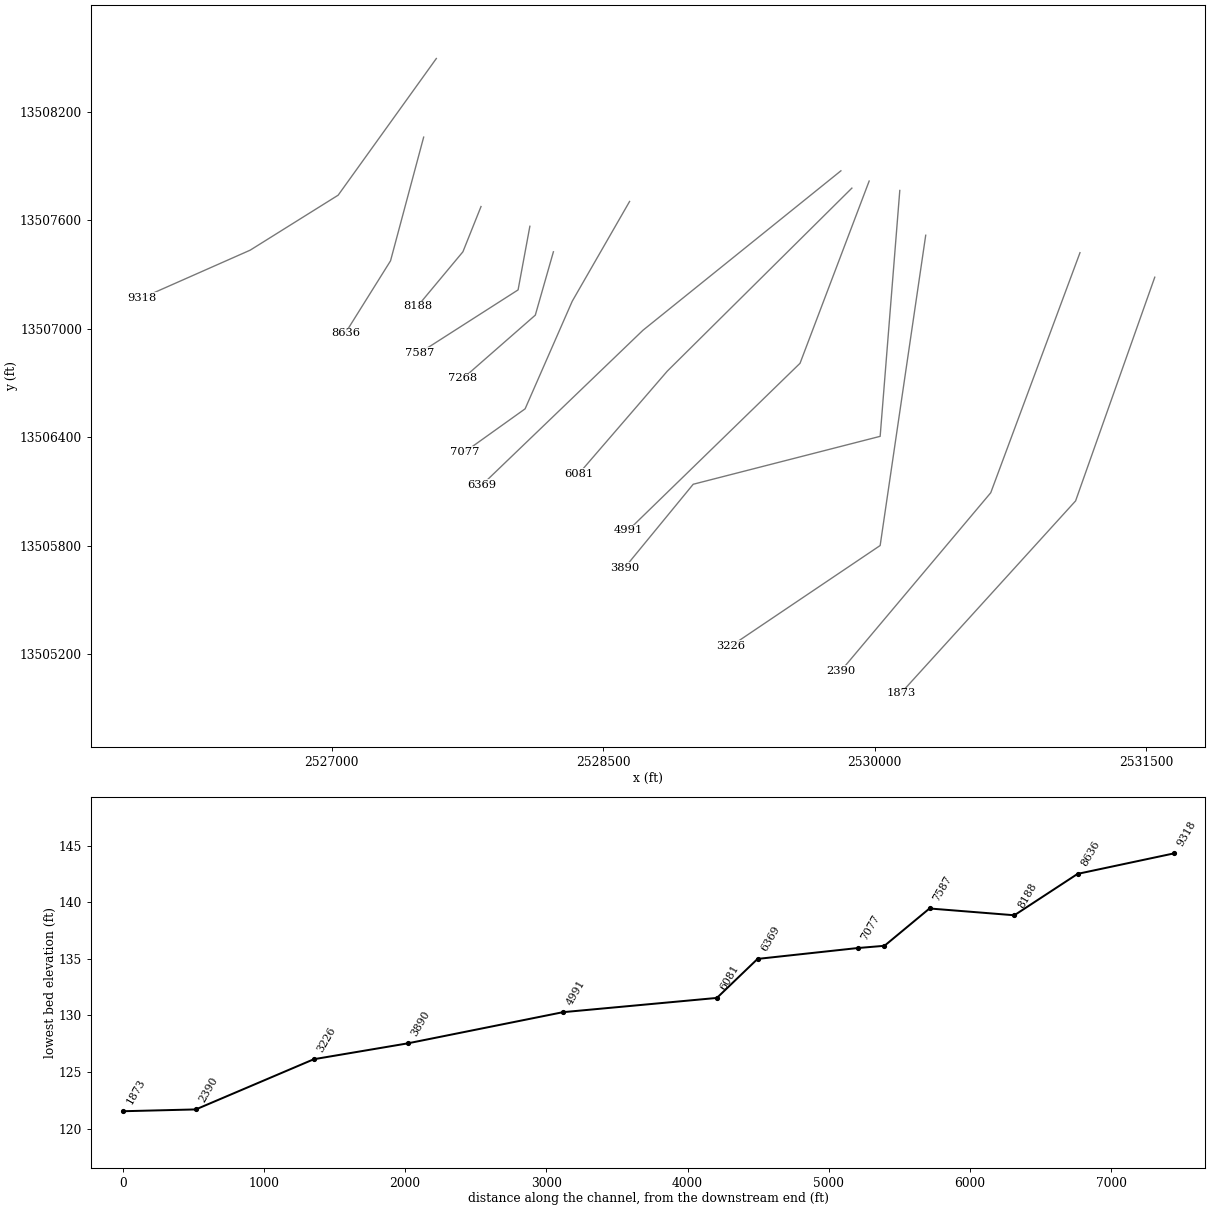
HEC-RAS study JOHNS CREEK.prj: JOHNS CREEK Base Level Engineering

--- JOHNS CREEK.g01 (geometry) --- (continued)

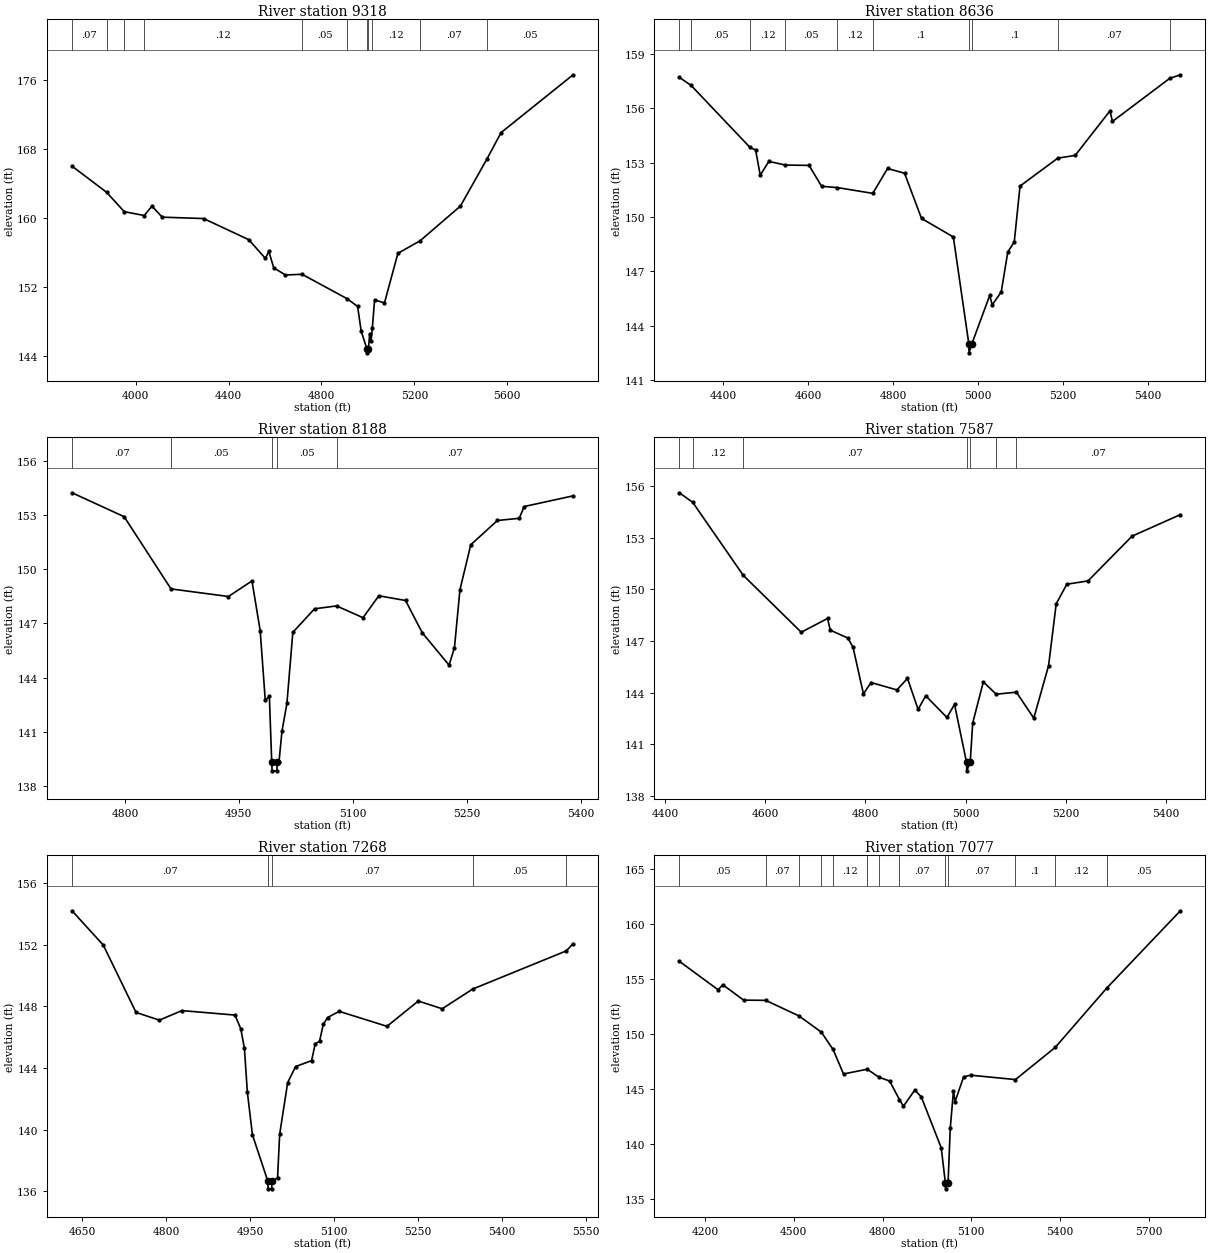
Type RM Length L Ch R = 1 ,9318    ,682,682,682
BEGIN DESCRIPTION:
Mapping XS aa3b2feb
END DESCRIPTION:
XS GIS Cut Line= 4
      2527578.14     13508492.96      2527035.61     13507737.76
       2526549.5     13507433.94      2525951.44     13507169.58
#Sta/Elev= 30
  3726.1  166.03  3874.9  162.99  3950.9  160.74  4037.1  160.29  4070.1  161.39
  4114.3   160.1  4292.3  159.94    4487  157.48  4558.7   155.3  4573.2  156.13
  4594.3  154.21  4644.7  153.38  4716.3  153.46  4911.1  150.61  4955.5  149.72
  4970.8  146.85  4995.2  144.83  4995.7  144.33  5002.2  144.83  5007.4  146.56
  5013.3  145.71  5018.7  147.16  5028.6  150.49  5071.1  150.13  5128.9   155.9
  5224.4  157.35  5398.1  161.39  5511.6  166.83  5573.1  169.93  5883.1  176.65
#Mann= 11 ,-1 , 0
  3726.1     .07       0  3874.9     .12       0  3950.9     .07       0
  4037.1     .12       0  4716.3     .05       0  4911.1     .07       0
  4995.2     .05       0  5002.2     .07       0  5018.7     .12       0
  5224.4     .07       0  5511.6     .05       0
Bank Sta=4995.2,5002.2
XS Rating Curve= 0 ,0
Exp/Cntr=0.3,0.1

Type RM Length L Ch R = 1 ,8636    ,448,448,448
BEGIN DESCRIPTION:
JOHNS CREEK 14.0
END DESCRIPTION:
XS GIS Cut Line= 3
      2527508.12      13508058.5        2527325.       13507375.
        2527075.       13506975.
#Sta/Elev= 30
  4296.3  157.69  4324.3  157.24  4462.7  153.83  4475.9  153.69  4486.8   152.3
    4507  153.06    4546  152.86  4601.7  152.84  4631.2  151.69  4668.1  151.62
  4751.7   151.3  4786.4  152.67  4826.4  152.41  4866.4  149.92  4941.3   148.9
  4977.7  143.02  4978.2  142.52  4984.9  143.02  5026.9  145.68  5032.8  145.16
    5054  145.87  5069.4  148.07  5084.7  148.63  5098.2   151.7  5187.1  153.24
    5228  153.39  5309.9  155.84  5315.8  155.26  5450.4  157.63  5475.6  157.83
#Mann= 10 ,-1 , 0
  4296.3     .07       0  4324.3     .05       0  4462.7     .12       0
    4546     .05       0  4668.1     .12       0  4751.7      .1       0
  4977.7     .05       0  4984.9      .1       0  5187.1     .07       0
  5450.4     .05       0
Bank Sta=4977.7,4984.9
XS Rating Curve= 0 ,0
Exp/Cntr=0.3,0.1

Type RM Length L Ch R = 1 ,8188    ,601,601,601
BEGIN DESCRIPTION:
JOHNS CREEK 13.0
END DESCRIPTION:
XS GIS Cut Line= 3
      2527824.98     13507674.95        2527725.       13507425.
      2527475.01     13507125.02
#Sta/Elev= 30
  4730.4  154.22    4799   152.9  4860.7  148.91  4936.3  148.49  4967.3  149.35
  4978.1  146.61  4984.8  142.76  4990.2  142.97  4993.3  139.36  4993.8  138.86
  5000.1  138.86  5000.6  139.36  5002.9  139.36  5006.8  141.05  5013.3  142.58
  5021.1  146.51  5049.7  147.81  5078.6  147.97  5113.5  147.32  5134.3  148.53
  5169.5  148.27  5191.6  146.48  5226.8   144.7  5233.9  145.66  5241.1  148.86
  5255.4  151.35  5290.5  152.69  5319.2  152.81  5325.7  153.46  5390.1  154.05
#Mann= 5 ,-1 , 0
  4730.4     .07       0  4860.7     .05       0  4993.3     .05       0
  5000.6     .05       0  5078.6     .07       0
Bank Sta=4993.3,5000.6
XS Rating Curve= 0 ,0
Exp/Cntr=0.3,0.1

Type RM Length L Ch R = 1 ,7587    ,319,319,319
BEGIN DESCRIPTION:
Mapping XS c70f4545
END DESCRIPTION:
XS GIS Cut Line= 3
      2528094.93     13507565.99      2528029.83     13507214.47
      2527488.67     13506868.12
#Sta/Elev= 30
  4428.4  155.61  4455.1  155.06  4555.9  150.82  4671.8  147.51  4724.3  148.31
  4729.7  147.63    4765  147.17  4775.2  146.63  4795.9  143.93  4811.1  144.59
  4862.7  144.16  4883.8  144.83    4905  143.03  4920.2  143.82  4962.5  142.56
  4977.7  143.32  5001.6  139.96  5002.1  139.46    5009  139.96    5014  142.24
  5035.2  144.63  5060.8  143.91  5101.1  144.03  5135.9  142.52  5165.4  145.57
  5180.6  149.16  5201.8   150.3  5244.1  150.49    5332  153.09  5428.4  154.34
#Mann= 7 ,-1 , 0
  4428.4     .07       0  4455.1     .12       0  4555.9     .07       0
  5001.6     .05       0    5009     .07       0  5060.8     .05       0
  5101.1     .07       0
Bank Sta=5001.6,5009
XS Rating Curve= 0 ,0
Exp/Cntr=0.3,0.1

Type RM Length L Ch R = 1 ,7268    ,191,191,191
BEGIN DESCRIPTION:
JOHNS CREEK 12.0
END DESCRIPTION:
XS GIS Cut Line= 3
        2528225.     13507425.01        2528125.       13507075.
      2527725.01     13506725.01
#Sta/Elev= 30
  4631.5  154.21  4687.4  151.98  4745.9  147.61  4787.5  147.11  4827.8  147.73
  4922.7  147.44  4933.1  146.55  4939.6  145.27  4944.8  142.45  4953.9  139.67
  4981.4  136.66  4981.9  136.16  4988.3  136.16  4988.8  136.66  4998.8  136.87
  5002.6  139.71  5016.9  143.06  5031.1   144.1  5059.6  144.48  5066.2  145.58
  5073.8  145.73  5080.5  146.84  5088.1  147.28  5108.9  147.68  5194.4  146.71
  5250.3  148.35  5293.1  147.85  5347.6  149.13  5515.1  151.61    5527  152.08
#Mann= 5 ,-1 , 0
  4631.5     .07       0  4981.4     .05       0  4988.8     .07       0
  5347.6     .05       0  5515.1     .07       0
Bank Sta=4981.4,4988.8
XS Rating Curve= 0 ,0
Exp/Cntr=0.3,0.1

Type RM Length L Ch R = 1 ,7077    ,708,708,708
BEGIN DESCRIPTION:
Mapping XS 642fe4c1
END DESCRIPTION:
XS GIS Cut Line= 4
      2528645.85     13507703.04      2528329.01     13507151.82
       2528068.6     13506557.21      2527735.48     13506319.26
#Sta/Elev= 30
  4112.7  156.64    4244  154.05  4259.8  154.51  4330.2  153.11  4404.7  153.09
    4517  151.68  4592.7  150.21  4632.6  148.63    4668   146.4  4748.2  146.83
  4788.1   146.1  4823.9  145.76  4857.1  144.07  4870.6  143.47  4908.8  144.93
  4930.6  144.34  4998.4  139.69  5012.6  136.46  5013.1  135.96  5020.1  136.46
  5021.8   136.7  5028.9  141.45  5039.7  144.84  5045.2  143.89    5074  146.13
  5097.4  146.29  5249.3  145.89  5383.7  148.81  5557.9   154.2    5807  161.23
#Mann= 13 ,-1 , 0
  4112.7     .05       0  4404.7     .07       0    4517     .05       0
  4592.7     .07       0  4632.6     .12       0  4748.2     .07       0
  4788.1     .12       0  4857.1     .07       0  5012.6     .05       0
  5020.1     .07       0  5249.3      .1       0  5383.7     .12       0
  5557.9     .05       0
Bank Sta=5012.6,5020.1
XS Rating Curve= 0 ,0
Exp/Cntr=0.3,0.1

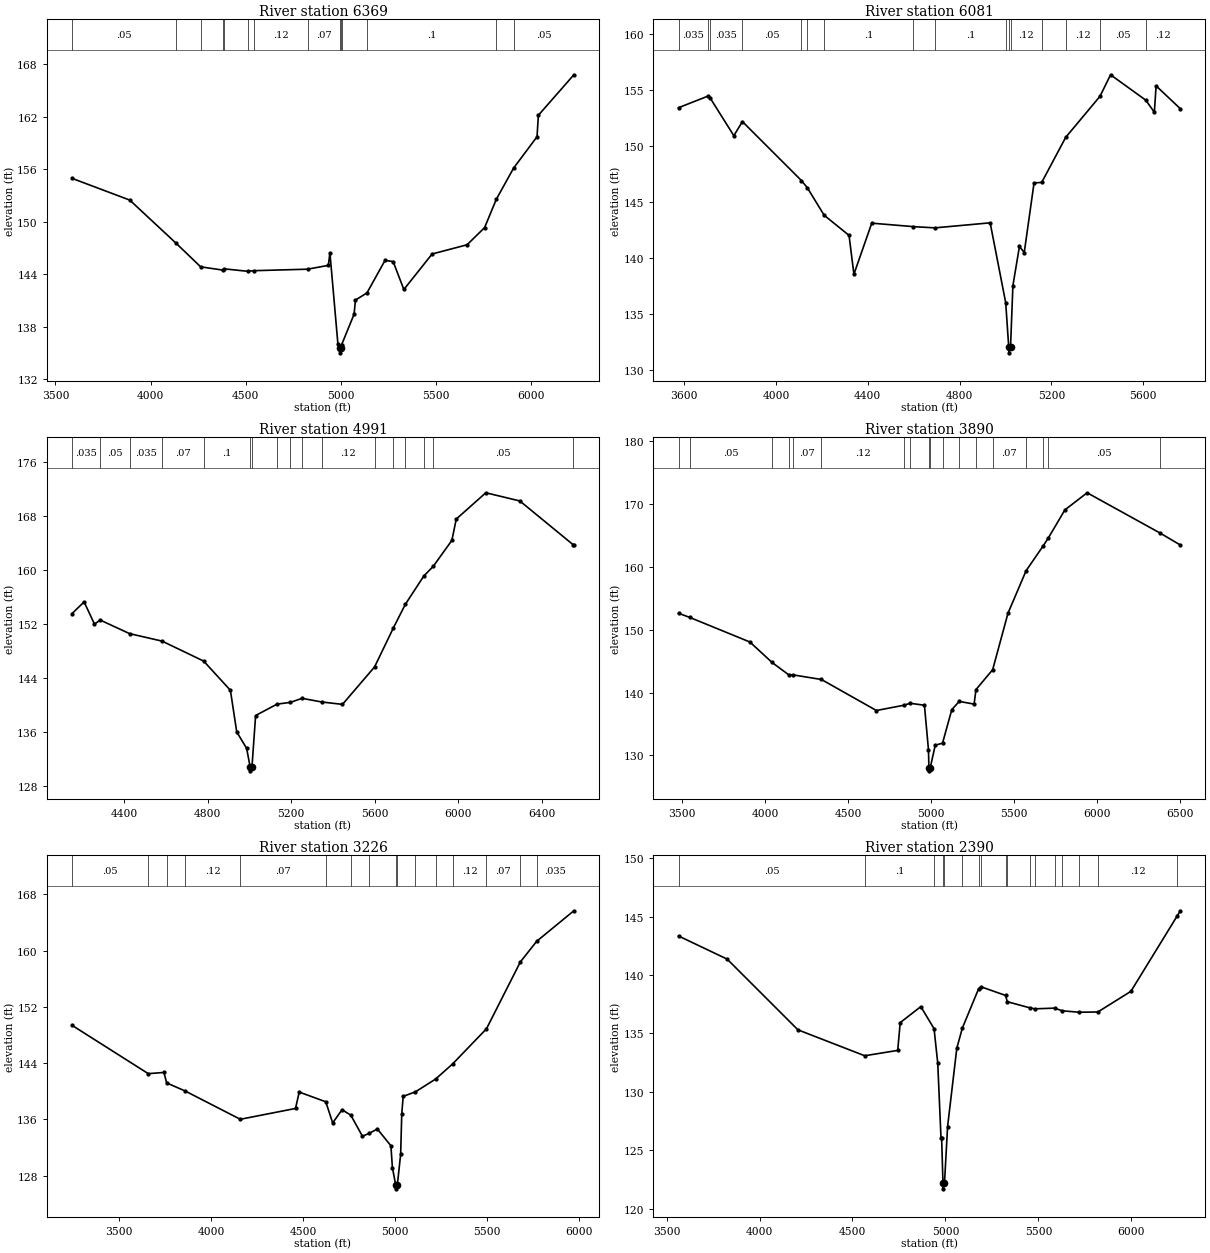
Type RM Length L Ch R = 1 ,6369    ,288,288,288
BEGIN DESCRIPTION:
Mapping XS fbe02e39
END DESCRIPTION:
XS GIS Cut Line= 3
      2529813.41     13507872.33      2528719.64     13506991.23
      2527829.97     13506136.28
#Sta/Elev= 30
  3587.4  154.94  3890.6  152.46  4135.6   147.5  4263.5  144.83  4382.3  144.45
  4386.9   144.6  4510.4  144.32  4545.2  144.39  4825.4  144.56  4935.1     145
  4943.1  146.45    4985  136.05  4995.7   135.5  4996.2     135  5003.2   135.5
  5005.1  135.95  5070.2  139.41  5077.5  141.03  5137.9  141.85  5233.1  145.57
  5275.6  145.43  5331.9  142.24  5480.6   146.3  5664.3  147.35  5756.4  149.31
  5818.3  152.56  5909.1  156.12  6032.2   159.7  6039.1  162.15  6225.8  166.78
#Mann= 14 ,-1 , 0
  3587.4     .05       0  4135.6    .035       0  4263.5     .05       0
  4382.3    .035       0  4386.9     .12       0  4510.4     .05       0
  4545.2     .12       0  4825.4     .07       0  4995.7     .05       0
  5003.2     .07       0  5005.1     .12       0  5137.9      .1       0
  5818.3     .12       0  5909.1     .05       0
Bank Sta=4995.7,5003.2
XS Rating Curve= 0 ,0
Exp/Cntr=0.3,0.1

Type RM Length L Ch R = 1 ,6081    ,1090,1090,1090
BEGIN DESCRIPTION:
Mapping XS 10a49a7d
END DESCRIPTION:
XS GIS Cut Line= 3
      2529874.15     13507776.82      2528854.19     13506765.54
      2528363.74     13506196.96
#Sta/Elev= 30
  3575.1  153.44  3704.1  154.48  3712.8  154.31  3816.2  150.94  3853.5   152.2
    4111  146.93  4136.5  146.29  4210.1  143.83  4318.3  142.04  4339.5  138.57
  4417.3  143.13  4598.9  142.82  4692.7  142.71  4933.4  143.16  5001.2  136.02
  5014.4  132.05  5014.9  131.55  5022.2  132.05  5032.5  137.55  5061.1  141.06
  5081.9   140.5  5124.7  146.72  5158.1  146.77  5262.9   150.8  5412.2  154.46
  5458.2  156.38  5611.9  154.11  5649.1  153.03  5656.7  155.39  5762.3  153.35
#Mann= 16 ,-1 , 0
  3575.1    .035       0  3704.1     .05       0  3712.8    .035       0
  3853.5     .05       0    4111    .035       0  4136.5     .07       0
  4210.1      .1       0  4598.9     .12       0  4692.7      .1       0
  5001.2     .12       0  5014.4     .05       0  5022.2     .12       0
  5158.1    .035       0  5262.9     .12       0  5412.2     .05       0
  5611.9     .12       0
Bank Sta=5014.4,5022.2
XS Rating Curve= 0 ,0
Exp/Cntr=0.3,0.1

Type RM Length L Ch R = 1 ,4991    ,1101,1101,1101
BEGIN DESCRIPTION:
Mapping XS f6e0bd62
END DESCRIPTION:
XS GIS Cut Line= 3
      2529969.64     13507815.89       2529587.7     13506808.94
      2528638.61     13505885.86
#Sta/Elev= 30
  4151.3  153.61  4208.9  155.33  4258.5  152.04    4286  152.64  4426.4  150.63
  4581.9  149.52  4780.9  146.56  4908.9  142.23  4939.1  136.06  4986.5  133.63
  5003.8  130.79  5004.3  130.29  5011.9  130.79  5029.5  138.49  5132.2  140.18
  5196.4  140.44  5251.5  141.04  5345.3   140.5  5445.1  140.14  5598.8   145.7
  5688.4  151.46  5745.8  154.97    5834  159.16  5879.3   160.6  5968.5  164.45
  5989.6  167.62    6131  171.51  6293.6   170.3  6549.2   163.8  6552.2  163.73
#Mann= 17 ,-1 , 0
  4151.3    .035       0    4286     .05       0  4426.4    .035       0
  4581.9     .07       0  4780.9      .1       0  5003.8     .05       0
  5011.9      .1       0  5132.2     .07       0  5196.4     .12       0
  5251.5     .07       0  5345.3     .12       0  5598.8      .1       0
  5688.4    .035       0  5745.8     .07       0    5834     .12       0
  5879.3     .05       0  6549.2     .12       0
Bank Sta=5003.8,5011.9
XS Rating Curve= 0 ,0
Exp/Cntr=0.3,0.1

Type RM Length L Ch R = 1 ,3890    ,664,664,664
BEGIN DESCRIPTION:
Mapping XS a3af5c6f
END DESCRIPTION:
XS GIS Cut Line= 4
      2530138.91     13507763.82       2530030.4      13506405.3
      2528997.42     13506140.54      2528619.89     13505680.56
#Sta/Elev= 30
  3477.1  152.63  3545.3  151.96  3907.3  148.05  4040.9  144.79    4140  142.85
  4167.9  142.81  4338.3  142.08  4669.7  137.14  4833.9  137.97  4873.4  138.29
  4959.1  137.98  4983.5  130.88    4986  128.03  4986.5  127.53  4994.1  128.03
  5024.3  131.61  5068.1  131.94  5124.3  137.29  5168.9  138.59  5258.5  138.16
  5269.7  140.47  5370.4  143.64  5462.6  152.63    5572  159.41  5672.7  163.28
  5705.2  164.59  5805.6  169.09  5939.8  171.82  6377.6  165.43  6501.4   163.5
#Mann= 18 ,-1 , 0
  3477.1    .035       0  3545.3     .05       0  4040.9    .035       0
    4140     .05       0  4167.9     .07       0  4338.3     .12       0
  4833.9     .07       0  4873.4     .12       0    4986     .05       0
  4994.1     .12       0  5068.1      .1       0  5168.9    .035       0
  5269.7     .12       0  5370.4     .07       0    5572     .05       0
  5672.7     .07       0  5705.2     .05       0  6377.6    .035       0
Bank Sta=4986,4994.1
XS Rating Curve= 0 ,0
Exp/Cntr=0.3,0.1

Type RM Length L Ch R = 1 ,3226    ,836,836,836
BEGIN DESCRIPTION:
Mapping XS 5a855827
END DESCRIPTION:
XS GIS Cut Line= 3
      2530282.14     13507516.41       2530030.4       13505802.
      2529205.77     13505246.46
#Sta/Elev= 30
  3243.8  149.38  3657.8  142.51    3743  142.68  3757.9  141.19  3857.9  140.05
  4158.1  136.02  4458.1  137.56  4478.3  139.89  4622.6  138.51  4660.2   135.5
  4710.8  137.38  4758.5  136.61    4822  133.61  4858.6  134.02  4902.8  134.64
  4976.6  132.26  4984.7  129.15  5003.1  126.63  5003.6  126.13  5011.3  126.63
  5029.6  131.06  5035.6  136.82  5043.4  139.28  5109.7  139.92    5220  141.75
  5311.8  143.89    5496  148.89  5680.2   158.4  5769.2  161.34  5970.9  165.67
#Mann= 16 ,-1 , 0
  3243.8     .05       0  3657.8    .035       0  3757.9     .05       0
  3857.9     .12       0  4158.1     .07       0  4622.6     .12       0
  4758.5     .07       0  4858.6      .1       0  5003.1     .05       0
  5011.3      .1       0  5109.7    .035       0    5220      .1       0
  5311.8     .12       0    5496     .07       0  5680.2     .12       0
  5769.2    .035       0
Bank Sta=5003.1,5011.3
XS Rating Curve= 0 ,0
Exp/Cntr=0.3,0.1

Type RM Length L Ch R = 1 ,2390    ,517,517,517
BEGIN DESCRIPTION:
Mapping XS 633f9b45
END DESCRIPTION:
XS GIS Cut Line= 3
      2531134.57     13507420.04      2530641.51     13506093.66
      2529815.12     13505111.02
#Sta/Elev= 30
  3564.4  143.35  3825.8  141.37  4206.7  135.31  4565.9  133.09  4743.3  133.55
  4756.8  135.93  4867.5   137.3  4938.8  135.41  4958.6  132.46  4976.1  126.07
  4979.5  126.07  4986.7  122.19  4987.2  121.69  4994.9  122.19  5011.6  127.03
  5061.1  133.73  5090.9  135.46    5178  138.81  5191.1     139  5323.1  138.26
  5332.9  137.72    5455  137.19  5480.7  137.11    5587  137.17  5628.6  136.94
  5718.9  136.82  5819.8  136.84  5997.6  138.61  6246.7  145.07  6263.4  145.51
#Mann= 17 ,-1 , 0
  3564.4     .05       0  4565.9      .1       0  4938.8     .12       0
  4986.7     .05       0  4994.9     .12       0  5090.9      .1       0
    5178     .12       0  5191.1      .1       0  5323.1     .12       0
  5332.9      .1       0    5455    .035       0  5480.7     .07       0
    5587    .035       0  5628.6      .1       0  5718.9    .035       0
  5819.8     .12       0  6246.7     .07       0
Bank Sta=4986.7,4994.9
XS Rating Curve= 0 ,0
Exp/Cntr=0.3,0.1

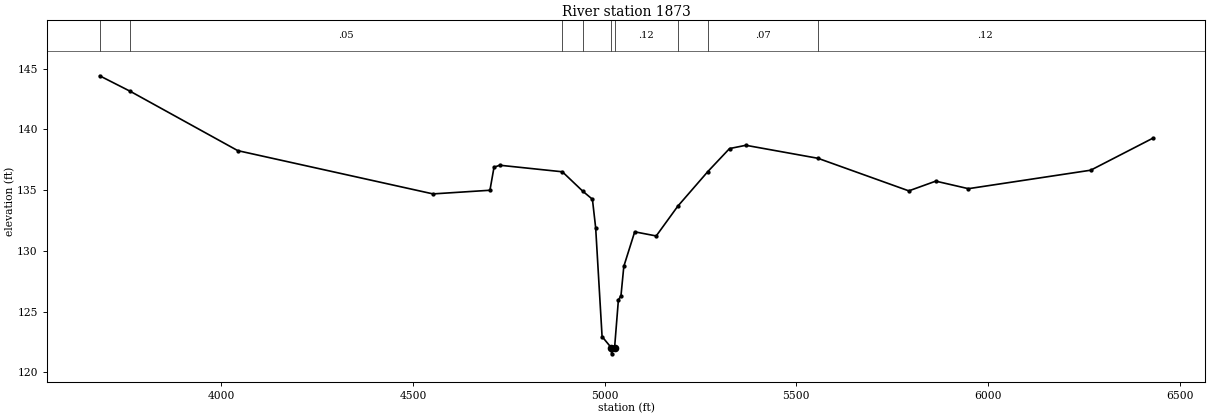
Type RM Length L Ch R = 1 ,1873    ,415,415,415
BEGIN DESCRIPTION:
Mapping XS c008bb6c
END DESCRIPTION:
XS GIS Cut Line= 3
      2531547.77     13507284.64      2531110.26     13506048.52
      2530144.96     13504985.99
#Sta/Elev= 30
  3682.9  144.41  3762.9  143.13  4043.2  138.25  4552.4  134.69  4700.9  134.99
  4711.5  136.88  4726.3  137.05  4889.8  136.51  4942.8  134.92  4968.2  134.25
  4976.7  131.89  4993.4  122.95  5017.5  122.03    5018  121.53    5026  122.03
  5035.9  125.95  5042.7  126.32  5050.1  128.73  5078.5  131.57  5134.6  131.23
  5190.9  133.68  5269.3  136.53  5325.8  138.42  5368.4  138.69  5556.5  137.62
  5793.4  134.94  5863.7  135.74  5948.9  135.12  6267.8  136.64  6429.7  139.27
#Mann= 9 ,-1 , 0
  3682.9     .12       0  3762.9     .05       0  4889.8     .07       0
  4942.8     .12       0  5017.5     .05       0    5026     .12       0
  5190.9      .1       0  5269.3     .07       0  5556.5     .12       0
Bank Sta=5017.5,5026
XS Rating Curve= 0 ,0
Exp/Cntr=0.3,0.1