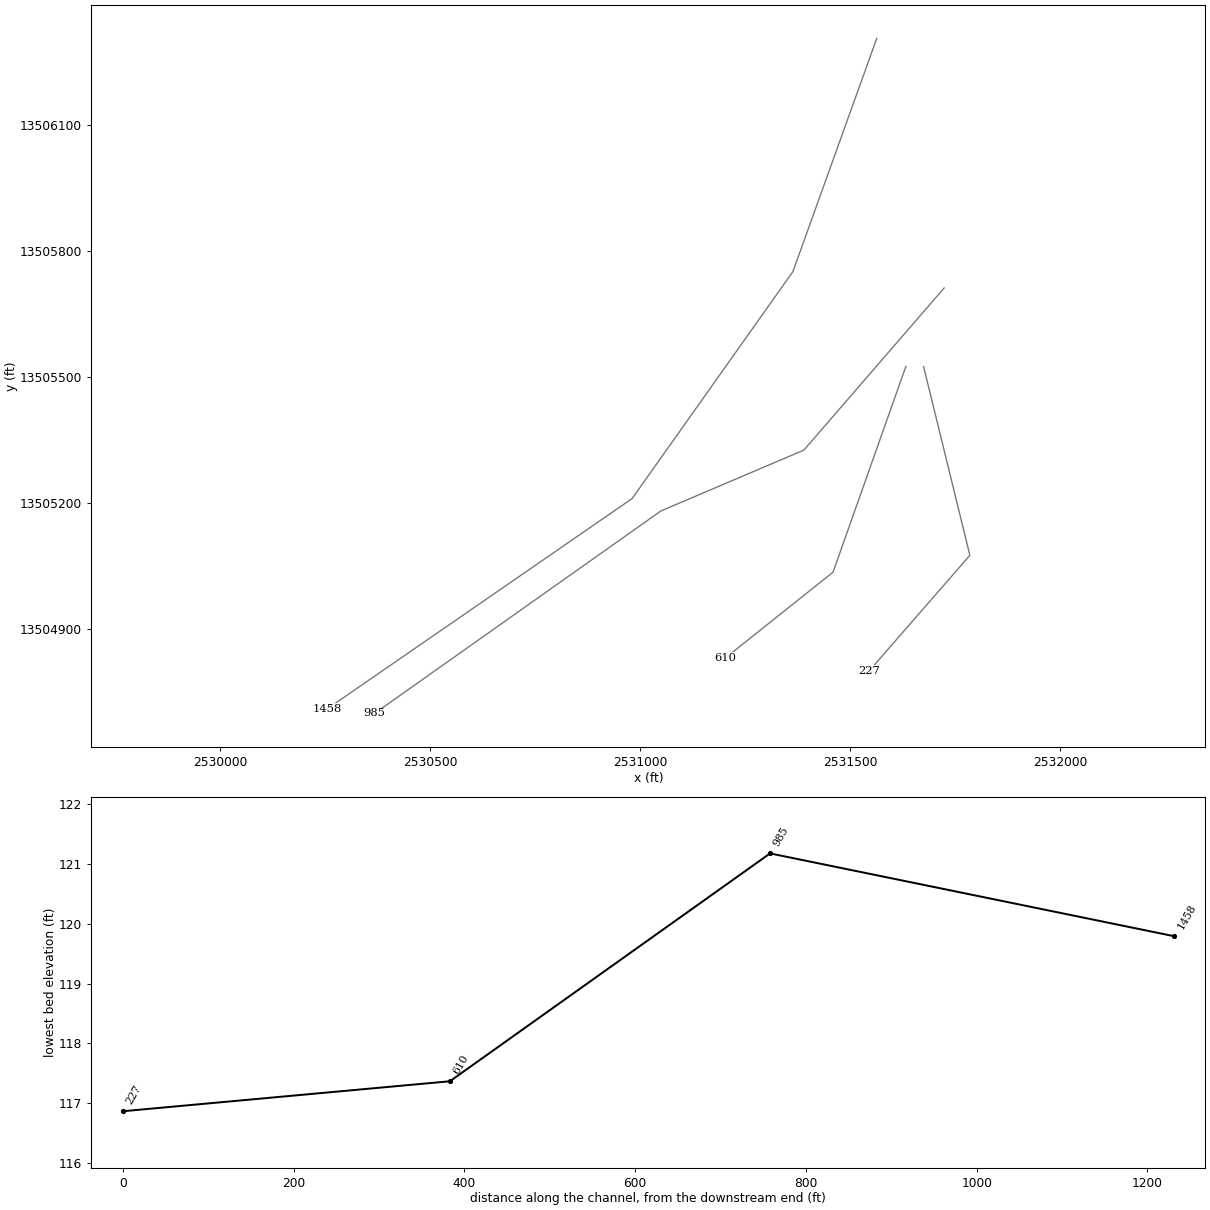
HEC-RAS study JOHNS CREEK.prj: JOHNS CREEK Base Level Engineering

--- JOHNS CREEK.g01 (geometry) --- (continued)

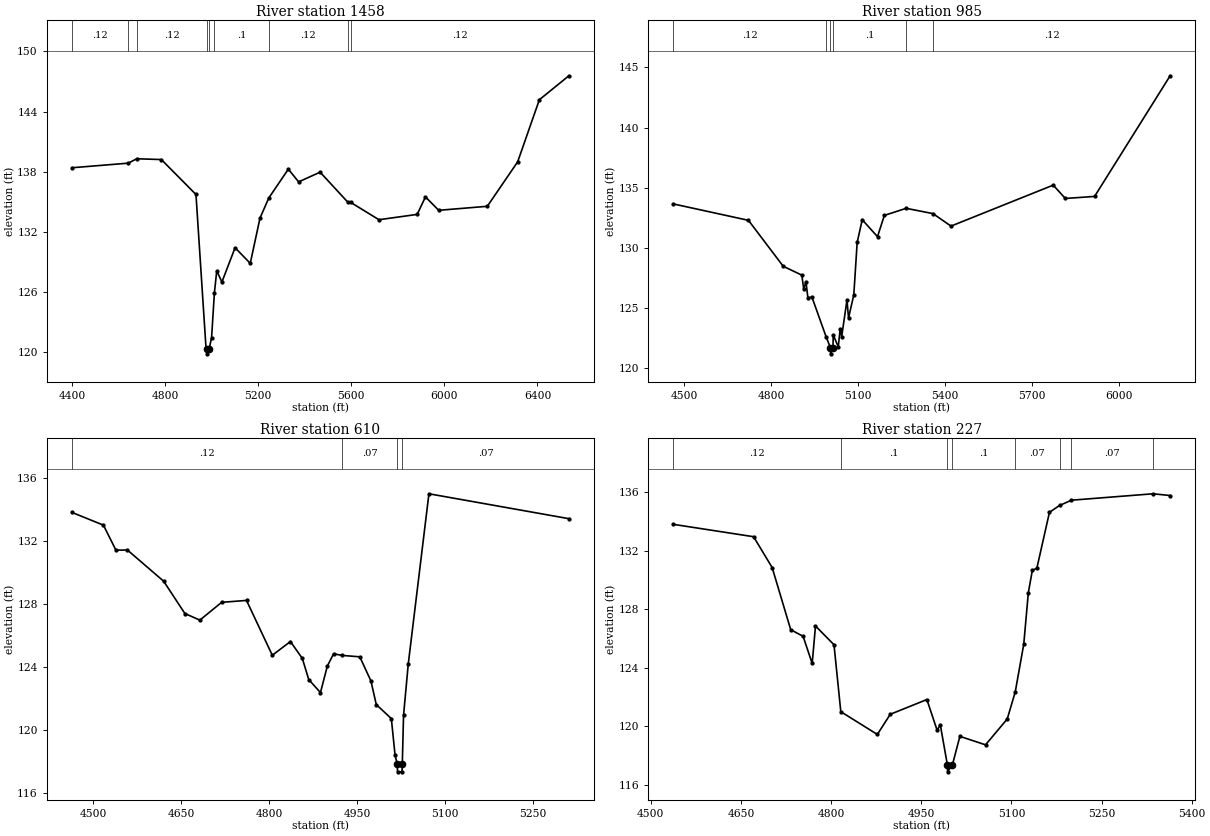
Type RM Length L Ch R = 1 ,1458    ,473,473,473
BEGIN DESCRIPTION:
Mapping XS 7ac92fda
END DESCRIPTION:
XS GIS Cut Line= 4
      2531563.39     13506307.04      2531363.75     13505751.51
      2530980.57     13505210.67      2530253.74     13504709.33
#Sta/Elev= 30
  4398.8  138.38  4641.5  138.84  4677.7  139.28  4783.5   139.2  4932.3  135.71
  4975.4  120.39  4980.4  120.29  4980.9  119.79  4988.9  120.29  4999.4  121.41
  5011.4  125.86  5021.6  128.08  5043.7  126.96  5100.3  130.39  5165.6  128.83
  5207.4  133.35  5245.2  135.36  5329.2  138.24  5373.5  136.97  5465.8  137.94
  5584.5  134.95  5596.6  134.93  5718.5  133.19  5882.8  133.72  5918.6  135.47
  5975.4  134.13  6184.3  134.53  6314.7  138.97  6408.1  145.18  6534.9  147.57
#Mann= 9 ,-1 , 0
  4398.8     .12       0  4641.5     .07       0  4677.7     .12       0
  4980.4     .05       0  4988.9     .12       0  5011.4      .1       0
  5245.2     .12       0  5584.5     .07       0  5596.6     .12       0
Bank Sta=4980.4,4988.9
XS Rating Curve= 0 ,0
Exp/Cntr=0.3,0.1

Type RM Length L Ch R = 1 ,985     ,375,375,375
BEGIN DESCRIPTION:
Mapping XS a13b4c7e
END DESCRIPTION:
XS GIS Cut Line= 4
      2531723.96     13505712.41      2531389.79     13505326.16
      2531049.29     13505181.27      2530367.35     13504699.06
#Sta/Elev= 30
  4460.8  133.65    4721  132.28  4840.9  128.46  4905.2  127.72  4911.8  126.56
  4919.5  127.18  4926.1  125.85  4940.3  125.88  4988.8  122.61  5004.1  121.67
  5004.6  121.17  5012.6  121.67  5013.8  122.74  5031.1  121.75  5037.4   123.2
  5042.9  122.61  5061.1  125.65  5066.5  124.15  5084.7  126.09  5096.3  130.44
  5113.8  132.33  5166.5  130.92  5190.1  132.69  5265.4  133.28  5357.9  132.84
  5420.3   131.8  5773.1  135.21  5814.9   134.1  5915.9  134.27  6176.8  144.31
#Mann= 6 ,-1 , 0
  4460.8     .12       0  4988.8      .1       0  5004.1     .05       0
  5012.6      .1       0  5265.4     .07       0  5357.9     .12       0
Bank Sta=5004.1,5012.6
XS Rating Curve= 0 ,0
Exp/Cntr=0.3,0.1

Type RM Length L Ch R = 1 ,610     ,383,383,383
BEGIN DESCRIPTION:
Mapping XS a2ea8f1e
END DESCRIPTION:
XS GIS Cut Line= 3
      2531632.86     13505525.85      2531459.23     13505035.36
      2531203.16     13504831.37
#Sta/Elev= 30
  4463.2  133.84  4517.1  133.03  4538.4  131.44    4558  131.45  4619.8  129.47
    4656  127.42  4681.5     127  4718.7  128.13  4761.1  128.25  4805.1  124.77
    4836  125.64  4856.3  124.57  4867.2  123.23  4887.2   122.4    4899  124.09
  4909.6  124.86  4924.7  124.76  4954.3  124.67  4973.3  123.14  4982.4  121.64
  5008.1  120.75  5014.5  118.41  5018.2  117.87  5018.7  117.37  5026.3  117.37
  5026.8  117.87  5028.9  120.95    5037  124.23  5072.2  135.02  5310.9  133.44
#Mann= 4 ,-1 , 0
  4463.2     .12       0  4924.7     .07       0  5018.2     .05       0
  5026.8     .07       0
Bank Sta=5018.2,5026.8
XS Rating Curve= 0 ,0
Exp/Cntr=0.3,0.1

Type RM Length L Ch R = 1 ,227     ,0,0,0
BEGIN DESCRIPTION:
JOHNS CREEK 1.0
END DESCRIPTION:
XS GIS Cut Line= 3
      2531674.99     13505525.04      2531785.19     13505075.55
      2531546.04     13504800.99
#Sta/Elev= 30
  4537.2  133.82  4671.1  132.97    4702  130.86  4732.9   126.6  4753.5  126.15
  4768.6  124.29  4774.1  126.86  4804.9  125.57  4816.2  120.99    4877  119.43
  4898.5  120.81  4959.4  121.82  4976.5  119.71  4981.7   120.1  4993.4  117.37
  4993.9  116.87    5002  117.37  5014.3   119.3    5057  118.72  5093.1  120.49
  5106.4  122.34  5120.6  125.62  5128.2  129.14  5134.8  130.66  5142.4  130.82
  5163.3  134.64  5180.1  135.11  5199.9  135.47  5335.8  135.91  5364.1  135.79
#Mann= 8 ,-1 , 0
  4537.2     .12       0  4816.2      .1       0  4993.4     .05       0
    5002      .1       0  5106.4     .07       0  5180.1     .05       0
  5199.9     .07       0  5335.8     .05       0
Bank Sta=4993.4,5002
XS Rating Curve= 0 ,0
Exp/Cntr=0.3,0.1

Chan Stop Cuts=-1
Use User Specified Reach Order=0
Composite Channel Slope=5