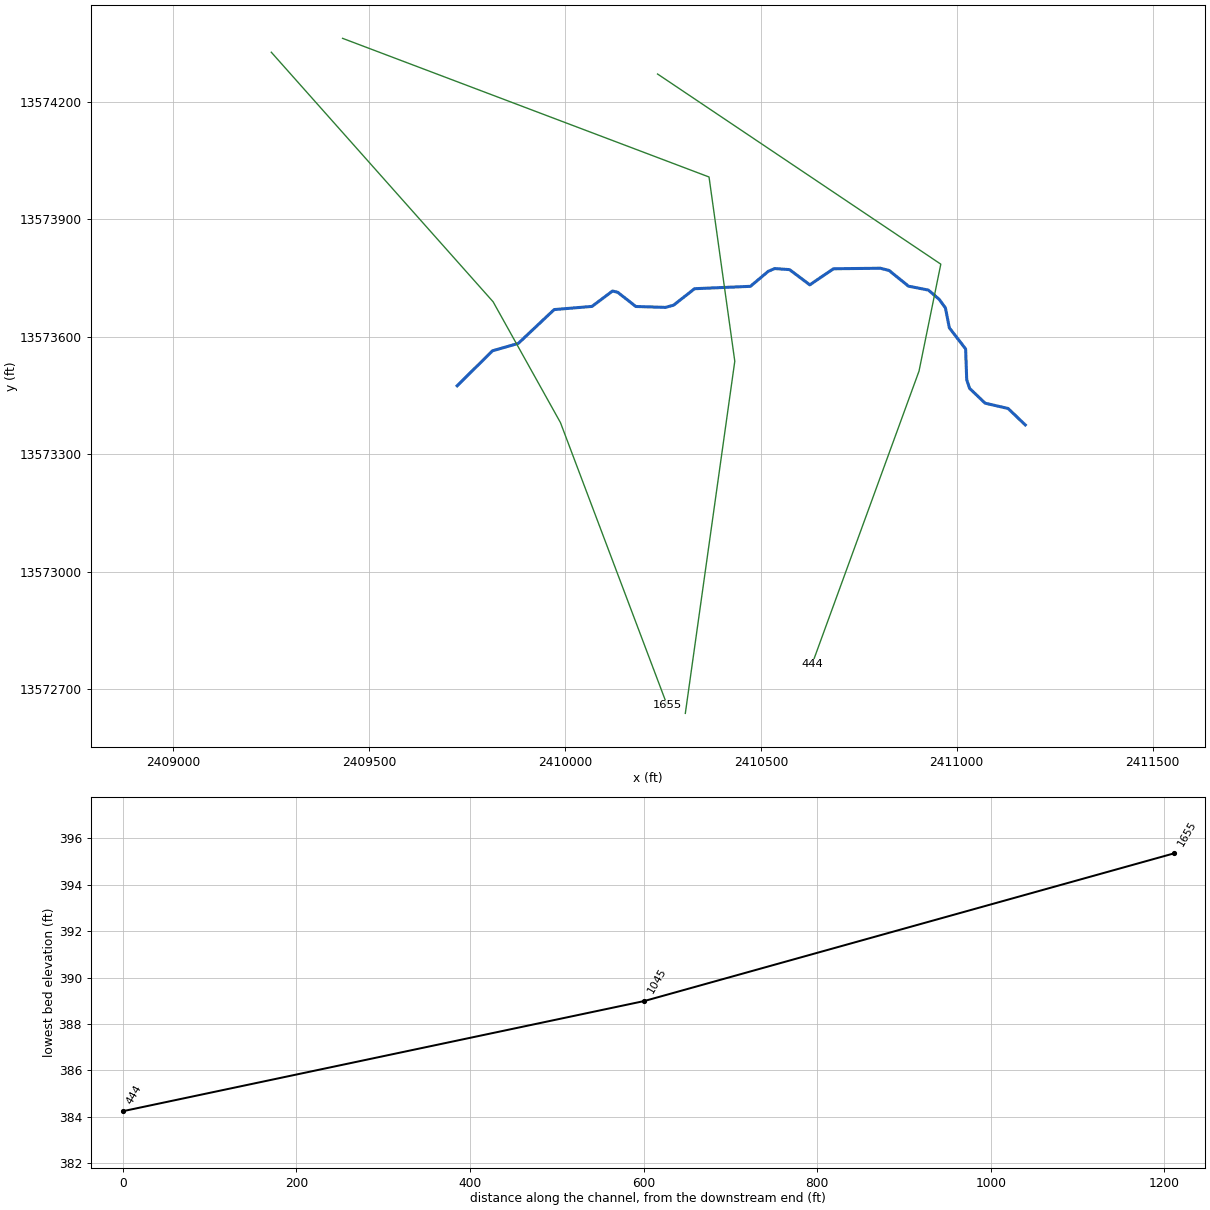
--- LG Stream126.prj (project) ---

Proj Title=LG Stream126 Base Level Engineering
Current Plan=p01
Default Exp/Contr=0.3,0.1
English Units
Geom File=g01
Flow File=f01
Plan File=p01
Y Axis Title=Elevation
X Axis Title(PF)=Main Channel Distance
X Axis Title(XS)=Station
BEGIN DESCRIPTION:
LG Stream126
END DESCRIPTION:
DSS Export Rating Curves= 0
DSS Export Rating Curve Sorted= 0
DSS Export Volume Flow Curves= 0
DXF OffsetX= 0
DXF OffsetY= 0
DXF ScaleX= 1
DXF ScaleY= 10

--- LG Stream126.p01 (plan) ---

Plan Title=Multiple Run
Short Identifier=Multiple
Geom File=g01
Flow File=f01
Subcritical Flow
K Sum by GR= 0
Std Step Tol= 0.01
Critical Tol= 0.01
Num of Std Step Trials= 20
Max Error Tol= 0.3
Flow Tol Ratio= 0.001
Split Flow NTrial= 30
Split Flow Tol= 0.02
Split Flow Ratio= 0.02
Log Output Level= 0
Friction Slope Method= 1
Unsteady Friction Slope Method= 2
Unsteady Bridges Friction Slope Method= 1
Parabolic Critical Depth
Global Vel Dist=  1 , 1 , 1
Global Log Level= 0
CheckData=True
Encroach Param= -1, 0, 0, 0
BEGIN DESCRIPTION:
Multiple Run
END DESCRIPTION:

--- LG Stream126.f01 (steady flow) ---

Flow Title=Multiple
Number of Profiles=7
Profile Names=10-year,25-year,50-year,1pct_min,100-year,1pct_plu,500-year
River Rch & RM= LG Stream126,Reach-1,1655
     430     686     915     593    1183    2361    1957
Boundary for River Rch & Prof#=LG Stream126,Reach-1,1
Up Type=0
Dn Type=3
Dn Slope=0.005
Boundary for River Rch & Prof#=LG Stream126,Reach-1,2
Up Type=0
Dn Type=3
Dn Slope=0.005
Boundary for River Rch & Prof#=LG Stream126,Reach-1,3
Up Type=0
Dn Type=3
Dn Slope=0.005
Boundary for River Rch & Prof#=LG Stream126,Reach-1,4
Up Type=0
Dn Type=3
Dn Slope=0.005
Boundary for River Rch & Prof#=LG Stream126,Reach-1,5
Up Type=0
Dn Type=3
Dn Slope=0.005
Boundary for River Rch & Prof#=LG Stream126,Reach-1,6
Up Type=0
Dn Type=3
Dn Slope=0.005
Boundary for River Rch & Prof#=LG Stream126,Reach-1,7
Up Type=0
Dn Type=3
Dn Slope=0.005

--- LG Stream126.g01 (geometry) ---

Geom Title=Existing Conditions

River Reach=LG Stream126,Reach-1
Reach XY= 30
      2409725.00     13573475.00      2409815.30     13573564.28
      2409881.04     13573583.17      2409972.58     13573669.47
      2410069.10     13573677.56      2410121.70     13573716.92
      2410134.91     13573713.52      2410180.89     13573677.36
      2410256.66     13573675.06      2410277.31     13573680.69
      2410330.94     13573722.73      2410473.44     13573728.82
      2410519.09     13573767.17      2410535.71     13573774.18
      2410573.36     13573771.39      2410624.99     13573732.59
      2410685.44     13573773.63      2410804.97     13573774.96
      2410827.35     13573769.30      2410876.78     13573729.23
      2410927.55     13573719.27      2410955.38     13573695.48
      2410971.14     13573673.58      2410981.15     13573622.85
      2411022.67     13573569.03      2411025.47     13573490.09
      2411032.73     13573468.54      2411072.35     13573430.59
      2411131.11     13573417.05      2411175.00     13573375.00

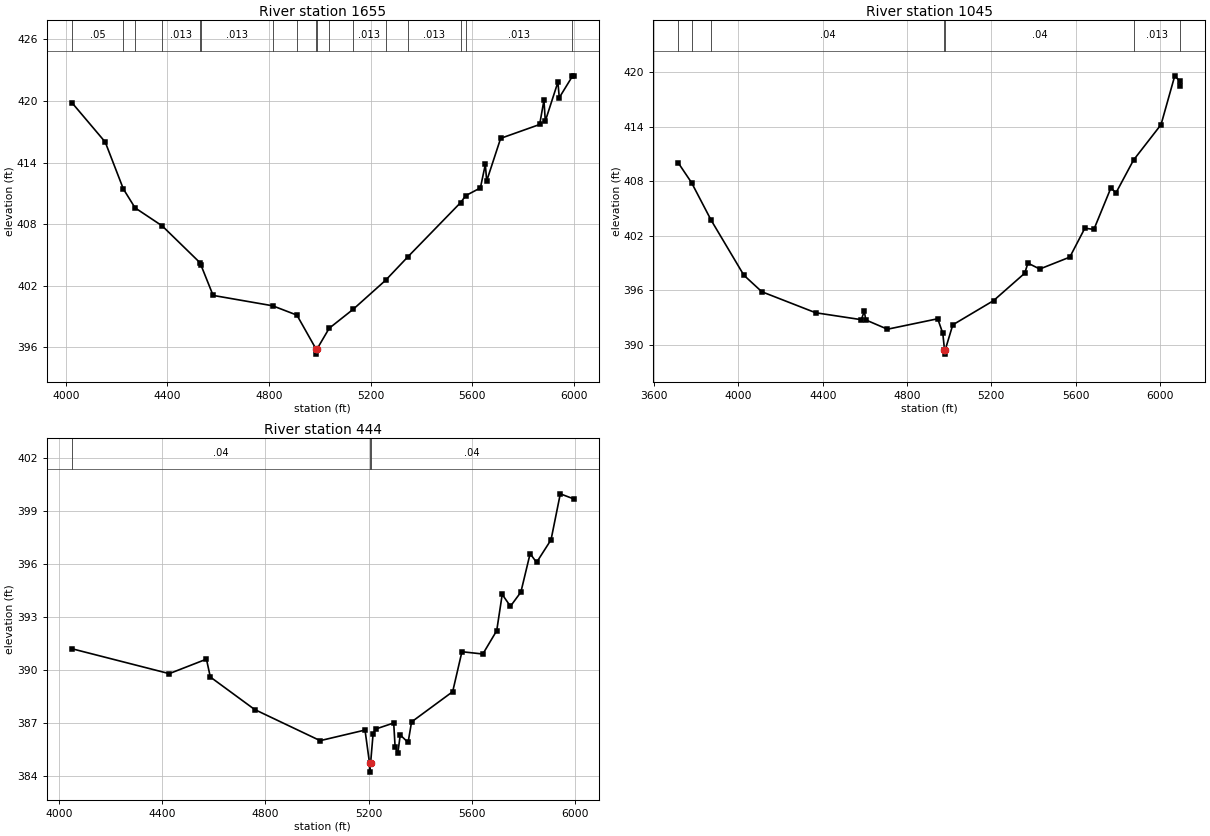
Type RM Length L Ch R = 1,1655,610,610,610
BEGIN DESCRIPTION:
LGII4678
END DESCRIPTION:
XS GIS Cut Line= 4
      2409250.64     13574326.28      2409816.81     13573689.34
      2409988.69     13573380.96      2410261.29     13572659.06
#Sta/Elev= 30
  4023.6  419.86  4155.3  416.01  4226.7  411.44  4272.8  409.60  4379.7  407.84
  4529.9  404.22  4532.7  404.00  4580.1  401.07  4814.4  400.06  4910.1  399.15
  4985.3  395.85  4985.5  395.35  4989.3  395.85  5037.2  397.87  5132.2  399.73
  5259.1  402.54  5346.6  404.82  5555.0  410.12  5574.8  410.79  5632.5  411.54
  5652.0  413.83  5657.3  412.22  5712.3  416.37  5865.9  417.72  5882.8  420.09
  5888.1  418.05  5937.8  421.85  5943.1  420.33  5994.8  422.42  6000.5  422.46
#Mann=17,-1,0
  4023.6    0.05       0  4226.7   0.013       0  4272.8    0.05       0
  4379.7   0.013       0  4529.9    0.05       0  4532.7   0.013       0
  4814.4    0.04       0  4910.1   0.013       0  4985.3    0.03       0
  4989.3   0.013       0  5037.2    0.04       0  5132.2   0.013       0
  5259.1    0.04       0  5346.6   0.013       0  5555.0    0.05       0
  5574.8   0.013       0  5994.8    0.04       0
Bank Sta=4985.3,4989.3
Exp/Cntr=0.3,0.1

Type RM Length L Ch R = 1,1045,601,601,601
BEGIN DESCRIPTION:
LGII4677
END DESCRIPTION:
XS GIS Cut Line= 4
      2409432.61     13574361.70      2410367.84     13574007.83
      2410433.56     13573537.68      2410307.33     13572638.96
#Sta/Elev= 30
  3714.4  410.03  3777.6  407.85  3870.3  403.73  4025.8  397.67  4111.0  395.85
  4366.5  393.54  4583.0  392.78  4597.1  393.71  4604.4  392.75  4707.1  391.73
  4945.5  392.88  4969.6  391.28  4977.7  389.49  4978.0  388.99  4981.7  389.49
  5017.0  392.21  5210.8  394.88  5358.4  397.89  5373.5  399.00  5429.7  398.35
  5572.3  399.66  5643.6  402.84  5686.6  402.71  5767.4  407.28  5791.2  406.72
  5874.8  410.34  6005.1  414.23  6070.3  419.60  6093.7  419.01  6096.6  418.52
#Mann=7,-1,0
  3714.4    0.04       0  3777.6    0.05       0  3870.3    0.04       0
  4977.7    0.04       0  4981.7    0.04       0  5874.8   0.013       0
  6093.7    0.04       0
Bank Sta=4977.7,4981.7
Exp/Cntr=0.3,0.1

Type RM Length L Ch R = 1,444,0,0,0
BEGIN DESCRIPTION:
LGII4676
END DESCRIPTION:
XS GIS Cut Line= 4
      2410236.42     13574270.69      2410959.32     13573785.39
      2410903.71     13573512.40      2410630.72     13572764.23
#Sta/Elev= 30
  4049.6  391.22  4427.4  389.81  4571.5  390.63  4586.5  389.62  4758.5  387.78
  5012.2  386.02  5186.0  386.62  5203.6  384.74  5203.8  384.24  5207.6  384.74
  5217.4  386.42  5228.0  386.68  5297.2  387.02  5302.6  385.67  5313.2  385.32
  5322.5  386.34  5353.0  385.92  5366.4  387.08  5525.7  388.79  5561.6  391.05
  5642.6  390.92  5696.4  392.24  5717.7  394.29  5749.6  393.62  5790.0  394.42
  5825.9  396.60  5850.8  396.10  5906.9  397.38  5942.8  399.98  5995.3  399.69
#Mann=3,-1,0
  4049.6    0.04       0  5203.6    0.04       0  5207.6    0.04       0
Bank Sta=5203.6,5207.6
Exp/Cntr=0.3,0.1

Chan Stop Cuts=-1