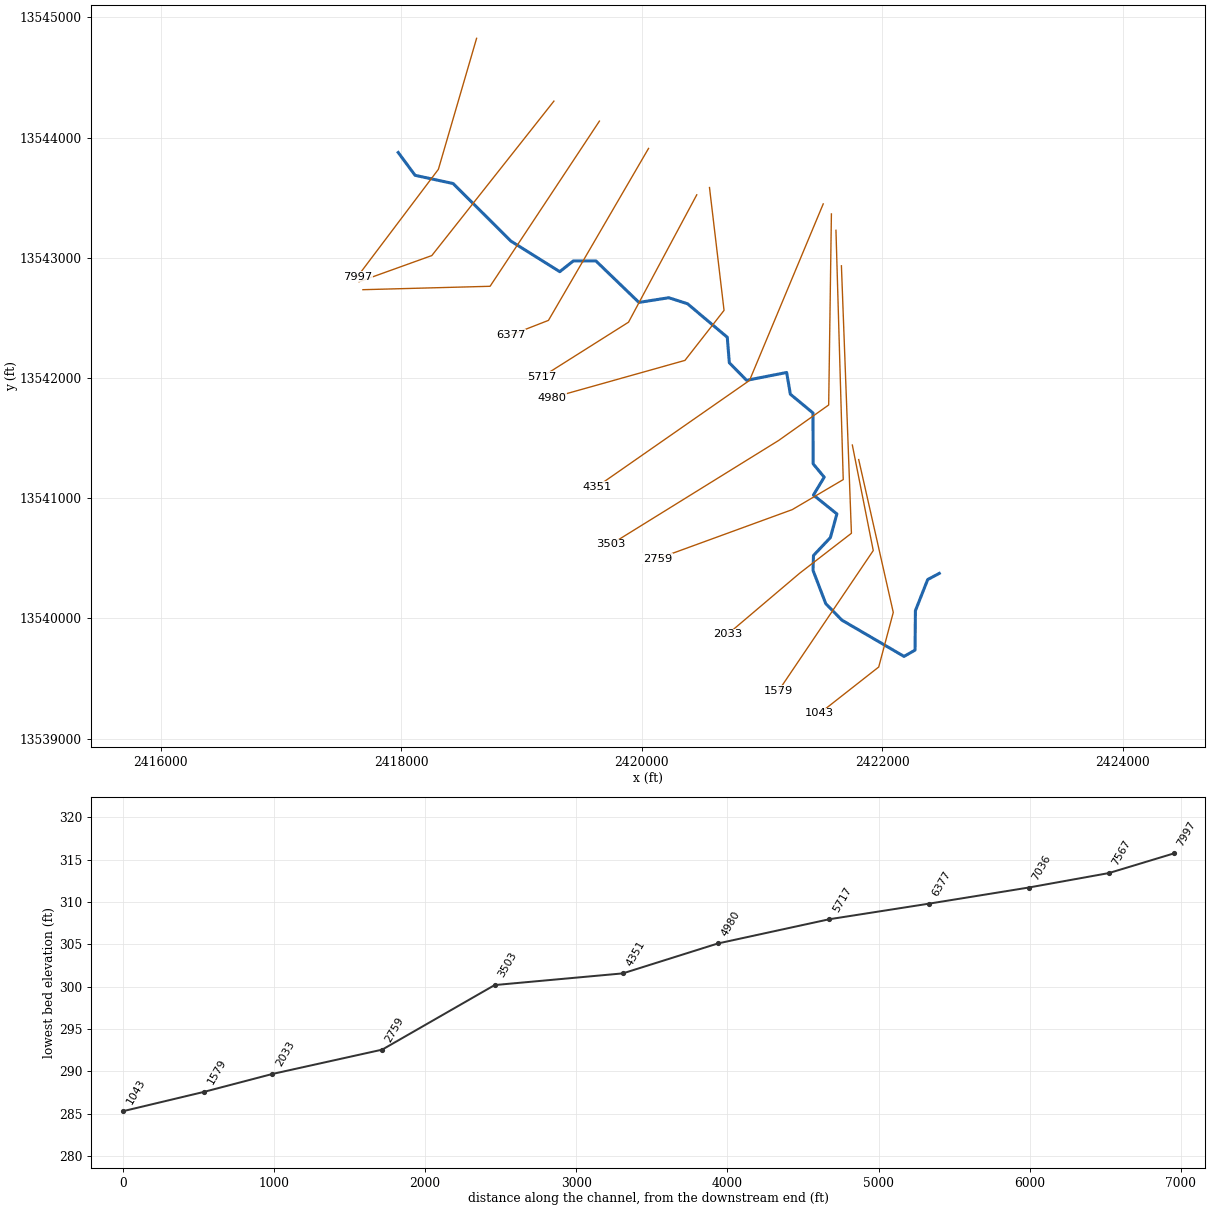
--- LG Stream140.prj (project) ---

Proj Title=LG Stream140 Base Level Engineering
Current Plan=p01
Default Exp/Contr=0.3,0.1
English Units
Geom File=g01
Flow File=f01
Plan File=p01
Y Axis Title=Elevation
X Axis Title(PF)=Main Channel Distance
X Axis Title(XS)=Station
BEGIN DESCRIPTION:
LG Stream140
END DESCRIPTION:
DSS Export Rating Curves= 0
DSS Export Rating Curve Sorted= 0
DSS Export Volume Flow Curves= 0
DXF OffsetX= 0
DXF OffsetY= 0
DXF ScaleX= 1
DXF ScaleY= 10

--- LG Stream140.p01 (plan) ---

Plan Title=Multiple Run
Short Identifier=Multiple
Geom File=g01
Flow File=f01
Subcritical Flow
K Sum by GR= 0
Std Step Tol= 0.01
Critical Tol= 0.01
Num of Std Step Trials= 20
Max Error Tol= 0.3
Flow Tol Ratio= 0.001
Split Flow NTrial= 30
Split Flow Tol= 0.02
Split Flow Ratio= 0.02
Log Output Level= 0
Friction Slope Method= 1
Unsteady Friction Slope Method= 2
Unsteady Bridges Friction Slope Method= 1
Parabolic Critical Depth
Global Vel Dist=  1 , 1 , 1
Global Log Level= 0
CheckData=True
Encroach Param= -1, 0, 0, 0
BEGIN DESCRIPTION:
Multiple Run
END DESCRIPTION:

--- LG Stream140.f01 (steady flow) ---

Flow Title=Multiple
Number of Profiles=7
Profile Names=10-year,25-year,50-year,1pct_min,100-year,1pct_plu,500-year
River Rch & RM= LG Stream140,Reach-1,7997
     691    1123    1516     990    1976    3942    3321
River Rch & RM= LG Stream140,Reach-1,7036
     849    1395    1896    1245    2485    4958    4228
Boundary for River Rch & Prof#=LG Stream140,Reach-1,1
Up Type=0
Dn Type=3
Dn Slope=0.005
Boundary for River Rch & Prof#=LG Stream140,Reach-1,2
Up Type=0
Dn Type=3
Dn Slope=0.005
Boundary for River Rch & Prof#=LG Stream140,Reach-1,3
Up Type=0
Dn Type=3
Dn Slope=0.005
Boundary for River Rch & Prof#=LG Stream140,Reach-1,4
Up Type=0
Dn Type=3
Dn Slope=0.005
Boundary for River Rch & Prof#=LG Stream140,Reach-1,5
Up Type=0
Dn Type=3
Dn Slope=0.005
Boundary for River Rch & Prof#=LG Stream140,Reach-1,6
Up Type=0
Dn Type=3
Dn Slope=0.005
Boundary for River Rch & Prof#=LG Stream140,Reach-1,7
Up Type=0
Dn Type=3
Dn Slope=0.005

--- LG Stream140.g01 (geometry) ---

Geom Title=Existing Conditions

River Reach=LG Stream140,Reach-1
Reach XY= 30
      2417975.00     13543875.00      2418115.19     13543685.51
      2418431.19     13543617.18      2418911.79     13543138.63
      2419318.33     13542883.96      2419431.05     13542973.33
      2419619.13     13542973.42      2419976.73     13542628.37
      2420224.99     13542667.41      2420381.17     13542617.14
      2420711.50     13542338.69      2420728.61     13542126.50
      2420872.57     13541980.40      2421205.39     13542045.68
      2421236.24     13541865.00      2421424.34     13541709.17
      2421426.06     13541285.43      2421517.90     13541175.00
      2421428.09     13541026.64      2421623.11     13540869.29
      2421569.17     13540672.70      2421428.53     13540523.53
      2421424.77     13540399.93      2421530.83     13540122.70
      2421665.32     13539985.76      2422181.66     13539684.37
      2422273.38     13539736.79      2422276.20     13540064.50
      2422378.46     13540323.70      2422475.00     13540375.00

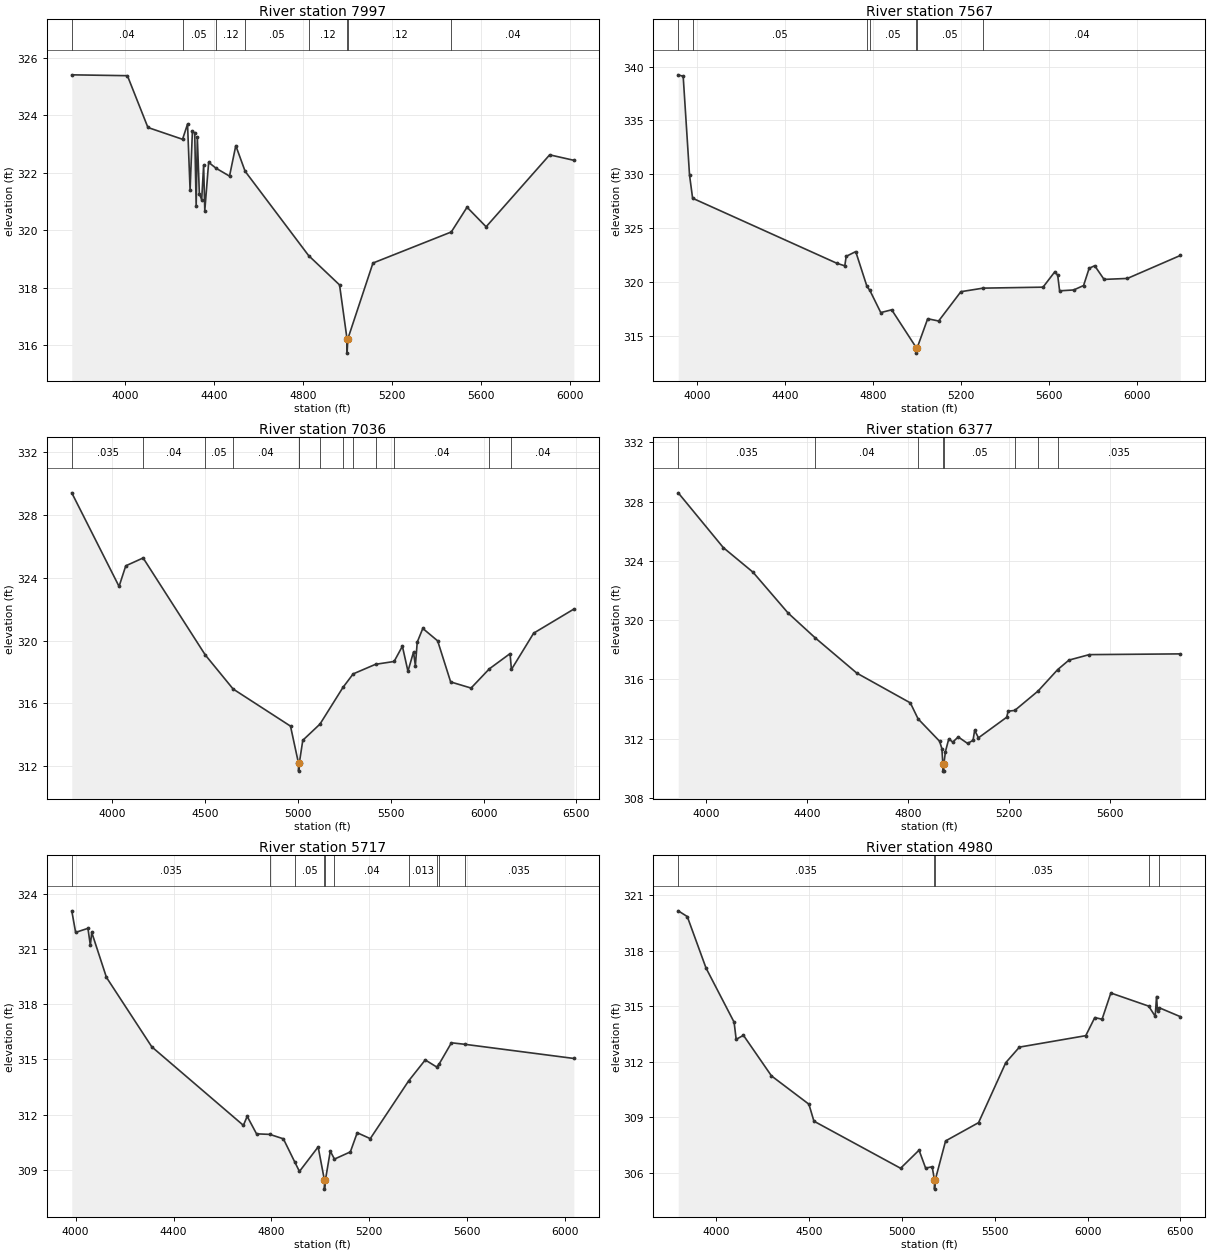
Type RM Length L Ch R = 1,7997,430,430,430
BEGIN DESCRIPTION:
LGII4641
END DESCRIPTION:
XS GIS Cut Line= 3
      2418626.69     13544824.72      2418308.90     13543735.16
      2417635.48     13542842.30
#Sta/Elev= 30
  3762.1  325.40  4011.8  325.37  4103.9  323.57  4259.3  323.16  4281.7  323.69
  4293.1  321.40  4303.5  323.44  4313.9  323.38  4320.4  320.84  4325.6  323.23
  4334.7  321.27  4345.1  321.06  4353.9  322.26  4359.1  320.68  4376.4  322.36
  4408.5  322.16  4470.1  321.88  4498.2  322.94  4540.0  322.05  4825.0  319.12
  4963.9  318.10  4997.3  316.23  4997.6  315.73  5001.3  316.23  5113.8  318.86
  5465.4  319.94  5536.1  320.80  5621.7  320.12  5906.9  322.62  6015.4  322.43
#Mann=8,-1,0
  3762.1    0.04       0  4259.3    0.05       0  4408.5    0.12       0
  4540.0    0.05       0  4825.0    0.12       0  4997.3    0.05       0
  5001.3    0.12       0  5465.4    0.04       0
Bank Sta=4997.3,5001.3
Exp/Cntr=0.3,0.1

Type RM Length L Ch R = 1,7567,531,531,531
BEGIN DESCRIPTION:
LGII4640
END DESCRIPTION:
XS GIS Cut Line= 3
      2419269.87     13544302.66      2418254.43     13543018.08
      2417649.06     13542800.34
#Sta/Elev= 30
  3915.7  339.23  3938.2  339.09  3967.0  329.93  3981.0  327.78  4637.0  321.74
  4672.3  321.51  4678.7  322.39  4722.0  322.83  4773.0  319.60  4785.9  319.24
  4835.8  317.17  4885.4  317.43  4997.2  313.91  4997.4  313.41  5001.3  313.91
  5048.9  316.60  5098.6  316.39  5199.7  319.11  5300.5  319.44  5572.8  319.53
  5626.9  320.97  5639.5  320.63  5648.2  319.19  5712.0  319.27  5757.0  319.68
  5782.4  321.28  5807.6  321.52  5850.1  320.25  5956.1  320.34  6196.5  322.47
#Mann=7,-1,0
  3915.7    0.04       0  3981.0    0.05       0  4773.0    0.04       0
  4785.9    0.05       0  4997.2    0.05       0  5001.3    0.05       0
  5300.5    0.04       0
Bank Sta=4997.2,5001.3
Exp/Cntr=0.3,0.1

Type RM Length L Ch R = 1,7036,659,659,659
BEGIN DESCRIPTION:
LGII4639
END DESCRIPTION:
XS GIS Cut Line= 3
      2419648.19     13544136.20      2418738.89     13542762.58
      2417681.49     13542734.26
#Sta/Elev= 30
  3781.3  329.39  4036.1  323.44  4072.2  324.75  4165.8  325.25  4500.3  319.09
  4650.6  316.92  4959.8  314.56  5002.9  312.20  5003.2  311.70  5007.1  312.20
  5026.0  313.66  5118.6  314.69  5242.4  317.02  5297.4  317.88  5417.9  318.49
  5518.0  318.67  5562.6  319.64  5592.6  318.05  5622.6  319.27  5632.6  318.40
  5642.6  319.90  5672.6  320.77  5752.6  319.98  5822.7  317.37  5932.7  316.98
  6030.9  318.20  6142.8  319.17  6150.0  318.16  6269.9  320.47  6486.4  322.00
#Mann=13,-1,0
  3781.3   0.035       0  4165.8    0.04       0  4500.3    0.05       0
  4650.6    0.04       0  5002.9    0.04       0  5007.1    0.04       0
  5118.6    0.05       0  5242.4    0.04       0  5297.4    0.05       0
  5417.9   0.035       0  5518.0    0.04       0  6030.9   0.013       0
  6150.0    0.04       0
Bank Sta=5002.9,5007.1
Exp/Cntr=0.3,0.1

Type RM Length L Ch R = 1,6377,660,660,660
BEGIN DESCRIPTION:
LGII4638
END DESCRIPTION:
XS GIS Cut Line= 3
      2420056.79     13543909.22      2419224.45     13542479.11
      2418914.23     13542358.05
#Sta/Elev= 30
  3891.1  328.60  4069.5  324.90  4187.0  323.24  4326.0  320.48  4432.9  318.81
  4598.2  316.42  4810.0  314.41  4840.7  313.33  4925.7  311.82  4934.9  311.32
  4938.6  310.30  4938.9  309.80  4942.6  309.80  4942.9  310.30  4948.9  311.12
  4962.2  311.98  4978.0  311.76  4999.5  312.11  5036.7  311.67  5058.2  311.88
  5064.6  312.56  5079.7  312.05  5191.4  313.44  5197.2  313.85  5223.4  313.90
  5315.6  315.21  5393.4  316.66  5438.0  317.30  5518.3  317.67  5878.8  317.72
#Mann=8,-1,0
  3891.1   0.035       0  4432.9    0.04       0  4840.7    0.05       0
  4938.6    0.05       0  4942.9    0.05       0  5223.4    0.12       0
  5315.6    0.05       0  5393.4   0.035       0
Bank Sta=4938.6,4942.9
Exp/Cntr=0.3,0.1

Type RM Length L Ch R = 1,5717,737,737,737
BEGIN DESCRIPTION:
LGII4637
END DESCRIPTION:
XS GIS Cut Line= 3
      2420457.80     13543523.30      2419890.31     13542463.98
      2419171.51     13542010.00
#Sta/Elev= 30
  3984.2  323.06  4000.0  321.89  4050.3  322.11  4060.1  321.19  4065.8  321.89
  4125.9  319.45  4311.3  315.68  4685.6  311.42  4701.1  311.91  4739.3  310.96
  4793.6  310.93  4849.0  310.69  4895.6  309.43  4914.7  308.92  4991.1  310.25
  5016.6  308.46  5016.9  307.96  5020.9  308.46  5040.7  310.02  5057.8  309.59
  5122.7  309.98  5150.8  311.02  5204.1  310.70  5360.8  313.83  5428.8  314.97
  5475.1  314.59  5484.8  314.73  5535.8  315.90  5589.3  315.82  6036.1  315.05
#Mann=10,-1,0
  3984.2   0.035       0  4793.6    0.04       0  4895.6    0.05       0
  5016.6    0.05       0  5020.9    0.05       0  5057.8    0.04       0
  5360.8   0.013       0  5475.1   0.035       0  5484.8   0.013       0
  5589.3   0.035       0
Bank Sta=5016.6,5020.9
Exp/Cntr=0.3,0.1

Type RM Length L Ch R = 1,4980,629,629,629
BEGIN DESCRIPTION:
LGII4636
END DESCRIPTION:
XS GIS Cut Line= 4
      2420563.73     13543583.79      2420684.79     13542562.34
      2420359.43     13542146.18      2419254.71     13541835.95
#Sta/Elev= 30
  3795.1  320.17  3843.8  319.86  3944.9  317.07  4096.0  314.14  4107.2  313.21
  4146.3  313.43  4297.4  311.23  4498.8  309.70  4526.0  308.78  4992.8  306.23
  5092.2  307.21  5127.5  306.24  5163.0  306.31  5175.1  305.60  5175.4  305.10
  5179.5  305.60  5235.1  307.71  5412.7  308.70  5559.4  311.95  5632.8  312.79
  5990.1  313.41  6038.7  314.39  6078.0  314.30  6125.2  315.72  6329.0  315.01
  6364.1  314.46  6371.4  315.53  6376.6  314.73  6386.3  314.92  6499.4  314.44
#Mann=5,-1,0
  3795.1   0.035       0  5175.1   0.035       0  5179.5   0.035       0
  6329.0   0.013       0  6386.3   0.035       0
Bank Sta=5175.1,5179.5
Exp/Cntr=0.3,0.1

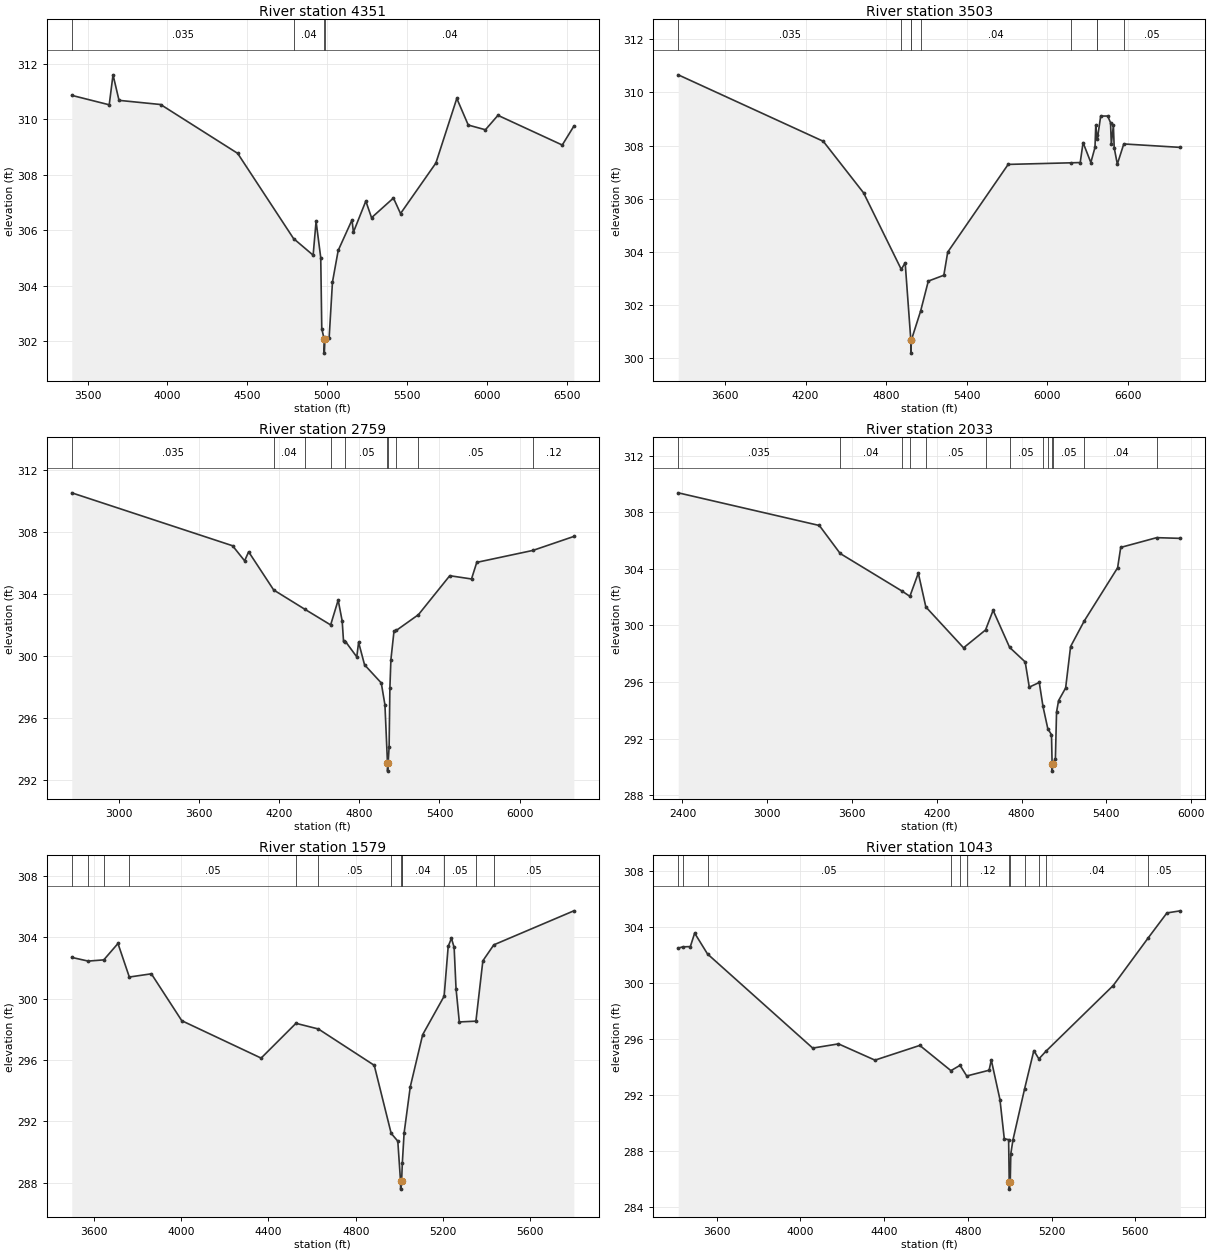
Type RM Length L Ch R = 1,4351,848,848,848
BEGIN DESCRIPTION:
LGII4635
END DESCRIPTION:
XS GIS Cut Line= 3
      2421509.56     13543447.67      2420896.66     13541979.72
      2419625.51     13541094.45
#Sta/Elev= 30
  3401.4  310.86  3635.6  310.52  3659.4  311.60  3696.9  310.68  3957.0  310.53
  4438.8  308.77  4788.2  305.70  4910.8  305.10  4929.2  306.32  4958.4  305.01
  4964.8  302.45  4980.0  302.07  4980.3  301.57  4984.5  302.07  5010.8  302.11
  5031.7  304.13  5067.5  305.27  5153.9  306.37  5162.7  305.93  5240.3  307.05
  5276.1  306.45  5413.1  307.16  5457.3  306.60  5678.4  308.42  5809.3  310.75
  5880.9  309.79  5988.2  309.62  6066.6  310.14  6468.7  309.07  6541.2  309.75
#Mann=4,-1,0
  3401.4   0.035       0  4788.2    0.04       0  4980.0    0.04       0
  4984.5    0.04       0
Bank Sta=4980,4984.5
Exp/Cntr=0.3,0.1

Type RM Length L Ch R = 1,3503,744,744,744
BEGIN DESCRIPTION:
LGII4634
END DESCRIPTION:
XS GIS Cut Line= 4
      2421577.64     13543364.35      2421554.94     13541775.42
      2421138.79     13541480.33      2419746.50     13540617.72
#Sta/Elev= 30
  3252.4  310.66  4331.9  308.16  4631.9  306.22  4912.6  303.34  4941.5  303.59
  4983.5  300.69  4983.8  300.19  4988.1  300.69  5057.0  301.78  5113.7  302.90
  5229.4  303.12  5258.2  303.99  5708.1  307.29  6176.3  307.35  6244.5  307.36
  6265.7  308.11  6323.6  307.36  6354.4  307.93  6360.2  308.76  6367.7  308.39
  6372.5  308.26  6396.9  309.11  6448.9  309.11  6470.1  308.86  6476.0  308.05
  6491.4  308.76  6497.3  307.92  6520.7  307.30  6568.8  308.06  6989.5  307.93
#Mann=9,-1,0
  3252.4   0.035       0  4912.6    0.05       0  4983.5    0.05       0
  4988.1    0.05       0  5057.0    0.04       0  6176.3   0.013       0
  6367.7    0.03       0  6372.5   0.013       0  6568.8    0.05       0
Bank Sta=4983.5,4988.1
Exp/Cntr=0.3,0.1

Type RM Length L Ch R = 1,2759,726,726,726
BEGIN DESCRIPTION:
LGII4633
END DESCRIPTION:
XS GIS Cut Line= 4
      2421615.48     13543228.19      2421676.01     13541154.97
      2421252.28     13540905.27      2420132.43     13540496.68
#Sta/Elev= 30
  2647.8  310.50  3851.5  307.09  3941.5  306.12  3971.6  306.70  4159.2  304.24
  4390.2  303.01  4585.5  301.99  4641.8  303.59  4671.9  302.24  4681.9  300.94
  4696.6  300.92  4781.1  299.93  4794.7  300.87  4839.2  299.42  4964.5  298.25
  4991.8  296.84  5011.0  293.07  5011.3  292.57  5015.6  293.07  5023.1  294.12
  5028.9  297.91  5036.5  299.75  5059.7  301.59  5077.7  301.64  5242.6  302.65
  5477.0  305.16  5639.8  304.95  5679.2  306.02  6099.5  306.79  6405.8  307.69
#Mann=10,-1,0
  2647.8   0.035       0  4159.2    0.04       0  4390.2    0.05       0
  4585.5   0.013       0  4696.6    0.05       0  5011.0    0.05       0
  5015.6    0.05       0  5077.7    0.12       0  5242.6    0.05       0
  6099.5    0.12       0
Bank Sta=5011,5015.6
Exp/Cntr=0.3,0.1

Type RM Length L Ch R = 1,2033,454,454,454
BEGIN DESCRIPTION:
LGII4632
END DESCRIPTION:
XS GIS Cut Line= 4
      2421660.88     13542933.08      2421744.11     13540708.54
      2421312.82     13540375.61      2420715.84     13539869.32
#Sta/Elev= 30
  2370.2  309.38  3369.0  307.07  3516.4  305.09  3956.2  302.42  4009.7  302.06
  4069.5  303.70  4122.8  301.31  4389.7  298.42  4545.2  299.68  4598.9  301.07
  4715.8  298.45  4826.0  297.42  4854.9  295.64  4925.6  295.97  4951.8  294.28
  4986.5  292.68  5012.1  292.28  5016.5  290.20  5016.8  289.70  5021.3  290.20
  5039.7  290.55  5047.9  293.88  5062.4  294.69  5112.2  295.58  5147.3  298.51
  5243.4  300.31  5480.1  304.08  5502.1  305.52  5756.9  306.21  5923.9  306.16
#Mann=13,-1,0
  2370.2   0.035       0  3516.4    0.04       0  3956.2    0.05       0
  4009.7   0.013       0  4122.8    0.05       0  4545.2    0.12       0
  4715.8    0.05       0  4951.8    0.12       0  4986.5    0.05       0
  5016.5    0.05       0  5021.3    0.05       0  5243.4    0.04       0
  5756.9    0.05       0
Bank Sta=5016.5,5021.3
Exp/Cntr=0.3,0.1

Type RM Length L Ch R = 1,1579,536,536,536
BEGIN DESCRIPTION:
LGII4631
END DESCRIPTION:
XS GIS Cut Line= 3
      2421751.67     13541442.54      2421925.70     13540564.78
      2421139.53     13539400.63
#Sta/Elev= 30
  3499.6  302.70  3574.8  302.46  3646.3  302.54  3711.2  303.61  3763.2  301.42
  3864.1  301.63  4003.5  298.57  4366.9  296.13  4526.4  298.40  4629.1  298.03
  4885.0  295.66  4962.5  291.22  4992.9  290.71  5005.5  288.08  5005.8  287.58
  5010.3  288.08  5013.6  289.28  5021.7  291.23  5049.9  294.25  5106.8  297.66
  5205.1  300.17  5223.7  303.42  5238.6  303.95  5250.9  303.35  5259.6  300.67
  5274.6  298.49  5350.7  298.54  5382.5  302.48  5432.6  303.52  5799.2  305.74
#Mann=13,-1,0
  3499.6    0.04       0  3574.8    0.05       0  3646.3   0.013       0
  3763.2    0.05       0  4526.4    0.12       0  4629.1    0.05       0
  4962.5    0.12       0  5005.5    0.05       0  5010.3    0.12       0
  5013.6    0.04       0  5205.1    0.05       0  5350.7    0.04       0
  5432.6    0.05       0
Bank Sta=5005.5,5010.3
Exp/Cntr=0.3,0.1

Type RM Length L Ch R = 1,1043,0,0,0
BEGIN DESCRIPTION:
LGII4630
END DESCRIPTION:
XS GIS Cut Line= 4
      2421804.63     13541321.47      2422092.17     13540050.25
      2421971.10     13539596.26      2421479.62     13539210.63
#Sta/Elev= 30
  3417.0  302.49  3438.4  302.58  3474.9  302.60  3495.4  303.56  3557.0  302.07
  4059.3  295.36  4182.3  295.66  4356.6  294.50  4570.7  295.55  4719.4  293.75
  4762.9  294.13  4794.8  293.37  4901.7  293.78  4912.1  294.51  4953.5  291.69
  4974.2  288.89  4994.9  288.83  4997.8  285.80  4998.2  285.30  5002.6  285.80
  5005.4  287.82  5015.5  288.80  5071.3  292.46  5115.4  295.18  5139.4  294.59
  5174.1  295.15  5494.3  299.82  5661.1  303.21  5751.0  305.00  5814.9  305.15
#Mann=12,-1,0
  3417.0    0.05       0  3438.4   0.013       0  3557.0    0.05       0
  4719.4    0.12       0  4762.9    0.05       0  4794.8    0.12       0
  4997.8    0.05       0  5002.6    0.12       0  5071.3    0.05       0
  5139.4    0.12       0  5174.1    0.04       0  5661.1    0.05       0
Bank Sta=4997.8,5002.6
Exp/Cntr=0.3,0.1

Chan Stop Cuts=-1