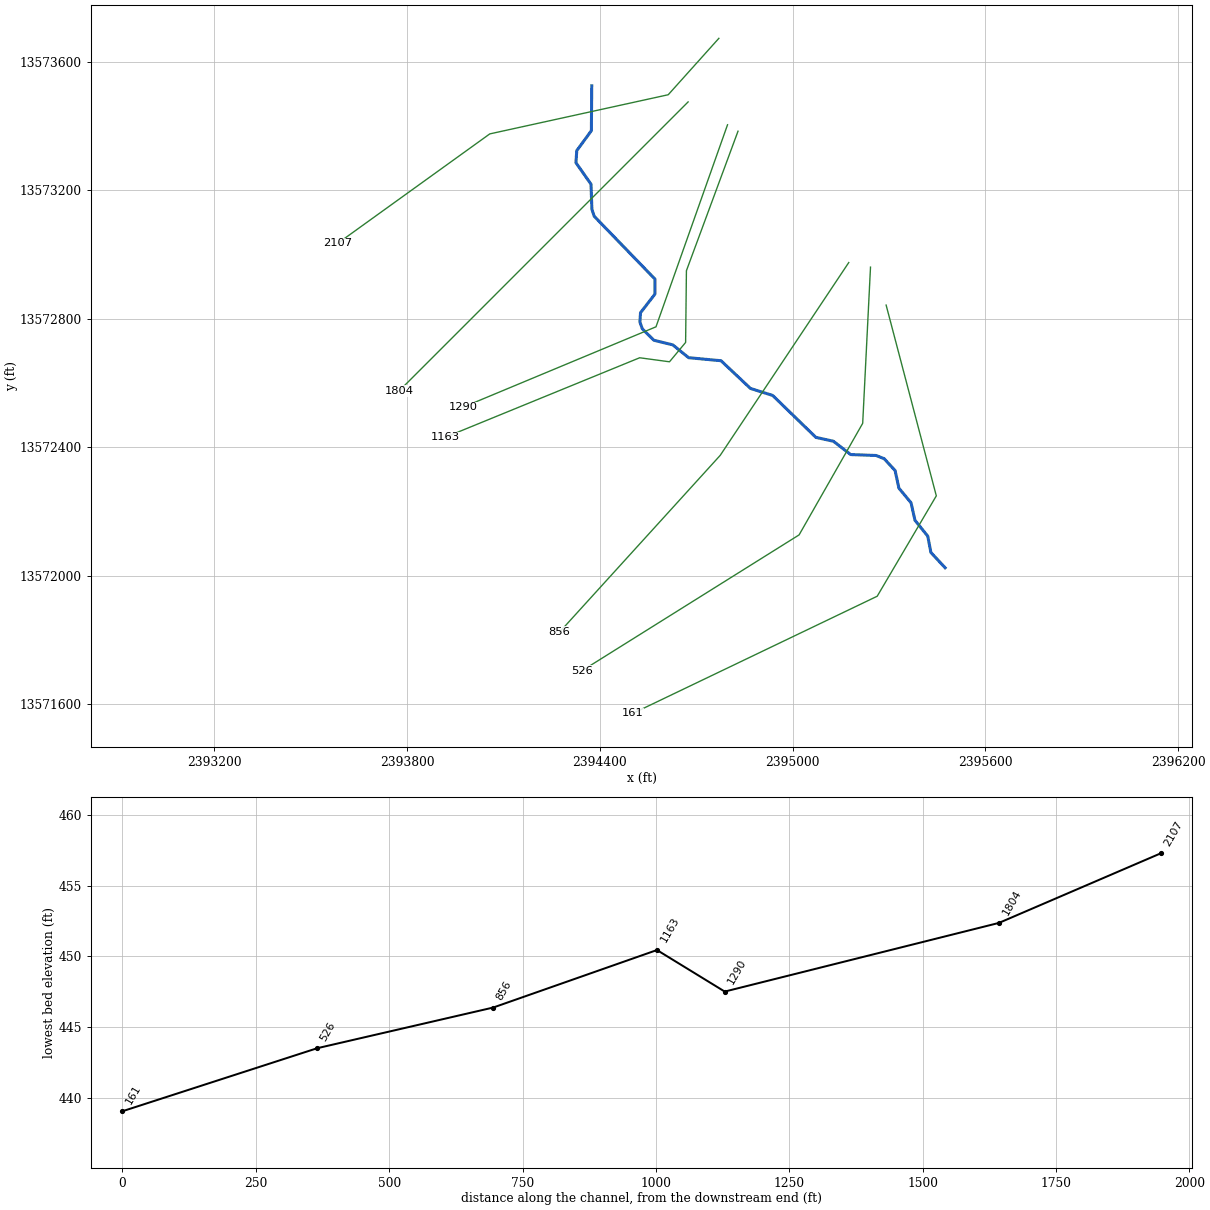
--- LG Stream142.prj (project) ---

Proj Title=LG Stream142 Base Level Engineering
Current Plan=p01
Default Exp/Contr=0.3,0.1
English Units
Geom File=g01
Flow File=f01
Plan File=p01
Y Axis Title=Elevation
X Axis Title(PF)=Main Channel Distance
X Axis Title(XS)=Station
BEGIN DESCRIPTION:
LG Stream142
END DESCRIPTION:
DSS Export Rating Curves= 0
DSS Export Rating Curve Sorted= 0
DSS Export Volume Flow Curves= 0
DXF OffsetX= 0
DXF OffsetY= 0
DXF ScaleX= 1
DXF ScaleY= 10

--- LG Stream142.p01 (plan) ---

Plan Title=Multiple Run
Short Identifier=Multiple
Geom File=g01
Flow File=f01
Subcritical Flow
K Sum by GR= 0
Std Step Tol= 0.01
Critical Tol= 0.01
Num of Std Step Trials= 20
Max Error Tol= 0.3
Flow Tol Ratio= 0.001
Split Flow NTrial= 30
Split Flow Tol= 0.02
Split Flow Ratio= 0.02
Log Output Level= 0
Friction Slope Method= 1
Unsteady Friction Slope Method= 2
Unsteady Bridges Friction Slope Method= 1
Parabolic Critical Depth
Global Vel Dist=  1 , 1 , 1
Global Log Level= 0
CheckData=True
Encroach Param= -1, 0, 0, 0
BEGIN DESCRIPTION:
Multiple Run
END DESCRIPTION:

--- LG Stream142.f01 (steady flow) ---

Flow Title=Multiple
Number of Profiles=7
Profile Names=10-year,25-year,50-year,1pct_min,100-year,1pct_plu,500-year
River Rch & RM= LG Stream142,Reach-1,2107
     426     682     912     593    1183    2359    1967
Boundary for River Rch & Prof#=LG Stream142,Reach-1,1
Up Type=0
Dn Type=3
Dn Slope=0.005
Boundary for River Rch & Prof#=LG Stream142,Reach-1,2
Up Type=0
Dn Type=3
Dn Slope=0.005
Boundary for River Rch & Prof#=LG Stream142,Reach-1,3
Up Type=0
Dn Type=3
Dn Slope=0.005
Boundary for River Rch & Prof#=LG Stream142,Reach-1,4
Up Type=0
Dn Type=3
Dn Slope=0.005
Boundary for River Rch & Prof#=LG Stream142,Reach-1,5
Up Type=0
Dn Type=3
Dn Slope=0.005
Boundary for River Rch & Prof#=LG Stream142,Reach-1,6
Up Type=0
Dn Type=3
Dn Slope=0.005
Boundary for River Rch & Prof#=LG Stream142,Reach-1,7
Up Type=0
Dn Type=3
Dn Slope=0.005

--- LG Stream142.g01 (geometry) ---

Geom Title=Existing Conditions

River Reach=LG Stream142,Reach-1
Reach XY= 30
      2394375.00     13573525.00      2394373.81     13573385.48
      2394328.37     13573323.27      2394325.77     13573285.69
      2394372.62     13573219.03      2394375.52     13573140.22
      2394382.86     13573118.83      2394571.87     13572923.37
      2394571.63     13572876.73      2394526.79     13572818.84
      2394524.91     13572790.21      2394532.37     13572768.66
      2394568.57     13572733.02      2394627.14     13572718.85
      2394676.58     13572678.83      2394777.42     13572669.46
      2394868.96     13572583.18      2394938.21     13572561.37
      2395072.70     13572430.83      2395127.17     13572418.86
      2395180.97     13572377.34      2395259.91     13572374.53
      2395285.11     13572364.62      2395319.28     13572327.58
      2395331.11     13572272.84      2395368.92     13572227.20
      2395381.07     13572172.80      2395420.96     13572123.33
      2395430.67     13572072.64      2395475.00     13572025.00

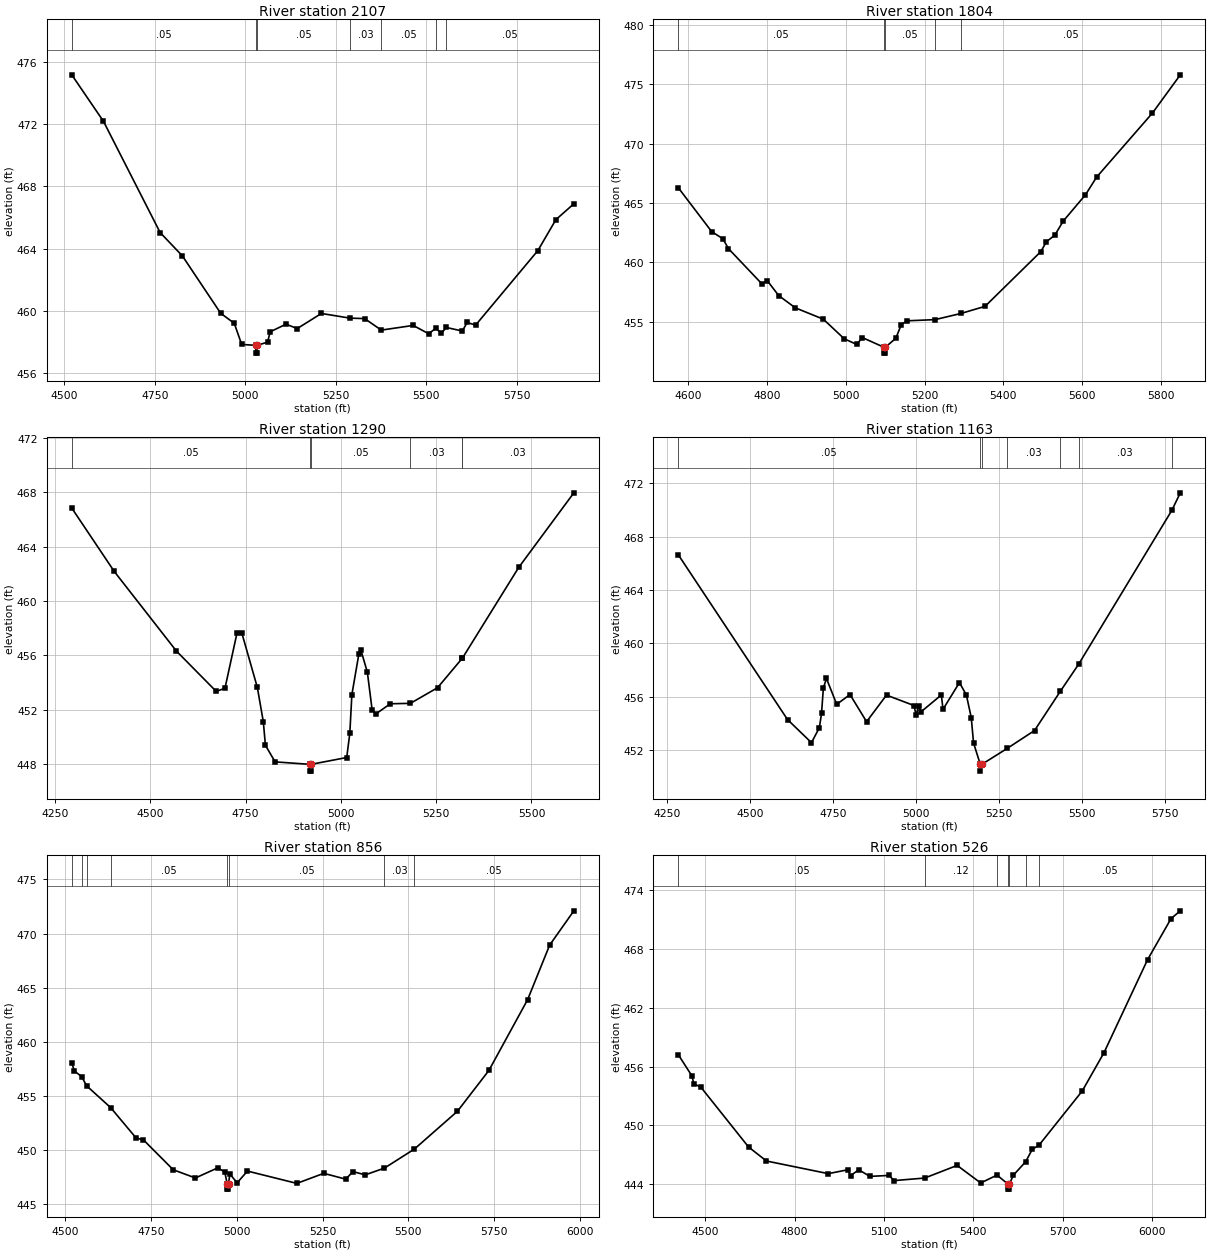
Type RM Length L Ch R = 1,2107,303,303,303
BEGIN DESCRIPTION:
Mapping XS ee0a85bf
END DESCRIPTION:
XS GIS Cut Line= 4
      2394770.67     13573672.84      2394613.03     13573497.28
      2394057.66     13573375.45      2393584.73     13573035.09
#Sta/Elev= 30
  4520.7  475.17  4608.3  472.18  4764.9  465.03  4826.3  463.53  4932.2  459.84
  4969.6  459.20  4990.1  457.84  5029.1  457.78  5029.3  457.28  5032.8  457.28
  5033.1  457.78  5061.8  457.99  5068.8  458.65  5112.6  459.14  5143.7  458.86
  5210.4  459.83  5289.2  459.53  5329.9  459.50  5375.9  458.76  5464.0  459.06
  5506.5  458.53  5526.4  458.87  5542.1  458.57  5555.7  458.93  5599.6  458.70
  5613.3  459.25  5636.5  459.08  5808.4  463.87  5858.3  465.86  5907.9  466.88
#Mann=7,-1,0
  4520.7    0.05       0  5029.1    0.05       0  5033.1    0.05       0
  5289.2    0.03       0  5375.9    0.05       0  5526.4    0.12       0
  5555.7    0.05       0
Bank Sta=5029.1,5033.1
Exp/Cntr=0.3,0.1

Type RM Length L Ch R = 1,1804,514,514,514
BEGIN DESCRIPTION:
THOMAS CREEK 100.0
END DESCRIPTION:
XS GIS Cut Line= 3
      2394674.97     13573474.97      2394375.00     13573175.00
      2393775.03     13572575.03
#Sta/Elev= 30
  4575.7  466.29  4660.5  462.59  4688.8  461.99  4702.9  461.16  4787.8  458.19
  4801.9  458.44  4830.2  457.21  4872.6  456.17  4943.4  455.22  4996.4  453.57
  5028.2  453.09  5042.3  453.67  5096.9  452.86  5097.2  452.36  5100.7  452.36
  5100.9  452.86  5127.2  453.61  5141.3  454.77  5155.5  455.08  5226.5  455.18
  5292.4  455.70  5353.5  456.30  5494.9  460.91  5509.0  461.74  5530.3  462.29
  5551.5  463.47  5608.0  465.69  5636.3  467.18  5777.7  472.57  5848.4  475.79
#Mann=5,-1,0
  4575.7    0.05       0  5096.9    0.05       0  5100.9    0.05       0
  5226.5    0.03       0  5292.4    0.05       0
Bank Sta=5096.9,5100.9
Exp/Cntr=0.3,0.1

Type RM Length L Ch R = 1,1290,127,127,127
BEGIN DESCRIPTION:
THOMAS CREEK 99.0
END DESCRIPTION:
XS GIS Cut Line= 3
      2394797.66     13573403.84      2394575.00     13572775.00
      2393974.99     13572525.00
#Sta/Elev= 30
  4294.1  466.83  4405.6  462.17  4568.7  456.32  4673.0  453.36  4696.0  453.59
  4727.8  457.68  4740.1  457.66  4780.9  453.65  4796.6  451.13  4802.1  449.40
  4827.5  448.18  4918.2  448.00  4918.4  447.50  4921.9  447.50  4922.2  448.00
  5015.4  448.50  5023.5  450.29  5028.9  453.12  5047.3  456.12  5052.7  456.38
  5069.5  454.77  5082.0  452.01  5091.2  451.69  5129.7  452.45  5182.4  452.48
  5253.7  453.63  5318.7  455.80  5319.1  455.81  5466.6  462.47  5611.2  467.95
#Mann=6,-1,0
  4294.1    0.05       0  4918.2    0.05       0  4922.2    0.05       0
  5182.4    0.03       0  5318.7    0.05       0  5319.1    0.03       0
Bank Sta=4918.2,4922.2
Exp/Cntr=0.3,0.1

Type RM Length L Ch R = 1,1163,307,307,307
BEGIN DESCRIPTION:
THOMAS CREEK 98.2
END DESCRIPTION:
XS GIS Cut Line= 6
      2394830.28     13573383.77      2394669.69     13572949.68
      2394667.18     13572726.34      2394616.99     13572666.11
      2394524.14     13572678.66      2393918.45     13572430.88
#Sta/Elev= 30
  4282.7  466.64  4611.9  454.30  4684.1  452.57  4707.9  453.69  4714.5  454.77
  4719.9  456.65  4729.2  457.38  4760.2  455.44  4800.2  456.17  4850.2  454.14
  4910.2  456.13  4992.9  455.35  4999.5  454.63  5007.3  455.34  5013.8  454.87
  5075.4  456.14  5080.5  455.07  5130.0  457.07  5150.9  456.13  5165.5  454.45
  5172.5  452.54  5192.9  450.94  5193.1  450.44  5196.9  450.94  5274.5  452.15
  5356.2  453.48  5433.5  456.40  5488.8  458.43  5769.9  469.96  5795.4  471.27
#Mann=7,-1,0
  4282.7    0.05       0  5192.9    0.05       0  5196.9    0.05       0
  5274.5    0.03       0  5433.5    0.05       0  5488.8    0.03       0
  5769.9    0.05       0
Bank Sta=5192.9,5196.9
Exp/Cntr=0.3,0.1

Type RM Length L Ch R = 1,856,330,330,330
BEGIN DESCRIPTION:
THOMAS CREEK 98.0
END DESCRIPTION:
XS GIS Cut Line= 3
      2395175.00     13572975.01      2394775.00     13572375.00
      2394275.01     13571825.02
#Sta/Elev= 30
  4518.4  458.06  4525.9  457.29  4547.1  456.78  4561.8  455.92  4632.0  453.90
  4706.2  451.09  4727.2  450.93  4814.4  448.16  4879.0  447.40  4943.6  448.33
  4964.6  447.97  4971.6  446.87  4971.9  446.37  4975.4  446.37  4975.6  446.87
  4979.6  447.77  5000.7  446.95  5030.7  448.04  5174.9  446.90  5253.4  447.83
  5317.6  447.29  5338.5  447.99  5374.3  447.69  5430.1  448.31  5518.0  450.08
  5643.3  453.57  5735.2  457.35  5848.0  463.89  5912.2  468.93  5982.8  472.10
#Mann=8,-1,0
  4518.4    0.12       0  4547.1    0.05       0  4561.8    0.12       0
  4632.0    0.05       0  4971.6    0.05       0  4975.6    0.05       0
  5430.1    0.03       0  5518.0    0.05       0
Bank Sta=4971.6,4975.6
Exp/Cntr=0.3,0.1

Type RM Length L Ch R = 1,526,365,365,365
BEGIN DESCRIPTION:
THOMAS CREEK 97.6
END DESCRIPTION:
XS GIS Cut Line= 4
      2395242.70     13572960.75      2395218.39     13572474.62
      2395020.48     13572127.39      2394343.38     13571703.77
#Sta/Elev= 30
  4409.6  457.22  4455.4  455.05  4462.1  454.23  4485.4  453.90  4645.6  447.79
  4705.7  446.36  4913.2  445.07  4978.0  445.46  4988.0  444.87  5015.5  445.46
  5053.0  444.79  5117.8  444.89  5133.6  444.36  5236.6  444.62  5345.7  445.91
  5424.7  444.12  5479.5  444.92  5517.0  443.99  5517.3  443.49  5520.8  443.49
  5521.0  443.99  5534.3  444.91  5575.5  446.28  5598.0  447.56  5620.3  447.97
  5765.4  453.50  5838.5  457.41  5984.7  466.90  6063.7  471.10  6094.7  471.89
#Mann=7,-1,0
  4409.6    0.05       0  5236.6    0.12       0  5479.5    0.05       0
  5517.0    0.05       0  5521.0    0.05       0  5575.5    0.12       0
  5620.3    0.05       0
Bank Sta=5517,5521
Exp/Cntr=0.3,0.1

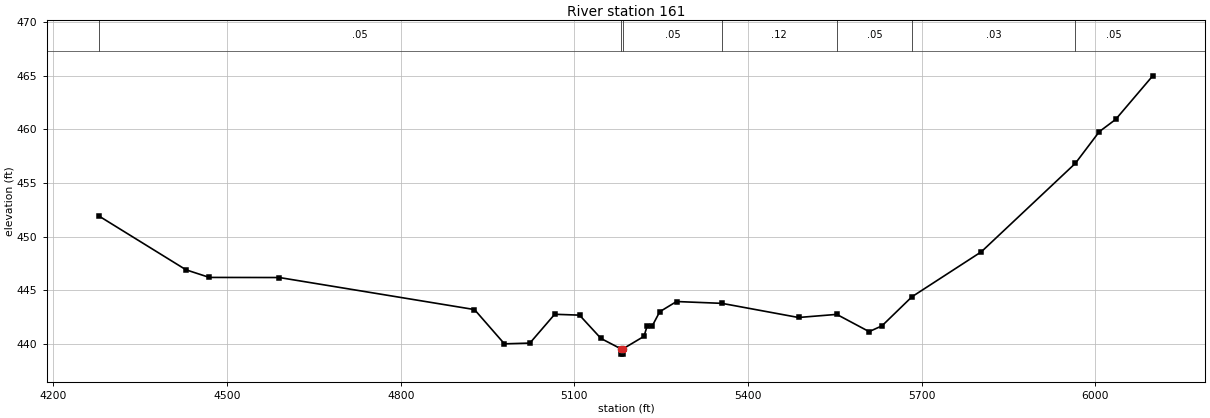
Type RM Length L Ch R = 1,161,0,0,0
BEGIN DESCRIPTION:
THOMAS CREEK 97.3
END DESCRIPTION:
XS GIS Cut Line= 4
      2395291.31     13572842.68      2395447.56     13572248.92
      2395263.53     13571936.42      2394503.15     13571571.85
#Sta/Elev= 30
  4279.3  451.90  4429.1  446.90  4469.4  446.19  4590.4  446.18  4927.4  443.19
  4979.1  439.99  5023.1  440.06  5066.0  442.75  5108.9  442.67  5146.0  440.49
  5180.2  439.53  5180.4  439.03  5183.9  439.03  5184.2  439.53  5220.2  440.69
  5226.0  441.70  5234.4  441.65  5247.5  442.99  5276.5  443.94  5354.9  443.77
  5487.2  442.45  5553.3  442.74  5609.2  441.13  5631.4  441.67  5683.1  444.38
  5803.0  448.58  5965.5  456.84  6006.9  459.80  6035.1  460.94  6099.2  465.01
#Mann=7,-1,0
  4279.3    0.05       0  5180.2    0.05       0  5184.2    0.05       0
  5354.9    0.12       0  5553.3    0.05       0  5683.1    0.03       0
  5965.5    0.05       0
Bank Sta=5180.2,5184.2
Exp/Cntr=0.3,0.1

Chan Stop Cuts=-1