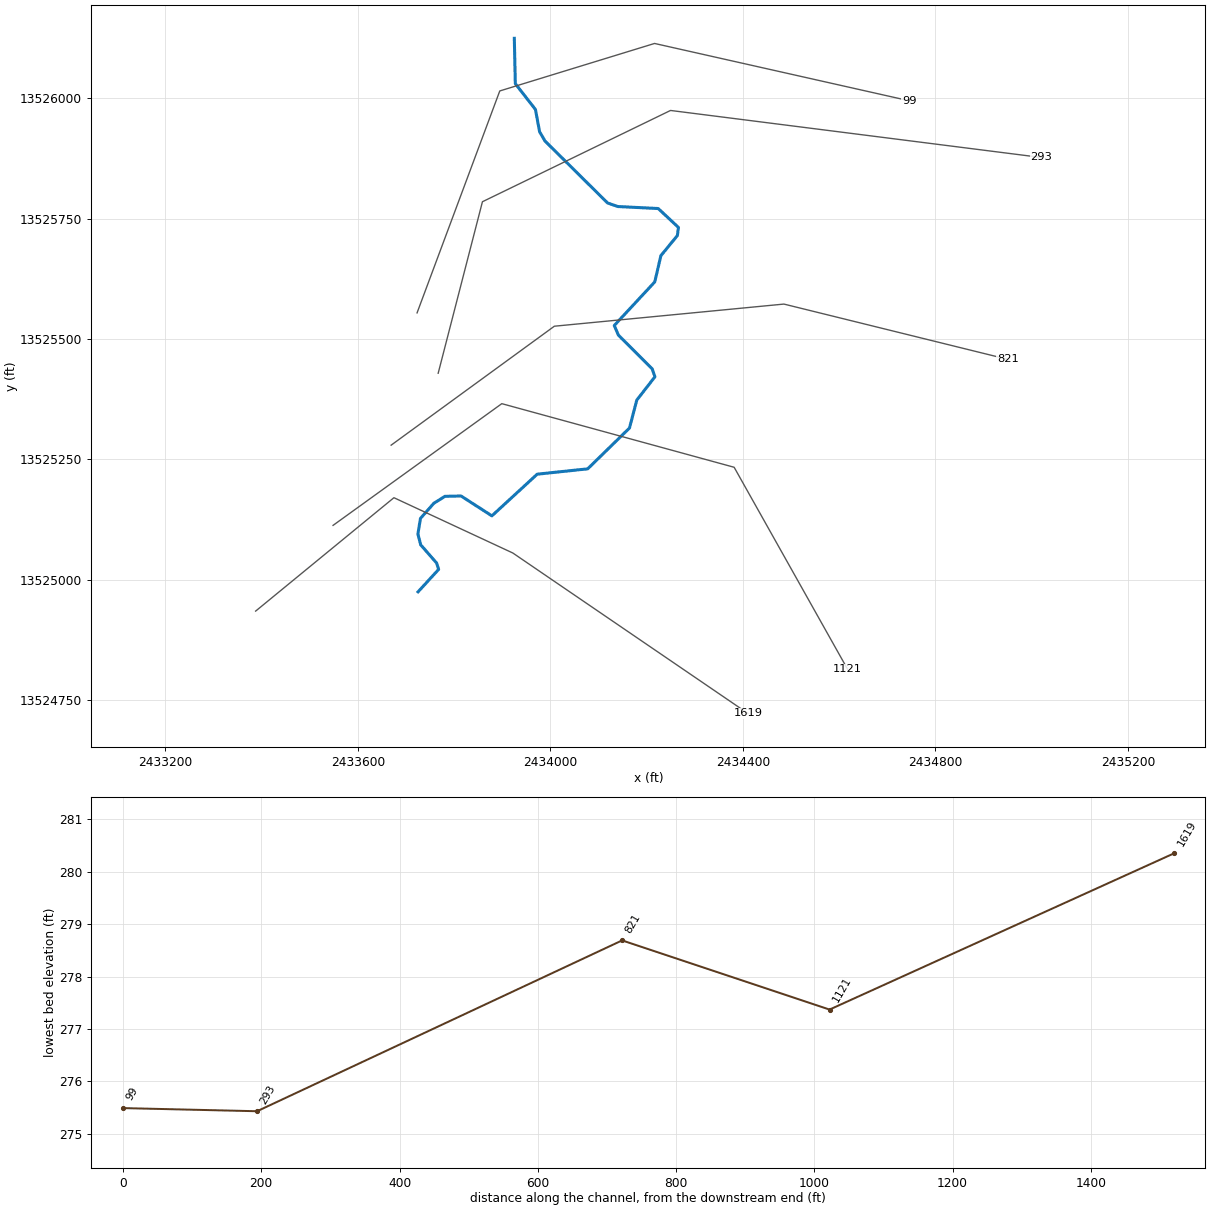
--- LG Stream169.prj (project) ---

Proj Title=LG Stream169 Base Level Engineering
Current Plan=p01
Default Exp/Contr=0.3,0.1
English Units
Geom File=g01
Flow File=f01
Plan File=p01
Y Axis Title=Elevation
X Axis Title(PF)=Main Channel Distance
X Axis Title(XS)=Station
BEGIN DESCRIPTION:
LG Stream169
END DESCRIPTION:
DSS Export Rating Curves= 0
DSS Export Rating Curve Sorted= 0
DSS Export Volume Flow Curves= 0
DXF OffsetX= 0
DXF OffsetY= 0
DXF ScaleX= 1
DXF ScaleY= 10

--- LG Stream169.p01 (plan) ---

Plan Title=Multiple Run
Short Identifier=Multiple
Geom File=g01
Flow File=f01
Subcritical Flow
K Sum by GR= 0
Std Step Tol= 0.01
Critical Tol= 0.01
Num of Std Step Trials= 20
Max Error Tol= 0.3
Flow Tol Ratio= 0.001
Split Flow NTrial= 30
Split Flow Tol= 0.02
Split Flow Ratio= 0.02
Log Output Level= 0
Friction Slope Method= 1
Unsteady Friction Slope Method= 2
Unsteady Bridges Friction Slope Method= 1
Parabolic Critical Depth
Global Vel Dist=  1 , 1 , 1
Global Log Level= 0
CheckData=True
Encroach Param= -1, 0, 0, 0
BEGIN DESCRIPTION:
Multiple Run
END DESCRIPTION:

--- LG Stream169.f01 (steady flow) ---

Flow Title=Multiple
Number of Profiles=7
Profile Names=10-year,25-year,50-year,1pct_min,100-year,1pct_plu,500-year
River Rch & RM= LG Stream169,Reach-1,1619
     770    1273    1739    1150    2294    4578    3955
Boundary for River Rch & Prof#=LG Stream169,Reach-1,1
Up Type=0
Dn Type=3
Dn Slope=0.005
Boundary for River Rch & Prof#=LG Stream169,Reach-1,2
Up Type=0
Dn Type=3
Dn Slope=0.005
Boundary for River Rch & Prof#=LG Stream169,Reach-1,3
Up Type=0
Dn Type=3
Dn Slope=0.005
Boundary for River Rch & Prof#=LG Stream169,Reach-1,4
Up Type=0
Dn Type=3
Dn Slope=0.005
Boundary for River Rch & Prof#=LG Stream169,Reach-1,5
Up Type=0
Dn Type=3
Dn Slope=0.005
Boundary for River Rch & Prof#=LG Stream169,Reach-1,6
Up Type=0
Dn Type=3
Dn Slope=0.005
Boundary for River Rch & Prof#=LG Stream169,Reach-1,7
Up Type=0
Dn Type=3
Dn Slope=0.005

--- LG Stream169.g01 (geometry) ---

Geom Title=Existing Conditions

River Reach=LG Stream169,Reach-1
Reach XY= 30
      2433725.00     13524975.00      2433767.73     13525021.56
      2433763.55     13525034.83      2433730.45     13525072.72
      2433724.66     13525095.25      2433730.00     13525127.62
      2433757.78     13525158.93      2433780.82     13525173.42
      2433814.30     13525174.13      2433878.40     13525132.84
      2433972.57     13525219.45      2434077.44     13525230.52
      2434164.26     13525315.30      2434179.47     13525373.35
      2434217.15     13525421.77      2434211.43     13525438.38
      2434141.27     13525508.33      2434132.62     13525528.33
      2434216.84     13525618.95      2434229.47     13525673.37
      2434263.79     13525715.28      2434266.03     13525732.06
      2434223.98     13525771.39      2434140.23     13525775.53
      2434118.83     13525782.86      2433988.62     13525911.78
      2433977.49     13525931.03      2433968.89     13525977.18
      2433927.07     13526030.86      2433925.00     13526125.00

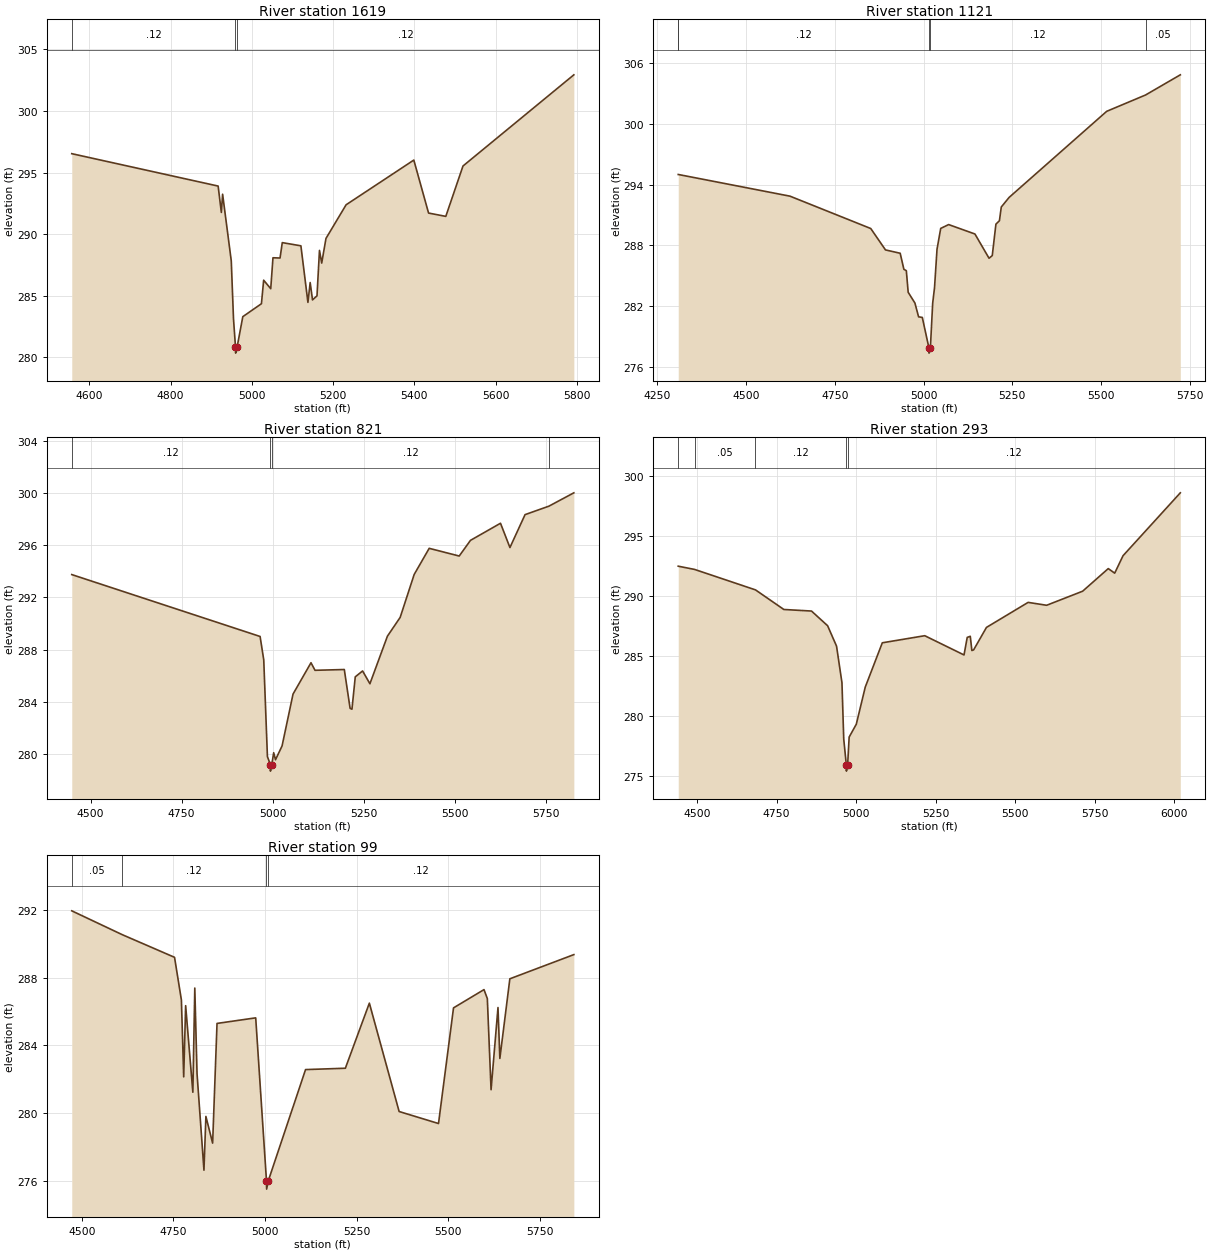
Type RM Length L Ch R = 1,1619,498,498,498
BEGIN DESCRIPTION:
LGII4659
END DESCRIPTION:
XS GIS Cut Line= 4
      2433387.54     13524934.96      2433674.85     13525170.56
      2433921.98     13525055.61      2434410.23     13524722.46
#Sta/Elev= 30
  4557.1  296.54  4917.2  293.91  4925.1  291.77  4928.2  293.25  4949.5  287.84
  4955.0  283.13  4959.9  280.85  4960.2  280.35  4963.9  280.85  4977.9  283.31
  5023.7  284.36  5029.2  286.27  5046.6  285.58  5052.1  288.09  5069.5  288.07
  5075.0  289.32  5120.8  289.06  5138.1  284.47  5143.6  286.08  5149.4  284.67
  5160.4  285.00  5166.5  288.69  5172.0  287.66  5182.5  289.66  5232.0  292.39
  5398.6  296.02  5434.9  291.72  5477.3  291.45  5519.6  295.54  5792.3  302.94
#Mann=3,-1,0
  4557.1    0.12       0  4959.9    0.05       0  4963.9    0.12       0
Bank Sta=4959.9,4963.9
Exp/Cntr=0.3,0.1

Type RM Length L Ch R = 1,1121,300,300,300
BEGIN DESCRIPTION:
LGII4658
END DESCRIPTION:
XS GIS Cut Line= 4
      2433548.39     13525113.07      2433898.99     13525365.96
      2434381.75     13525233.78      2434617.38     13524814.24
#Sta/Elev= 30
  4309.2  294.99  4309.4  294.99  4624.1  292.85  4851.4  289.66  4892.9  287.55
  4934.3  287.22  4944.7  285.64  4951.6  285.50  4956.8  283.37  4975.8  282.31
  4986.1  280.95  4996.6  280.89  5015.3  277.87  5015.5  277.37  5019.3  277.87
  5025.8  282.29  5031.0  283.83  5038.0  287.61  5048.4  289.67  5070.7  290.05
  5144.8  289.12  5184.5  286.73  5193.6  286.99  5203.9  290.09  5213.8  290.43
  5219.0  291.78  5241.1  292.73  5515.9  301.22  5625.3  302.83  5723.2  304.82
#Mann=5,-1,0
  4309.2    0.05       0  4309.4    0.12       0  5015.3    0.05       0
  5019.3    0.12       0  5625.3    0.05       0
Bank Sta=5015.3,5019.3
Exp/Cntr=0.3,0.1

Type RM Length L Ch R = 1,821,528,528,528
BEGIN DESCRIPTION:
LGII4657
END DESCRIPTION:
XS GIS Cut Line= 4
      2433669.07     13525279.73      2434008.19     13525526.88
      2434485.20     13525572.86      2434950.38     13525458.00
#Sta/Elev= 30
  4448.5  293.74  4965.4  289.00  4975.4  287.21  4985.5  279.80  4993.5  279.19
  4993.8  278.69  4997.5  279.19  5002.7  280.10  5007.7  279.56  5025.7  280.62
  5055.8  284.59  5105.1  286.99  5116.1  286.41  5196.5  286.47  5212.4  283.50
  5217.5  283.43  5226.6  285.91  5246.7  286.36  5266.8  285.38  5314.8  289.02
  5349.8  290.46  5388.3  293.75  5429.5  295.75  5511.9  295.16  5542.8  296.36
  5625.2  297.67  5651.1  295.81  5692.6  298.33  5758.2  298.98  5826.5  300.00
#Mann=4,-1,0
  4448.5    0.12       0  4993.5    0.05       0  4997.5    0.12       0
  5758.2    0.05       0
Bank Sta=4993.5,4997.5
Exp/Cntr=0.3,0.1

Type RM Length L Ch R = 1,293,194,194,194
BEGIN DESCRIPTION:
LGII4656
END DESCRIPTION:
XS GIS Cut Line= 4
      2433766.81     13525429.17      2433858.76     13525785.50
      2434249.57     13525975.15      2435019.69     13525877.45
#Sta/Elev= 30
  4440.8  292.47  4492.3  292.20  4683.7  290.50  4772.9  288.87  4859.8  288.74
  4910.5  287.52  4938.6  285.82  4955.6  282.78  4961.2  278.10  4969.4  275.93
  4969.6  275.43  4973.4  275.93  4978.2  278.26  5000.7  279.33  5028.9  282.42
  5082.5  286.10  5215.9  286.69  5339.4  285.09  5349.5  286.55  5359.1  286.64
  5364.1  285.46  5369.6  285.51  5410.0  287.38  5541.0  289.46  5599.2  289.22
  5712.4  290.39  5793.0  292.27  5813.2  291.89  5839.4  293.34  6019.5  298.57
#Mann=5,-1,0
  4440.8    0.12       0  4492.3    0.05       0  4683.7    0.12       0
  4969.4    0.05       0  4973.4    0.12       0
Bank Sta=4969.4,4973.4
Exp/Cntr=0.3,0.1

Type RM Length L Ch R = 1,99,0,0,0
BEGIN DESCRIPTION:
LGII4656a
END DESCRIPTION:
XS GIS Cut Line= 4
      2433722.93     13525554.57      2433894.78     13526015.68
      2434216.35     13526114.36      2434745.45     13525995.27
#Sta/Elev= 30
  4472.3  291.95  4610.1  290.54  4752.9  289.20  4771.6  286.68  4777.9  282.13
  4783.2  286.34  4802.9  281.22  4808.2  287.38  4814.3  282.33  4833.2  276.61
  4838.5  279.79  4856.9  278.21  4868.9  285.29  4974.5  285.62  5003.9  275.99
  5004.3  275.49  5009.0  275.99  5110.6  282.56  5219.3  282.64  5284.8  286.49
  5366.1  280.08  5473.6  279.37  5514.6  286.21  5597.8  287.29  5606.9  286.76
  5617.1  281.37  5636.0  286.23  5641.1  283.22  5668.4  287.93  5843.1  289.36
#Mann=4,-1,0
  4472.3    0.05       0  4610.1    0.12       0  5003.9    0.05       0
  5009.0    0.12       0
Bank Sta=5003.9,5009
Exp/Cntr=0.3,0.1

Chan Stop Cuts=-1