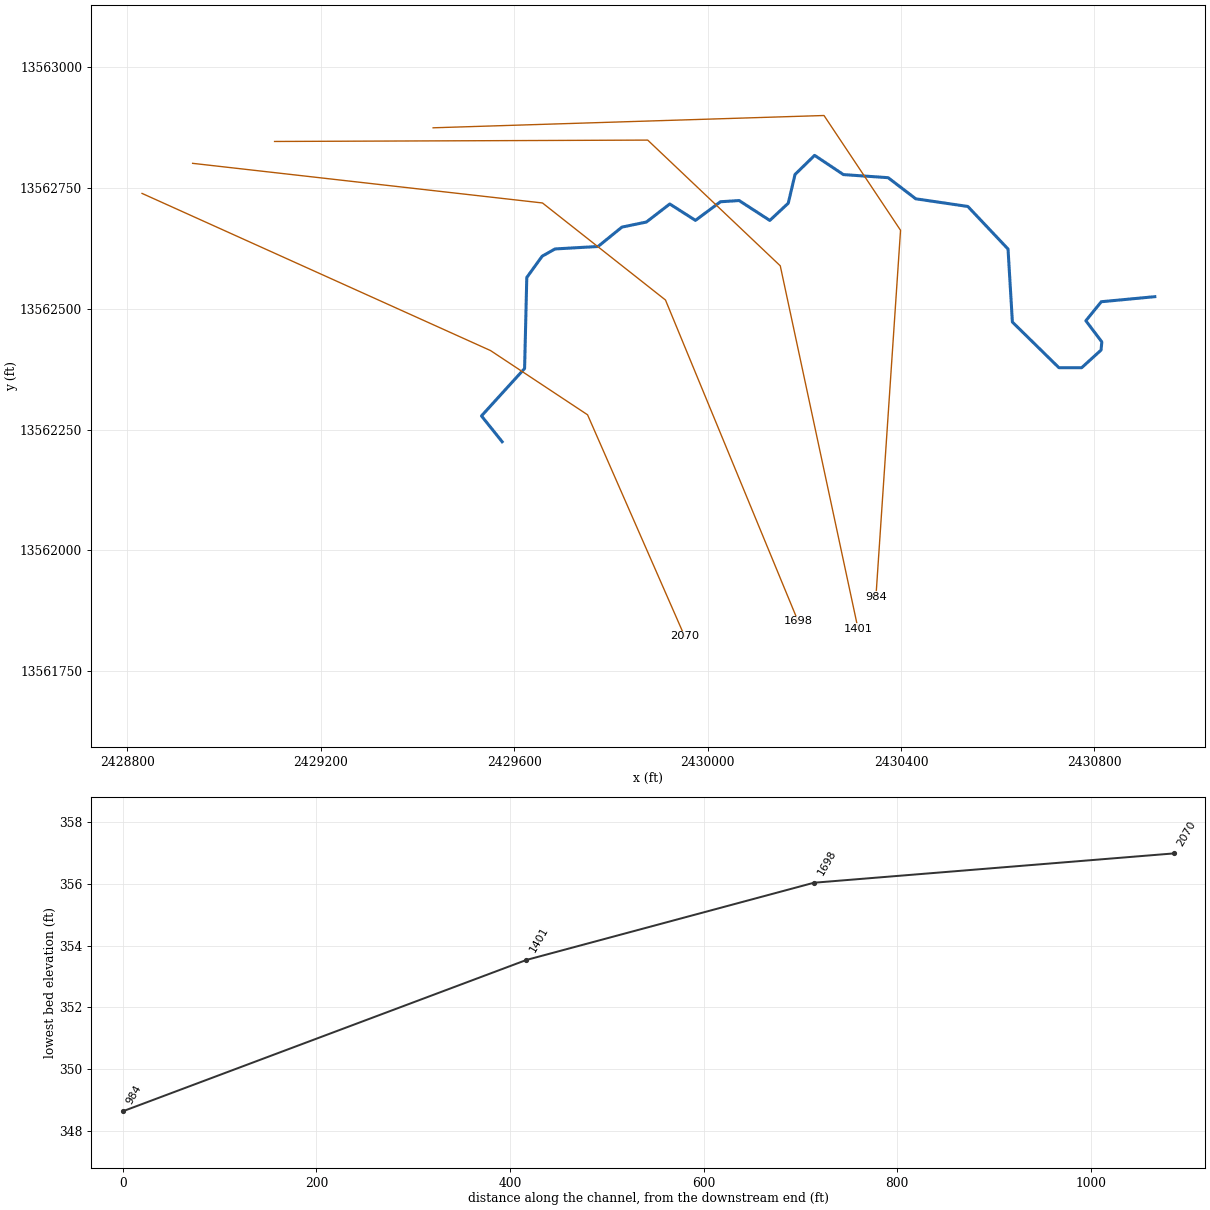
--- LG Stream182.prj (project) ---

Proj Title=LG Stream182 Base Level Engineering
Current Plan=p01
Default Exp/Contr=0.3,0.1
English Units
Geom File=g01
Flow File=f01
Plan File=p01
Y Axis Title=Elevation
X Axis Title(PF)=Main Channel Distance
X Axis Title(XS)=Station
BEGIN DESCRIPTION:
LG Stream182
END DESCRIPTION:
DSS Export Rating Curves= 0
DSS Export Rating Curve Sorted= 0
DSS Export Volume Flow Curves= 0
DXF OffsetX= 0
DXF OffsetY= 0
DXF ScaleX= 1
DXF ScaleY= 10

--- LG Stream182.p01 (plan) ---

Plan Title=Multiple Run
Short Identifier=Multiple
Geom File=g01
Flow File=f01
Subcritical Flow
K Sum by GR= 0
Std Step Tol= 0.01
Critical Tol= 0.01
Num of Std Step Trials= 20
Max Error Tol= 0.3
Flow Tol Ratio= 0.001
Split Flow NTrial= 30
Split Flow Tol= 0.02
Split Flow Ratio= 0.02
Log Output Level= 0
Friction Slope Method= 1
Unsteady Friction Slope Method= 2
Unsteady Bridges Friction Slope Method= 1
Parabolic Critical Depth
Global Vel Dist=  1 , 1 , 1
Global Log Level= 0
CheckData=True
Encroach Param= -1, 0, 0, 0
BEGIN DESCRIPTION:
Multiple Run
END DESCRIPTION:

--- LG Stream182.f01 (steady flow) ---

Flow Title=Multiple
Number of Profiles=7
Profile Names=10-year,25-year,50-year,1pct_min,100-year,1pct_plu,500-year
River Rch & RM= LG Stream182,Reach-1,2070
     383     600     791     506    1010    2015    1628
Boundary for River Rch & Prof#=LG Stream182,Reach-1,1
Up Type=0
Dn Type=3
Dn Slope=0.005
Boundary for River Rch & Prof#=LG Stream182,Reach-1,2
Up Type=0
Dn Type=3
Dn Slope=0.005
Boundary for River Rch & Prof#=LG Stream182,Reach-1,3
Up Type=0
Dn Type=3
Dn Slope=0.005
Boundary for River Rch & Prof#=LG Stream182,Reach-1,4
Up Type=0
Dn Type=3
Dn Slope=0.005
Boundary for River Rch & Prof#=LG Stream182,Reach-1,5
Up Type=0
Dn Type=3
Dn Slope=0.005
Boundary for River Rch & Prof#=LG Stream182,Reach-1,6
Up Type=0
Dn Type=3
Dn Slope=0.005
Boundary for River Rch & Prof#=LG Stream182,Reach-1,7
Up Type=0
Dn Type=3
Dn Slope=0.005

--- LG Stream182.g01 (geometry) ---

Geom Title=Existing Conditions

River Reach=LG Stream182,Reach-1
Reach XY= 30
      2429575.00     13562225.00      2429532.27     13562278.33
      2429621.45     13562376.46      2429625.98     13562564.73
      2429657.78     13562608.74      2429684.46     13562623.76
      2429773.41     13562628.83      2429822.83     13562668.91
      2429873.37     13562679.41      2429921.77     13562716.76
      2429974.92     13562682.83      2430026.65     13562721.37
      2430065.21     13562723.85      2430128.66     13562682.72
      2430166.85     13562718.35      2430180.85     13562777.80
      2430221.33     13562817.31      2430280.88     13562777.56
      2430373.40     13562771.15      2430430.57     13562727.47
      2430538.33     13562711.61      2430621.46     13562623.54
      2430630.46     13562472.53      2430726.70     13562378.09
      2430773.82     13562378.10      2430813.89     13562414.57
      2430815.44     13562431.49      2430782.44     13562475.22
      2430814.38     13562514.57      2430925.00     13562525.00

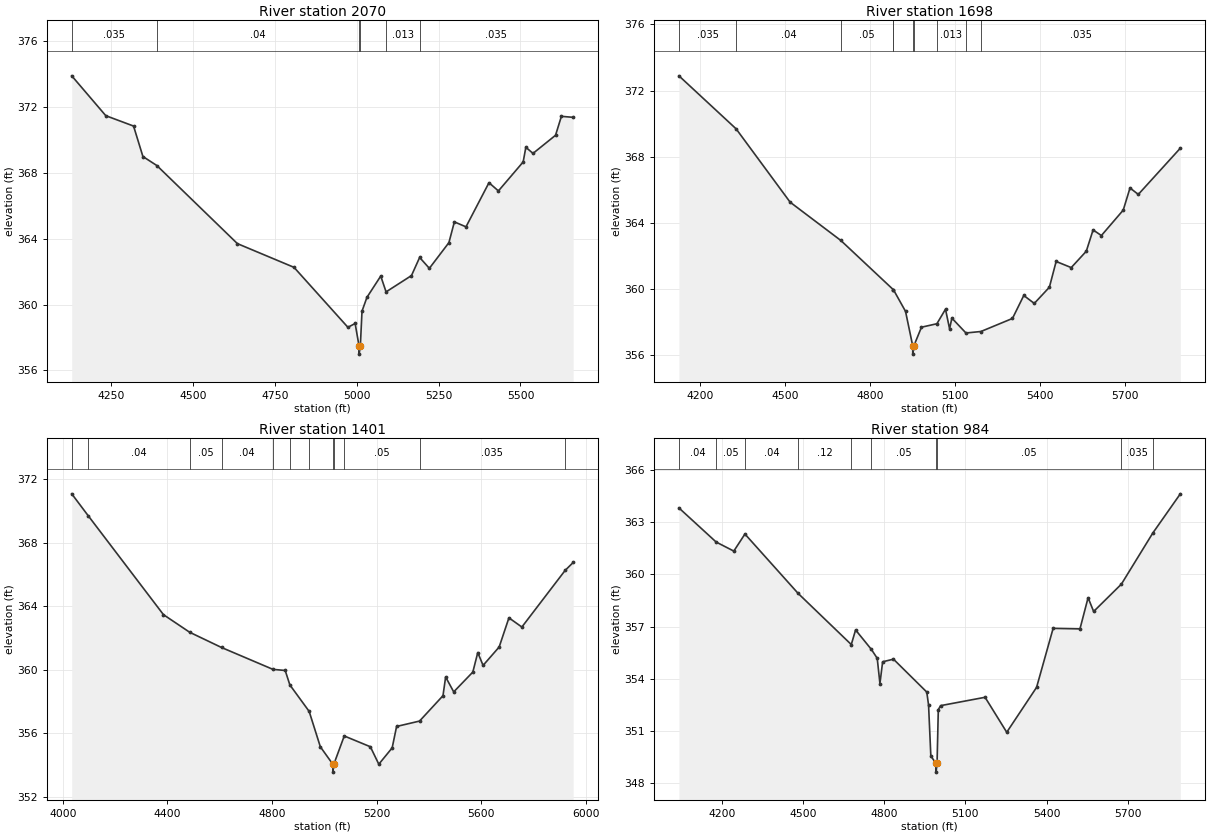
Type RM Length L Ch R = 1,2070,372,372,372
BEGIN DESCRIPTION:
LGII4707
END DESCRIPTION:
XS GIS Cut Line= 4
      2428830.16     13562738.63      2429551.00     13562413.54
      2429751.72     13562280.67      2429952.44     13561822.69
#Sta/Elev= 30
  4129.4  373.89  4233.4  371.47  4318.2  370.84  4346.8  368.99  4389.5  368.44
  4635.4  363.70  4808.3  362.26  4972.9  358.62  4995.0  358.85  5006.9  357.49
  5007.1  356.99  5010.9  357.49  5016.0  359.60  5031.1  360.44  5073.2  361.73
  5089.5  360.77  5167.1  361.76  5192.0  362.86  5221.7  362.20  5281.4  363.76
  5298.1  365.02  5333.6  364.72  5403.8  367.40  5432.6  366.90  5508.2  368.66
  5516.4  369.55  5538.3  369.18  5607.1  370.28  5625.0  371.43  5660.9  371.37
#Mann=6,-1,0
  4129.4   0.035       0  4389.5    0.04       0  5006.9    0.04       0
  5010.9    0.04       0  5089.5   0.013       0  5192.0   0.035       0
Bank Sta=5006.9,5010.9
Exp/Cntr=0.3,0.1

Type RM Length L Ch R = 1,1698,297,297,297
BEGIN DESCRIPTION:
LGII4706
END DESCRIPTION:
XS GIS Cut Line= 4
      2428934.74     13562800.84      2429658.43     13562718.86
      2429912.86     13562518.14      2430187.08     13561853.80
#Sta/Elev= 30
  4126.0  372.89  4328.0  369.68  4518.8  365.24  4698.0  362.92  4883.4  359.94
  4883.7  359.94  4926.4  358.63  4951.8  356.54  4952.0  356.04  4955.8  356.54
  4982.7  357.67  5037.2  357.88  5067.6  358.76  5082.0  357.57  5090.1  358.22
  5139.8  357.32  5192.7  357.41  5304.1  358.20  5344.1  359.59  5381.2  359.11
  5434.5  360.09  5458.4  361.65  5511.7  361.28  5564.9  362.27  5588.9  363.56
  5618.2  363.22  5695.4  364.76  5719.3  366.10  5748.6  365.71  5897.1  368.51
#Mann=10,-1,0
  4126.0   0.035       0  4328.0    0.04       0  4698.0    0.05       0
  4883.4    0.04       0  4883.7    0.05       0  4951.8    0.05       0
  4955.8    0.05       0  5037.2   0.013       0  5139.8    0.05       0
  5192.7   0.035       0
Bank Sta=4951.8,4955.8
Exp/Cntr=0.3,0.1

Type RM Length L Ch R = 1,1401,417,417,417
BEGIN DESCRIPTION:
LGII4705
END DESCRIPTION:
XS GIS Cut Line= 4
      2429104.31     13562846.07      2429876.11     13562848.90
      2430150.33     13562588.81      2430311.13     13561838.39
#Sta/Elev= 30
  4034.1  371.09  4097.0  369.71  4384.8  363.47  4485.1  362.36  4606.8  361.40
  4803.5  360.02  4850.3  359.95  4868.1  359.04  4941.9  357.37  4984.6  355.14
  5032.3  354.04  5032.5  353.54  5036.3  354.04  5076.1  355.82  5175.9  355.14
  5208.2  354.04  5259.3  355.07  5276.2  356.42  5364.0  356.76  5453.6  358.36
  5463.7  359.54  5494.6  358.60  5567.7  359.85  5586.6  361.08  5606.9  360.27
  5668.4  361.43  5705.7  363.27  5755.2  362.69  5920.6  366.26  5951.3  366.76
#Mann=12,-1,0
  4034.1   0.035       0  4097.0    0.04       0  4485.1    0.05       0
  4606.8    0.04       0  4803.5    0.12       0  4868.1    0.04       0
  4941.9   0.013       0  5032.3    0.03       0  5036.3   0.013       0
  5076.1    0.05       0  5364.0   0.035       0  5920.6    0.04       0
Bank Sta=5032.3,5036.3
Exp/Cntr=0.3,0.1

Type RM Length L Ch R = 1,984,0,0,0
BEGIN DESCRIPTION:
LGII4704
END DESCRIPTION:
XS GIS Cut Line= 4
      2429432.23     13562874.34      2430240.79     13562899.78
      2430399.10     13562662.32      2430348.22     13561904.69
#Sta/Elev= 30
  4041.1  363.82  4178.7  361.86  4244.0  361.34  4285.1  362.32  4481.7  358.91
  4678.3  355.97  4694.2  356.81  4752.6  355.69  4774.2  355.18  4784.2  353.73
  4794.2  354.98  4834.3  355.13  4957.4  353.24  4964.0  352.49  4972.4  349.57
  4991.4  349.14  4991.7  348.64  4995.4  349.14  5000.0  352.23  5008.5  352.46
  5172.9  352.94  5253.0  350.93  5363.3  353.51  5424.5  356.90  5523.7  356.87
  5553.7  358.66  5574.3  357.87  5676.8  359.44  5793.1  362.38  5894.8  364.63
#Mann=10,-1,0
  4041.1    0.04       0  4178.7    0.05       0  4285.1    0.04       0
  4481.7    0.12       0  4678.3   0.013       0  4752.6    0.05       0
  4991.4    0.05       0  4995.4    0.05       0  5676.8   0.035       0
  5793.1    0.04       0
Bank Sta=4991.4,4995.4
Exp/Cntr=0.3,0.1

Chan Stop Cuts=-1