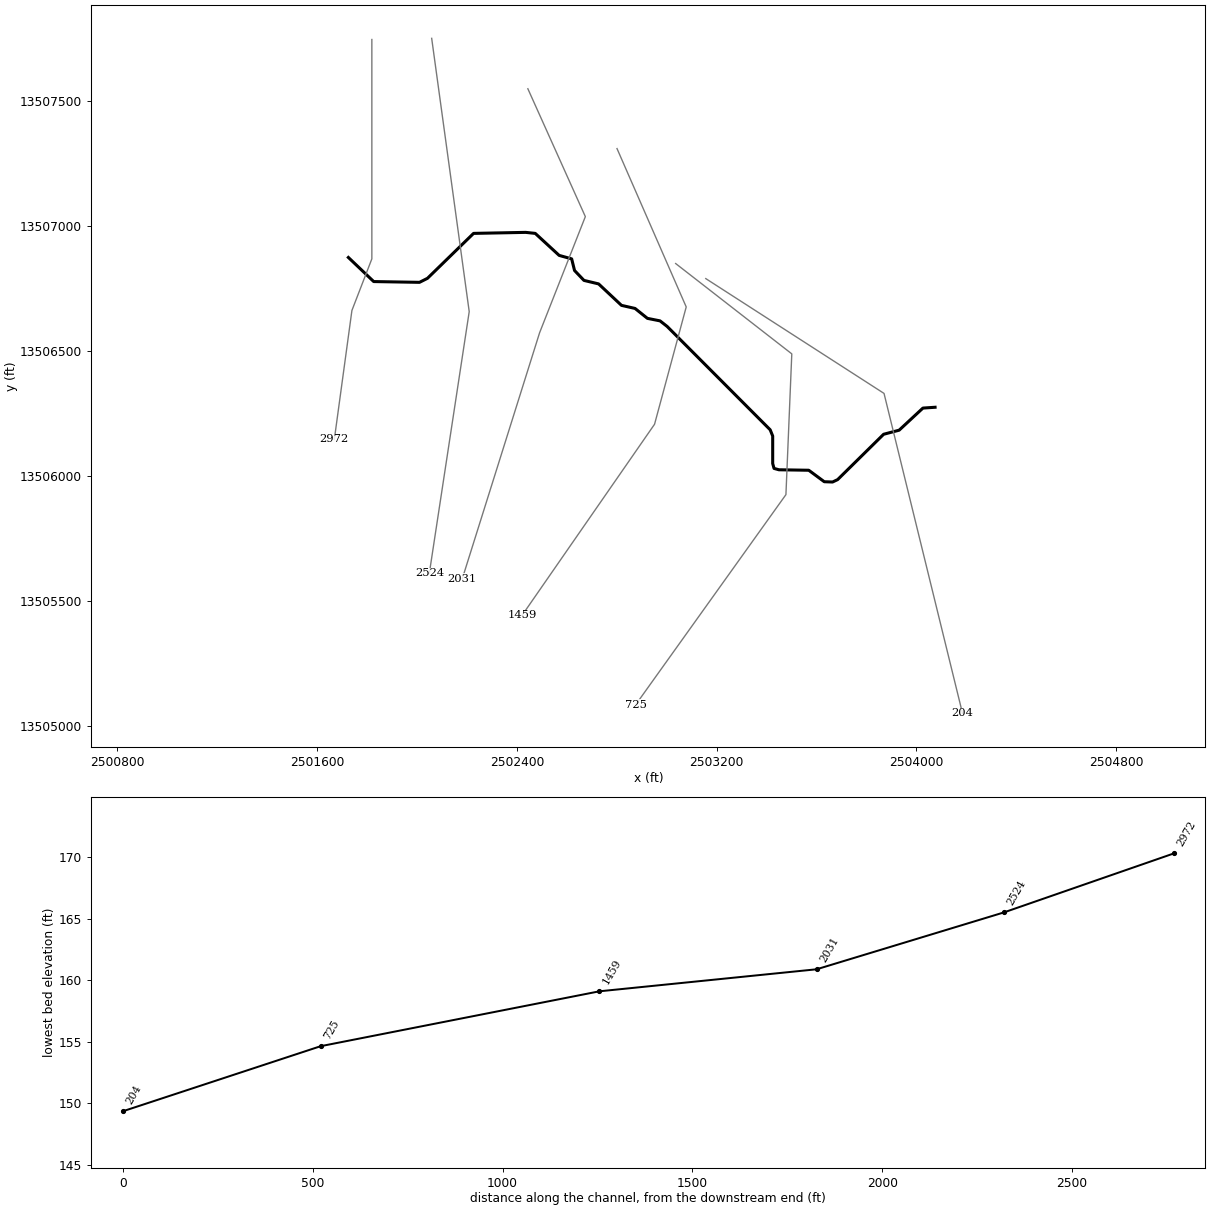
--- LG Stream210.prj (project) ---

Proj Title=LG Stream210 Base Level Engineering
Current Plan=p01
Default Exp/Contr=0.3,0.1
English Units
Geom File=g01
Flow File=f01
Plan File=p01
Y Axis Title=Elevation
X Axis Title(PF)=Main Channel Distance
X Axis Title(XS)=Station
BEGIN DESCRIPTION:
LG Stream210
END DESCRIPTION:
DSS Export Rating Curves= 0
DSS Export Rating Curve Sorted= 0
DSS Export Volume Flow Curves= 0
DXF OffsetX= 0
DXF OffsetY= 0
DXF ScaleX= 1
DXF ScaleY= 10

--- LG Stream210.p01 (plan) ---

Plan Title=Multiple Run
Short Identifier=Multiple
Geom File=g01
Flow File=f01
Subcritical Flow
K Sum by GR= 0
Std Step Tol= 0.01
Critical Tol= 0.01
Num of Std Step Trials= 20
Max Error Tol= 0.3
Flow Tol Ratio= 0.001
Split Flow NTrial= 30
Split Flow Tol= 0.02
Split Flow Ratio= 0.02
Log Output Level= 0
Friction Slope Method= 1
Unsteady Friction Slope Method= 2
Unsteady Bridges Friction Slope Method= 1
Parabolic Critical Depth
Global Vel Dist=  1 , 1 , 1
Global Log Level= 0
CheckData=True
Encroach Param= -1, 0, 0, 0
BEGIN DESCRIPTION:
Multiple Run
END DESCRIPTION:

--- LG Stream210.f01 (steady flow) ---

Flow Title=Multiple
Number of Profiles=7
Profile Names=10-year,25-year,50-year,1pct_min,100-year,1pct_plu,500-year
River Rch & RM= LG Stream210,Reach-1,2972
     667    1075    1444     939    1873    3737    3118
Boundary for River Rch & Prof#=LG Stream210,Reach-1,1
Up Type=0
Dn Type=3
Dn Slope=0.005
Boundary for River Rch & Prof#=LG Stream210,Reach-1,2
Up Type=0
Dn Type=3
Dn Slope=0.005
Boundary for River Rch & Prof#=LG Stream210,Reach-1,3
Up Type=0
Dn Type=3
Dn Slope=0.005
Boundary for River Rch & Prof#=LG Stream210,Reach-1,4
Up Type=0
Dn Type=3
Dn Slope=0.005
Boundary for River Rch & Prof#=LG Stream210,Reach-1,5
Up Type=0
Dn Type=3
Dn Slope=0.005
Boundary for River Rch & Prof#=LG Stream210,Reach-1,6
Up Type=0
Dn Type=3
Dn Slope=0.005
Boundary for River Rch & Prof#=LG Stream210,Reach-1,7
Up Type=0
Dn Type=3
Dn Slope=0.005

--- LG Stream210.g01 (geometry) ---

Geom Title=Existing Conditions

River Reach=LG Stream210,Reach-1
Reach XY= 30
      2501725.00     13506875.00      2501826.44     13506778.48
      2502009.84     13506775.38      2502041.76     13506791.43
      2502226.46     13506971.46      2502435.21     13506975.50
      2502473.53     13506971.45      2502569.26     13506883.30
      2502619.37     13506869.35      2502630.89     13506822.80
      2502668.69     13506783.09      2502727.26     13506769.12
      2502818.95     13506683.16      2502873.27     13506670.81
      2502922.81     13506631.10      2502973.37     13506621.05
      2503001.82     13506598.71      2503414.52     13506184.80
      2503424.60     13506159.82      2503424.61     13506049.59
      2503430.01     13506030.01      2503449.59     13506024.61
      2503569.06     13506022.70      2503631.13     13505976.78
      2503664.38     13505975.60      2503684.68     13505985.19
      2503868.95     13506166.84      2503931.05     13506183.16
      2504026.36     13506271.71      2504075.00     13506275.00

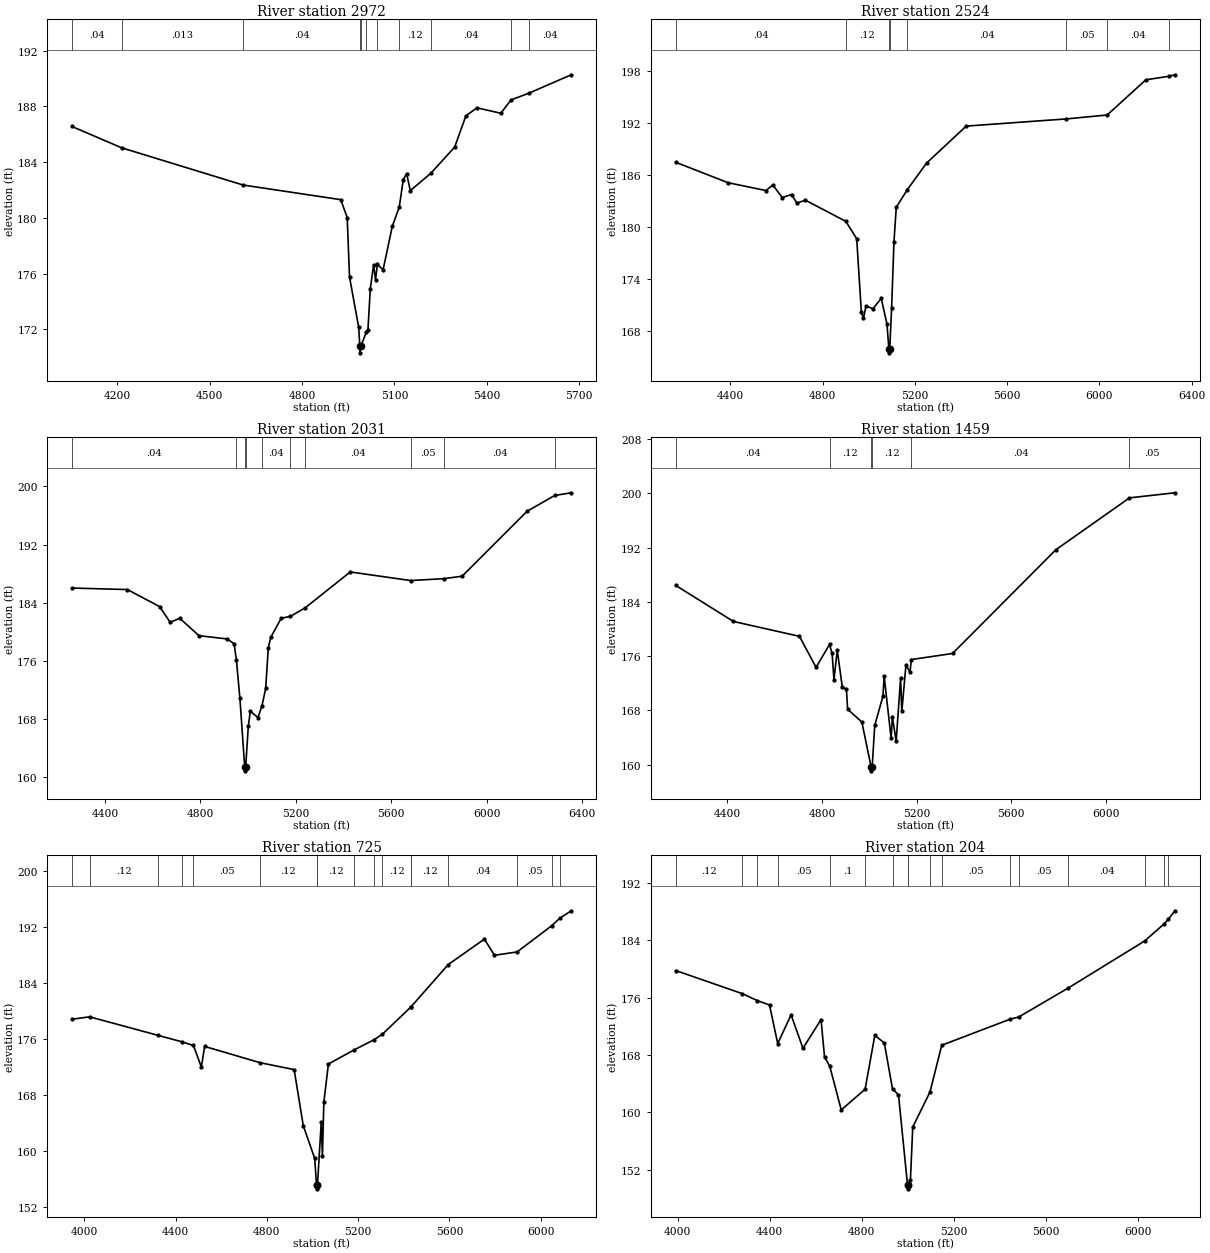
Type RM Length L Ch R = 1,2972,448,448,448
BEGIN DESCRIPTION:
LGII4692
END DESCRIPTION:
XS GIS Cut Line= 4
      2501819.06     13507748.06      2501819.06     13506869.47
      2501739.19     13506662.74      2501668.72     13506145.93
#Sta/Elev= 30
  4052.3  186.55  4213.9  185.02  4608.3  182.35  4925.4  181.30  4946.4  180.02
  4953.9  175.76  4983.8  172.13  4987.3  170.81  4987.5  170.31  4991.3  170.81
  5008.7  171.81  5013.8  171.96  5021.4  174.89  5032.2  176.63  5038.4  175.54
  5044.4  176.65  5063.0  176.27  5092.9  179.39  5115.6  180.78  5128.6  182.74
  5139.4  183.17  5151.4  181.95  5217.9  183.19  5295.5  185.07  5331.9  187.31
  5367.9  187.89  5445.3  187.50  5478.8  188.46  5536.8  188.94  5674.1  190.26
#Mann=11,-1,0
  4052.3    0.04       0  4213.9   0.013       0  4608.3    0.04       0
  4987.3    0.04       0  4991.3    0.04       0  5008.7   0.013       0
  5044.4    0.04       0  5115.6    0.12       0  5217.9    0.04       0
  5478.8    0.12       0  5536.8    0.04       0
Bank Sta=4987.3,4991.3
Exp/Cntr=0.3,0.1

Type RM Length L Ch R = 1,2524,493,493,493
BEGIN DESCRIPTION:
LGII4691
END DESCRIPTION:
XS GIS Cut Line= 3
      2502058.69     13507752.72      2502209.03     13506658.04
      2502049.29     13505610.31
#Sta/Elev= 30
  4162.5  187.49  4390.0  185.13  4553.9  184.23  4584.1  184.87  4624.5  183.42
  4664.9  183.77  4688.4  182.79  4725.5  183.11  4900.6  180.67  4947.5  178.67
  4967.7  170.21  4976.7  169.51  4987.9  170.89  5018.2  170.61  5053.8  171.79
  5078.7  168.85  5086.8  166.01  5087.1  165.51  5090.8  166.01  5098.9  170.66
  5109.0  178.29  5119.1  182.30  5167.2  184.34  5250.3  187.39  5422.3  191.66
  5856.5  192.49  6033.5  192.94  6201.2  197.00  6301.8  197.41  6327.3  197.58
#Mann=8,-1,0
  4162.5    0.04       0  4900.6    0.12       0  5086.8    0.05       0
  5090.8    0.12       0  5167.2    0.04       0  5856.5    0.05       0
  6033.5    0.04       0  6301.8    0.05       0
Bank Sta=5086.8,5090.8
Exp/Cntr=0.3,0.1

Type RM Length L Ch R = 1,2031,572,572,572
BEGIN DESCRIPTION:
LGII4690
END DESCRIPTION:
XS GIS Cut Line= 4
      2502443.94     13507550.76      2502674.18     13507038.61
      2502490.94     13506573.47      2502181.35     13505588.42
#Sta/Elev= 30
  4261.3  186.03  4494.0  185.82  4629.4  183.47  4673.3  181.31  4713.4  181.87
  4793.9  179.48  4911.7  179.03  4941.4  178.38  4951.2  176.09  4965.8  170.84
  4985.9  161.39  4986.2  160.89  4989.9  161.39  5001.0  167.05  5009.4  169.07
  5041.7  168.22  5058.4  169.85  5073.9  172.24  5084.9  177.84  5095.4  179.27
  5139.0  181.88  5177.7  182.13  5240.2  183.33  5428.6  188.24  5681.9  187.06
  5822.1  187.32  5897.9  187.66  6170.2  196.59  6286.1  198.76  6355.3  199.13
#Mann=10,-1,0
  4261.3    0.04       0  4951.2    0.12       0  4985.9    0.05       0
  4989.9    0.12       0  5058.4    0.04       0  5177.7    0.05       0
  5240.2    0.04       0  5681.9    0.05       0  5822.1    0.04       0
  6286.1    0.05       0
Bank Sta=4985.9,4989.9
Exp/Cntr=0.3,0.1

Type RM Length L Ch R = 1,1459,734,734,734
BEGIN DESCRIPTION:
LGII4689
END DESCRIPTION:
XS GIS Cut Line= 4
      2502801.03     13507311.12      2503078.24     13506676.83
      2502951.38     13506206.99      2502420.44     13505441.11
#Sta/Elev= 30
  4181.4  186.43  4425.6  181.11  4704.8  178.92  4775.0  174.35  4832.2  177.72
  4842.9  176.39  4850.7  172.54  4864.7  176.86  4885.9  171.45  4903.3  171.13
  4908.5  168.18  4968.7  166.29  5008.2  159.60  5008.4  159.10  5012.2  159.60
  5023.0  165.79  5057.7  170.08  5062.9  173.03  5092.4  163.89  5097.6  167.02
  5113.7  163.47  5132.3  172.72  5137.5  167.86  5155.2  174.74  5172.2  173.59
  5177.8  175.50  5352.0  176.39  5789.3  191.69  6100.1  199.32  6292.2  200.07
#Mann=6,-1,0
  4181.4    0.04       0  4832.2    0.12       0  5008.2    0.05       0
  5012.2    0.12       0  5177.8    0.04       0  6100.1    0.05       0
Bank Sta=5008.2,5012.2
Exp/Cntr=0.3,0.1

Type RM Length L Ch R = 1,725,521,521,521
BEGIN DESCRIPTION:
LGII4688
END DESCRIPTION:
XS GIS Cut Line= 4
      2503035.92     13506850.70      2503501.10     13506488.89
      2503477.61     13505925.08      2502876.23     13505084.10
#Sta/Elev= 30
  3946.0  178.84  4023.6  179.18  4325.2  176.52  4426.3  175.63  4478.5  175.09
  4512.9  172.01  4527.4  174.96  4770.9  172.63  4919.5  171.65  4959.6  163.64
  5009.6  158.98  5017.6  155.14  5017.9  154.64  5021.6  155.14  5038.4  164.18
  5043.4  159.31  5049.7  167.01  5069.7  172.45  5182.9  174.47  5269.5  175.91
  5306.6  176.71  5430.6  180.57  5431.6  180.61  5594.7  186.64  5753.1  190.27
  5797.3  187.96  5896.5  188.44  6048.9  192.20  6082.5  193.22  6133.5  194.31
#Mann=17,-1,0
  3946.0    0.04       0  4023.6    0.12       0  4325.2    0.05       0
  4426.3    0.12       0  4478.5    0.05       0  4770.9    0.12       0
  5017.6    0.05       0  5021.6    0.12       0  5182.9    0.05       0
  5269.5    0.04       0  5306.6    0.12       0  5430.6    0.05       0
  5431.6    0.12       0  5594.7    0.04       0  5896.5    0.05       0
  6048.9    0.12       0  6082.5    0.05       0
Bank Sta=5017.6,5021.6
Exp/Cntr=0.3,0.1

Type RM Length L Ch R = 1,204,0,0,0
BEGIN DESCRIPTION:
LGII4687
END DESCRIPTION:
XS GIS Cut Line= 3
      2503156.53     13506790.37      2503870.54     13506330.49
      2504184.90     13505048.88
#Sta/Elev= 30
  3991.4  179.76  4280.7  176.54  4345.4  175.58  4399.2  174.96  4434.7  169.59
  4492.9  173.58  4544.4  168.93  4623.0  172.93  4638.1  167.74  4660.9  166.42
  4710.8  160.34  4814.4  163.22  4856.6  170.73  4897.8  169.67  4933.5  163.26
  4959.4  162.46  4998.8  149.85  4999.0  149.35  5002.8  149.85  5011.3  150.57
  5021.4  157.96  5096.3  162.84  5147.3  169.35  5446.0  173.00  5481.5  173.28
  5697.9  177.34  6029.0  183.88  6113.8  186.27  6130.7  186.87  6160.3  188.08
#Mann=17,-1,0
  3991.4    0.12       0  4280.7    0.05       0  4345.4    0.12       0
  4434.7    0.05       0  4660.9     0.1       0  4814.4    0.12       0
  4933.5     0.1       0  4998.8    0.05       0  5002.8     0.1       0
  5096.3    0.12       0  5147.3    0.05       0  5446.0    0.04       0
  5481.5    0.05       0  5697.9    0.04       0  6029.0    0.03       0
  6113.8    0.04       0  6130.7    0.05       0
Bank Sta=4998.8,5002.8
Exp/Cntr=0.3,0.1

Chan Stop Cuts=-1