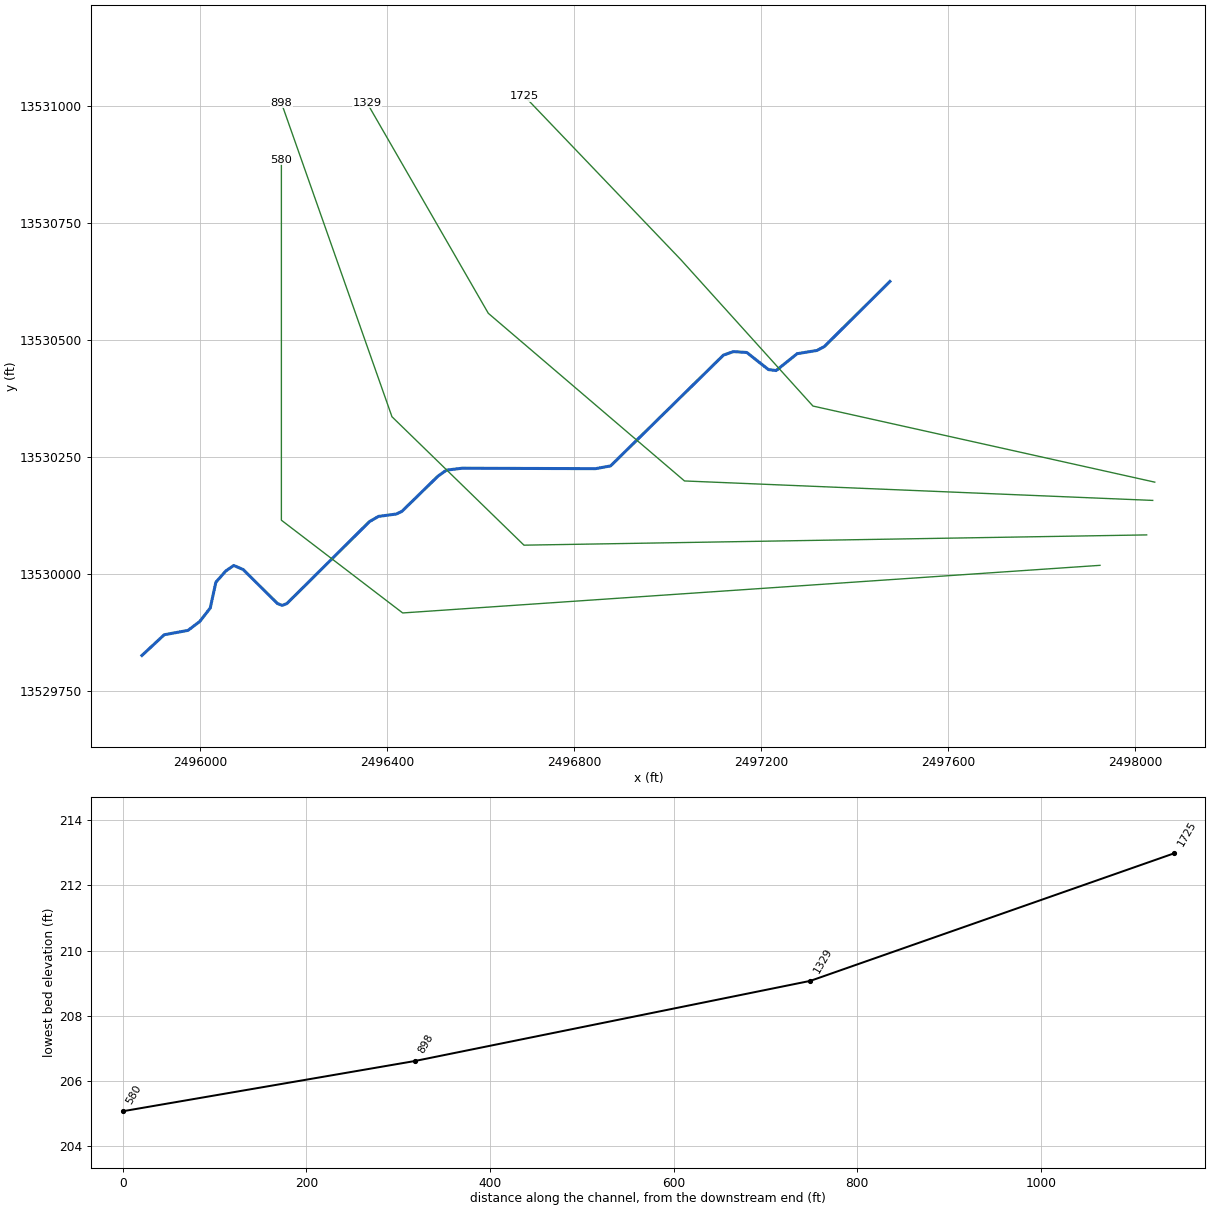
--- LG Stream235.prj (project) ---

Proj Title=LG Stream235 Base Level Engineering
Current Plan=p01
Default Exp/Contr=0.3,0.1
English Units
Geom File=g01
Flow File=f01
Plan File=p01
Y Axis Title=Elevation
X Axis Title(PF)=Main Channel Distance
X Axis Title(XS)=Station
BEGIN DESCRIPTION:
LG Stream235
END DESCRIPTION:
DSS Export Rating Curves= 0
DSS Export Rating Curve Sorted= 0
DSS Export Volume Flow Curves= 0
DXF OffsetX= 0
DXF OffsetY= 0
DXF ScaleX= 1
DXF ScaleY= 10

--- LG Stream235.p01 (plan) ---

Plan Title=Multiple Run
Short Identifier=Multiple
Geom File=g01
Flow File=f01
Subcritical Flow
K Sum by GR= 0
Std Step Tol= 0.01
Critical Tol= 0.01
Num of Std Step Trials= 20
Max Error Tol= 0.3
Flow Tol Ratio= 0.001
Split Flow NTrial= 30
Split Flow Tol= 0.02
Split Flow Ratio= 0.02
Log Output Level= 0
Friction Slope Method= 1
Unsteady Friction Slope Method= 2
Unsteady Bridges Friction Slope Method= 1
Parabolic Critical Depth
Global Vel Dist=  1 , 1 , 1
Global Log Level= 0
CheckData=True
Encroach Param= -1, 0, 0, 0
BEGIN DESCRIPTION:
Multiple Run
END DESCRIPTION:

--- LG Stream235.f01 (steady flow) ---

Flow Title=Multiple
Number of Profiles=7
Profile Names=10-year,25-year,50-year,1pct_min,100-year,1pct_plu,500-year
River Rch & RM= LG Stream235,Reach-1,1725
     765    1245    1682    1100    2195    4379    3696
River Rch & RM= LG Stream235,Reach-1,898
     786    1282    1735    1136    2266    4521    3825
Boundary for River Rch & Prof#=LG Stream235,Reach-1,1
Up Type=0
Dn Type=3
Dn Slope=0.005
Boundary for River Rch & Prof#=LG Stream235,Reach-1,2
Up Type=0
Dn Type=3
Dn Slope=0.005
Boundary for River Rch & Prof#=LG Stream235,Reach-1,3
Up Type=0
Dn Type=3
Dn Slope=0.005
Boundary for River Rch & Prof#=LG Stream235,Reach-1,4
Up Type=0
Dn Type=3
Dn Slope=0.005
Boundary for River Rch & Prof#=LG Stream235,Reach-1,5
Up Type=0
Dn Type=3
Dn Slope=0.005
Boundary for River Rch & Prof#=LG Stream235,Reach-1,6
Up Type=0
Dn Type=3
Dn Slope=0.005
Boundary for River Rch & Prof#=LG Stream235,Reach-1,7
Up Type=0
Dn Type=3
Dn Slope=0.005

--- LG Stream235.g01 (geometry) ---

Geom Title=Existing Conditions

River Reach=LG Stream235,Reach-1
Reach XY= 30
      2497475.00     13530625.00      2497334.68     13530485.74
      2497318.95     13530477.46      2497276.65     13530470.55
      2497231.61     13530434.43      2497215.08     13530436.52
      2497168.95     13530473.02      2497140.36     13530474.99
      2497118.95     13530467.50      2496877.45     13530230.46
      2496845.18     13530224.57      2496559.80     13530225.49
      2496526.47     13530221.45      2496508.25     13530208.54
      2496431.04     13530133.18      2496418.95     13530127.54
      2496381.05     13530122.47      2496361.79     13530111.37
      2496185.00     13529935.96      2496175.00     13529932.10
      2496165.00     13529936.00      2496091.58     13530008.77
      2496071.42     13530017.50      2496054.62     13530005.94
      2496033.17     13529981.69      2496021.12     13529926.50
      2495998.86     13529897.85      2495973.66     13529878.71
      2495922.68     13529869.28      2495875.00     13529825.00

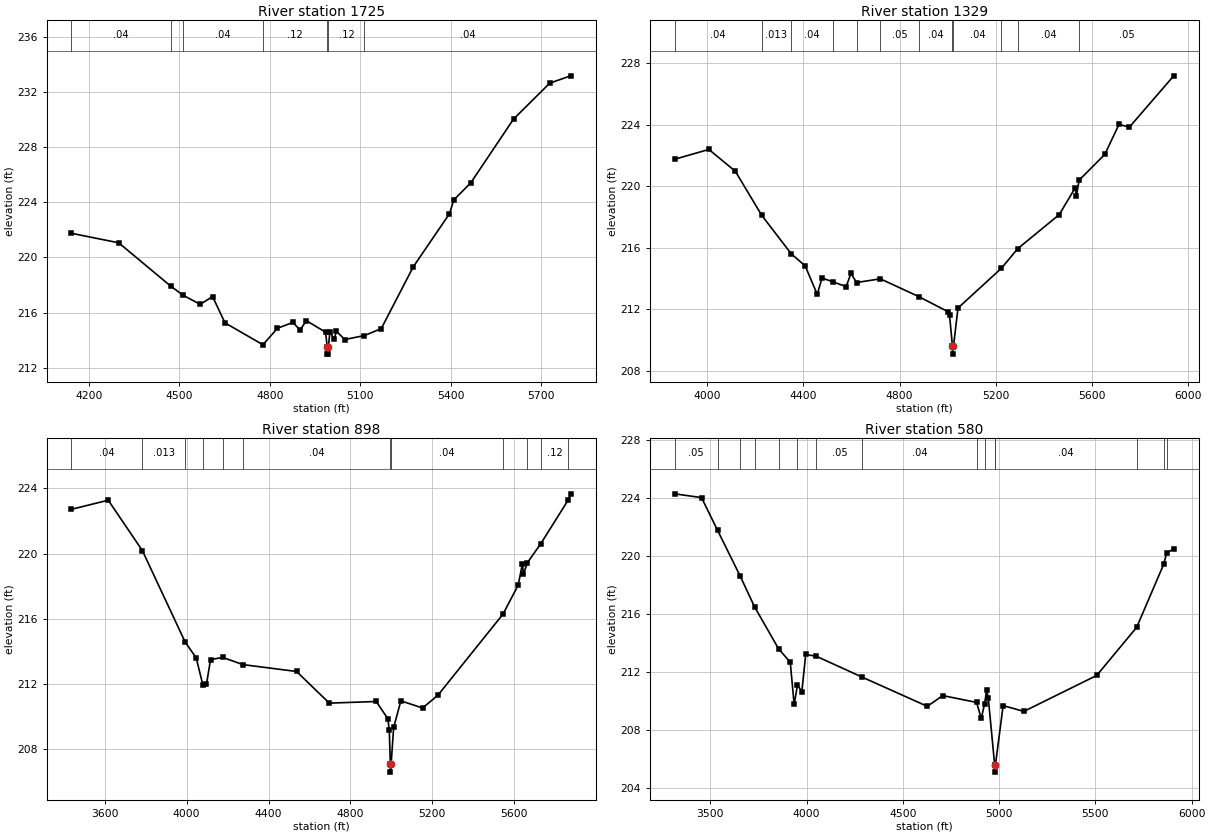
Type RM Length L Ch R = 1,1725,396,396,396
BEGIN DESCRIPTION:
LGII4575
END DESCRIPTION:
XS GIS Cut Line= 4
      2498041.51     13530195.73      2497310.29     13530358.52
      2497027.95     13530671.38      2496693.36     13531021.18
#Sta/Elev= 30
  4142.9  221.75  4299.4  221.06  4472.6  217.90  4514.1  217.24  4569.6  216.59
  4610.6  217.16  4651.6  215.25  4777.6  213.66  4825.7  214.86  4876.9  215.28
  4900.7  214.73  4921.6  215.41  4985.2  214.57  4990.6  213.48  4990.9  212.98
  4994.4  212.98  4994.6  213.48  4999.4  214.62  5013.6  214.05  5021.0  214.64
  5048.9  214.04  5114.1  214.33  5169.7  214.83  5275.9  219.32  5395.9  223.17
  5410.1  224.17  5466.7  225.42  5608.2  230.04  5728.4  232.65  5797.5  233.18
#Mann=7,-1,0
  4142.9    0.04       0  4472.6   0.013       0  4514.1    0.04       0
  4777.6    0.12       0  4990.6    0.05       0  4994.6    0.12       0
  5114.1    0.04       0
Bank Sta=4990.6,4994.6
Exp/Cntr=0.3,0.1

Type RM Length L Ch R = 1,1329,431,431,431
BEGIN DESCRIPTION:
LGII4574
END DESCRIPTION:
XS GIS Cut Line= 4
      2498037.12     13530156.67      2497035.58     13530198.27
      2496615.88     13530556.92      2496356.43     13531007.14
#Sta/Elev= 30
  3864.9  221.75  4007.1  222.39  4117.2  220.97  4227.0  218.10  4349.5  215.60
  4407.5  214.81  4457.5  212.96  4477.5  214.02  4522.6  213.78  4577.6  213.46
  4597.6  214.32  4621.1  213.73  4719.7  213.97  4880.1  212.81  4999.6  211.84
  5007.3  211.60  5019.6  209.57  5019.9  209.07  5023.6  209.57  5042.5  212.07
  5223.0  214.66  5290.6  215.93  5463.3  218.15  5529.0  219.88  5534.8  219.39
  5545.8  220.39  5652.6  222.07  5711.5  224.02  5754.6  223.84  5939.0  227.18
#Mann=12,-1,0
  3864.9    0.04       0  4227.0   0.013       0  4349.5    0.04       0
  4522.6    0.12       0  4621.1    0.04       0  4719.7    0.05       0
  4880.1    0.04       0  5019.6    0.04       0  5023.6    0.04       0
  5223.0    0.05       0  5290.6    0.04       0  5545.8    0.05       0
Bank Sta=5019.6,5023.6
Exp/Cntr=0.3,0.1

Type RM Length L Ch R = 1,898,318,318,318
BEGIN DESCRIPTION:
LGII4573
END DESCRIPTION:
XS GIS Cut Line= 4
      2498024.14     13530082.88      2496692.19     13530060.92
      2496409.85     13530335.62      2496173.30     13531007.12
#Sta/Elev= 30
  3437.4  222.72  3616.8  223.28  3783.6  220.19  3992.3  214.59  4046.6  213.61
  4078.5  211.98  4096.6  211.99  4116.6  213.51  4176.8  213.64  4275.1  213.20
  4536.7  212.78  4696.7  210.84  4926.0  210.94  4982.6  209.88  4989.6  209.17
  4994.7  207.11  4995.0  206.61  4998.7  207.11  5010.9  209.35  5046.2  210.98
  5152.3  210.54  5227.5  211.33  5545.2  216.30  5619.2  218.07  5639.6  219.36
  5644.9  218.76  5663.9  219.44  5728.8  220.60  5864.1  223.30  5875.4  223.67
#Mann=12,-1,0
  3437.4    0.04       0  3783.6   0.013       0  3992.3    0.04       0
  4078.5    0.12       0  4176.8    0.05       0  4275.1    0.04       0
  4994.7    0.04       0  4998.7    0.04       0  5545.2    0.12       0
  5663.9    0.05       0  5728.8    0.12       0  5864.1    0.04       0
Bank Sta=4994.7,4998.7
Exp/Cntr=0.3,0.1

Type RM Length L Ch R = 1,580,0,0,0
BEGIN DESCRIPTION:
LGII4572
END DESCRIPTION:
XS GIS Cut Line= 4
      2497924.33     13530017.78      2496432.74     13529915.93
      2496173.29     13530114.33      2496173.29     13530885.05
#Sta/Elev= 30
  3314.6  224.27  3454.3  224.01  3537.8  221.75  3655.7  218.58  3729.6  216.48
  3854.5  213.58  3915.3  212.65  3935.4  209.74  3952.8  211.08  3975.5  210.63
  3995.5  213.19  4051.2  213.06  4289.3  211.62  4627.0  209.61  4707.2  210.35
  4882.8  209.88  4907.5  208.78  4924.5  209.78  4935.3  210.72  4943.5  210.21
  4976.9  205.57  4977.1  205.07  4980.9  205.57  5020.8  209.66  5128.5  209.26
  5506.9  211.74  5714.5  215.06  5854.8  219.41  5870.1  220.19  5907.0  220.47
#Mann=15,-1,0
  3314.6    0.05       0  3537.8    0.04       0  3655.7   0.013       0
  3729.6    0.04       0  3854.5    0.05       0  3952.8    0.12       0
  4051.2    0.05       0  4289.3    0.04       0  4882.8    0.05       0
  4924.5    0.04       0  4976.9    0.04       0  4980.9    0.04       0
  5714.5    0.12       0  5854.8    0.05       0  5870.1    0.12       0
Bank Sta=4976.9,4980.9
Exp/Cntr=0.3,0.1

Chan Stop Cuts=-1