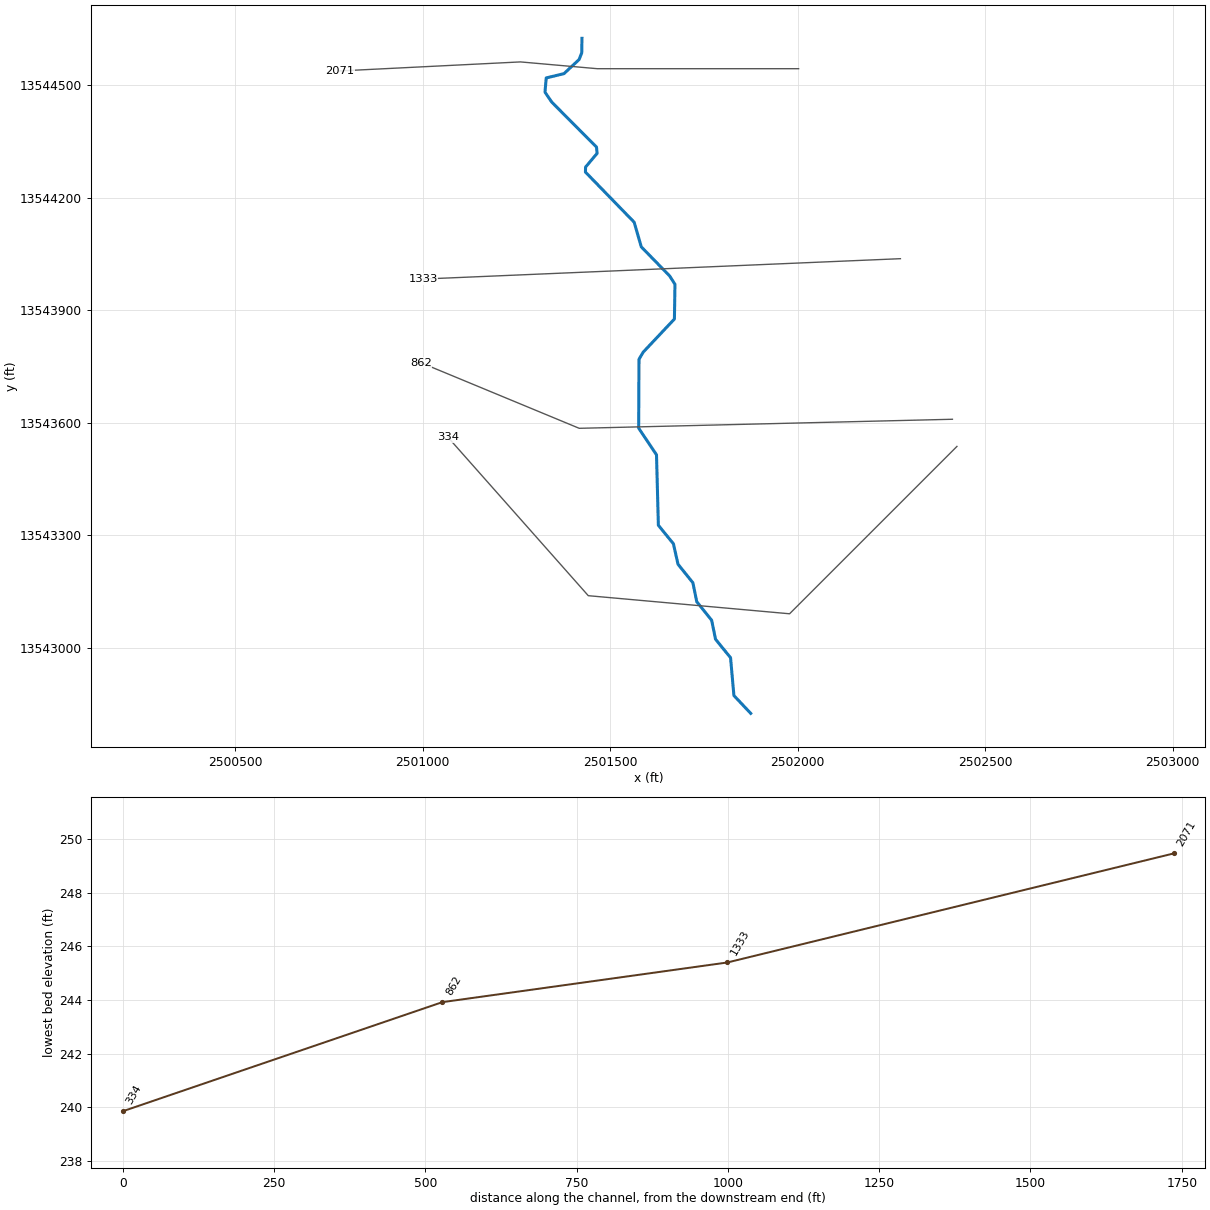
--- LG Stream255.prj (project) ---

Proj Title=LG Stream255 Base Level Engineering
Current Plan=p01
Default Exp/Contr=0.3,0.1
English Units
Geom File=g01
Flow File=f01
Plan File=p01
Y Axis Title=Elevation
X Axis Title(PF)=Main Channel Distance
X Axis Title(XS)=Station
BEGIN DESCRIPTION:
LG Stream255
END DESCRIPTION:
DSS Export Rating Curves= 0
DSS Export Rating Curve Sorted= 0
DSS Export Volume Flow Curves= 0
DXF OffsetX= 0
DXF OffsetY= 0
DXF ScaleX= 1
DXF ScaleY= 10

--- LG Stream255.p01 (plan) ---

Plan Title=Multiple Run
Short Identifier=Multiple
Geom File=g01
Flow File=f01
Subcritical Flow
K Sum by GR= 0
Std Step Tol= 0.01
Critical Tol= 0.01
Num of Std Step Trials= 20
Max Error Tol= 0.3
Flow Tol Ratio= 0.001
Split Flow NTrial= 30
Split Flow Tol= 0.02
Split Flow Ratio= 0.02
Log Output Level= 0
Friction Slope Method= 1
Unsteady Friction Slope Method= 2
Unsteady Bridges Friction Slope Method= 1
Parabolic Critical Depth
Global Vel Dist=  1 , 1 , 1
Global Log Level= 0
CheckData=True
Encroach Param= -1, 0, 0, 0
BEGIN DESCRIPTION:
Multiple Run
END DESCRIPTION:

--- LG Stream255.f01 (steady flow) ---

Flow Title=Multiple
Number of Profiles=7
Profile Names=10-year,25-year,50-year,1pct_min,100-year,1pct_plu,500-year
River Rch & RM= LG Stream255,Reach-1,2071
     284     432     559     351     700    1397    1085
Boundary for River Rch & Prof#=LG Stream255,Reach-1,1
Up Type=0
Dn Type=3
Dn Slope=0.005
Boundary for River Rch & Prof#=LG Stream255,Reach-1,2
Up Type=0
Dn Type=3
Dn Slope=0.005
Boundary for River Rch & Prof#=LG Stream255,Reach-1,3
Up Type=0
Dn Type=3
Dn Slope=0.005
Boundary for River Rch & Prof#=LG Stream255,Reach-1,4
Up Type=0
Dn Type=3
Dn Slope=0.005
Boundary for River Rch & Prof#=LG Stream255,Reach-1,5
Up Type=0
Dn Type=3
Dn Slope=0.005
Boundary for River Rch & Prof#=LG Stream255,Reach-1,6
Up Type=0
Dn Type=3
Dn Slope=0.005
Boundary for River Rch & Prof#=LG Stream255,Reach-1,7
Up Type=0
Dn Type=3
Dn Slope=0.005

--- LG Stream255.g01 (geometry) ---

Geom Title=Existing Conditions

River Reach=LG Stream255,Reach-1
Reach XY= 30
      2501425.00     13544625.00      2501424.47     13544586.63
      2501417.33     13544568.39      2501376.99     13544530.86
      2501329.72     13544519.40      2501326.42     13544481.43
      2501344.35     13544455.08      2501463.76     13544335.00
      2501465.38     13544318.33      2501434.62     13544281.67
      2501434.30     13544268.33      2501564.22     13544134.68
      2501583.18     13544068.96      2501658.57     13543991.74
      2501673.03     13543969.10      2501671.53     13543876.50
      2501588.40     13543788.31      2501577.06     13543769.14
      2501576.22     13543585.51      2501623.78     13543514.49
      2501628.75     13543326.55      2501668.88     13543277.18
      2501681.08     13543222.80      2501720.84     13543173.28
      2501731.08     13543122.80      2501770.84     13543073.28
      2501781.11     13543022.82      2501821.20     13542973.43
      2501830.22     13542872.45      2501875.00     13542825.00

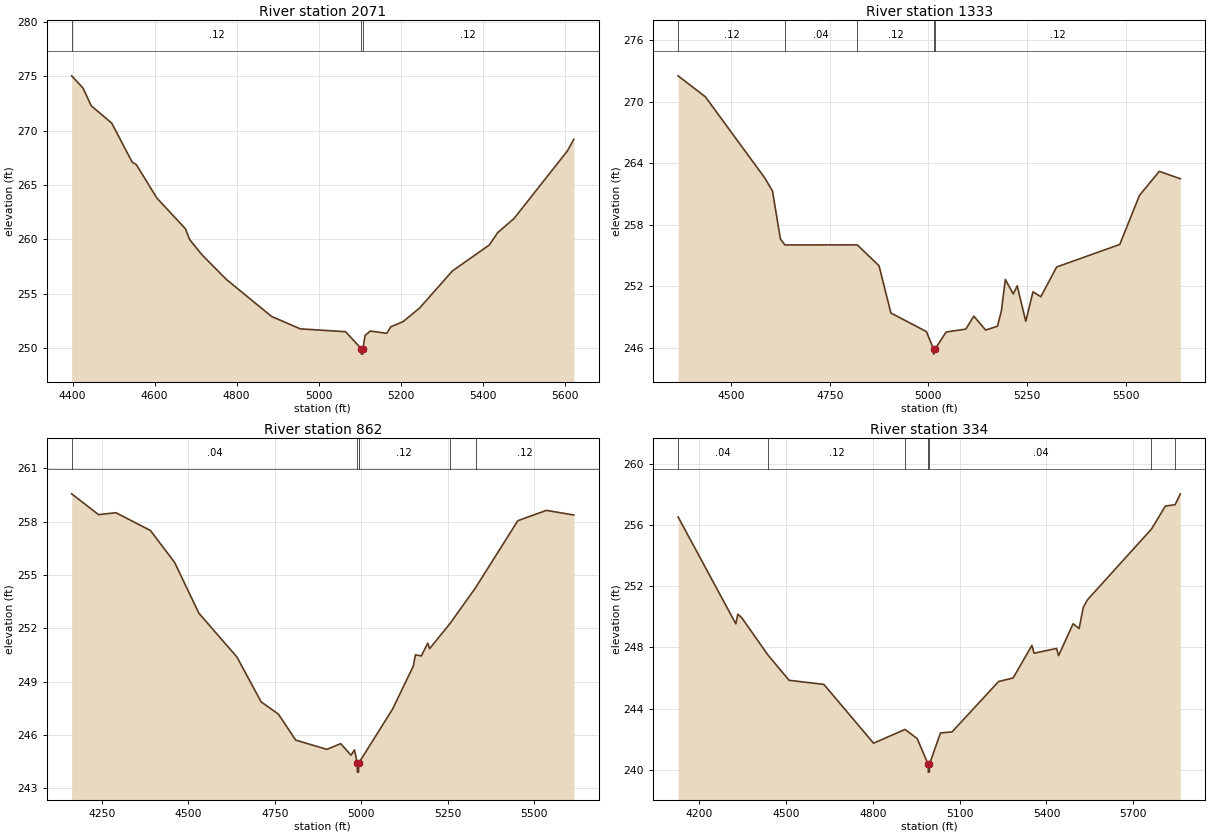
Type RM Length L Ch R = 1,2071,738,738,738
BEGIN DESCRIPTION:
LGII4703
END DESCRIPTION:
XS GIS Cut Line= 4
      2502002.71     13544544.04      2501465.99     13544544.04
      2501260.93     13544562.13      2500779.21     13544538.05
#Sta/Elev= 30
  4397.7  275.03  4425.4  273.91  4445.4  272.28  4495.4  270.69  4545.4  267.10
  4555.4  266.88  4605.4  263.81  4675.4  260.98  4685.4  260.00  4715.4  258.60
  4775.4  256.32  4885.4  252.93  4955.5  251.79  5065.9  251.53  5104.1  249.97
  5104.3  249.47  5107.8  249.47  5108.1  249.97  5113.5  251.19  5126.2  251.59
  5166.2  251.38  5176.3  251.98  5206.3  252.46  5246.3  253.70  5326.4  257.11
  5416.6  259.50  5436.6  260.62  5476.6  261.92  5606.8  268.13  5622.6  269.20
#Mann=3,-1,0
  4397.7    0.12       0  5104.1    0.05       0  5108.1    0.12       0
Bank Sta=5104.1,5108.1
Exp/Cntr=0.3,0.1

Type RM Length L Ch R = 1,1333,471,471,471
BEGIN DESCRIPTION:
LGII4702
END DESCRIPTION:
XS GIS Cut Line= 2
      2502274.18     13544037.44      2501001.64     13543983.16
#Sta/Elev= 30
  4365.3  272.55  4434.5  270.50  4584.7  262.61  4604.7  261.31  4624.7  256.64
  4636.0  256.05  4819.7  256.06  4874.9  254.02  4905.0  249.41  4995.1  247.60
  5013.1  245.90  5013.3  245.40  5017.1  245.90  5045.1  247.56  5095.1  247.84
  5115.2  249.11  5145.2  247.75  5175.2  248.12  5185.2  249.61  5195.2  252.68
  5215.3  251.27  5225.3  252.06  5247.1  248.60  5265.3  251.48  5285.3  251.00
  5325.4  253.90  5485.5  256.10  5535.5  260.89  5585.6  263.23  5639.0  262.51
#Mann=5,-1,0
  4365.3    0.12       0  4636.0    0.04       0  4819.7    0.12       0
  5013.1    0.05       0  5017.1    0.12       0
Bank Sta=5013.1,5017.1
Exp/Cntr=0.3,0.1

Type RM Length L Ch R = 1,862,528,528,528
BEGIN DESCRIPTION:
LGII4701
END DESCRIPTION:
XS GIS Cut Line= 3
      2502412.86     13543609.25      2501417.74     13543585.12
      2500995.55     13543760.03
#Sta/Elev= 30
  4162.6  259.56  4240.5  258.39  4290.5  258.50  4390.5  257.50  4460.5  255.70
  4530.6  252.85  4640.6  250.39  4710.6  247.87  4760.6  247.18  4810.7  245.72
  4900.7  245.20  4940.7  245.52  4970.7  244.87  4980.7  245.17  4988.7  244.42
  4989.0  243.92  4992.5  243.92  4992.7  244.42  4992.9  244.43  5090.7  247.46
  5150.8  249.88  5156.9  250.51  5174.0  250.45  5192.5  251.17  5197.9  250.86
  5256.5  252.26  5330.7  254.28  5453.0  258.05  5535.5  258.63  5615.0  258.37
#Mann=6,-1,0
  4162.6    0.04       0  4988.7    0.05       0  4992.7    0.04       0
  4992.9    0.12       0  5256.5    0.04       0  5330.7    0.12       0
Bank Sta=4988.7,4992.7
Exp/Cntr=0.3,0.1

Type RM Length L Ch R = 1,334,0,0,0
BEGIN DESCRIPTION:
LGII4700
END DESCRIPTION:
XS GIS Cut Line= 4
      2502424.88     13543536.85      2501978.62     13543090.58
      2501441.86     13543138.83      2501067.93     13543561.01
#Sta/Elev= 30
  4128.1  256.52  4327.3  249.54  4334.4  250.17  4348.5  249.92  4437.9  247.51
  4511.2  245.85  4631.4  245.58  4803.0  241.74  4911.5  242.64  4953.6  242.04
  4991.8  240.35  4992.0  239.85  4995.5  239.85  4995.8  240.35  5033.9  242.41
  5074.1  242.48  5234.7  245.77  5284.9  246.00  5349.7  248.13  5357.2  247.62
  5435.0  247.93  5441.7  247.46  5491.9  249.54  5512.8  249.23  5527.0  250.61
  5541.2  251.10  5762.6  255.73  5810.5  257.23  5844.2  257.32  5862.1  258.03
#Mann=7,-1,0
  4128.1    0.04       0  4437.9    0.12       0  4911.5    0.04       0
  4991.8    0.04       0  4995.8    0.04       0  5762.6    0.12       0
  5844.2    0.04       0
Bank Sta=4991.8,4995.8
Exp/Cntr=0.3,0.1

Chan Stop Cuts=-1