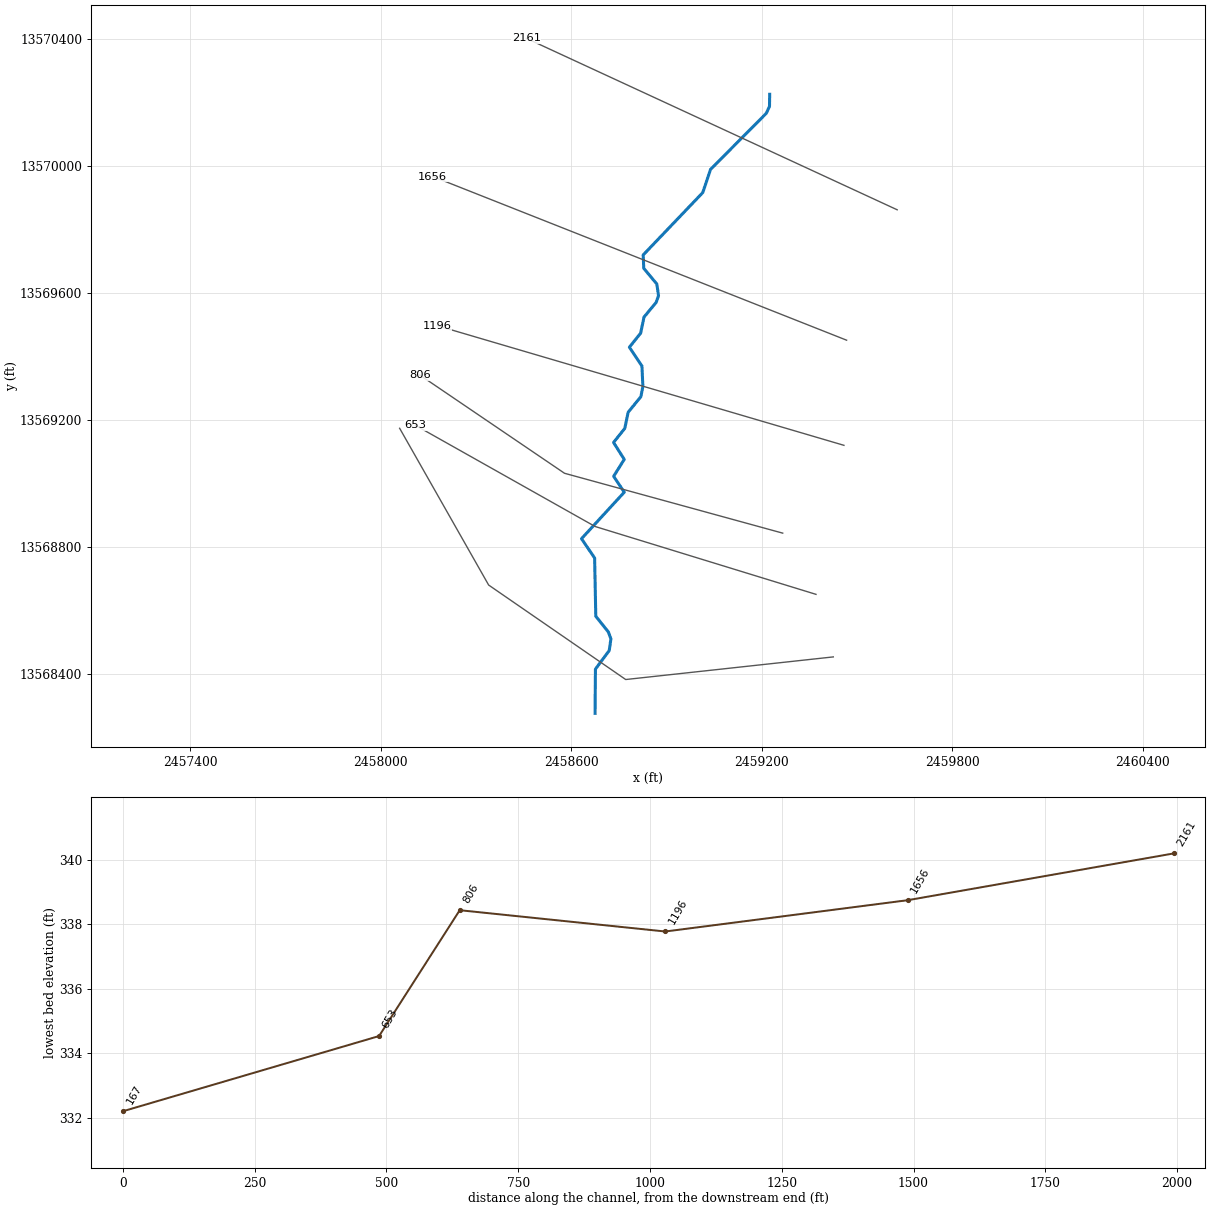
--- LG Stream302.prj (project) ---

Proj Title=LG Stream302 Base Level Engineering
Current Plan=p01
Default Exp/Contr=0.3,0.1
English Units
Geom File=g01
Flow File=f01
Plan File=p01
Y Axis Title=Elevation
X Axis Title(PF)=Main Channel Distance
X Axis Title(XS)=Station
BEGIN DESCRIPTION:
LG Stream302
END DESCRIPTION:
DSS Export Rating Curves= 0
DSS Export Rating Curve Sorted= 0
DSS Export Volume Flow Curves= 0
DXF OffsetX= 0
DXF OffsetY= 0
DXF ScaleX= 1
DXF ScaleY= 10

--- LG Stream302.p01 (plan) ---

Plan Title=Multiple Run
Short Identifier=Multiple
Geom File=g01
Flow File=f01
Subcritical Flow
K Sum by GR= 0
Std Step Tol= 0.01
Critical Tol= 0.01
Num of Std Step Trials= 20
Max Error Tol= 0.3
Flow Tol Ratio= 0.001
Split Flow NTrial= 30
Split Flow Tol= 0.02
Split Flow Ratio= 0.02
Log Output Level= 0
Friction Slope Method= 1
Unsteady Friction Slope Method= 2
Unsteady Bridges Friction Slope Method= 1
Parabolic Critical Depth
Global Vel Dist=  1 , 1 , 1
Global Log Level= 0
CheckData=True
Encroach Param= -1, 0, 0, 0
BEGIN DESCRIPTION:
Multiple Run
END DESCRIPTION:

--- LG Stream302.f01 (steady flow) ---

Flow Title=Multiple
Number of Profiles=7
Profile Names=10-year,25-year,50-year,1pct_min,100-year,1pct_plu,500-year
River Rch & RM= LG Stream302,Reach-1,2161
     483     769    1024     661    1319    2632    2167
Boundary for River Rch & Prof#=LG Stream302,Reach-1,1
Up Type=0
Dn Type=3
Dn Slope=0.005
Boundary for River Rch & Prof#=LG Stream302,Reach-1,2
Up Type=0
Dn Type=3
Dn Slope=0.005
Boundary for River Rch & Prof#=LG Stream302,Reach-1,3
Up Type=0
Dn Type=3
Dn Slope=0.005
Boundary for River Rch & Prof#=LG Stream302,Reach-1,4
Up Type=0
Dn Type=3
Dn Slope=0.005
Boundary for River Rch & Prof#=LG Stream302,Reach-1,5
Up Type=0
Dn Type=3
Dn Slope=0.005
Boundary for River Rch & Prof#=LG Stream302,Reach-1,6
Up Type=0
Dn Type=3
Dn Slope=0.005
Boundary for River Rch & Prof#=LG Stream302,Reach-1,7
Up Type=0
Dn Type=3
Dn Slope=0.005

--- LG Stream302.g01 (geometry) ---

Geom Title=Existing Conditions

River Reach=LG Stream302,Reach-1
Reach XY= 30
      2459225.00     13570225.00      2459224.41     13570186.84
      2459214.48     13570165.21      2459038.63     13569988.21
      2459014.22     13569915.32      2458826.62     13569718.97
      2458828.37     13569676.74      2458869.59     13569627.20
      2458874.92     13569590.39      2458867.23     13569569.06
      2458829.19     13569523.26      2458818.61     13569472.71
      2458783.05     13569428.32      2458822.63     13569369.11
      2458825.59     13569304.95      2458819.35     13569272.68
      2458779.16     13569223.25      2458768.63     13569172.70
      2458733.23     13569128.23      2458766.98     13569075.00
      2458733.56     13569021.67      2458767.02     13568971.67
      2458632.32     13568825.10      2458673.61     13568764.57
      2458677.29     13568580.93      2458717.19     13568530.92
      2458724.91     13568509.61      2458719.63     13568472.82
      2458676.19     13568414.52      2458675.00     13568275.00

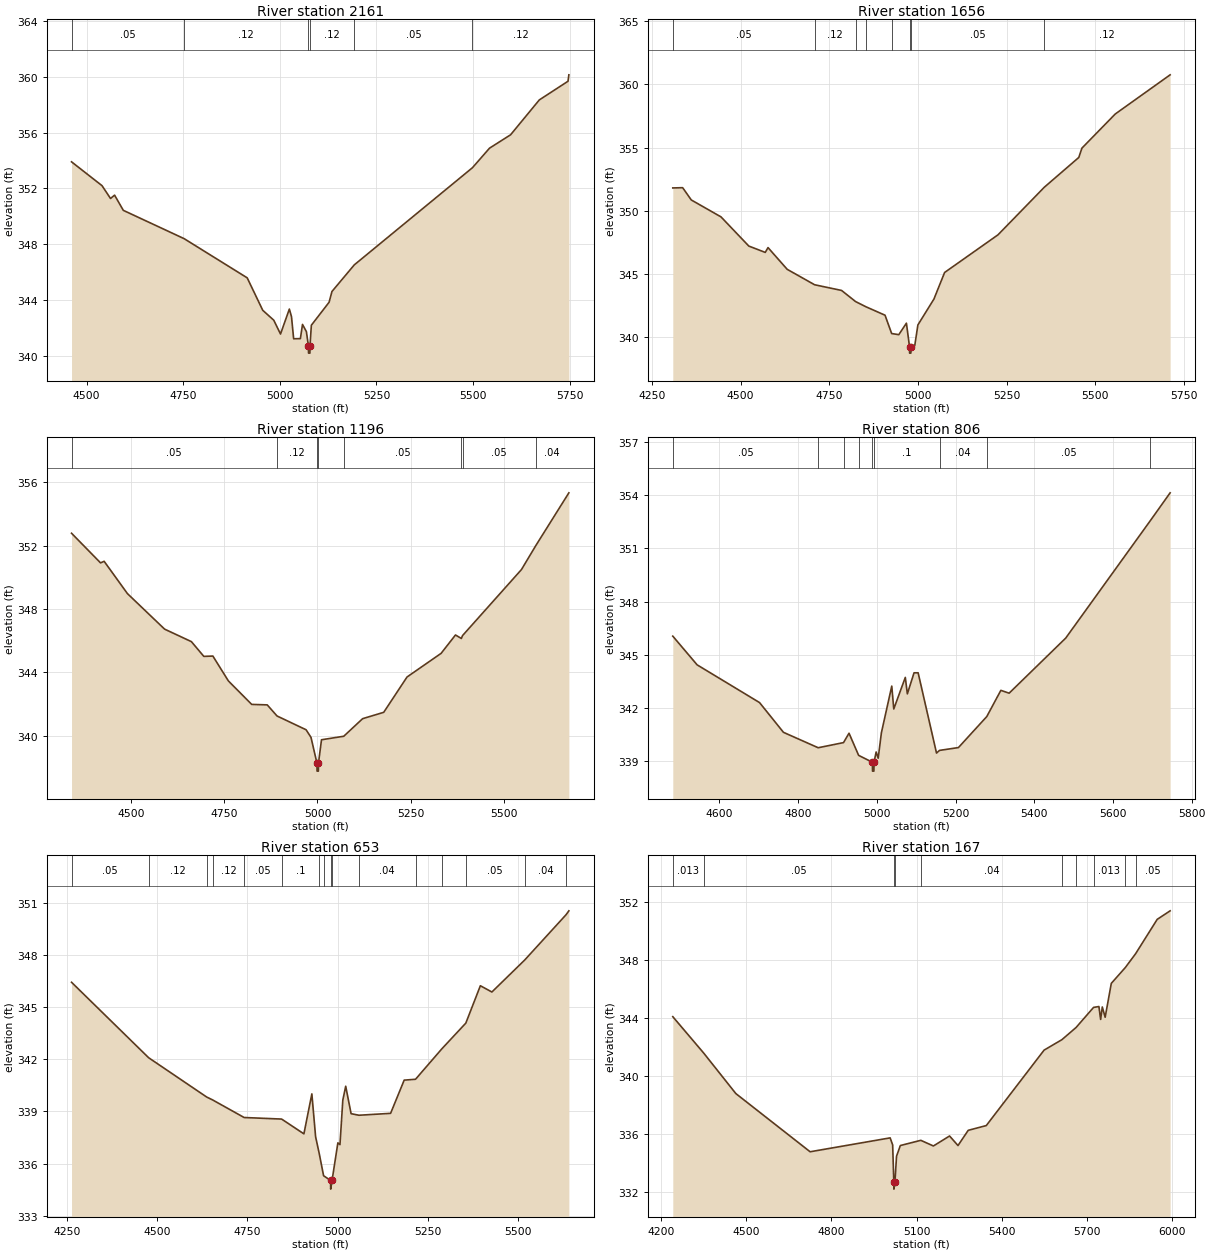
Type RM Length L Ch R = 1,2161,505,505,505
BEGIN DESCRIPTION:
LGII4589
END DESCRIPTION:
XS GIS Cut Line= 2
      2459626.63     13569861.16      2458458.63     13570401.20
#Sta/Elev= 30
  4461.0  353.91  4539.9  352.20  4561.9  351.28  4572.4  351.52  4595.0  350.43
  4752.3  348.40  4915.5  345.59  4955.8  343.26  4984.3  342.55  5001.7  341.56
  5024.6  343.35  5030.1  342.81  5035.7  341.22  5053.1  341.23  5058.6  342.25
  5068.7  341.73  5074.0  340.69  5074.3  340.19  5077.8  340.19  5078.0  340.69
  5081.5  342.19  5127.4  343.84  5134.8  344.61  5192.6  346.52  5498.4  353.49
  5542.5  354.89  5597.0  355.85  5671.3  358.35  5745.6  359.69  5747.8  360.15
#Mann=6,-1,0
  4461.0    0.05       0  4752.3    0.12       0  5074.0    0.05       0
  5078.0    0.12       0  5192.6    0.05       0  5498.4    0.12       0
Bank Sta=5074,5078
Exp/Cntr=0.3,0.1

Type RM Length L Ch R = 1,1656,460,460,460
BEGIN DESCRIPTION:
LGII4588
END DESCRIPTION:
XS GIS Cut Line= 2
      2459467.36     13569450.40      2458163.81     13569965.96
#Sta/Elev= 30
  4308.8  351.81  4336.6  351.83  4360.9  350.86  4444.7  349.52  4523.1  347.21
  4569.4  346.71  4577.2  347.09  4631.3  345.37  4708.5  344.15  4784.5  343.70
  4824.0  342.82  4853.0  342.41  4907.0  341.74  4925.7  340.29  4945.8  340.20
  4967.3  341.11  4976.1  339.24  4976.3  338.74  4979.8  338.74  4980.1  339.24
  4990.8  339.34  4999.6  340.97  5044.9  343.02  5074.9  345.12  5225.4  348.10
  5356.1  351.87  5453.1  354.22  5462.0  354.96  5555.9  357.66  5710.6  360.76
#Mann=8,-1,0
  4308.8    0.05       0  4708.5    0.12       0  4824.0    0.05       0
  4853.0    0.12       0  4925.7    0.05       0  4976.1    0.05       0
  4980.1    0.05       0  5356.1    0.12       0
Bank Sta=4976.1,4980.1
Exp/Cntr=0.3,0.1

Type RM Length L Ch R = 1,1196,390,390,390
BEGIN DESCRIPTION:
LGII4587
END DESCRIPTION:
XS GIS Cut Line= 2
      2459458.97     13569119.29      2458178.22     13569495.98
#Sta/Elev= 30
  4339.8  352.78  4417.7  350.91  4427.3  351.01  4489.9  348.97  4589.6  346.73
  4661.6  345.94  4694.9  345.01  4719.2  345.03  4760.9  343.46  4823.4  341.98
  4865.1  341.95  4891.4  341.25  4969.4  340.38  4982.6  339.90  4998.6  338.27
  4998.9  337.77  5002.4  337.77  5002.6  338.27  5010.8  339.75  5070.5  339.97
  5121.2  341.08  5177.8  341.48  5240.4  343.71  5331.8  345.20  5370.4  346.36
  5386.3  346.14  5389.3  346.32  5547.6  350.49  5585.5  351.98  5674.8  355.33
#Mann=8,-1,0
  4339.8    0.05       0  4891.4    0.12       0  4998.6    0.05       0
  5002.6    0.12       0  5070.5    0.05       0  5386.3    0.12       0
  5389.3    0.05       0  5585.5    0.04       0
Bank Sta=4998.6,5002.6
Exp/Cntr=0.3,0.1

Type RM Length L Ch R = 1,806,153,153,153
BEGIN DESCRIPTION:
LGII4586
END DESCRIPTION:
XS GIS Cut Line= 3
      2459266.13     13568842.67      2458578.75     13569031.28
      2458122.96     13569340.72
#Sta/Elev= 30
  4481.6  346.05  4543.4  344.43  4702.0  342.30  4762.8  340.62  4851.0  339.75
  4915.4  340.04  4929.4  340.57  4953.8  339.32  4988.9  338.93  4989.1  338.43
  4992.6  338.43  4992.9  338.93  4998.3  339.51  5003.5  339.16  5011.6  340.59
  5038.0  343.23  5043.1  341.94  5072.4  343.72  5077.6  342.79  5094.6  343.98
  5105.0  343.98  5151.7  339.45  5159.4  339.60  5207.4  339.76  5279.4  341.51
  5315.2  342.99  5336.2  342.83  5480.0  345.94  5694.7  352.56  5745.3  354.14
#Mann=9,-1,0
  4481.6    0.05       0  4851.0    0.12       0  4915.4    0.05       0
  4953.8     0.1       0  4988.9    0.05       0  4992.9     0.1       0
  5159.4    0.04       0  5279.4    0.05       0  5694.7    0.04       0
Bank Sta=4988.9,4992.9
Exp/Cntr=0.3,0.1

Type RM Length L Ch R = 1,653,486,486,486
BEGIN DESCRIPTION:
LGII4585
END DESCRIPTION:
XS GIS Cut Line= 3
      2459370.92     13568649.87      2458675.15     13568863.63
      2458109.67     13569181.97
#Sta/Elev= 30
  4263.2  346.43  4476.6  342.09  4637.2  339.83  4653.9  339.66  4741.0  338.65
  4844.8  338.56  4906.5  337.71  4928.5  340.01  4938.9  337.54  4948.6  336.61
  4961.0  335.30  4980.4  335.03  4980.6  334.53  4984.4  335.03  5000.5  337.19
  5006.3  337.09  5014.2  339.65  5022.2  340.45  5037.1  338.87  5058.9  338.78
  5146.5  338.89  5184.1  340.80  5215.5  340.85  5288.3  342.60  5354.7  344.08
  5395.0  346.23  5426.9  345.87  5517.7  347.71  5632.4  350.32  5640.0  350.54
#Mann=16,-1,0
  4263.2    0.05       0  4476.6    0.12       0  4637.2    0.05       0
  4653.9    0.12       0  4741.0    0.05       0  4844.8     0.1       0
  4948.6   0.013       0  4961.0     0.1       0  4980.4    0.05       0
  4984.4     0.1       0  5058.9    0.04       0  5215.5    0.05       0
  5288.3    0.04       0  5354.7    0.05       0  5517.7    0.04       0
  5632.4    0.05       0
Bank Sta=4980.4,4984.4
Exp/Cntr=0.3,0.1

Type RM Length L Ch R = 1,167,0,0,0
BEGIN DESCRIPTION:
LGII4584
END DESCRIPTION:
XS GIS Cut Line= 4
      2459425.45     13568452.88      2458771.55     13568381.62
      2458339.84     13568679.21      2458059.49     13569172.96
#Sta/Elev= 30
  4242.1  344.11  4350.7  341.60  4463.9  338.80  4725.3  334.78  5006.9  335.74
  5015.7  335.25  5019.8  332.70  5020.0  332.20  5023.8  332.70  5029.3  334.47
  5042.7  335.21  5114.7  335.57  5159.1  335.18  5215.9  335.87  5245.6  335.21
  5281.5  336.26  5345.1  336.59  5548.5  341.80  5611.1  342.52  5660.9  343.36
  5722.6  344.75  5741.4  344.81  5747.5  343.92  5753.3  344.78  5763.4  344.07
  5785.0  346.41  5834.2  347.50  5870.6  348.46  5946.5  350.83  5992.0  351.42
#Mann=10,-1,0
  4242.1   0.013       0  4350.7    0.05       0  5019.8    0.05       0
  5023.8    0.05       0  5114.7    0.04       0  5611.1   0.013       0
  5660.9    0.04       0  5722.6   0.013       0  5834.2    0.04       0
  5870.6    0.05       0
Bank Sta=5019.8,5023.8
Exp/Cntr=0.3,0.1

Chan Stop Cuts=-1