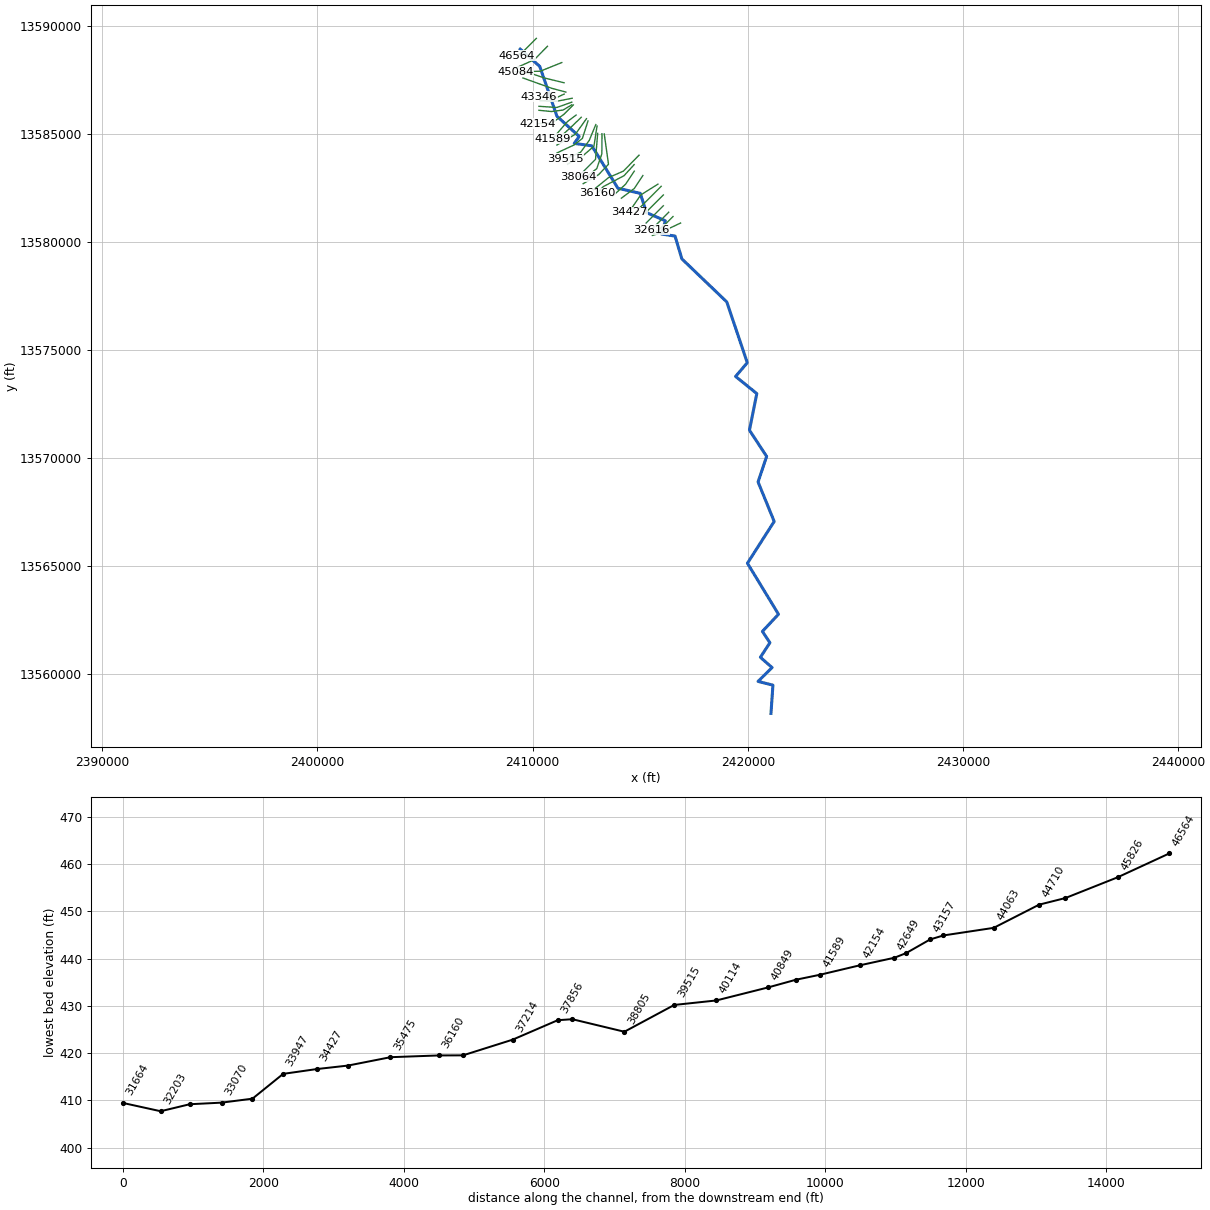
--- LITTLE SALT CREEK.prj (project) ---

Proj Title=LITTLE SALT CREEK Base Level Engineering
Current Plan=p01
Default Exp/Contr=0.3,0.1
English Units
Geom File=g01
Flow File=f01
Plan File=p01
Y Axis Title=Elevation
X Axis Title(PF)=Main Channel Distance
X Axis Title(XS)=Station
BEGIN DESCRIPTION:
LITTLE SALT CREEK
END DESCRIPTION:
DSS Export Rating Curves= 0
DSS Export Rating Curve Sorted= 0
DSS Export Volume Flow Curves= 0
DXF OffsetX= 0
DXF OffsetY= 0
DXF ScaleX= 1
DXF ScaleY= 10

--- LITTLE SALT CREEK.p01 (plan) ---

Plan Title=Multiple Run
Short Identifier=Multiple
Geom File=g01
Flow File=f01
Subcritical Flow
K Sum by GR= 0
Std Step Tol= 0.01
Critical Tol= 0.01
Num of Std Step Trials= 20
Max Error Tol= 0.3
Flow Tol Ratio= 0.001
Split Flow NTrial= 30
Split Flow Tol= 0.02
Split Flow Ratio= 0.02
Log Output Level= 0
Friction Slope Method= 1
Unsteady Friction Slope Method= 2
Unsteady Bridges Friction Slope Method= 1
Parabolic Critical Depth
Global Vel Dist=  1 , 1 , 1
Global Log Level= 0
CheckData=True
Encroach Param= -1, 0, 0, 0
BEGIN DESCRIPTION:
Multiple Run
END DESCRIPTION:

--- LITTLE SALT CREEK.f01 (steady flow) ---

Flow Title=Multiple
Number of Profiles=7
Profile Names=10-year,25-year,50-year,1pct_min,100-year,1pct_plu,500-year
River Rch & RM= LITTLE SALT CREE,Reach-1,46564
     504     819    1105     725    1446    2886    2452
River Rch & RM= LITTLE SALT CREE,Reach-1,45826
     722    1192    1625    1074    2143    4276    3693
River Rch & RM= LITTLE SALT CREE,Reach-1,42154
     888    1476    2023    1342    2678    5343    4651
River Rch & RM= LITTLE SALT CREE,Reach-1,38064
     927    1542    2114    1403    2798    5584    4862
River Rch & RM= LITTLE SALT CREE,Reach-1,36507
    1402    2377    3300    2213    4415    8810    7843
River Rch & RM= LITTLE SALT CREE,Reach-1,31664
    1610    2740    3812    2560    5108   10192    9104
River Rch & RM= LITTLE SALT CREE,Reach-1,26516
    1813    3100    4327    2914    5814   11600   10418
River Rch & RM= LITTLE SALT CREE,Reach-1,23898
    1877    3213    4488    3024    6034   12039   10824
River Rch & RM= LITTLE SALT CREE,Reach-1,22935
    2059    3523    4920    3314    6612   13193   11851
River Rch & RM= LITTLE SALT CREE,Reach-1,20745
    2141    3664    5118    3447    6878   13724   12323
River Rch & RM= LITTLE SALT CREE,Reach-1,17202
    2364    4059    5681    3833    7648   15259   13751
River Rch & RM= LITTLE SALT CREE,Reach-1,12953
    2385    4110    5766    3898    7778   15520   14051
River Rch & RM= LITTLE SALT CREE,Reach-1,10301
    2402    4139    5806    3925    7832   15627   14148
River Rch & RM= LITTLE SALT CREE,Reach-1,8912
    2655    4572    6412    4332    8644   17247   15588
Boundary for River Rch & Prof#=LITTLE SALT CREE,Reach-1,1
Up Type=0
Dn Type=3
Dn Slope=0.0022
Boundary for River Rch & Prof#=LITTLE SALT CREE,Reach-1,2
Up Type=0
Dn Type=3
Dn Slope=0.0022
Boundary for River Rch & Prof#=LITTLE SALT CREE,Reach-1,3
Up Type=0
Dn Type=3
Dn Slope=0.0022
Boundary for River Rch & Prof#=LITTLE SALT CREE,Reach-1,4
Up Type=0
Dn Type=3
Dn Slope=0.0022
Boundary for River Rch & Prof#=LITTLE SALT CREE,Reach-1,5
Up Type=0
Dn Type=3
Dn Slope=0.0022
Boundary for River Rch & Prof#=LITTLE SALT CREE,Reach-1,6
Up Type=0
Dn Type=3
Dn Slope=0.0022
Boundary for River Rch & Prof#=LITTLE SALT CREE,Reach-1,7
Up Type=0
Dn Type=3
Dn Slope=0.0022

--- LITTLE SALT CREEK.g01 (geometry) ---

Geom Title=Existing Conditions

River Reach=LITTLE SALT CREE,Reach-1
Reach XY= 30
      2409425.00     13588925.00      2410334.20     13588126.15
      2411130.05     13585822.73      2412166.01     13584882.01
      2411938.16     13584561.28      2412752.51     13584448.97
      2413965.32     13582485.17      2415002.14     13582248.53
      2415291.41     13581358.20      2416169.58     13580977.75
      2415985.47     13580365.15      2416619.75     13580269.56
      2416935.76     13579215.32      2419021.33     13577223.42
      2419974.62     13574409.73      2419432.58     13573771.65
      2420417.49     13572978.58      2420075.59     13571285.62
      2420873.20     13570068.89      2420475.38     13568890.16
      2421224.64     13567059.73      2419982.53     13565124.99
      2421424.45     13562764.36      2420677.06     13561969.15
      2421025.11     13561445.11      2420582.60     13560771.66
      2421125.22     13560294.83      2420474.89     13559655.11
      2421165.99     13559482.12      2421075.00     13558175.00

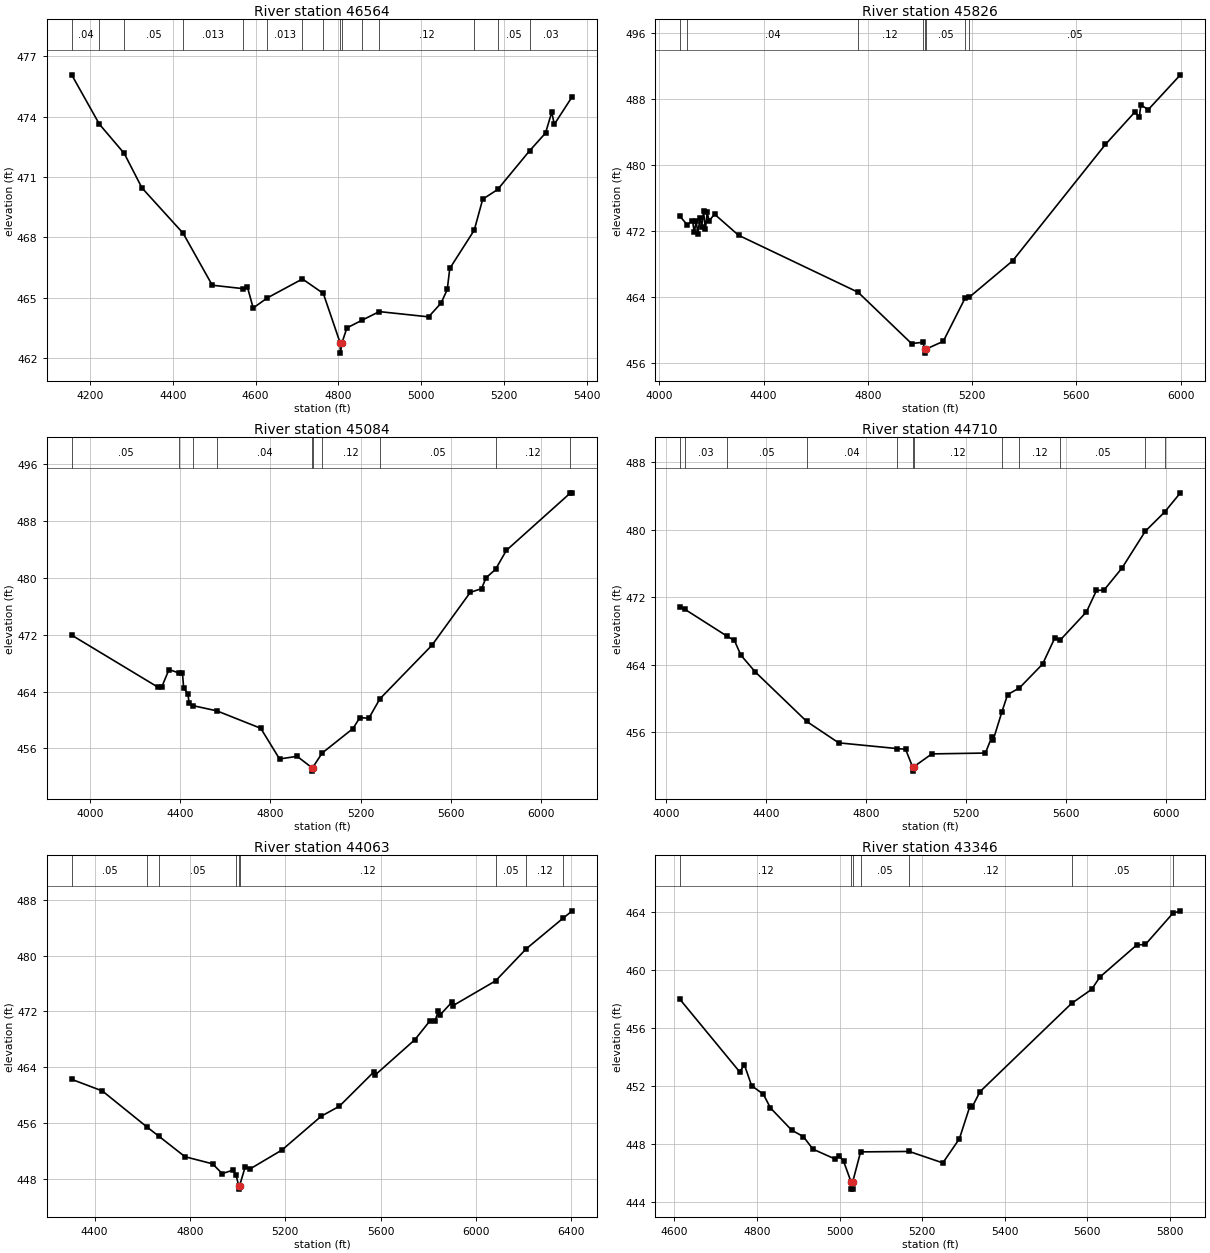
Type RM Length L Ch R = 1,46564,738,738,738
BEGIN DESCRIPTION:
LITTLE SALT CREEK 84.0
END DESCRIPTION:
XS GIS Cut Line= 3
      2410175.03     13589425.03      2409575.00     13588825.00
      2409275.02     13588625.01
#Sta/Elev= 30
  4155.7  476.07  4222.6  473.62  4282.6  472.17  4325.4  470.46  4424.8  468.21
  4495.2  465.63  4569.6  465.46  4580.0  465.55  4594.1  464.50  4628.2  465.00
  4713.1  465.94  4763.5  465.22  4804.3  462.76  4804.5  462.26  4808.3  462.76
  4820.4  463.51  4856.6  463.89  4898.7  464.32  5017.8  464.06  5047.8  464.74
  5062.9  465.42  5068.9  466.46  5128.0  468.36  5148.5  469.90  5184.6  470.38
  5261.7  472.30  5300.2  473.18  5315.3  474.22  5321.3  473.61  5364.8  474.99
#Mann=15,-1,0
  4155.7    0.04       0  4222.6   0.013       0  4282.6    0.05       0
  4424.8   0.013       0  4569.6    0.12       0  4628.2   0.013       0
  4713.1    0.05       0  4763.5    0.12       0  4804.3    0.05       0
  4808.3    0.12       0  4856.6    0.05       0  4898.7    0.12       0
  5128.0   0.013       0  5184.6    0.05       0  5261.7    0.03       0
Bank Sta=4804.3,4808.3
Exp/Cntr=0.3,0.1

Type RM Length L Ch R = 1,45826,742,742,742
BEGIN DESCRIPTION:
Mapping XS 152ef2ab
END DESCRIPTION:
XS GIS Cut Line= 3
      2410691.96     13589056.65      2410077.27     13588433.76
      2409122.48     13588007.60
#Sta/Elev= 30
  4078.7  473.81  4106.9  472.76  4127.2  473.25  4134.3  471.87  4141.3  473.16
  4148.5  471.70  4155.5  473.60  4162.6  472.53  4169.6  474.40  4176.7  472.20
  4183.8  474.27  4190.9  473.24  4212.1  474.04  4304.0  471.49  4762.9  464.57
  4967.9  458.35  5010.1  458.50  5020.0  457.69  5020.3  457.19  5024.0  457.69
  5089.5  458.62  5174.4  463.93  5188.9  463.96  5355.8  468.39  5711.9  482.51
  5824.3  486.42  5842.1  485.85  5847.6  487.30  5876.2  486.73  5999.4  490.95
#Mann=8,-1,0
  4078.7    0.05       0  4106.9    0.04       0  4762.9    0.12       0
  5010.1    0.05       0  5020.0    0.05       0  5024.0    0.05       0
  5174.4    0.12       0  5188.9    0.05       0
Bank Sta=5020,5024
Exp/Cntr=0.3,0.1

Type RM Length L Ch R = 1,45084,374,374,374
BEGIN DESCRIPTION:
Mapping XS 394bdb72
END DESCRIPTION:
XS GIS Cut Line= 3
      2411355.78     13588302.64      2410351.82     13587901.06
      2409212.60     13587880.57
#Sta/Elev= 30
  3918.7  471.92  4302.3  464.59  4318.0  464.62  4350.4  467.09  4395.3  466.59
  4410.0  466.63  4415.4  464.48  4434.3  463.69  4439.7  462.32  4458.5  462.00
  4562.7  461.28  4757.4  458.83  4840.8  454.52  4918.9  454.89  4983.8  453.31
  4984.1  452.81  4987.8  453.31  5029.8  455.35  5166.8  458.80  5196.8  460.33
  5236.9  460.24  5286.0  462.97  5516.9  470.50  5686.9  477.93  5736.9  478.45
  5756.9  479.98  5799.0  481.16  5847.0  483.83  6130.7  491.89  6139.4  491.92
#Mann=10,-1,0
  3918.7    0.05       0  4395.3    0.12       0  4458.5    0.05       0
  4562.7    0.04       0  4983.8    0.04       0  4987.8    0.04       0
  5029.8    0.12       0  5286.0    0.05       0  5799.0    0.12       0
  6130.7    0.05       0
Bank Sta=4983.8,4987.8
Exp/Cntr=0.3,0.1

Type RM Length L Ch R = 1,44710,647,647,647
BEGIN DESCRIPTION:
Mapping XS 29d1f295
END DESCRIPTION:
XS GIS Cut Line= 4
      2411462.28     13587368.36      2410536.22     13587593.73
      2409970.73     13587786.32      2409520.02     13587815.00
#Sta/Elev= 30
  4056.1  470.79  4075.7  470.58  4246.5  467.36  4274.5  466.88  4300.3  465.14
  4358.0  463.15  4563.7  457.29  4691.4  454.76  4924.9  454.08  4959.0  454.00
  4987.1  451.91  4987.3  451.41  4991.1  451.91  5064.1  453.45  5278.3  453.55
  5304.4  455.48  5309.7  455.12  5344.6  458.45  5367.1  460.47  5414.4  461.26
  5507.0  464.08  5555.2  467.13  5578.6  466.96  5682.5  470.26  5722.5  472.80
  5752.6  472.84  5824.8  475.46  5917.8  479.81  5995.4  482.09  6058.2  484.36
#Mann=12,-1,0
  4056.1    0.04       0  4075.7    0.03       0  4246.5    0.05       0
  4563.7    0.04       0  4924.9    0.12       0  4987.1    0.05       0
  4991.1    0.12       0  5344.6    0.05       0  5414.4    0.12       0
  5578.6    0.05       0  5917.8    0.12       0  5995.4    0.05       0
Bank Sta=4987.1,4991.1
Exp/Cntr=0.3,0.1

Type RM Length L Ch R = 1,44063,717,717,717
BEGIN DESCRIPTION:
Mapping XS 476c7ce1
END DESCRIPTION:
XS GIS Cut Line= 3
      2411548.31     13586938.10      2410896.82     13587110.20
      2409552.80     13587589.62
#Sta/Elev= 30
  4303.9  462.26  4432.7  460.59  4620.1  455.41  4671.0  454.06  4779.6  451.15
  4895.2  450.13  4935.4  448.73  4981.4  449.23  4994.0  448.49  5004.6  447.00
  5004.8  446.50  5008.6  447.00  5032.1  449.71  5054.0  449.43  5186.1  452.11
  5351.3  456.97  5427.3  458.40  5570.7  463.28  5576.0  462.84  5744.1  467.95
  5806.5  470.62  5829.0  470.67  5842.6  472.11  5850.3  471.52  5899.0  473.32
  5904.3  472.84  6082.9  476.40  6211.6  481.00  6365.8  485.38  6404.7  486.45
#Mann=9,-1,0
  4303.9    0.05       0  4620.1    0.12       0  4671.0    0.05       0
  4994.0    0.12       0  5004.6    0.05       0  5008.6    0.12       0
  6082.9    0.05       0  6211.6    0.12       0  6365.8    0.05       0
Bank Sta=5004.6,5008.6
Exp/Cntr=0.3,0.1

Type RM Length L Ch R = 1,43346,189,189,189
BEGIN DESCRIPTION:
Mapping XS 7a5dd529
END DESCRIPTION:
XS GIS Cut Line= 3
      2411466.36     13586843.83      2411122.19     13586684.03
      2410290.36     13586725.01
#Sta/Elev= 30
  4613.2  458.00  4758.0  452.99  4769.7  453.46  4787.1  452.03  4815.5  451.44
  4832.8  450.49  4884.2  448.96  4912.6  448.51  4935.5  447.65  4988.4  446.98
  4999.9  447.17  5009.9  446.81  5027.9  445.39  5028.1  444.89  5031.6  444.89
  5031.9  445.39  5051.0  447.46  5168.8  447.49  5250.2  446.70  5290.2  448.36
  5316.2  450.65  5321.2  450.56  5340.3  451.62  5562.0  457.71  5610.6  458.68
  5630.6  459.53  5719.7  461.74  5740.8  461.78  5807.3  463.93  5825.5  464.10
#Mann=7,-1,0
  4613.2    0.12       0  5027.9    0.05       0  5031.9    0.12       0
  5051.0    0.05       0  5168.8    0.12       0  5562.0    0.05       0
  5807.3    0.03       0
Bank Sta=5027.9,5031.9
Exp/Cntr=0.3,0.1

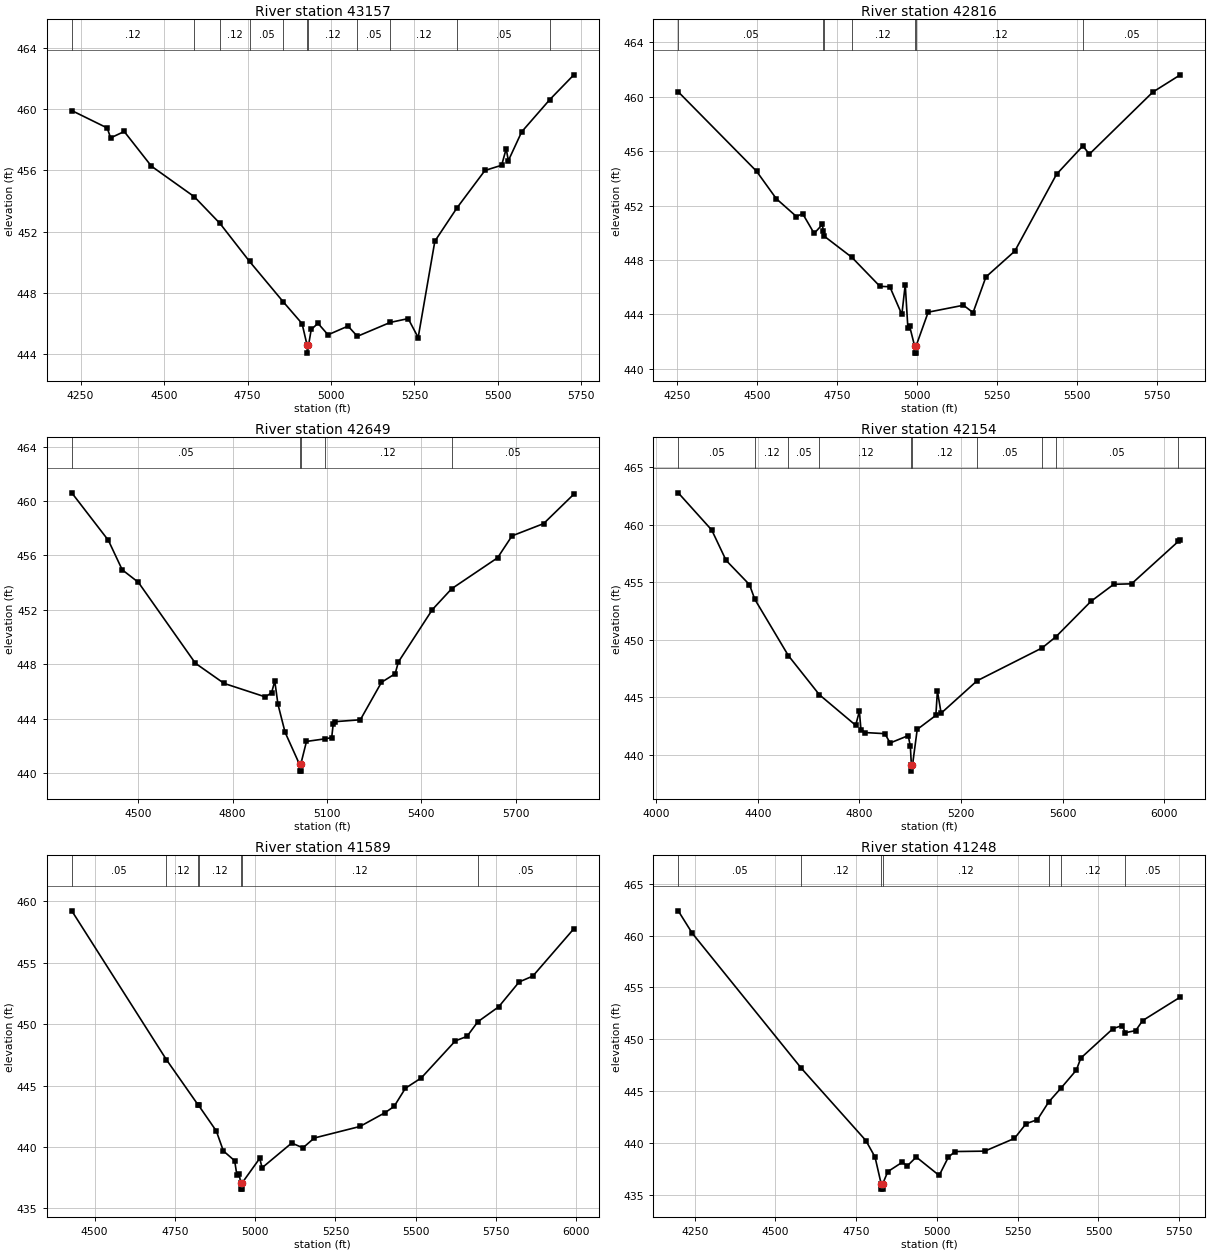
Type RM Length L Ch R = 1,43157,341,341,341
BEGIN DESCRIPTION:
Mapping XS 907dc638
END DESCRIPTION:
XS GIS Cut Line= 3
      2411839.25     13586651.24      2411122.19     13586511.93
      2410348.85     13586536.48
#Sta/Elev= 30
  4223.5  459.92  4329.7  458.78  4339.9  458.13  4380.6  458.55  4462.1  456.28
  4590.5  454.28  4667.5  452.53  4756.2  450.04  4857.0  447.40  4913.5  445.97
  4928.7  444.54  4929.0  444.04  4932.7  444.54  4940.9  445.59  4961.2  445.99
  4991.2  445.24  5051.2  445.81  5079.1  445.14  5177.6  446.05  5231.3  446.30
  5261.3  445.06  5311.3  451.37  5377.6  453.55  5461.4  456.00  5511.4  456.34
  5525.0  457.42  5531.5  456.64  5571.5  458.53  5655.7  460.64  5727.7  462.26
#Mann=11,-1,0
  4223.5    0.12       0  4590.5    0.05       0  4667.5    0.12       0
  4756.2    0.05       0  4857.0    0.12       0  4928.7    0.05       0
  4932.7    0.12       0  5079.1    0.05       0  5177.6    0.12       0
  5377.6    0.05       0  5655.7    0.03       0
Bank Sta=4928.7,4932.7
Exp/Cntr=0.3,0.1

Type RM Length L Ch R = 1,42816,167,167,167
BEGIN DESCRIPTION:
Mapping XS 4cc02eae
END DESCRIPTION:
XS GIS Cut Line= 3
      2411822.92     13586470.95      2411130.39     13586225.08
      2410299.27     13586278.31
#Sta/Elev= 30
  4254.6  460.36  4499.2  454.52  4560.9  452.50  4623.8  451.19  4642.9  451.41
  4679.0  449.95  4704.6  450.61  4707.4  450.16  4710.9  449.74  4796.9  448.19
  4884.4  446.06  4915.3  446.03  4952.8  443.99  4963.4  446.19  4971.7  442.99
  4977.0  443.14  4992.9  441.65  4993.1  441.15  4996.6  441.15  4996.9  441.65
  5035.0  444.16  5145.2  444.67  5175.2  444.13  5215.3  446.75  5305.5  448.65
  5435.8  454.30  5517.9  456.38  5538.4  455.78  5736.4  460.34  5822.3  461.61
#Mann=7,-1,0
  4254.6    0.05       0  4707.4    0.12       0  4710.9    0.05       0
  4796.9    0.12       0  4992.9    0.05       0  4996.9    0.12       0
  5517.9    0.05       0
Bank Sta=4992.9,4996.9
Exp/Cntr=0.3,0.1

Type RM Length L Ch R = 1,42649,495,495,495
BEGIN DESCRIPTION:
Mapping XS 13ea9fca
END DESCRIPTION:
XS GIS Cut Line= 4
      2411822.89     13586348.01      2411417.23     13586106.25
      2410880.43     13586036.59      2410299.29     13586093.88
#Sta/Elev= 30
  4288.1  460.60  4404.6  457.11  4448.6  454.95  4500.0  454.03  4681.4  448.09
  4772.7  446.61  4903.8  445.62  4923.9  445.92  4934.0  446.79  4944.1  445.08
  4966.8  443.02  5012.7  440.67  5012.9  440.17  5016.4  440.17  5016.7  440.67
  5034.9  442.35  5093.8  442.54  5115.1  442.63  5120.1  443.66  5125.6  443.80
  5206.3  443.94  5273.5  446.69  5317.1  447.32  5327.2  448.18  5435.5  452.03
  5496.9  453.56  5642.9  455.83  5688.9  457.44  5789.4  458.34  5885.6  460.50
#Mann=5,-1,0
  4288.1    0.05       0  5012.7    0.05       0  5016.7    0.05       0
  5093.8    0.12       0  5496.9    0.05       0
Bank Sta=5012.7,5016.7
Exp/Cntr=0.3,0.1

Type RM Length L Ch R = 1,42154,565,565,565
BEGIN DESCRIPTION:
Mapping XS 98de1267
END DESCRIPTION:
XS GIS Cut Line= 4
      2411892.56     13586343.92      2411458.21     13585909.56
      2410888.62     13585491.59      2410233.00     13585479.30
#Sta/Elev= 30
  4086.8  462.78  4218.7  459.54  4275.2  456.90  4367.2  454.79  4388.1  453.52
  4520.1  448.62  4642.4  445.21  4785.3  442.55  4799.9  443.77  4806.1  442.18
  4820.8  441.92  4900.2  441.82  4921.1  441.01  4992.1  441.65  5000.6  440.72
  5004.6  439.06  5004.9  438.56  5008.9  439.06  5027.6  442.19  5100.9  443.41
  5107.1  445.53  5121.7  443.60  5263.0  446.42  5519.1  449.28  5573.9  450.26
  5711.2  453.33  5801.3  454.82  5871.3  454.86  6055.8  458.56  6063.3  458.71
#Mann=10,-1,0
  4086.8    0.05       0  4388.1    0.12       0  4520.1    0.05       0
  4642.4    0.12       0  5004.6    0.05       0  5008.9    0.12       0
  5263.0    0.05       0  5519.1    0.12       0  5573.9    0.05       0
  6055.8    0.04       0
Bank Sta=5004.6,5008.9
Exp/Cntr=0.3,0.1

Type RM Length L Ch R = 1,41589,341,341,341
BEGIN DESCRIPTION:
LITTLE SALT CREEK 73.0
END DESCRIPTION:
XS GIS Cut Line= 3
      2412025.02     13585875.01      2411625.00     13585575.00
      2410925.03     13584775.03
#Sta/Elev= 30
  4429.0  459.22  4723.5  447.11  4822.1  443.43  4823.8  443.39  4879.0  441.30
  4900.9  439.68  4936.1  438.88  4942.8  437.75  4950.4  437.78  4954.9  437.07
  4955.2  436.57  4958.9  436.57  4959.2  437.07  5014.0  439.07  5021.6  438.31
  5113.6  440.32  5148.7  439.93  5183.9  440.73  5326.2  441.67  5404.1  442.79
  5432.5  443.30  5467.6  444.78  5517.0  445.62  5623.3  448.64  5659.4  449.00
  5693.0  450.19  5758.1  451.41  5821.7  453.43  5864.4  453.91  5992.0  457.76
#Mann=7,-1,0
  4429.0    0.05       0  4723.5    0.12       0  4822.1    0.05       0
  4823.8    0.12       0  4954.9    0.05       0  4959.2    0.12       0
  5693.0    0.05       0
Bank Sta=4954.9,4959.2
Exp/Cntr=0.3,0.1

Type RM Length L Ch R = 1,41248,399,399,399
BEGIN DESCRIPTION:
Mapping XS 9306d7d1
END DESCRIPTION:
XS GIS Cut Line= 3
      2412261.35     13585770.22      2411794.22     13585319.49
      2411122.23     13584713.05
#Sta/Elev= 30
  4199.1  462.40  4242.6  460.23  4580.0  447.20  4780.0  440.21  4808.3  438.62
  4827.4  436.02  4827.7  435.52  4831.6  435.52  4831.9  436.02  4847.9  437.21
  4893.3  438.13  4907.5  437.74  4935.9  438.62  5006.9  436.84  5035.3  438.61
  5056.2  439.15  5148.1  439.19  5240.0  440.42  5275.9  441.84  5311.0  442.23
  5346.0  443.94  5384.4  445.29  5431.4  447.01  5445.5  448.18  5544.9  451.02
  5573.3  451.32  5583.2  450.63  5615.2  450.83  5636.9  451.80  5753.4  454.07
#Mann=7,-1,0
  4199.1    0.05       0  4580.0    0.12       0  4827.4    0.05       0
  4831.9    0.12       0  5346.0    0.05       0  5384.4    0.12       0
  5583.2    0.05       0
Bank Sta=4827.4,4831.9
Exp/Cntr=0.3,0.1

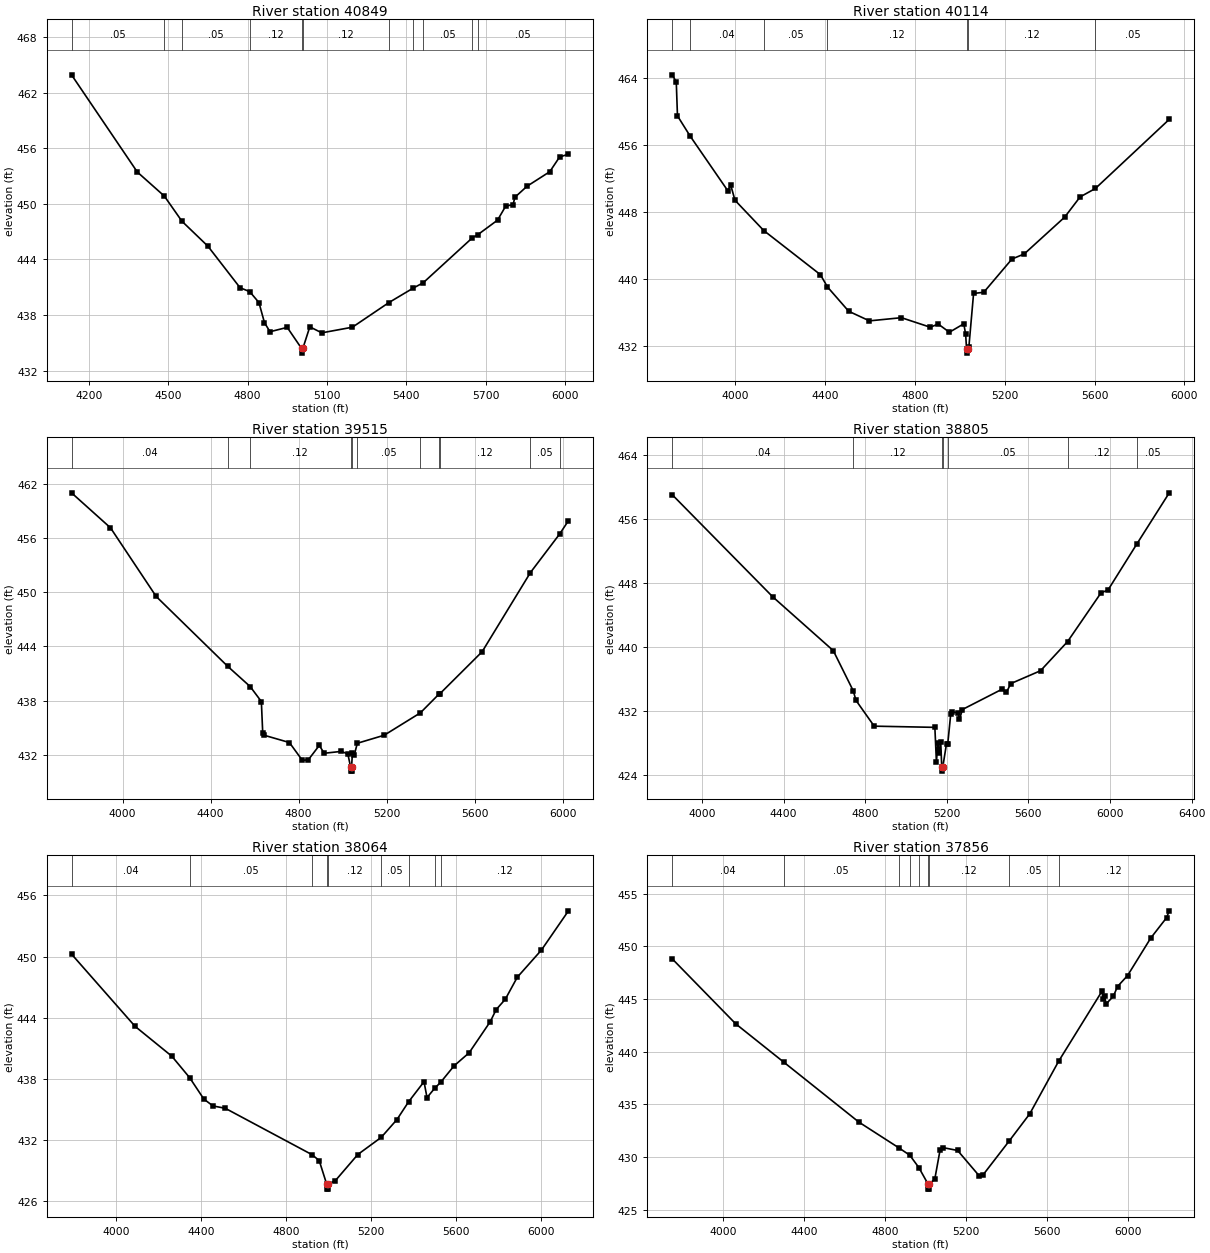
Type RM Length L Ch R = 1,40849,735,735,735
BEGIN DESCRIPTION:
Mapping XS e3a6d8dd
END DESCRIPTION:
XS GIS Cut Line= 3
      2412503.12     13585704.66      2411990.91     13584987.57
      2411130.39     13584483.55
#Sta/Elev= 30
  4134.2  463.93  4383.1  453.43  4485.0  450.84  4551.7  448.12  4649.7  445.43
  4771.4  440.94  4807.8  440.52  4842.7  439.34  4863.6  437.17  4884.5  436.19
  4949.6  436.66  5004.0  434.38  5004.3  433.88  5008.6  434.38  5035.0  436.72
  5080.2  436.07  5196.1  436.68  5334.0  439.34  5425.2  440.89  5463.8  441.48
  5649.4  446.33  5670.2  446.67  5744.7  448.24  5775.6  449.76  5803.3  449.91
  5810.3  450.71  5856.2  451.90  5942.1  453.47  5979.3  455.06  6012.7  455.36
#Mann=11,-1,0
  4134.2    0.05       0  4485.0    0.04       0  4551.7    0.05       0
  4807.8    0.12       0  5004.0    0.05       0  5008.6    0.12       0
  5334.0    0.05       0  5425.2    0.12       0  5463.8    0.05       0
  5649.4    0.12       0  5670.2    0.05       0
Bank Sta=5004,5008.6
Exp/Cntr=0.3,0.1

Type RM Length L Ch R = 1,40114,599,599,599
BEGIN DESCRIPTION:
Mapping XS f14038e2
END DESCRIPTION:
XS GIS Cut Line= 4
      2412576.88     13585602.21      2412314.63     13584790.88
      2411925.35     13584487.64      2411139.31     13584123.28
#Sta/Elev= 30
  3719.8  464.43  3737.4  463.56  3742.7  459.52  3798.9  457.11  3966.8  450.56
  3979.6  451.25  3998.8  449.42  4126.8  445.80  4379.0  440.52  4410.5  439.05
  4505.1  436.14  4597.4  434.99  4739.9  435.37  4868.3  434.23  4903.6  434.61
  4953.4  433.63  5017.6  434.64  5025.8  433.37  5029.8  431.63  5030.1  431.13
  5034.5  431.63  5040.2  431.89  5061.1  438.27  5106.4  438.41  5232.0  442.39
  5286.7  443.00  5466.6  447.40  5535.3  449.82  5603.4  450.83  5932.3  459.10
#Mann=7,-1,0
  3719.8    0.05       0  3798.9    0.04       0  4126.8    0.05       0
  4410.5    0.12       0  5029.8    0.05       0  5034.5    0.12       0
  5603.4    0.05       0
Bank Sta=5029.8,5034.5
Exp/Cntr=0.3,0.1

Type RM Length L Ch R = 1,39515,710,710,710
BEGIN DESCRIPTION:
Mapping XS e4b4d37d
END DESCRIPTION:
XS GIS Cut Line= 4
      2412937.48     13585434.19      2412634.26     13584700.73
      2412228.58     13584147.53      2411515.59     13583836.11
#Sta/Elev= 30
  3768.0  461.04  3945.1  457.16  4152.6  449.55  4477.7  441.80  4579.6  439.56
  4630.5  437.90  4636.7  434.43  4643.2  434.16  4757.9  433.35  4816.6  431.38
  4843.6  431.43  4893.8  433.03  4916.0  432.16  4994.1  432.37  5023.4  432.08
  5035.7  430.68  5036.0  430.18  5040.1  430.18  5040.5  430.68  5044.3  432.22
  5052.4  431.95  5066.5  433.27  5188.6  434.16  5352.8  436.64  5439.2  438.76
  5441.2  438.75  5633.5  443.42  5853.0  452.20  5985.6  456.47  6025.7  457.95
#Mann=11,-1,0
  3768.0    0.04       0  4477.7    0.05       0  4579.6    0.12       0
  5035.7    0.05       0  5040.5    0.12       0  5066.5    0.05       0
  5352.8    0.12       0  5439.2    0.05       0  5441.2    0.12       0
  5853.0    0.05       0  5985.6    0.12       0
Bank Sta=5035.7,5040.5
Exp/Cntr=0.3,0.1

Type RM Length L Ch R = 1,38805,741,741,741
BEGIN DESCRIPTION:
Mapping XS ed23847c
END DESCRIPTION:
XS GIS Cut Line= 4
      2412994.86     13585364.57      2412851.44     13584430.28
      2412380.20     13584024.60      2411623.51     13583599.22
#Sta/Elev= 30
  3855.1  459.04  4346.9  446.30  4643.8  439.57  4741.6  434.55  4755.1  433.35
  4844.3  430.13  5141.6  429.98  5149.3  425.60  5155.9  428.06  5163.6  426.79
  5170.2  428.20  5175.4  425.01  5175.7  424.51  5180.3  425.01  5198.7  427.94
  5204.6  427.87  5219.5  431.68  5227.2  431.94  5255.7  431.75  5262.3  430.97
  5276.6  432.21  5470.3  434.74  5492.0  434.34  5513.7  435.45  5659.6  437.06
  5792.0  440.70  5955.8  446.79  5990.2  447.15  6130.4  452.86  6290.2  459.29
#Mann=7,-1,0
  3855.1    0.04       0  4741.6    0.12       0  5175.4    0.05       0
  5180.3    0.12       0  5204.6    0.05       0  5792.0    0.12       0
  6130.4    0.05       0
Bank Sta=5175.4,5180.3
Exp/Cntr=0.3,0.1

Type RM Length L Ch R = 1,38064,208,208,208
BEGIN DESCRIPTION:
LITTLE SALT CREEK 67.0
END DESCRIPTION:
XS GIS Cut Line= 3
      2413025.00     13585024.99      2412925.00     13583825.00
      2412125.01     13583025.01
#Sta/Elev= 30
  3791.3  450.24  4089.8  443.15  4262.9  440.21  4346.3  438.11  4413.4  436.00
  4456.1  435.33  4513.8  435.10  4921.1  430.55  4955.3  429.97  4990.4  427.66
  4990.8  427.16  4995.1  427.16  4995.5  427.66  5030.8  427.98  5136.9  430.56
  5246.7  432.24  5320.7  433.99  5375.6  435.74  5448.0  437.71  5462.1  436.15
  5498.4  437.07  5526.1  437.65  5589.4  439.27  5660.1  440.55  5759.1  443.60
  5787.4  444.80  5829.8  445.80  5886.4  447.97  5999.5  450.63  6126.8  454.49
#Mann=9,-1,0
  3791.3    0.04       0  4346.3    0.05       0  4921.1    0.12       0
  4990.4    0.05       0  4995.5    0.12       0  5246.7    0.05       0
  5375.6    0.12       0  5498.4    0.05       0  5526.1    0.12       0
Bank Sta=4990.4,4995.5
Exp/Cntr=0.3,0.1

Type RM Length L Ch R = 1,37856,642,642,642
BEGIN DESCRIPTION:
Mapping XS e3492b9a
END DESCRIPTION:
XS GIS Cut Line= 4
      2413224.33     13585008.07      2413220.23     13584081.97
      2412982.56     13583393.55      2412352.96     13582898.86
#Sta/Elev= 30
  3749.2  448.81  4062.3  442.65  4299.7  439.01  4671.3  433.31  4866.9  430.89
  4922.4  430.17  4967.1  429.00  5012.0  427.45  5012.4  426.95  5016.7  426.95
  5017.1  427.45  5045.7  427.88  5071.6  430.62  5084.7  430.90  5158.7  430.62
  5264.5  428.23  5284.6  428.31  5414.6  431.55  5515.0  434.10  5657.9  439.10
  5871.1  445.72  5878.1  444.97  5884.4  445.25  5892.5  444.55  5927.8  445.25
  5948.6  446.19  5998.3  447.23  6112.7  450.79  6190.8  452.72  6204.3  453.38
#Mann=9,-1,0
  3749.2    0.04       0  4299.7    0.05       0  4866.9    0.12       0
  4922.4    0.05       0  4967.1    0.12       0  5012.0    0.05       0
  5017.1    0.12       0  5414.6    0.05       0  5657.9    0.12       0
Bank Sta=5012,5017.1
Exp/Cntr=0.3,0.1

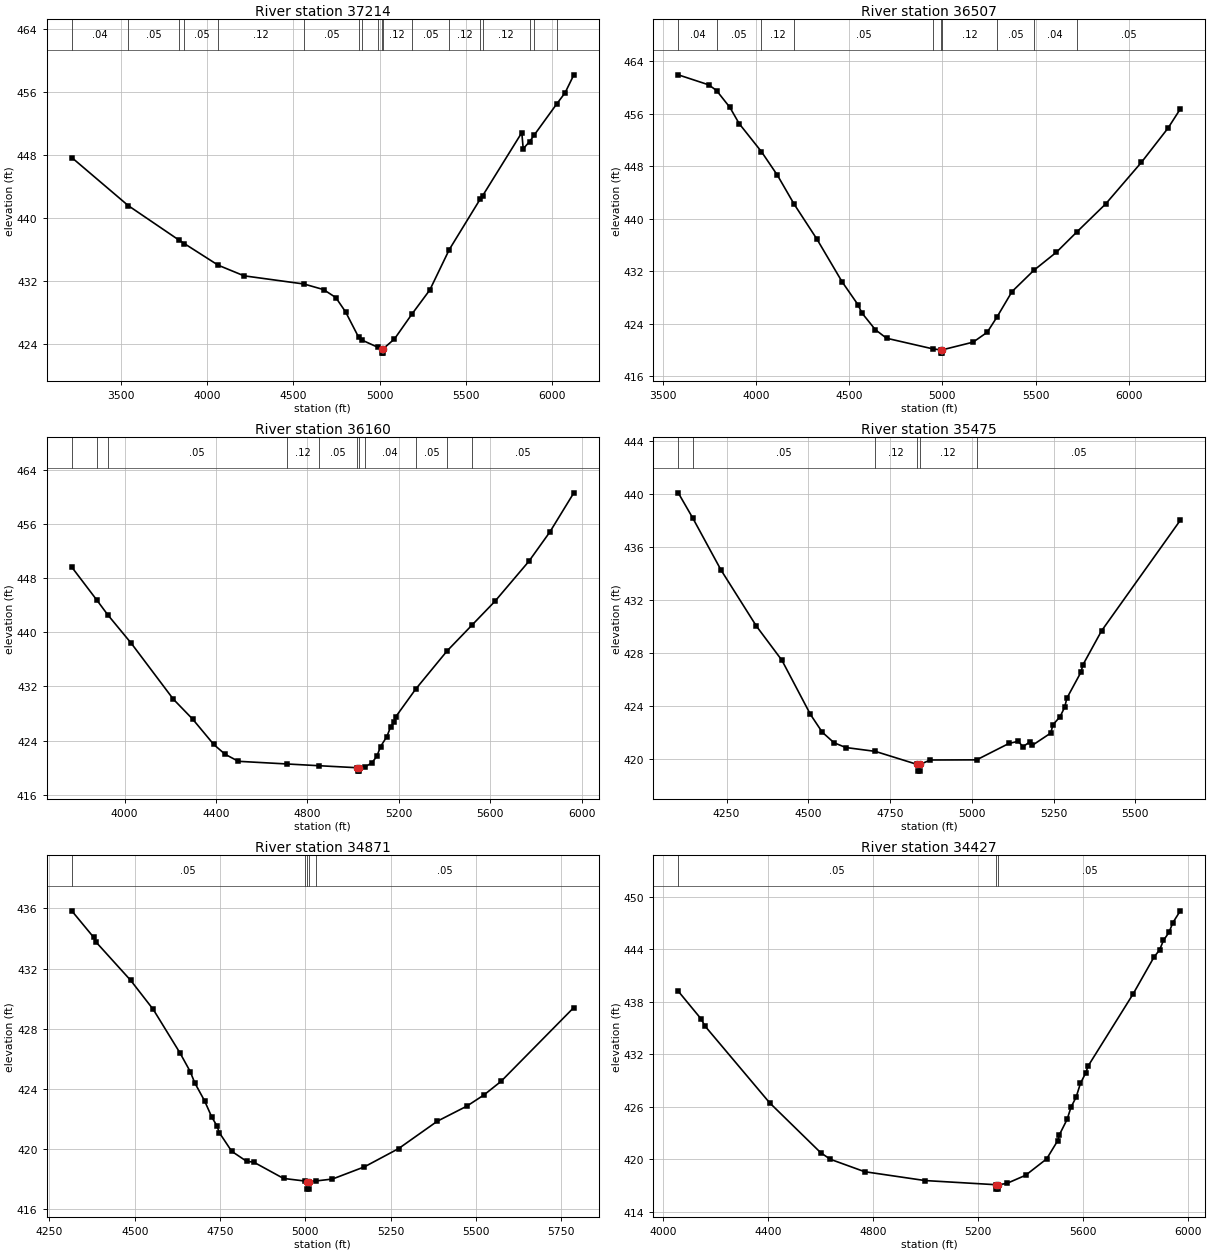
Type RM Length L Ch R = 1,37214,707,707,707
BEGIN DESCRIPTION:
Mapping XS f9a968da
END DESCRIPTION:
XS GIS Cut Line= 4
      2413330.88     13584995.73      2413527.56     13583594.34
      2413068.62     13583114.90      2412351.55     13582696.95
#Sta/Elev= 30
  3215.5  447.70  3542.6  441.59  3839.6  437.16  3868.3  436.75  4063.9  434.01
  4213.7  432.66  4560.7  431.62  4674.3  430.91  4745.1  429.90  4801.7  428.08
  4878.2  424.82  4894.6  424.51  4990.0  423.56  5011.4  423.33  5011.8  422.83
  5016.1  422.83  5016.5  423.33  5084.7  424.62  5186.1  427.79  5289.8  430.86
  5402.4  435.99  5580.7  442.38  5595.8  442.84  5822.8  450.87  5830.9  448.82
  5868.1  449.73  5895.0  450.57  6024.5  454.50  6073.4  455.93  6124.3  458.22
#Mann=18,-1,0
  3215.5    0.04       0  3542.6    0.05       0  3839.6    0.12       0
  3868.3    0.05       0  4063.9    0.12       0  4560.7    0.05       0
  4878.2    0.12       0  4894.6    0.05       0  4990.0    0.12       0
  5011.4    0.05       0  5016.5    0.12       0  5186.1    0.05       0
  5402.4    0.12       0  5580.7    0.05       0  5595.8    0.12       0
  5868.1    0.05       0  5895.0    0.12       0  6024.5    0.05       0
Bank Sta=5011.4,5016.5
Exp/Cntr=0.3,0.1

Type RM Length L Ch R = 1,36507,347,347,347
BEGIN DESCRIPTION:
Mapping XS a45bcbee
END DESCRIPTION:
XS GIS Cut Line= 4
      2414945.40     13584016.42      2414220.08     13583278.81
      2413527.56     13582975.58      2412826.86     13582410.10
#Sta/Elev= 30
  3584.1  461.90  3748.0  460.37  3789.3  459.51  3861.2  456.93  3910.6  454.47
  4030.0  450.20  4115.8  446.60  4204.8  442.22  4327.9  436.85  4462.2  430.38
  4547.1  426.90  4568.2  425.64  4640.5  423.08  4700.5  421.78  4951.5  420.14
  4991.6  420.01  4992.1  419.51  4998.4  419.51  4998.9  420.01  5164.3  421.18
  5239.9  422.68  5291.8  424.98  5373.2  428.89  5489.9  432.12  5611.0  434.88
  5719.2  437.93  5874.8  442.23  6066.8  448.58  6209.1  453.78  6275.0  456.70
#Mann=10,-1,0
  3584.1    0.04       0  3789.3    0.05       0  4030.0    0.12       0
  4204.8    0.05       0  4951.5    0.12       0  4991.6    0.05       0
  4998.9    0.12       0  5291.8    0.05       0  5489.9    0.04       0
  5719.2    0.05       0
Bank Sta=4991.6,4998.9
Exp/Cntr=0.3,0.1

Type RM Length L Ch R = 1,36160,685,685,685
BEGIN DESCRIPTION:
Mapping XS da7876de
END DESCRIPTION:
XS GIS Cut Line= 4
      2414720.01     13583577.96      2414248.76     13583065.73
      2413281.70     13582557.61      2413007.16     13582254.38
#Sta/Elev= 30
  3768.7  449.62  3878.6  444.74  3926.8  442.55  4029.3  438.36  4213.1  430.12
  4298.1  427.16  4390.0  423.43  4439.3  421.99  4497.9  420.94  4708.6  420.55
  4850.2  420.29  5018.8  419.99  5019.3  419.49  5025.7  419.49  5026.2  419.99
  5051.2  420.09  5081.8  420.70  5103.9  421.68  5120.3  423.12  5148.0  424.60
  5164.4  426.05  5180.6  426.73  5186.4  427.50  5273.7  431.59  5411.1  437.23
  5520.8  441.07  5620.3  444.55  5769.0  450.46  5860.9  454.79  5966.2  460.59
#Mann=11,-1,0
  3768.7    0.05       0  3878.6    0.12       0  3926.8    0.05       0
  4708.6    0.12       0  4850.2    0.05       0  5018.8    0.05       0
  5026.2    0.05       0  5051.2    0.04       0  5273.7    0.05       0
  5411.1    0.04       0  5520.8    0.05       0
Bank Sta=5018.8,5026.2
Exp/Cntr=0.3,0.1

Type RM Length L Ch R = 1,35475,604,604,604
BEGIN DESCRIPTION:
LITTLE SALT CREEK 63.0
END DESCRIPTION:
XS GIS Cut Line= 3
      2414725.02     13583275.02      2414325.00     13582675.00
      2413724.98     13582124.99
#Sta/Elev= 30
  4102.3  440.11  4146.9  438.20  4233.0  434.29  4341.2  430.06  4419.3  427.48
  4506.4  423.40  4542.5  422.06  4578.6  421.26  4614.6  420.90  4704.8  420.61
  4833.6  419.62  4834.1  419.12  4840.6  419.12  4841.1  419.62  4873.1  419.96
  5014.6  419.97  5113.6  421.21  5141.9  421.37  5156.1  420.96  5177.1  421.32
  5184.5  421.06  5241.2  421.99  5248.0  422.62  5269.6  423.22  5283.7  423.93
  5290.5  424.62  5333.1  426.56  5339.9  427.15  5396.6  429.70  5637.4  438.04
#Mann=6,-1,0
  4102.3    0.12       0  4146.9    0.05       0  4704.8    0.12       0
  4833.6    0.05       0  4841.1    0.12       0  5014.6    0.05       0
Bank Sta=4833.6,4841.1
Exp/Cntr=0.3,0.1

Type RM Length L Ch R = 1,34871,444,444,444
BEGIN DESCRIPTION:
LITTLE SALT CREEK 62.0
END DESCRIPTION:
XS GIS Cut Line= 3
      2415124.97     13583074.96      2414725.00     13582475.00
      2414124.97     13582024.98
#Sta/Elev= 30
  4315.4  435.83  4379.9  434.06  4387.5  433.73  4488.1  431.21  4554.2  429.28
  4632.3  426.40  4662.4  425.16  4675.9  424.40  4704.4  423.22  4725.5  422.14
  4740.5  421.56  4748.0  421.09  4784.1  419.86  4827.6  419.20  4848.7  419.14
  4935.8  418.06  4997.4  417.89  5004.1  417.85  5004.6  417.35  5011.2  417.35
  5011.7  417.85  5029.9  417.89  5079.2  418.02  5172.9  418.83  5272.9  420.04
  5386.5  421.86  5472.9  422.86  5522.9  423.60  5572.9  424.50  5786.5  429.41
#Mann=5,-1,0
  4315.4    0.05       0  4997.4    0.12       0  5004.1    0.05       0
  5011.7    0.12       0  5029.9    0.05       0
Bank Sta=5004.1,5011.7
Exp/Cntr=0.3,0.1

Type RM Length L Ch R = 1,34427,480,480,480
BEGIN DESCRIPTION:
LITTLE SALT CREEK 61.0
END DESCRIPTION:
XS GIS Cut Line= 3
      2415825.01     13582675.01      2415025.00     13582175.00
      2414475.02     13581375.03
#Sta/Elev= 30
  4057.1  439.20  4143.8  436.05  4159.1  435.22  4405.6  426.46  4600.2  420.77
  4636.7  420.02  4767.6  418.60  4997.6  417.59  5269.9  417.11  5270.4  416.61
  5277.3  416.61  5277.8  417.11  5309.7  417.26  5381.4  418.19  5461.7  420.06
  5503.9  422.14  5510.2  422.81  5539.7  424.57  5554.6  425.96  5574.2  427.11
  5590.5  428.68  5611.4  429.91  5619.4  430.64  5790.7  438.85  5871.2  443.10
  5892.2  443.90  5907.1  445.00  5928.0  445.90  5942.9  447.02  5971.3  448.37
#Mann=3,-1,0
  4057.1    0.05       0  5269.9    0.05       0  5277.8    0.05       0
Bank Sta=5269.9,5277.8
Exp/Cntr=0.3,0.1

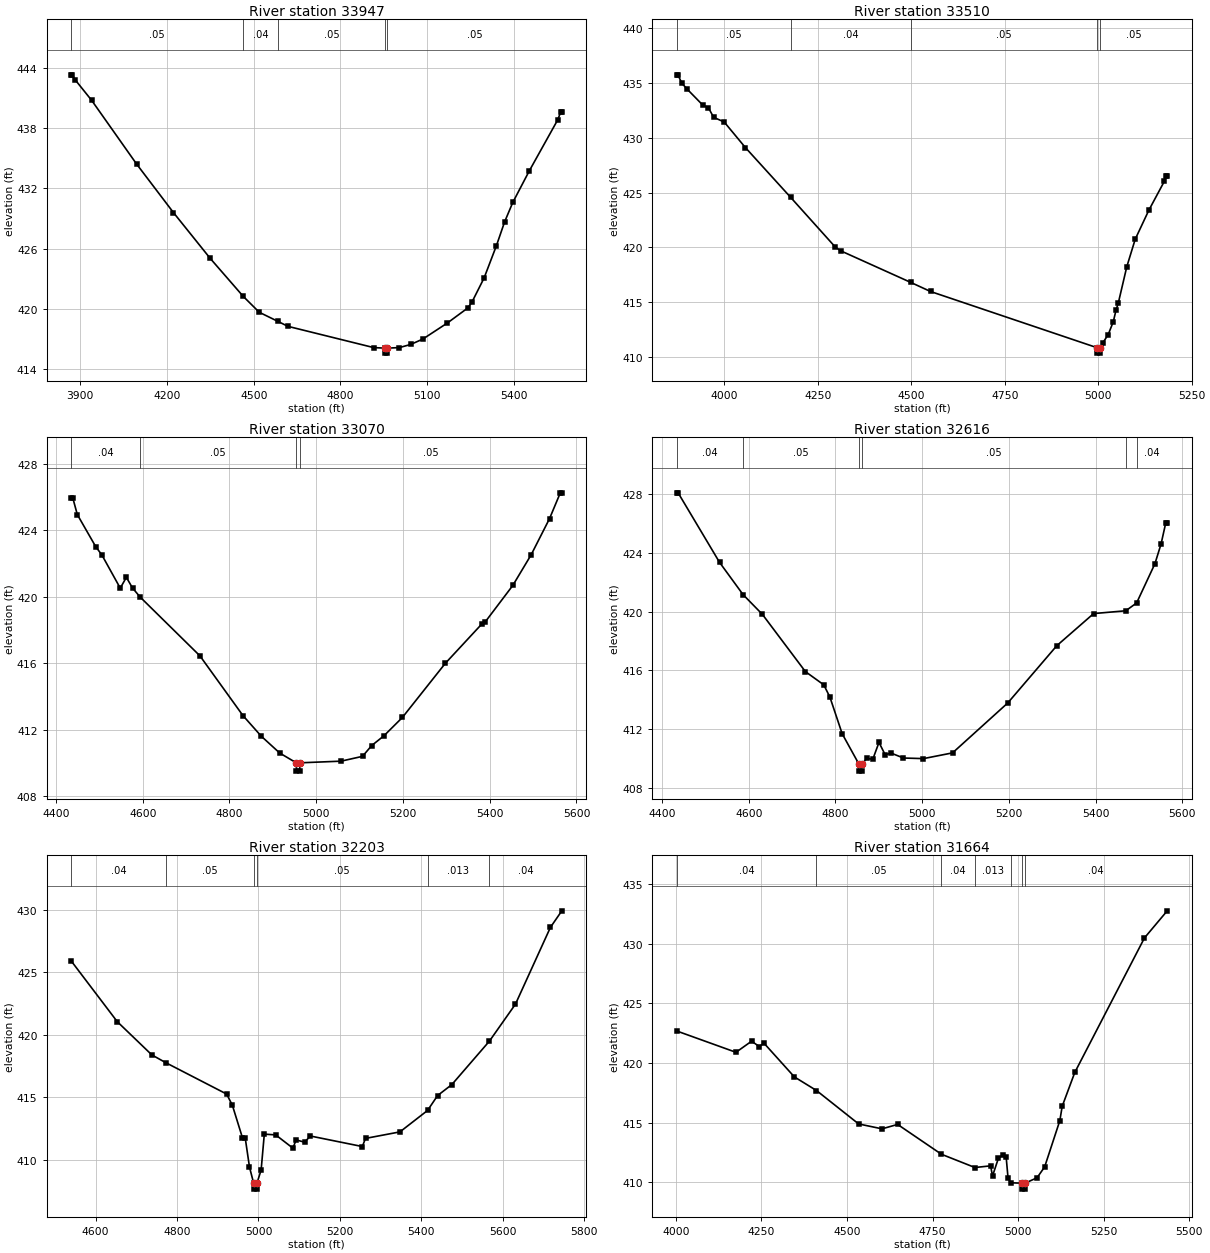
Type RM Length L Ch R = 1,33947,437,437,437
BEGIN DESCRIPTION:
LITTLE SALT CREEK 60.0
END DESCRIPTION:
XS GIS Cut Line= 3
      2415974.98     13582574.98      2415175.00     13581775.00
      2414775.02     13581375.02
#Sta/Elev= 30
  3868.7  443.32  3872.2  443.32  3882.8  442.81  3939.4  440.78  4094.9  434.43
  4222.2  429.60  4349.5  425.03  4463.6  421.25  4519.2  419.66  4583.9  418.75
  4618.2  418.26  4915.2  416.14  4953.5  416.09  4954.0  415.59  4961.2  415.59
  4961.7  416.09  5003.6  416.14  5042.5  416.45  5084.9  416.99  5169.7  418.59
  5240.5  420.09  5254.6  420.66  5297.0  423.09  5339.4  426.29  5367.7  428.66
  5396.0  430.60  5452.6  433.72  5551.6  438.84  5562.2  439.64  5565.7  439.64
#Mann=5,-1,0
  3868.7    0.05       0  4463.6    0.04       0  4583.9    0.05       0
  4953.5    0.05       0  4961.7    0.05       0
Bank Sta=4953.5,4961.7
Exp/Cntr=0.3,0.1

Type RM Length L Ch R = 1,33510,440,440,440
BEGIN DESCRIPTION:
LITTLE SALT CREEK 59.0
END DESCRIPTION:
XS GIS Cut Line= 3
      2416074.99     13582174.99      2415275.00     13581375.00
      2415125.02     13581275.02
#Sta/Elev= 30
  3872.9  435.76  3876.4  435.76  3887.0  434.99  3901.2  434.45  3943.6  432.97
  3957.7  432.77  3971.9  431.88  4000.2  431.45  4056.7  429.12  4178.0  424.56
  4297.1  420.03  4311.3  419.69  4498.2  416.81  4551.7  415.97  4996.6  410.84
  4997.1  410.34  5004.4  410.34  5004.9  410.84  5007.3  410.84  5011.8  411.25
  5026.8  412.04  5040.3  413.21  5047.8  414.29  5053.8  414.93  5076.4  418.23
  5098.9  420.74  5135.0  423.37  5177.0  426.05  5181.5  426.54  5184.5  426.54
#Mann=5,-1,0
  3872.9    0.05       0  4178.0    0.04       0  4498.2    0.05       0
  4996.6    0.05       0  5004.9    0.05       0
Bank Sta=4996.6,5004.9
Exp/Cntr=0.3,0.1

Type RM Length L Ch R = 1,33070,454,454,454
BEGIN DESCRIPTION:
LITTLE SALT CREEK 58.0
END DESCRIPTION:
XS GIS Cut Line= 3
      2416074.97     13581674.97      2415675.00     13581275.00
      2415275.02     13580875.02
#Sta/Elev= 30
  4435.0  425.97  4438.5  425.97  4449.1  424.95  4491.5  423.02  4505.7  422.52
  4548.1  420.52  4562.2  421.17  4576.4  420.53  4593.7  419.99  4731.9  416.44
  4830.9  412.85  4873.4  411.60  4915.8  410.59  4954.0  410.00  4954.5  409.50
  4961.9  409.50  4962.4  410.00  5057.2  410.10  5106.7  410.39  5127.9  411.04
  5156.2  411.63  5198.6  412.73  5297.6  415.99  5382.5  418.38  5389.5  418.48
  5453.2  420.68  5495.6  422.53  5538.0  424.71  5562.8  426.26  5566.3  426.26
#Mann=4,-1,0
  4435.0    0.04       0  4593.7    0.05       0  4954.0    0.05       0
  4962.4    0.05       0
Bank Sta=4954,4962.4
Exp/Cntr=0.3,0.1

Type RM Length L Ch R = 1,32616,413,413,413
BEGIN DESCRIPTION:
LITTLE SALT CREEK 57.0
END DESCRIPTION:
XS GIS Cut Line= 3
      2416324.99     13581374.99      2415925.00     13580975.00
      2415524.97     13580574.97
#Sta/Elev= 30
  4433.6  428.06  4437.1  428.06  4532.6  423.34  4586.8  421.15  4631.6  419.80
  4730.6  415.92  4773.0  415.02  4787.1  414.19  4815.4  411.70  4853.6  409.66
  4854.1  409.16  4861.6  409.16  4862.1  409.66  4872.0  410.02  4886.1  409.97
  4900.3  411.11  4914.4  410.28  4928.6  410.38  4956.8  410.05  5002.8  410.01
  5070.0  410.40  5197.3  413.79  5310.4  417.68  5395.3  419.86  5469.4  420.05
  5494.4  420.58  5536.7  423.25  5550.8  424.59  5561.4  425.99  5565.0  425.99
#Mann=6,-1,0
  4433.6    0.04       0  4586.8    0.05       0  4853.6    0.05       0
  4862.1    0.05       0  5469.4   0.013       0  5494.4    0.04       0
Bank Sta=4853.6,4862.1
Exp/Cntr=0.3,0.1

Type RM Length L Ch R = 1,32203,539,539,539
BEGIN DESCRIPTION:
LITTLE SALT CREEK 56.0
END DESCRIPTION:
XS GIS Cut Line= 3
      2416525.02     13581175.02      2416225.00     13580875.00
      2415625.01     13580375.01
#Sta/Elev= 30
  4539.9  425.90  4653.1  421.05  4737.9  418.40  4772.0  417.78  4921.8  415.27
  4935.9  414.37  4960.7  411.77  4967.4  411.77  4977.9  409.44  4987.9  408.18
  4988.4  407.68  4996.0  407.68  4996.5  408.18  5006.5  409.21  5014.3  412.07
  5042.3  412.01  5084.6  410.95  5092.4  411.61  5113.2  411.43  5127.6  411.92
  5255.1  411.08  5262.9  411.73  5347.5  412.25  5415.3  413.96  5440.0  415.15
  5475.1  416.03  5567.4  419.50  5631.3  422.45  5717.2  428.58  5745.2  429.90
#Mann=6,-1,0
  4539.9    0.04       0  4772.0    0.05       0  4987.9    0.05       0
  4996.5    0.05       0  5415.3   0.013       0  5567.4    0.04       0
Bank Sta=4987.9,4996.5
Exp/Cntr=0.3,0.1

Type RM Length L Ch R = 1,31664,144,144,144
BEGIN DESCRIPTION:
Mapping XS 231ced30
END DESCRIPTION:
XS GIS Cut Line= 4
      2416875.56     13580874.65      2416268.75     13580588.17
      2415836.46     13580379.84      2415565.61     13580301.71
#Sta/Elev= 30
  4002.4  422.69  4175.8  420.90  4221.4  421.83  4244.1  421.38  4257.4  421.67
  4346.3  418.84  4410.9  417.70  4534.0  414.90  4602.3  414.49  4647.8  414.86
  4775.9  412.36  4873.6  411.25  4919.4  411.39  4925.0  410.54  4942.0  412.01
  4955.1  412.33  4964.7  412.17  4970.2  410.41  4977.7  409.97  5010.8  409.94
  5011.3  409.44  5019.6  409.44  5020.1  409.94  5055.0  410.39  5077.2  411.30
  5121.6  415.18  5128.5  416.38  5165.2  419.21  5368.7  430.48  5435.2  432.75
#Mann=7,-1,0
  4002.4    0.04       0  4410.9    0.05       0  4775.9    0.04       0
  4873.6   0.013       0  4977.7    0.04       0  5010.8    0.04       0
  5020.1    0.04       0
Bank Sta=5010.8,5020.1
Exp/Cntr=0.3,0.1