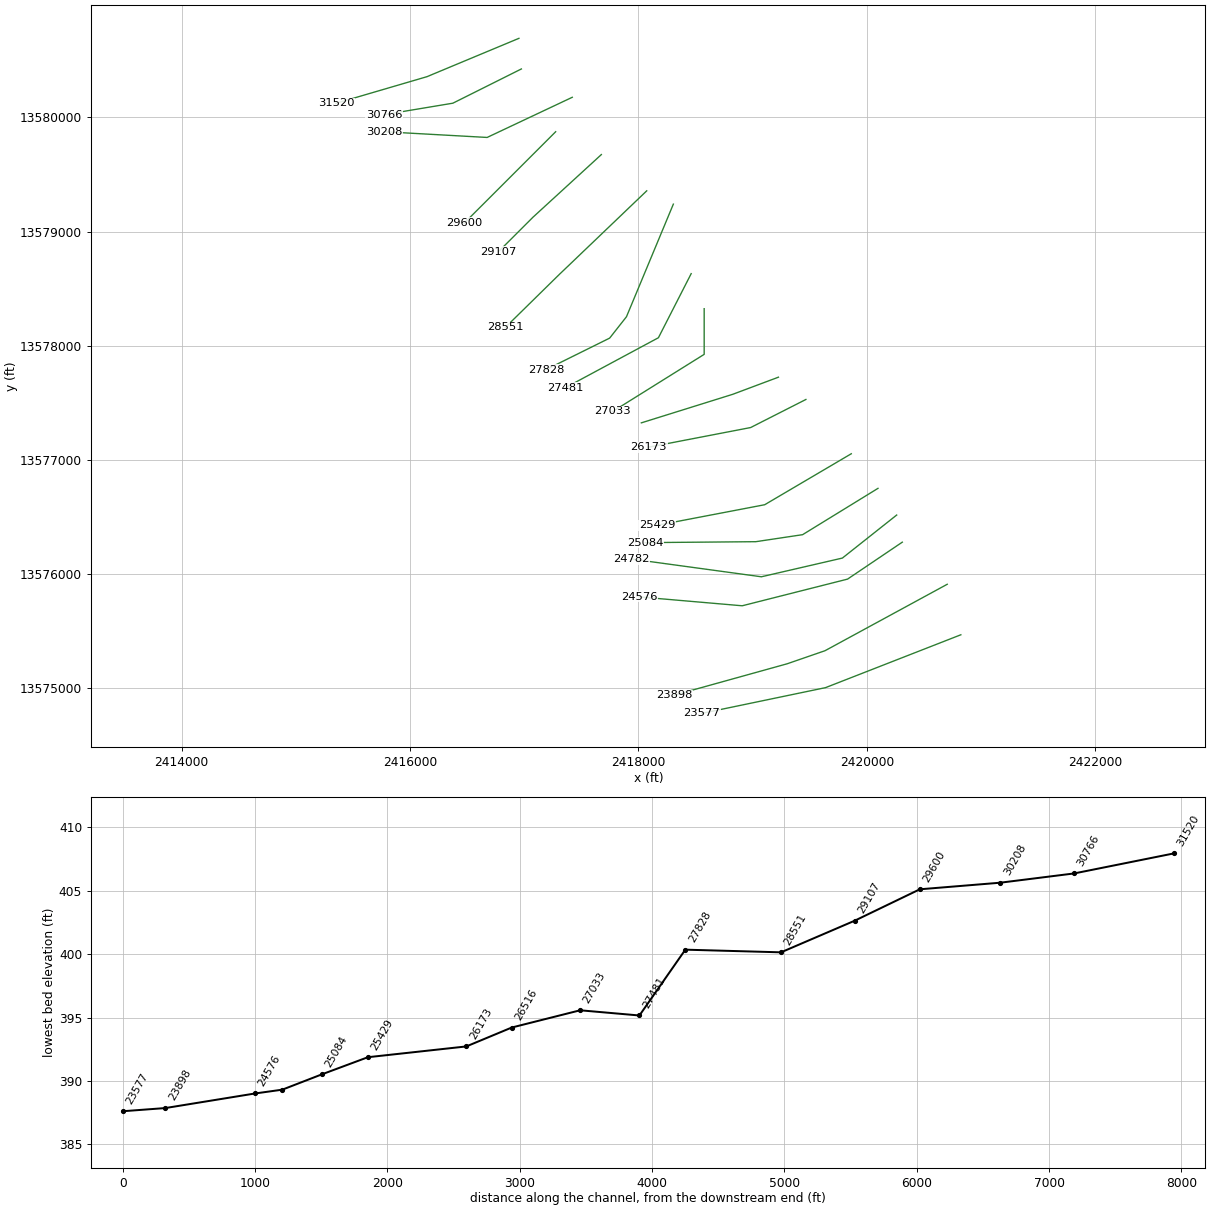
HEC-RAS study LITTLE SALT CREEK.prj: LITTLE SALT CREEK Base Level Engineering

--- LITTLE SALT CREEK.g01 (geometry) --- (continued)

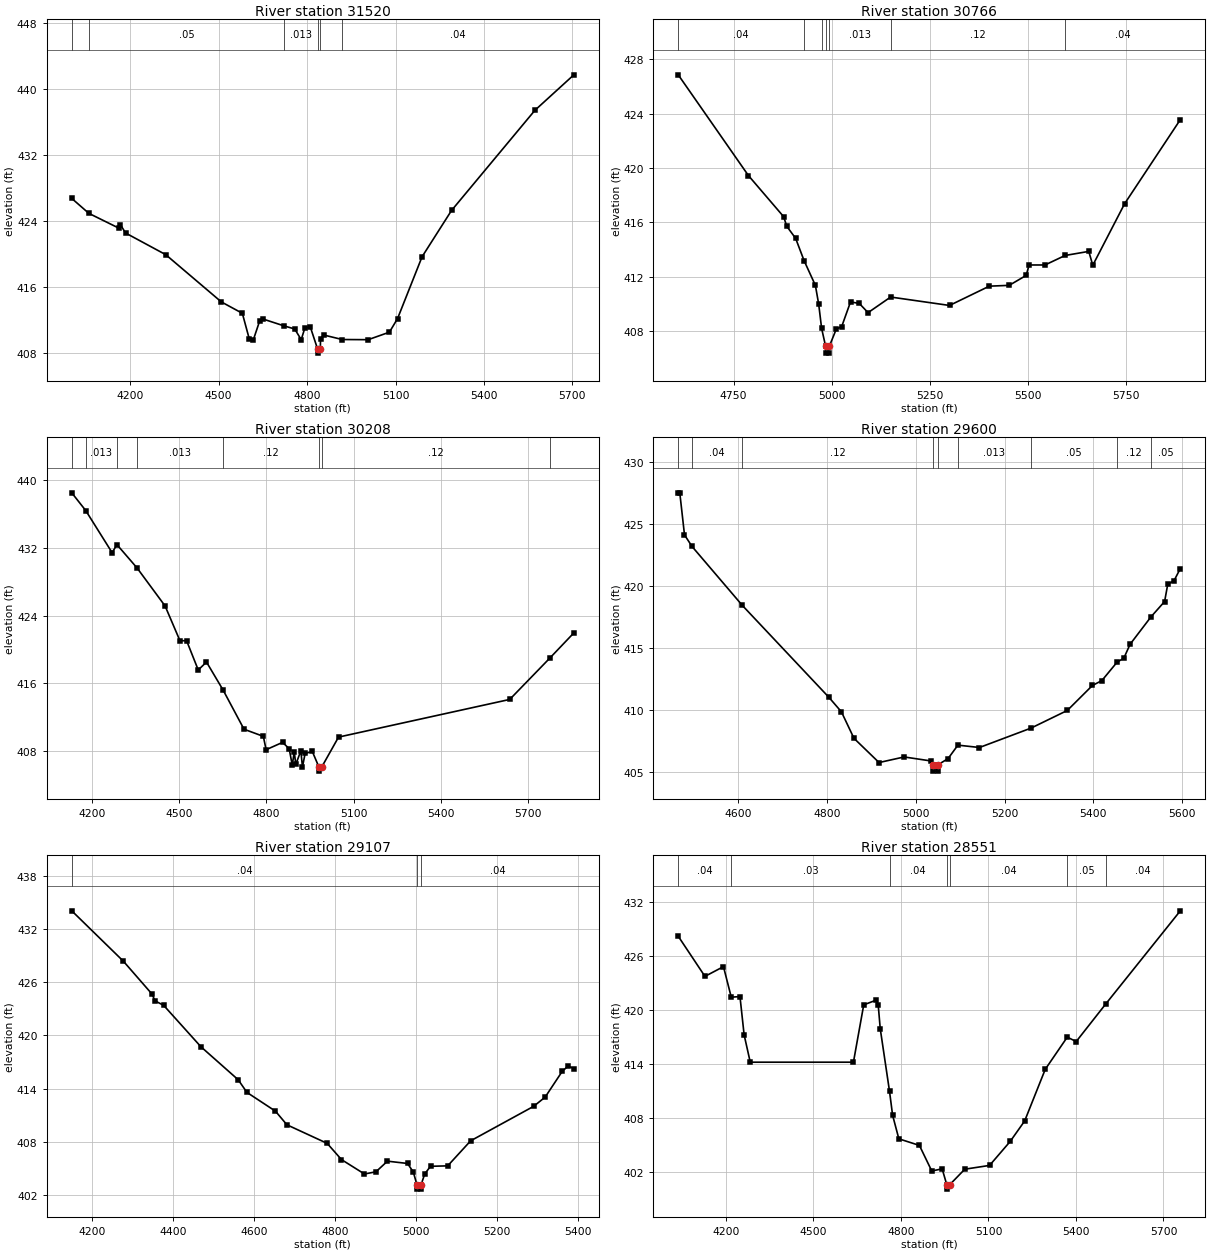
Type RM Length L Ch R = 1,31520,754,754,754
BEGIN DESCRIPTION:
Mapping XS f820bb47
END DESCRIPTION:
XS GIS Cut Line= 3
      2416953.29     13580693.15      2416148.81     13580357.42
      2415351.01     13580123.54
#Sta/Elev= 30
  4001.7  426.70  4059.7  424.89  4161.3  423.10  4166.7  423.52  4184.1  422.51
  4320.5  419.88  4509.1  414.15  4580.3  412.77  4604.2  409.61  4617.5  409.54
  4639.2  411.86  4650.0  412.08  4723.0  411.23  4757.9  410.87  4780.0  409.57
  4792.6  411.02  4811.0  411.10  4835.5  408.44  4836.0  407.94  4844.8  408.44
  4845.6  409.70  4855.9  410.14  4919.2  409.59  5007.0  409.57  5079.1  410.48
  5106.7  412.12  5190.0  419.63  5289.9  425.24  5572.8  437.39  5704.8  441.69
#Mann=6,-1,0
  4001.7    0.04       0  4059.7    0.05       0  4723.0   0.013       0
  4835.5    0.04       0  4844.8   0.013       0  4919.2    0.04       0
Bank Sta=4835.5,4844.8
Exp/Cntr=0.3,0.1

Type RM Length L Ch R = 1,30766,558,558,558
BEGIN DESCRIPTION:
LITTLE SALT CREEK 54.0
END DESCRIPTION:
XS GIS Cut Line= 3
      2416975.02     13580425.01      2416375.00     13580125.00
      2415775.02     13580025.00
#Sta/Elev= 30
  4608.8  426.85  4787.7  419.43  4877.2  416.41  4885.5  415.69  4907.9  414.81
  4929.4  413.17  4958.2  411.35  4966.6  409.97  4974.1  408.18  4984.3  406.86
  4984.8  406.36  4993.2  406.36  4993.7  406.86  5011.3  408.12  5025.3  408.32
  5047.7  410.13  5070.0  410.02  5092.4  409.34  5149.9  410.49  5299.9  409.87
  5401.3  411.29  5452.0  411.35  5495.1  412.08  5502.7  412.85  5543.2  412.85
  5594.4  413.55  5654.7  413.85  5664.9  412.83  5746.0  417.36  5887.9  423.55
#Mann=7,-1,0
  4608.8    0.04       0  4929.4    0.05       0  4974.1   0.013       0
  4984.3    0.03       0  4993.7   0.013       0  5149.9    0.12       0
  5594.4    0.04       0
Bank Sta=4984.3,4993.7
Exp/Cntr=0.3,0.1

Type RM Length L Ch R = 1,30208,608,608,608
BEGIN DESCRIPTION:
LITTLE SALT CREEK 53.0
END DESCRIPTION:
XS GIS Cut Line= 3
      2417420.41     13580176.82      2416675.00     13579825.00
      2415774.95     13579875.00
#Sta/Elev= 30
  4131.4  438.51  4179.3  436.42  4270.1  431.44  4286.6  432.39  4355.9  429.63
  4452.2  425.14  4503.3  421.03  4526.1  421.04  4566.1  417.58  4594.4  418.52
  4651.7  415.20  4723.4  410.58  4789.8  409.74  4799.4  408.16  4856.1  409.03
  4878.7  408.27  4889.3  406.33  4896.0  407.92  4901.5  406.42  4918.7  408.03
  4924.3  406.13  4933.5  407.72  4958.2  407.95  4980.7  406.13  4981.2  405.63
  4990.8  406.13  5048.3  409.65  5636.7  414.10  5774.7  418.99  5857.1  421.96
#Mann=8,-1,0
  4131.4    0.04       0  4179.3   0.013       0  4286.6    0.04       0
  4355.9   0.013       0  4651.7    0.12       0  4980.7    0.05       0
  4990.8    0.12       0  5774.7    0.04       0
Bank Sta=4980.7,4990.8
Exp/Cntr=0.3,0.1

Type RM Length L Ch R = 1,29600,493,493,493
BEGIN DESCRIPTION:
LITTLE SALT CREEK 52.0
END DESCRIPTION:
XS GIS Cut Line= 3
      2417274.99     13579874.99      2416875.00     13579475.00
      2416474.97     13579074.97
#Sta/Elev= 30
  4464.7  427.49  4468.2  427.49  4478.8  424.11  4495.7  423.18  4609.3  418.43
  4804.1  411.05  4832.4  409.88  4860.7  407.75  4917.2  405.80  4973.8  406.25
  5033.9  405.93  5039.4  405.61  5039.9  405.11  5049.1  405.11  5049.6  405.61
  5072.8  406.12  5094.9  407.20  5143.5  407.01  5259.7  408.57  5341.5  409.99
  5398.1  412.00  5419.3  412.39  5453.8  413.88  5468.8  414.19  5482.9  415.31
  5530.1  417.52  5560.7  418.75  5567.8  420.14  5581.9  420.42  5596.1  421.40
#Mann=9,-1,0
  4464.7   0.013       0  4495.7    0.04       0  4609.3    0.12       0
  5039.4    0.05       0  5049.6    0.12       0  5094.9   0.013       0
  5259.7    0.05       0  5453.8    0.12       0  5530.1    0.05       0
Bank Sta=5039.4,5049.6
Exp/Cntr=0.3,0.1

Type RM Length L Ch R = 1,29107,556,556,556
BEGIN DESCRIPTION:
LITTLE SALT CREEK 51.0
END DESCRIPTION:
XS GIS Cut Line= 3
      2417675.02     13579675.02      2417075.00     13579125.00
      2416775.03     13578825.03
#Sta/Elev= 30
  4150.6  434.08  4278.0  428.38  4348.9  424.65  4355.7  423.91  4377.2  423.40
  4469.1  418.72  4561.0  414.99  4582.6  413.56  4652.9  411.44  4681.2  409.90
  4780.5  407.80  4815.7  405.97  4872.4  404.34  4900.8  404.59  4929.1  405.79
  4978.7  405.53  4992.9  404.56  5001.8  403.13  5002.3  402.63  5011.6  402.63
  5012.1  403.13  5021.1  404.35  5035.3  405.21  5077.7  405.26  5134.3  408.09
  5289.8  411.99  5318.1  413.03  5360.6  415.97  5374.7  416.53  5388.8  416.26
#Mann=3,-1,0
  4150.6    0.04       0  5001.8    0.04       0  5012.1    0.04       0
Bank Sta=5001.8,5012.1
Exp/Cntr=0.3,0.1

Type RM Length L Ch R = 1,28551,723,723,723
BEGIN DESCRIPTION:
Mapping XS a845733e
END DESCRIPTION:
XS GIS Cut Line= 3
      2418071.98     13579357.31      2417305.68     13578623.78
      2416834.41     13578160.71
#Sta/Elev= 30
  4036.3  428.19  4127.9  423.74  4191.4  424.82  4218.1  421.43  4248.0  421.50
  4262.2  417.26  4283.2  414.22  4637.0  414.22  4672.3  420.58  4714.7  421.10
  4722.0  420.55  4728.9  417.94  4760.7  411.00  4771.3  408.34  4792.7  405.72
  4863.2  404.99  4905.6  402.15  4941.2  402.39  4957.0  400.64  4957.5  400.14
  4967.5  400.64  5018.8  402.35  5103.8  402.77  5174.5  405.43  5224.1  407.70
  5294.7  413.43  5370.2  417.00  5400.8  416.51  5502.9  420.71  5757.8  431.01
#Mann=7,-1,0
  4036.3    0.04       0  4218.1    0.03       0  4760.7    0.04       0
  4957.0    0.04       0  4967.5    0.04       0  5370.2    0.05       0
  5502.9    0.04       0
Bank Sta=4957,4967.5
Exp/Cntr=0.3,0.1

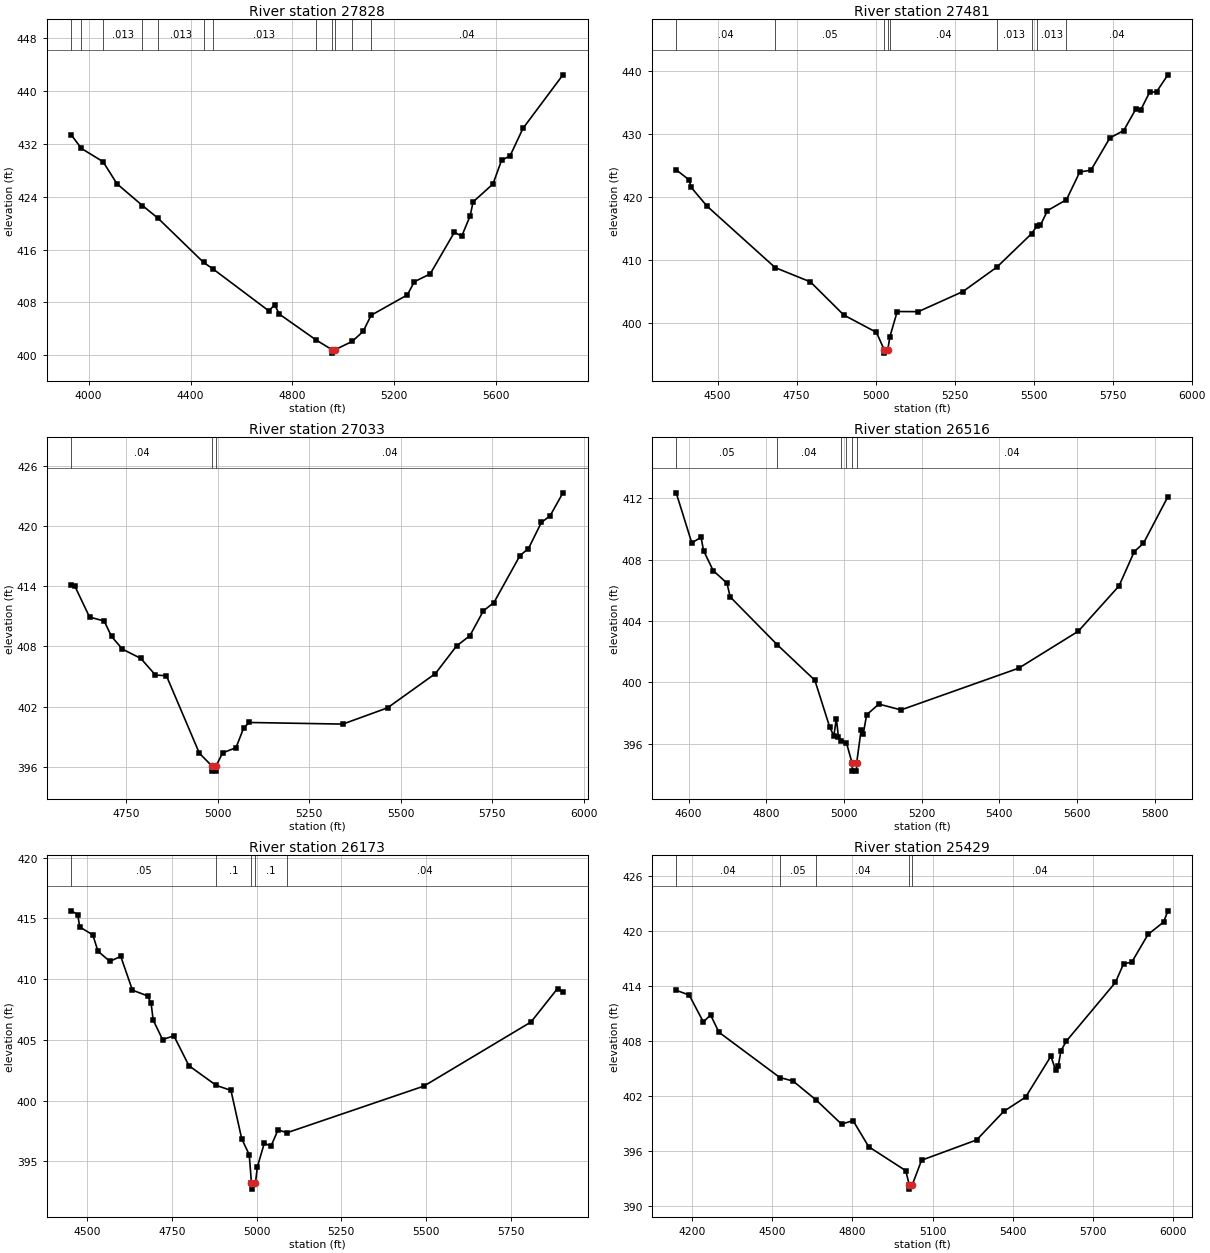
Type RM Length L Ch R = 1,27828,347,347,347
BEGIN DESCRIPTION:
Mapping XS 9a219bdb
END DESCRIPTION:
XS GIS Cut Line= 4
      2418305.12     13579240.77      2417894.84     13578254.62
      2417747.65     13578067.33      2417189.13     13577790.42
#Sta/Elev= 30
  3931.9  433.33  3972.0  431.27  4056.8  429.27  4111.4  425.93  4211.5  422.64
  4272.8  420.72  4451.0  414.06  4488.9  413.05  4707.1  406.74  4730.2  407.64
  4748.7  406.24  4891.6  402.37  4955.8  400.85  4956.3  400.35  4966.5  400.85
  5034.5  402.12  5077.4  403.63  5108.7  406.07  5250.7  409.14  5278.7  411.15
  5340.4  412.31  5435.6  418.62  5464.4  418.02  5497.3  421.09  5509.0  423.20
  5587.0  425.91  5620.7  429.49  5654.1  430.16  5704.7  434.31  5861.6  442.40
#Mann=12,-1,0
  3931.9   0.013       0  3972.0    0.04       0  4056.8   0.013       0
  4211.5    0.04       0  4272.8   0.013       0  4451.0    0.04       0
  4488.9   0.013       0  4891.6    0.04       0  4955.8    0.04       0
  4966.5    0.04       0  5034.5   0.013       0  5108.7    0.04       0
Bank Sta=4955.8,4966.5
Exp/Cntr=0.3,0.1

Type RM Length L Ch R = 1,27481,448,448,448
BEGIN DESCRIPTION:
Mapping XS 4697703a
END DESCRIPTION:
XS GIS Cut Line= 3
      2418461.22     13578631.95      2418174.40     13578070.59
      2417359.51     13577632.44
#Sta/Elev= 30
  4369.2  424.29  4410.5  422.67  4416.1  421.53  4466.8  418.51  4682.3  408.75
  4793.8  406.48  4899.3  401.22  5002.7  398.46  5027.6  395.66  5028.1  395.16
  5038.4  395.66  5045.5  397.80  5068.4  401.77  5135.2  401.75  5276.2  404.94
  5384.1  408.84  5494.0  414.16  5509.6  415.29  5521.2  415.45  5543.9  417.81
  5604.0  419.55  5646.1  423.95  5681.2  424.22  5741.2  429.35  5785.1  430.53
  5823.2  433.93  5839.1  433.83  5867.0  436.61  5888.9  436.68  5924.8  439.38
#Mann=9,-1,0
  4369.2    0.04       0  4682.3    0.05       0  5027.6    0.05       0
  5038.4    0.05       0  5045.5    0.04       0  5384.1   0.013       0
  5494.0    0.04       0  5509.6   0.013       0  5604.0    0.04       0
Bank Sta=5027.6,5038.4
Exp/Cntr=0.3,0.1

Type RM Length L Ch R = 1,27033,517,517,517
BEGIN DESCRIPTION:
LITTLE SALT CREEK 46.0
END DESCRIPTION:
XS GIS Cut Line= 3
      2418575.00     13578325.04      2418575.00     13577925.00
      2417775.03     13577425.02
#Sta/Elev= 30
  4600.0  414.12  4610.0  414.00  4650.0  410.93  4690.0  410.54  4710.0  409.00
  4740.0  407.73  4790.0  406.81  4830.0  405.15  4860.0  405.08  4950.0  397.36
  4984.6  396.07  4985.1  395.57  4994.9  395.57  4995.4  396.07  5013.6  397.39
  5050.2  397.91  5071.4  399.91  5086.7  400.42  5342.0  400.26  5464.1  401.88
  5595.0  405.30  5652.7  408.05  5689.3  409.08  5725.9  411.55  5754.8  412.38
  5826.1  417.07  5849.1  417.76  5884.5  420.37  5908.1  421.02  5943.4  423.32
#Mann=3,-1,0
  4600.0    0.04       0  4984.6    0.04       0  4995.4    0.04       0
Bank Sta=4984.6,4995.4
Exp/Cntr=0.3,0.1

Type RM Length L Ch R = 1,26516,343,343,343
BEGIN DESCRIPTION:
LITTLE SALT CREEK 45.0
END DESCRIPTION:
XS GIS Cut Line= 3
      2419225.01     13577725.00      2418825.00     13577575.00
      2418024.96     13577324.99
#Sta/Elev= 30
  4568.2  412.35  4608.3  409.09  4632.3  409.45  4638.5  408.59  4663.4  407.28
  4699.0  406.46  4707.0  405.57  4827.8  402.46  4925.1  400.13  4963.4  397.07
  4974.0  396.51  4980.3  397.64  4985.6  396.46  4993.2  396.20  5006.2  396.07
  5021.1  394.71  5021.6  394.21  5032.0  394.21  5032.5  394.71  5044.1  396.90
  5049.4  396.60  5058.3  397.88  5089.7  398.58  5146.8  398.20  5449.6  400.92
  5603.1  403.33  5707.8  406.28  5747.1  408.52  5770.7  409.06  5833.6  412.10
#Mann=6,-1,0
  4568.2    0.05       0  4827.8    0.04       0  4993.2     0.1       0
  5006.2    0.04       0  5021.1    0.05       0  5032.5    0.04       0
Bank Sta=5021.1,5032.5
Exp/Cntr=0.3,0.1

Type RM Length L Ch R = 1,26173,744,744,744
BEGIN DESCRIPTION:
Mapping XS 918e8daf
END DESCRIPTION:
XS GIS Cut Line= 3
      2419465.22     13577529.71      2418981.65     13577283.82
      2418089.16     13577111.88
#Sta/Elev= 30
  4453.1  415.63  4472.3  415.32  4478.0  414.30  4516.8  413.65  4531.9  412.31
  4567.0  411.47  4599.2  411.88  4633.7  409.10  4678.2  408.63  4688.9  408.01
  4694.9  406.64  4722.7  405.03  4756.0  405.34  4800.5  402.88  4881.0  401.26
  4924.5  400.85  4956.2  396.87  4978.5  395.55  4985.0  393.22  4985.5  392.72
  4996.8  393.22  5002.4  394.54  5022.7  396.48  5043.1  396.28  5063.5  397.60
  5089.7  397.36  5493.9  401.20  5810.3  406.48  5888.4  409.23  5904.5  408.98
#Mann=5,-1,0
  4453.1    0.05       0  4881.0     0.1       0  4985.0    0.05       0
  4996.8     0.1       0  5089.7    0.04       0
Bank Sta=4985,4996.8
Exp/Cntr=0.3,0.1

Type RM Length L Ch R = 1,25429,345,345,345
BEGIN DESCRIPTION:
Mapping XS 75ed79da
END DESCRIPTION:
XS GIS Cut Line= 3
      2419862.65     13577054.34      2419104.58     13576607.70
      2418162.13     13576427.40
#Sta/Elev= 30
  4140.9  413.54  4189.6  413.02  4242.4  410.09  4269.6  410.85  4300.7  408.97
  4528.8  404.03  4578.1  403.65  4665.6  401.55  4759.6  398.95  4802.5  399.34
  4861.1  396.49  4999.7  393.88  5012.4  392.37  5012.9  391.87  5024.5  392.37
  5058.8  395.02  5264.7  397.23  5366.5  400.35  5447.9  401.89  5542.7  406.36
  5559.9  404.86  5570.1  405.26  5580.3  406.96  5600.7  408.01  5783.9  414.39
  5814.5  416.43  5845.0  416.60  5906.1  419.63  5964.3  420.98  5980.3  422.20
#Mann=5,-1,0
  4140.9    0.04       0  4528.8    0.05       0  4665.6    0.04       0
  5012.4    0.04       0  5024.5    0.04       0
Bank Sta=5012.4,5024.5
Exp/Cntr=0.3,0.1

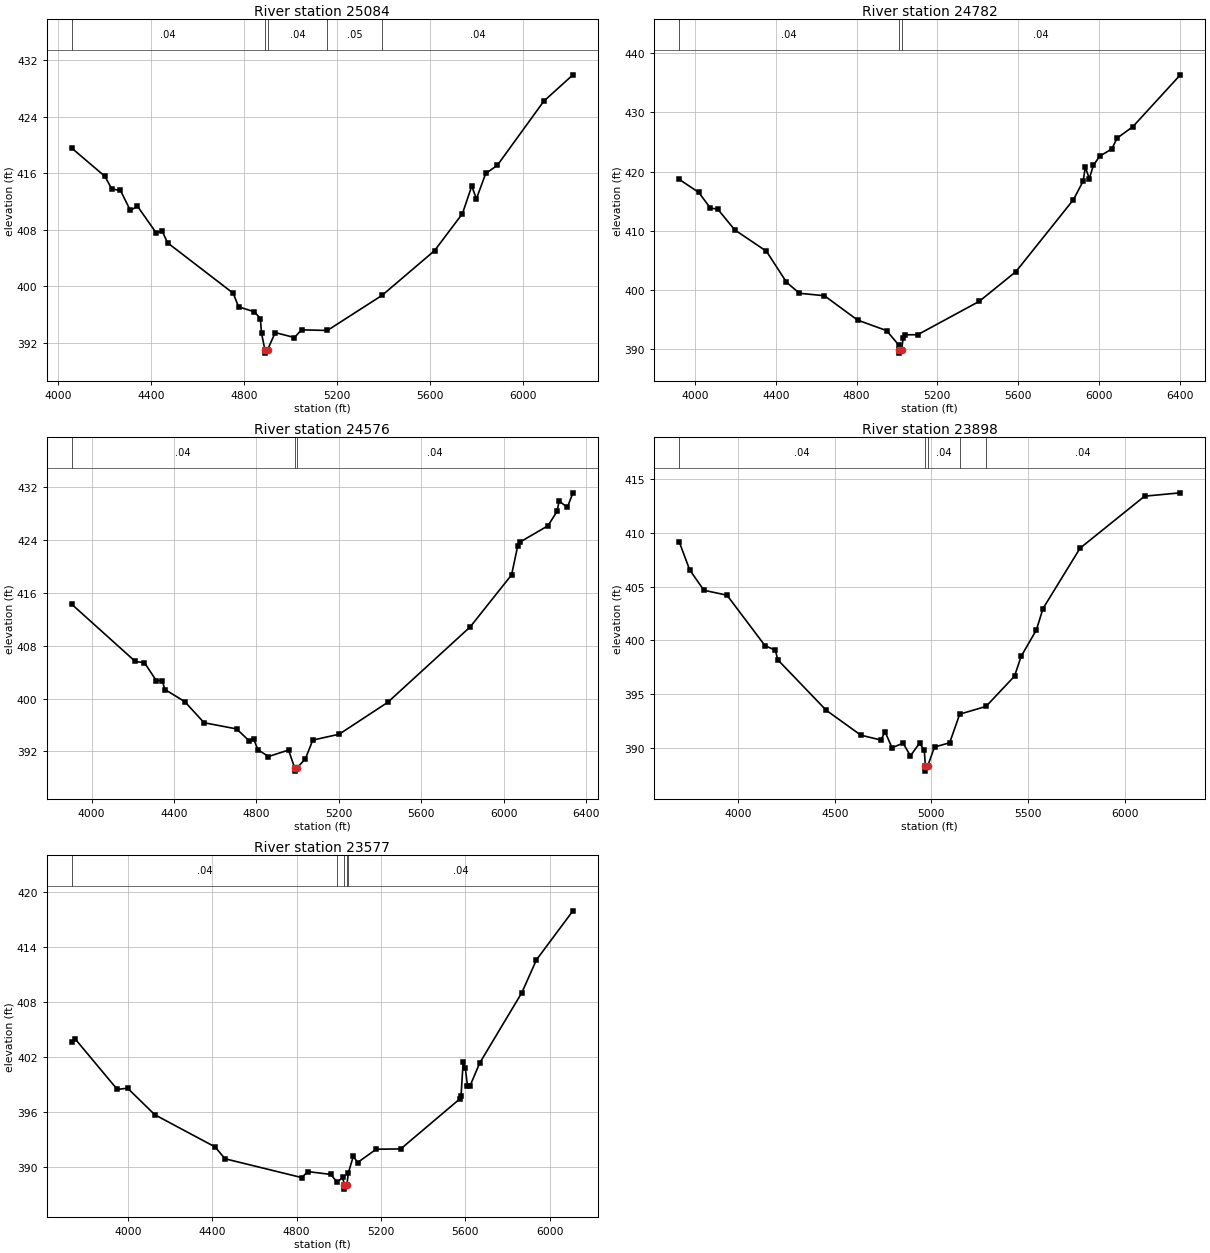
Type RM Length L Ch R = 1,25084,302,302,302
BEGIN DESCRIPTION:
Mapping XS a6dadc8b
END DESCRIPTION:
XS GIS Cut Line= 4
      2420096.22     13576751.11      2419436.50     13576345.44
      2419026.73     13576283.98      2418059.78     13576275.78
#Sta/Elev= 30
  4058.9  419.58  4201.2  415.59  4231.7  413.77  4268.4  413.59  4311.0  410.75
  4341.8  411.34  4421.1  407.62  4448.2  407.80  4471.2  406.16  4753.6  399.01
  4776.4  397.10  4845.0  396.37  4870.2  395.43  4875.3  393.36  4889.5  391.03
  4890.0  390.53  4901.6  391.03  4934.2  393.44  5016.9  392.74  5047.2  393.83
  5158.5  393.74  5394.3  398.73  5619.5  405.05  5739.5  410.30  5779.5  414.20
  5799.5  412.39  5839.5  415.98  5889.5  417.14  6089.5  426.23  6214.7  429.96
#Mann=5,-1,0
  4058.9    0.04       0  4889.5    0.04       0  4901.6    0.04       0
  5158.5    0.05       0  5394.3    0.04       0
Bank Sta=4889.5,4901.6
Exp/Cntr=0.3,0.1

Type RM Length L Ch R = 1,24782,206,206,206
BEGIN DESCRIPTION:
Mapping XS b8606ffa
END DESCRIPTION:
XS GIS Cut Line= 4
      2420260.12     13576517.53      2419784.81     13576140.56
      2419075.90     13575976.65      2417938.35     13576132.14
#Sta/Elev= 30
  3921.4  418.70  4018.8  416.48  4076.5  413.81  4111.8  413.69  4196.7  410.15
  4353.7  406.54  4453.1  401.30  4517.1  399.43  4640.8  399.02  4805.0  394.90
  4948.7  393.12  5010.3  390.63  5011.1  389.81  5011.6  389.31  5023.2  389.81
  5030.8  391.92  5041.1  392.41  5102.6  392.42  5408.0  398.07  5589.6  403.10
  5874.2  415.26  5922.7  418.41  5932.8  420.76  5953.0  418.83  5973.2  421.07
  6003.5  422.59  6064.0  423.83  6091.0  425.68  6168.2  427.59  6403.8  436.37
#Mann=3,-1,0
  3921.4    0.04       0  5011.1    0.04       0  5023.2    0.04       0
Bank Sta=5011.1,5023.2
Exp/Cntr=0.3,0.1

Type RM Length L Ch R = 1,24576,678,678,678
BEGIN DESCRIPTION:
Mapping XS 382ab483
END DESCRIPTION:
XS GIS Cut Line= 4
      2420309.34     13576279.89      2419829.88     13575956.16
      2418907.89     13575722.59      2418008.17     13575800.29
#Sta/Elev= 30
  3903.3  414.28  4211.6  405.62  4256.5  405.42  4313.4  402.73  4342.9  402.67
  4355.4  401.37  4451.3  399.55  4545.6  396.34  4703.5  395.40  4765.4  393.57
  4786.0  393.92  4806.6  392.26  4858.2  391.22  4955.5  392.20  4985.3  389.51
  4985.8  389.01  4997.5  389.51  5037.5  390.88  5073.3  393.71  5201.5  394.60
  5436.9  399.42  5837.3  410.85  6038.1  418.72  6068.2  423.14  6078.2  423.68
  6215.1  426.17  6258.9  428.35  6268.9  429.89  6309.1  428.96  6336.0  431.15
#Mann=3,-1,0
  3903.3    0.04       0  4985.3    0.04       0  4997.5    0.04       0
Bank Sta=4985.3,4997.5
Exp/Cntr=0.3,0.1

Type RM Length L Ch R = 1,23898,321,321,321
BEGIN DESCRIPTION:
Mapping XS 843e5c60
END DESCRIPTION:
XS GIS Cut Line= 4
      2420702.70     13575911.08      2419633.19     13575329.20
      2419301.27     13575214.47      2418313.86     13574939.96
#Sta/Elev= 30
  3694.6  409.18  3748.9  406.56  3822.7  404.66  3942.3  404.20  4139.0  399.51
  4192.9  399.09  4204.5  398.21  4455.3  393.52  4634.8  391.20  4738.4  390.75
  4760.2  391.51  4796.2  390.03  4853.3  390.46  4891.3  389.28  4938.5  390.45
  4963.1  389.81  4968.7  388.36  4969.2  387.86  4981.3  388.36  5016.0  390.10
  5094.4  390.49  5146.4  393.15  5282.5  393.87  5430.0  396.68  5464.3  398.52
  5543.1  400.97  5577.4  402.96  5769.3  408.57  6103.4  413.40  6288.2  413.71
#Mann=5,-1,0
  3694.6    0.04       0  4968.7    0.04       0  4981.3    0.04       0
  5146.4    0.05       0  5282.5    0.04       0
Bank Sta=4968.7,4981.3
Exp/Cntr=0.3,0.1

Type RM Length L Ch R = 1,23577,642,642,642
BEGIN DESCRIPTION:
Mapping XS e2cb53dd
END DESCRIPTION:
XS GIS Cut Line= 3
      2420821.58     13575468.54      2419637.29     13575005.48
      2418555.52     13574780.11
#Sta/Elev= 30
  3733.9  403.60  3751.7  403.93  3950.0  398.47  3998.7  398.61  4127.5  395.72
  4414.2  392.20  4460.4  390.92  4824.2  388.87  4854.0  389.52  4962.6  389.21
  4992.7  388.34  5018.1  388.89  5026.6  388.11  5027.1  387.61  5039.2  388.11
  5044.8  389.32  5069.1  391.19  5089.6  390.51  5177.9  391.96  5293.9  391.99
  5573.2  397.42  5579.9  397.78  5590.1  401.50  5600.3  400.76  5610.5  398.88
  5623.3  398.89  5668.2  401.34  5868.4  409.02  5937.4  412.59  6110.5  417.93
#Mann=5,-1,0
  3733.9    0.04       0  4992.7    0.05       0  5026.6    0.05       0
  5039.2    0.05       0  5044.8    0.04       0
Bank Sta=5026.6,5039.2
Exp/Cntr=0.3,0.1