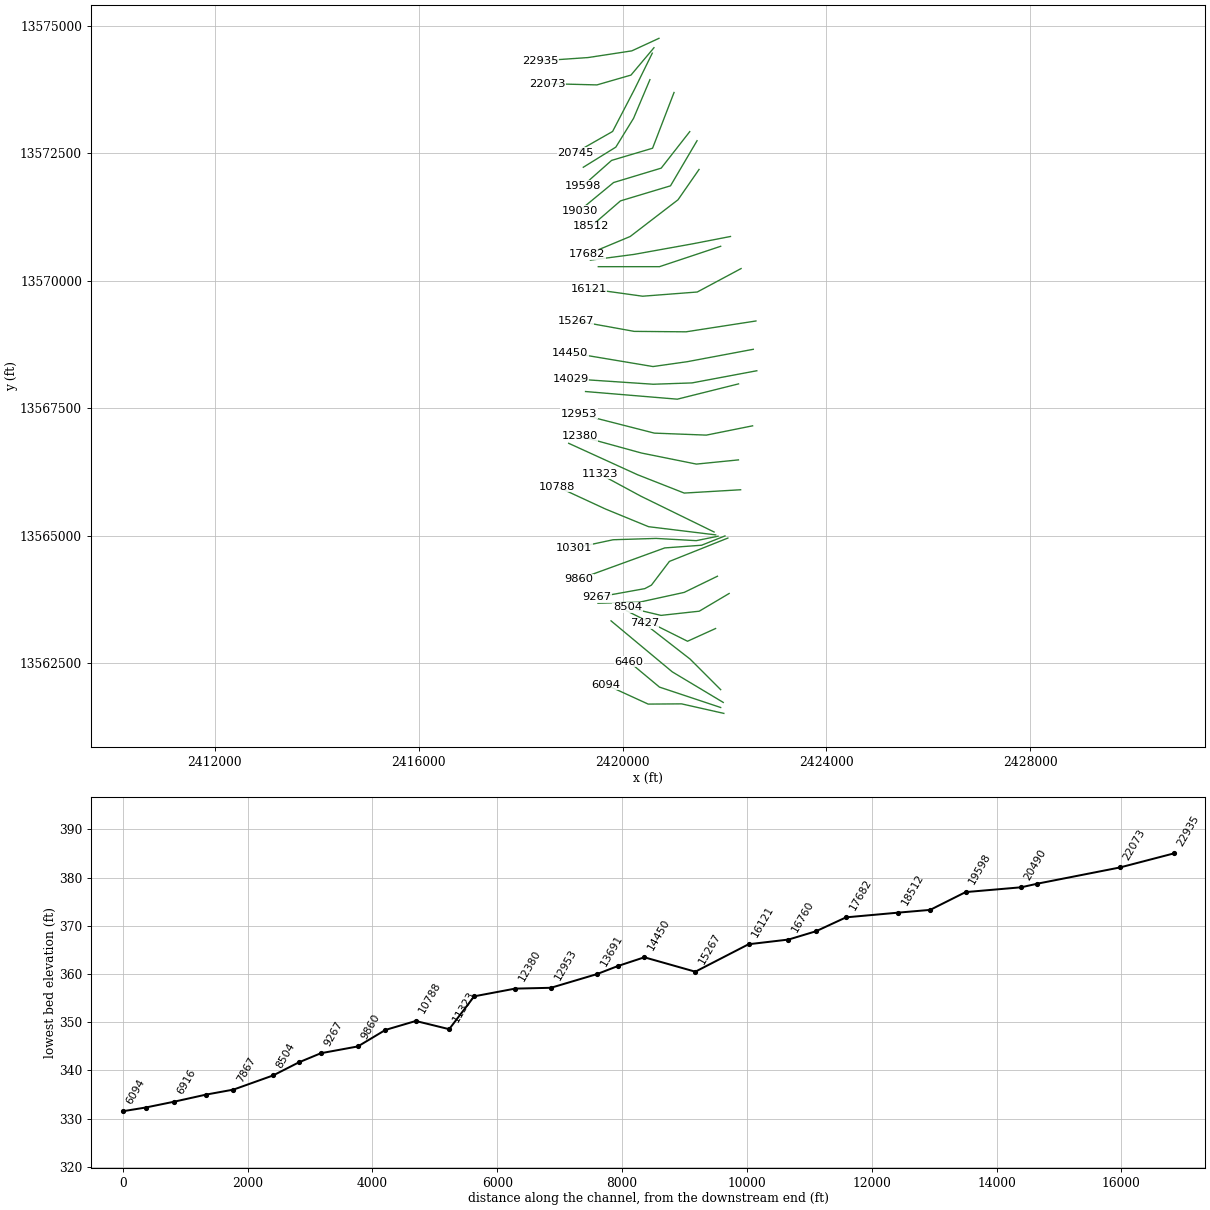
HEC-RAS study LITTLE SALT CREEK.prj: LITTLE SALT CREEK Base Level Engineering

--- LITTLE SALT CREEK.g01 (geometry) --- (continued)

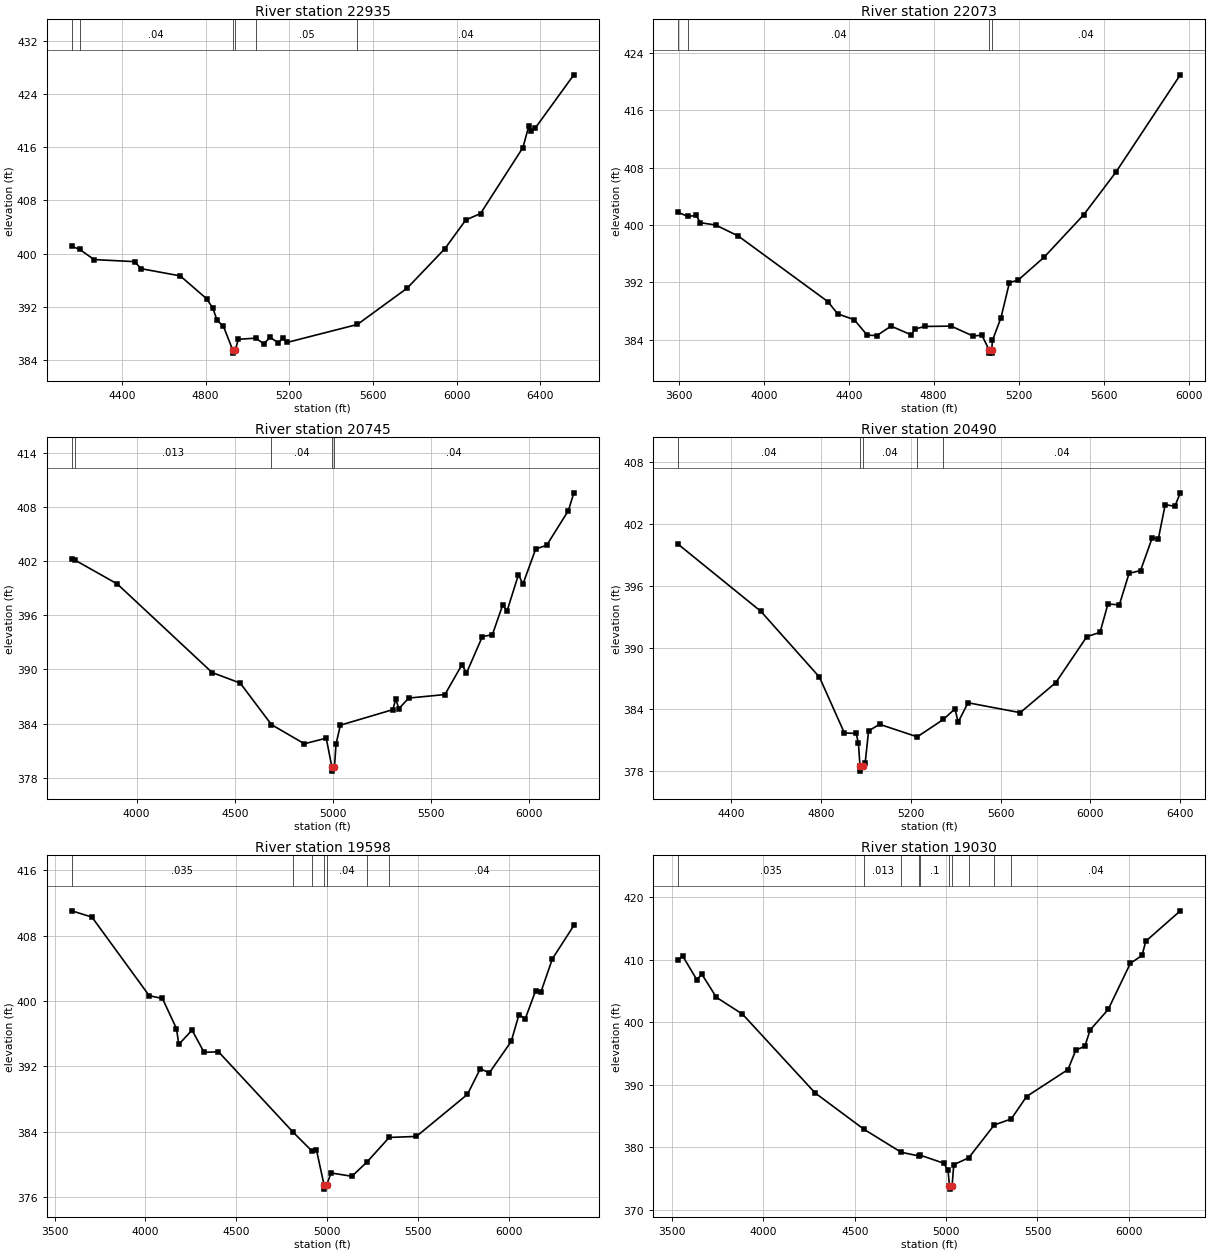
Type RM Length L Ch R = 1,22935,862,862,862
BEGIN DESCRIPTION:
Mapping XS 973a392a
END DESCRIPTION:
XS GIS Cut Line= 4
      2420715.02     13574755.53      2420182.29     13574509.66
      2419325.86     13574378.53      2418379.67     13574312.99
#Sta/Elev= 30
  4159.7  401.09  4197.9  400.61  4266.4  399.09  4460.9  398.78  4490.1  397.73
  4678.5  396.64  4804.4  393.21  4834.7  391.78  4855.0  389.94  4885.3  389.06
  4929.2  385.53  4929.7  385.03  4942.6  385.53  4956.1  387.11  5040.2  387.28
  5078.6  386.42  5107.9  387.41  5148.4  386.57  5168.6  387.33  5188.8  386.63
  5526.0  389.34  5764.1  394.80  5944.5  400.73  6044.7  405.05  6114.9  406.01
  6317.8  415.93  6345.5  419.13  6355.5  418.38  6375.5  418.81  6561.3  426.86
#Mann=6,-1,0
  4159.7   0.013       0  4197.9    0.04       0  4929.2    0.04       0
  4942.6    0.04       0  5040.2    0.05       0  5526.0    0.04       0
Bank Sta=4929.2,4942.6
Exp/Cntr=0.3,0.1

Type RM Length L Ch R = 1,22073,1328,1328,1328
BEGIN DESCRIPTION:
Mapping XS eb45ce63
END DESCRIPTION:
XS GIS Cut Line= 4
      2420616.67     13574571.15      2420165.90     13574034.32
      2419497.96     13573841.73      2418530.91     13573866.31
#Sta/Elev= 30
  3597.5  401.76  3642.3  401.19  3681.5  401.32  3702.3  400.31  3773.8  399.99
  3879.8  398.46  4301.6  389.31  4348.2  387.60  4425.9  386.78  4486.8  384.64
  4532.1  384.56  4599.4  385.89  4694.9  384.66  4710.8  385.47  4757.4  385.84
  4882.2  385.89  4986.3  384.49  5026.6  384.64  5059.9  382.62  5060.4  382.12
  5072.9  382.12  5073.4  382.62  5076.6  383.89  5116.6  387.04  5156.7  391.97
  5196.7  392.28  5320.5  395.52  5506.8  401.44  5656.8  407.32  5961.0  420.94
#Mann=4,-1,0
  3597.5   0.013       0  3642.3    0.04       0  5059.9    0.04       0
  5073.4    0.04       0
Bank Sta=5059.9,5073.4
Exp/Cntr=0.3,0.1

Type RM Length L Ch R = 1,20745,255,255,255
BEGIN DESCRIPTION:
Mapping XS e4687141
END DESCRIPTION:
XS GIS Cut Line= 4
      2420583.87     13574464.58      2420231.46     13573747.48
      2419805.30     13572927.93      2419080.01     13572514.07
#Sta/Elev= 30
  3669.9  402.26  3688.6  402.08  3901.6  399.47  4384.8  389.66  4528.1  388.49
  4687.1  383.89  4854.9  381.77  4966.3  382.39  4994.6  379.24  4995.1  378.74
  5008.3  379.24  5016.2  381.74  5038.3  383.83  5305.8  385.55  5320.1  386.71
  5336.5  385.66  5386.4  386.83  5570.8  387.22  5657.8  390.53  5680.8  389.60
  5761.4  393.63  5812.7  393.85  5865.0  397.13  5887.6  396.49  5945.6  400.50
  5968.3  399.45  6033.1  403.33  6089.6  403.76  6200.1  407.60  6227.7  409.56
#Mann=5,-1,0
  3669.9    0.04       0  3688.6   0.013       0  4687.1    0.04       0
  4994.6    0.04       0  5008.3    0.04       0
Bank Sta=4994.6,5008.3
Exp/Cntr=0.3,0.1

Type RM Length L Ch R = 1,20490,892,892,892
BEGIN DESCRIPTION:
Mapping XS aa6775c0
END DESCRIPTION:
XS GIS Cut Line= 4
      2420537.18     13573944.58      2420216.01     13573185.04
      2419868.79     13572620.80      2419230.80     13572225.86
#Sta/Elev= 30
  4163.4  400.03  4532.1  393.51  4792.7  387.13  4903.7  381.71  4956.5  381.66
  4966.4  380.69  4973.4  378.50  4973.9  378.00  4987.1  378.50  4996.7  378.83
  5011.6  381.90  5060.6  382.55  5228.6  381.33  5344.8  383.02  5396.7  384.05
  5410.8  382.75  5454.7  384.64  5687.3  383.68  5845.6  386.59  5984.3  391.06
  6043.1  391.48  6078.4  394.23  6129.2  394.15  6172.5  397.21  6223.7  397.48
  6275.8  400.67  6302.9  400.55  6333.7  403.89  6376.2  403.71  6400.9  405.03
#Mann=5,-1,0
  4163.4    0.04       0  4973.4    0.04       0  4987.1    0.04       0
  5228.6   0.013       0  5344.8    0.04       0
Bank Sta=4973.4,4987.1
Exp/Cntr=0.3,0.1

Type RM Length L Ch R = 1,19598,568,568,568
BEGIN DESCRIPTION:
Mapping XS 8eb56f27
END DESCRIPTION:
XS GIS Cut Line= 4
      2421010.28     13573692.85      2420589.27     13572599.10
      2419786.32     13572360.39      2419222.07     13571861.25
#Sta/Elev= 30
  3594.9  411.02  3706.1  410.25  4021.2  400.64  4093.8  400.31  4171.2  396.62
  4183.8  394.69  4256.9  396.44  4323.0  393.72  4402.3  393.79  4812.5  383.97
  4914.2  381.71  4941.3  381.80  4983.4  377.50  4983.9  377.00  4997.4  377.50
  5021.7  378.98  5136.5  378.57  5219.4  380.31  5341.8  383.32  5491.2  383.44
  5772.2  388.58  5843.3  391.72  5892.6  391.21  6013.1  395.05  6055.8  398.33
  6090.9  397.84  6147.8  401.27  6176.2  401.06  6239.8  405.15  6357.9  409.23
#Mann=7,-1,0
  3594.9   0.035       0  4812.5    0.05       0  4914.2    0.04       0
  4983.4    0.04       0  4997.4    0.04       0  5219.4   0.013       0
  5341.8    0.04       0
Bank Sta=4983.4,4997.4
Exp/Cntr=0.3,0.1

Type RM Length L Ch R = 1,19030,518,518,518
BEGIN DESCRIPTION:
Mapping XS ca8405f6
END DESCRIPTION:
XS GIS Cut Line= 4
      2421318.46     13572924.65      2420758.54     13572208.48
      2419825.38     13571926.36      2419158.46     13571376.36
#Sta/Elev= 30
  3533.6  409.96  3557.9  410.61  3634.8  406.84  3663.7  407.66  3742.4  404.00
  3885.3  401.31  4283.2  388.69  4550.1  382.89  4753.9  379.21  4849.1  378.63
  4855.7  378.77  4987.3  377.45  5010.5  376.31  5018.5  373.81  5019.0  373.31
  5032.6  373.81  5041.9  377.22  5124.1  378.33  5263.2  383.57  5356.7  384.54
  5440.4  388.13  5667.0  392.44  5710.1  395.56  5759.6  396.17  5788.2  398.77
  5887.2  402.06  6008.4  409.43  6072.3  410.70  6093.1  412.98  6282.0  417.84
#Mann=10,-1,0
  3533.6   0.035       0  4550.1   0.013       0  4753.9    0.05       0
  4849.1    0.12       0  4855.7     0.1       0  5018.5    0.05       0
  5032.6     0.1       0  5124.1    0.03       0  5263.2   0.013       0
  5356.7    0.04       0
Bank Sta=5018.5,5032.6
Exp/Cntr=0.3,0.1

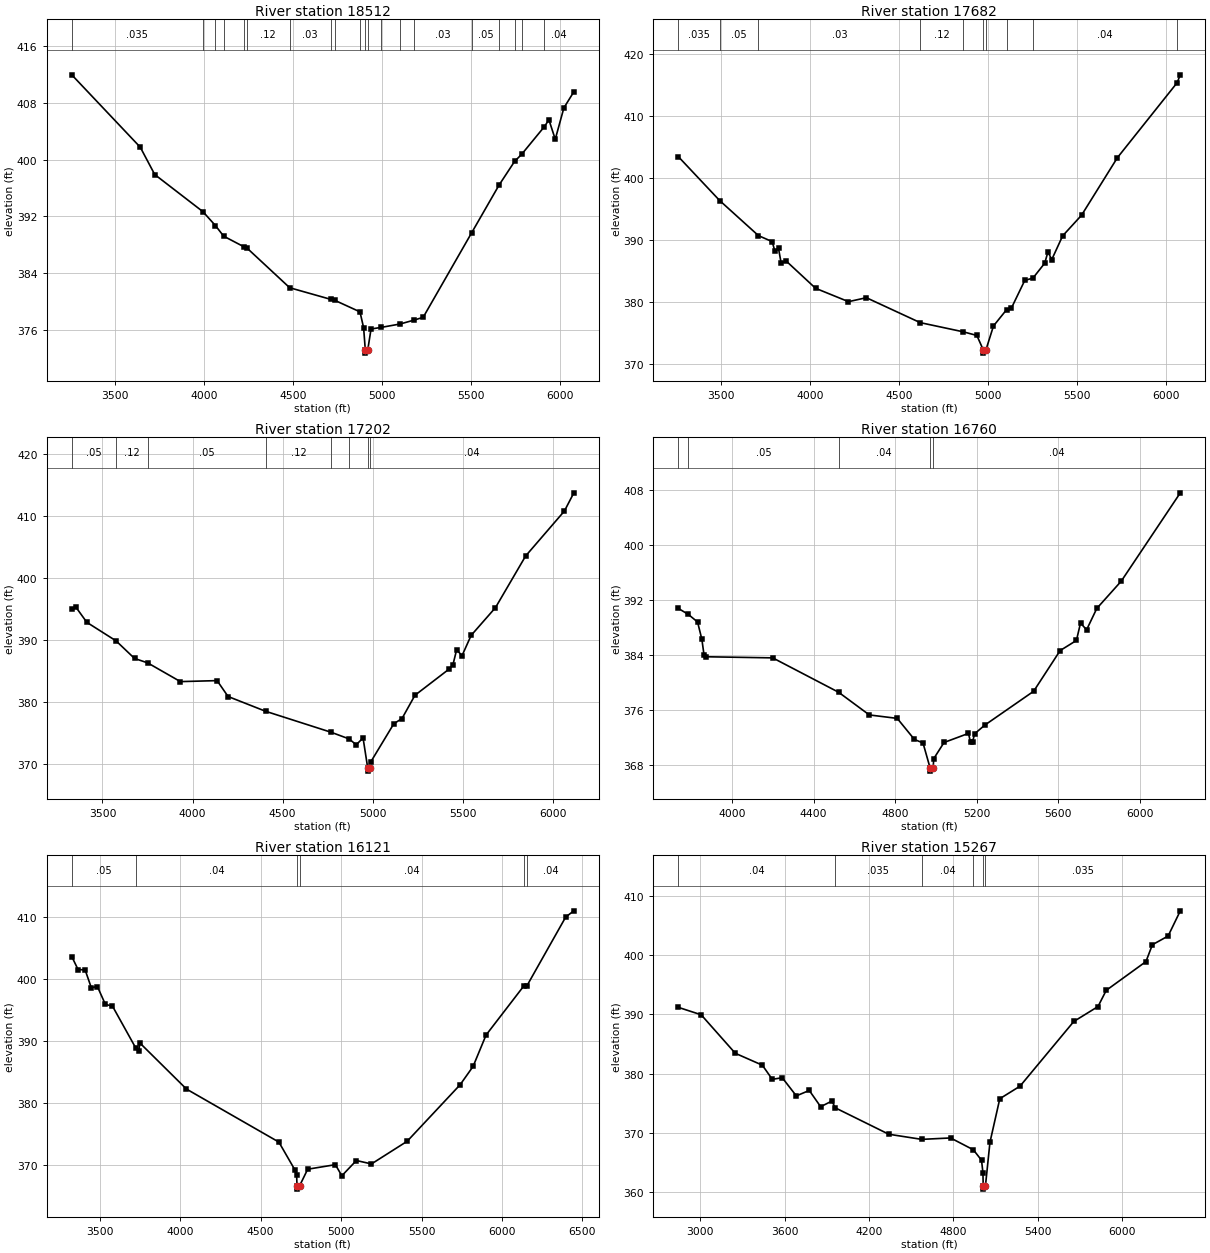
Type RM Length L Ch R = 1,18512,830,830,830
BEGIN DESCRIPTION:
Mapping XS bdb20b91
END DESCRIPTION:
XS GIS Cut Line= 4
      2421461.68     13572746.70      2420940.83     13571861.25
      2419959.93     13571566.12      2419379.14     13571063.34
#Sta/Elev= 30
  3256.5  411.97  3641.3  401.76  3722.5  397.91  3993.4  392.67  4063.1  390.72
  4109.7  389.22  4226.0  387.69  4238.6  387.59  4480.4  381.95  4711.4  380.31
  4732.4  380.19  4875.1  378.55  4895.6  376.31  4904.9  373.23  4905.4  372.73
  4919.1  373.23  4937.3  376.13  4994.7  376.36  5101.1  376.84  5180.6  377.40
  5230.1  377.78  5501.7  389.67  5656.9  396.45  5743.5  399.76  5783.8  400.78
  5910.7  404.66  5936.3  405.63  5971.9  402.88  6020.3  407.31  6076.3  409.58
#Mann=20,-1,0
  3256.5   0.035       0  3993.4   0.013       0  4063.1    0.12       0
  4109.7   0.013       0  4226.0    0.03       0  4238.6    0.12       0
  4480.4    0.03       0  4711.4    0.12       0  4732.4    0.03       0
  4875.1    0.12       0  4904.9    0.03       0  4919.1    0.12       0
  4994.7    0.03       0  5101.1    0.12       0  5180.6    0.03       0
  5501.7    0.05       0  5656.9   0.013       0  5743.5    0.03       0
  5783.8   0.013       0  5910.7    0.04       0
Bank Sta=4904.9,4919.1
Exp/Cntr=0.3,0.1

Type RM Length L Ch R = 1,17682,480,480,480
BEGIN DESCRIPTION:
Mapping XS 04544b6c
END DESCRIPTION:
XS GIS Cut Line= 4
      2421500.75     13572182.46      2421088.40     13571587.82
      2420150.90     13570867.33      2419309.40     13570515.98
#Sta/Elev= 30
  3260.5  403.47  3493.4  396.36  3710.8  390.71  3787.5  389.75  3802.4  388.28
  3823.3  388.65  3838.2  386.27  3865.9  386.63  4031.2  382.22  4216.0  380.06
  4316.3  380.70  4618.5  376.68  4861.3  375.19  4936.5  374.61  4972.8  372.26
  4973.3  371.76  4987.2  372.26  5029.9  376.15  5104.0  378.79  5129.5  378.97
  5205.4  383.49  5251.5  383.87  5317.2  386.26  5335.4  388.07  5357.1  386.86
  5417.9  390.67  5524.0  394.00  5725.4  403.29  6060.1  415.36  6078.4  416.65
#Mann=10,-1,0
  3260.5   0.035       0  3493.4    0.05       0  3710.8    0.03       0
  4618.5    0.12       0  4861.3    0.03       0  4972.8    0.05       0
  4987.2    0.03       0  5104.0    0.03       0  5251.5    0.04       0
  6060.1   0.013       0
Bank Sta=4972.8,4987.2
Exp/Cntr=0.3,0.1

Type RM Length L Ch R = 1,17202,442,442,442
BEGIN DESCRIPTION:
Mapping XS 26abc616
END DESCRIPTION:
XS GIS Cut Line= 4
      2422117.09     13570867.34      2421379.20     13570724.10
      2420224.69     13570515.77      2419369.82     13570402.94
#Sta/Elev= 30
  3329.5  394.98  3352.0  395.31  3413.1  392.85  3575.5  389.86  3677.9  387.03
  3750.7  386.32  3932.6  383.30  4136.2  383.46  4197.2  380.90  4405.6  378.52
  4770.3  375.13  4869.8  374.06  4908.5  373.12  4946.5  374.23  4972.4  369.38
  4972.9  368.88  4986.8  369.38  4989.8  370.39  5117.4  376.52  5162.6  377.35
  5234.6  381.10  5425.5  385.35  5445.7  386.05  5465.8  388.41  5496.1  387.49
  5546.5  390.75  5681.6  395.22  5849.1  403.54  6064.3  410.78  6116.6  413.71
#Mann=8,-1,0
  3329.5    0.05       0  3575.5    0.12       0  3750.7    0.05       0
  4405.6    0.12       0  4770.3    0.03       0  4869.8    0.04       0
  4972.4    0.04       0  4986.8    0.04       0
Bank Sta=4972.4,4986.8
Exp/Cntr=0.3,0.1

Type RM Length L Ch R = 1,16760,639,639,639
BEGIN DESCRIPTION:
LITTLE SALT CREEK 27.0
END DESCRIPTION:
XS GIS Cut Line= 3
      2421925.02     13570675.01      2420725.00     13570275.00
      2419525.03     13570275.00
#Sta/Elev= 30
  3735.1  390.79  3784.7  389.91  3830.0  388.81  3851.1  386.29  3861.6  384.05
  3872.1  383.76  4198.9  383.60  4522.2  378.61  4673.3  375.31  4810.3  374.81
  4894.6  371.75  4936.8  371.24  4971.2  367.65  4971.7  367.15  4986.6  367.65
  4989.5  368.96  5040.0  371.31  5160.0  372.63  5170.0  371.35  5180.0  371.37
  5190.0  372.57  5240.0  373.83  5480.0  378.75  5610.0  384.66  5690.0  386.13
  5710.0  388.65  5740.0  387.68  5790.0  390.78  5910.0  394.74  6200.0  407.57
#Mann=5,-1,0
  3735.1    0.12       0  3784.7    0.05       0  4522.2    0.04       0
  4971.2    0.04       0  4986.6    0.04       0
Bank Sta=4971.2,4986.6
Exp/Cntr=0.3,0.1

Type RM Length L Ch R = 1,16121,854,854,854
BEGIN DESCRIPTION:
Mapping XS b129d252
END DESCRIPTION:
XS GIS Cut Line= 4
      2422325.36     13570237.98      2421466.01     13569777.92
      2420393.96     13569695.46      2419334.95     13569843.02
#Sta/Elev= 30
  3327.2  403.65  3366.3  401.56  3410.2  401.50  3448.4  398.64  3486.4  398.82
  3536.1  395.94  3580.0  395.67  3724.9  388.91  3744.1  388.41  3749.8  389.74
  4039.9  382.30  4613.9  373.76  4714.2  369.24  4724.2  368.44  4726.5  366.68
  4727.0  366.18  4742.0  366.68  4792.9  369.39  4964.9  370.12  5005.0  368.33
  5095.3  370.79  5189.1  370.24  5410.8  373.89  5739.6  382.99  5820.4  385.95
  5901.1  391.01  6136.3  398.94  6154.2  398.91  6395.9  410.02  6446.4  411.02
#Mann=6,-1,0
  3327.2    0.05       0  3724.9    0.04       0  4726.5    0.04       0
  4742.0    0.04       0  6136.3    0.05       0  6154.2    0.04       0
Bank Sta=4726.5,4742
Exp/Cntr=0.3,0.1

Type RM Length L Ch R = 1,15267,817,817,817
BEGIN DESCRIPTION:
Mapping XS 041b53f4
END DESCRIPTION:
XS GIS Cut Line= 4
      2422616.21     13569209.35      2421244.65     13568996.67
      2420229.03     13569005.35      2419079.45     13569213.58
#Sta/Elev= 30
  2842.3  391.21  3005.4  389.95  3248.3  383.44  3440.6  381.43  3511.4  379.04
  3582.3  379.31  3682.4  376.24  3774.5  377.16  3855.5  374.41  3936.4  375.38
  3958.0  374.24  4339.9  369.76  4574.5  368.89  4779.9  369.13  4941.8  367.13
  4999.9  365.37  5009.9  363.29  5012.1  360.98  5012.6  360.48  5027.7  360.98
  5059.9  368.39  5129.9  375.76  5273.7  377.88  5656.5  388.82  5828.6  391.34
  5887.2  394.08  6169.7  398.94  6215.5  401.79  6327.3  403.26  6414.2  407.52
#Mann=6,-1,0
  2842.3    0.04       0  3958.0   0.035       0  4574.5    0.04       0
  4941.8   0.035       0  5012.1   0.035       0  5027.7   0.035       0
Bank Sta=5012.1,5027.7
Exp/Cntr=0.3,0.1

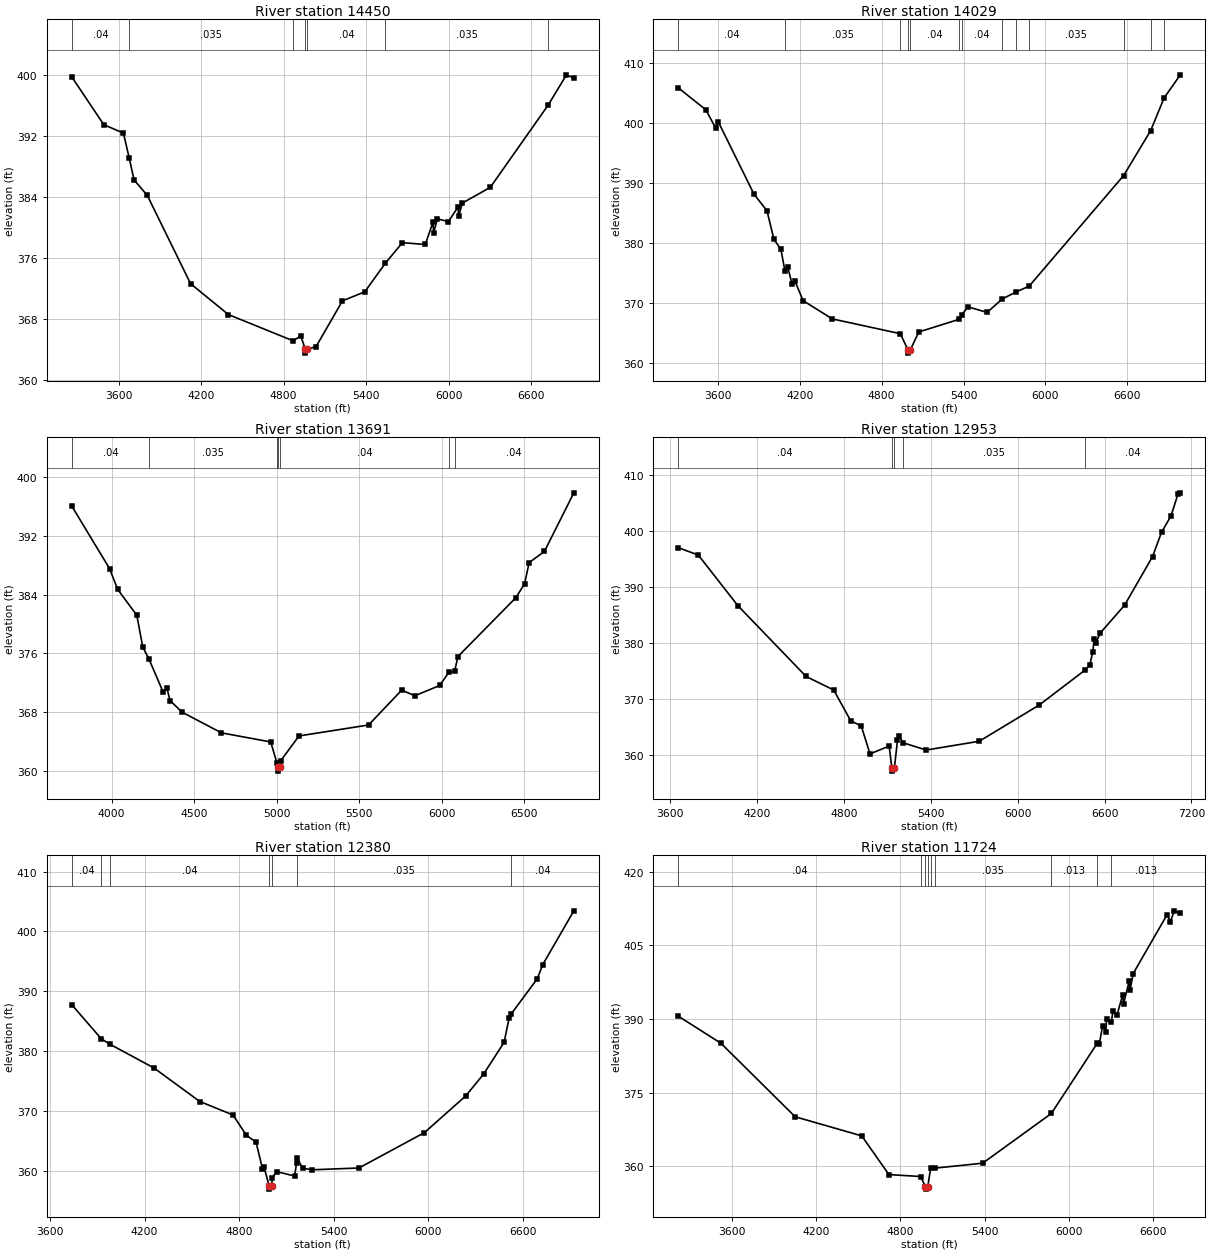
Type RM Length L Ch R = 1,14450,421,421,421
BEGIN DESCRIPTION:
Mapping XS 1b48c3fb
END DESCRIPTION:
XS GIS Cut Line= 4
      2422564.11     13568653.79      2421270.70     13568410.73
      2420597.95     13568315.25      2418966.04     13568588.68
#Sta/Elev= 30
  3260.0  399.78  3492.6  393.50  3635.6  392.39  3677.6  389.12  3712.8  386.24
  3808.5  384.22  4124.0  372.59  4398.7  368.54  4869.1  365.09  4925.2  365.73
  4957.7  363.97  4958.2  363.47  4973.6  363.97  5036.3  364.34  5228.2  370.34
  5390.3  371.53  5538.5  375.26  5664.1  377.99  5830.2  377.75  5885.8  380.67
  5890.8  379.28  5917.6  381.11  5998.7  380.77  6067.8  382.67  6072.9  381.50
  6100.1  383.20  6302.9  385.26  6725.3  396.12  6856.6  400.05  6910.2  399.62
#Mann=7,-1,0
  3260.0    0.04       0  3677.6   0.035       0  4869.1    0.04       0
  4957.7    0.04       0  4973.6    0.04       0  5538.5   0.035       0
  6725.3    0.04       0
Bank Sta=4957.7,4973.6
Exp/Cntr=0.3,0.1

Type RM Length L Ch R = 1,14029,338,338,338
BEGIN DESCRIPTION:
Mapping XS e847a175
END DESCRIPTION:
XS GIS Cut Line= 4
      2422633.58     13568232.79      2421361.84     13567994.07
      2420602.29     13567968.03      2418983.37     13568076.53
#Sta/Elev= 30
  3311.1  405.86  3513.2  402.20  3584.4  399.18  3604.7  400.18  3866.2  388.13
  3960.8  385.39  4011.7  380.62  4062.6  378.99  4092.9  375.29  4113.5  375.94
  4144.2  373.21  4164.3  373.74  4225.4  370.41  4439.0  367.37  4937.3  364.91
  4994.0  362.17  4994.5  361.67  5010.2  362.17  5072.2  365.19  5364.8  367.28
  5385.4  368.00  5432.5  369.38  5572.8  368.45  5683.7  370.69  5782.5  371.83
  5881.3  372.84  6572.6  391.25  6770.1  398.71  6868.9  404.17  6987.6  408.02
#Mann=13,-1,0
  3311.1    0.04       0  4092.9   0.035       0  4937.3    0.04       0
  4994.0    0.04       0  5010.2    0.04       0  5364.8   0.013       0
  5385.4    0.04       0  5683.7   0.035       0  5782.5    0.04       0
  5881.3   0.035       0  6572.6    0.04       0  6770.1    0.05       0
  6868.9    0.04       0
Bank Sta=4994,5010.2
Exp/Cntr=0.3,0.1

Type RM Length L Ch R = 1,13691,738,738,738
BEGIN DESCRIPTION:
LITTLE SALT CREEK 22.0
END DESCRIPTION:
XS GIS Cut Line= 3
      2422274.99     13567975.00      2421075.00     13567675.00
      2419274.96     13567825.00
#Sta/Elev= 30
  3758.3  396.06  3987.6  387.54  4036.6  384.72  4152.6  381.19  4188.6  376.87
  4226.7  375.21  4312.3  370.73  4335.5  371.25  4353.6  369.58  4428.3  367.99
  4665.4  365.19  4964.3  363.95  5001.3  361.13  5007.2  360.48  5007.7  359.98
  5023.4  360.48  5025.3  361.41  5135.7  364.77  5557.2  366.26  5757.9  371.00
  5838.1  370.24  5988.6  371.64  6043.4  373.41  6078.2  373.55  6099.0  375.58
  6450.2  383.59  6502.9  385.49  6530.5  388.36  6623.3  389.89  6801.5  397.86
#Mann=7,-1,0
  3758.3    0.04       0  4226.7   0.035       0  5001.3    0.04       0
  5007.2   0.035       0  5023.4    0.04       0  6043.4   0.013       0
  6078.2    0.04       0
Bank Sta=5007.2,5023.4
Exp/Cntr=0.3,0.1

Type RM Length L Ch R = 1,12953,573,573,573
BEGIN DESCRIPTION:
Mapping XS 97c6bedc
END DESCRIPTION:
XS GIS Cut Line= 4
      2422551.08     13567152.05      2421643.96     13566969.76
      2420623.99     13567008.82      2419149.18     13567386.20
#Sta/Elev= 30
  3654.6  397.10  3793.4  395.77  4067.4  386.70  4538.0  374.06  4728.9  371.64
  4845.7  366.16  4919.1  365.20  4979.1  360.23  5111.4  361.61  5130.9  357.64
  5131.4  357.14  5147.5  357.64  5169.2  362.64  5179.3  363.45  5207.8  362.21
  5367.2  360.91  5733.7  362.48  6146.6  368.93  6467.7  375.26  6497.7  376.14
  6518.2  378.44  6528.2  380.80  6538.8  380.04  6569.1  381.81  6737.5  386.79
  6931.1  395.50  6993.0  399.84  7058.8  402.78  7106.6  406.67  7122.9  406.90
#Mann=5,-1,0
  3654.6    0.04       0  5130.9    0.04       0  5147.5    0.04       0
  5207.8   0.035       0  6467.7    0.04       0
Bank Sta=5130.9,5147.5
Exp/Cntr=0.3,0.1

Type RM Length L Ch R = 1,12380,656,656,656
BEGIN DESCRIPTION:
Mapping XS 1a857e6d
END DESCRIPTION:
XS GIS Cut Line= 4
      2422273.27     13566483.65      2421448.65     13566401.19
      2420372.26     13566618.20      2419158.50     13566951.98
#Sta/Elev= 30
  3738.3  387.77  3925.0  382.09  3980.6  381.16  4259.2  377.21  4550.6  371.60
  4761.5  369.35  4846.2  365.96  4907.4  364.83  4948.2  360.40  4958.4  360.65
  4990.9  357.47  4991.4  356.97  5007.5  357.47  5009.4  358.90  5040.0  359.88
  5152.2  359.16  5164.9  361.34  5167.9  362.17  5203.2  360.46  5264.4  360.20
  5560.3  360.50  5976.1  366.41  6237.7  372.53  6351.3  376.18  6481.6  381.49
  6512.7  385.49  6526.5  386.22  6692.2  392.11  6726.6  394.46  6923.9  403.44
#Mann=7,-1,0
  3738.3    0.04       0  3925.0    0.03       0  3980.6    0.04       0
  4990.9    0.04       0  5007.5    0.04       0  5164.9   0.035       0
  6526.5    0.04       0
Bank Sta=4990.9,5007.5
Exp/Cntr=0.3,0.1

Type RM Length L Ch R = 1,11724,401,401,401
BEGIN DESCRIPTION:
Mapping XS 9096dd04
END DESCRIPTION:
XS GIS Cut Line= 4
      2422316.67     13565897.71      2421209.93     13565832.61
      2420294.13     13566192.85      2418944.33     13566809.16
#Sta/Elev= 30
  3217.1  390.59  3521.5  385.06  4050.2  370.10  4524.5  366.21  4717.9  358.33
  4943.7  357.94  4978.2  355.87  4978.7  355.37  4994.9  355.87  5014.9  359.63
  5047.0  359.65  5385.9  360.65  5875.4  370.78  6201.6  385.05  6216.9  384.91
  6239.9  388.61  6262.9  387.41  6268.4  389.99  6302.2  389.47  6314.5  391.57
  6343.0  390.86  6383.6  394.93  6389.1  393.05  6429.6  397.75  6435.1  395.83
  6458.2  399.27  6699.5  411.24  6722.5  409.83  6751.0  412.03  6793.7  411.52
#Mann=9,-1,0
  3217.1    0.04       0  4943.7   0.035       0  4978.2   0.035       0
  4994.9   0.035       0  5014.9    0.04       0  5047.0   0.035       0
  5875.4   0.013       0  6201.6    0.04       0  6302.2   0.013       0
Bank Sta=4978.2,4994.9
Exp/Cntr=0.3,0.1

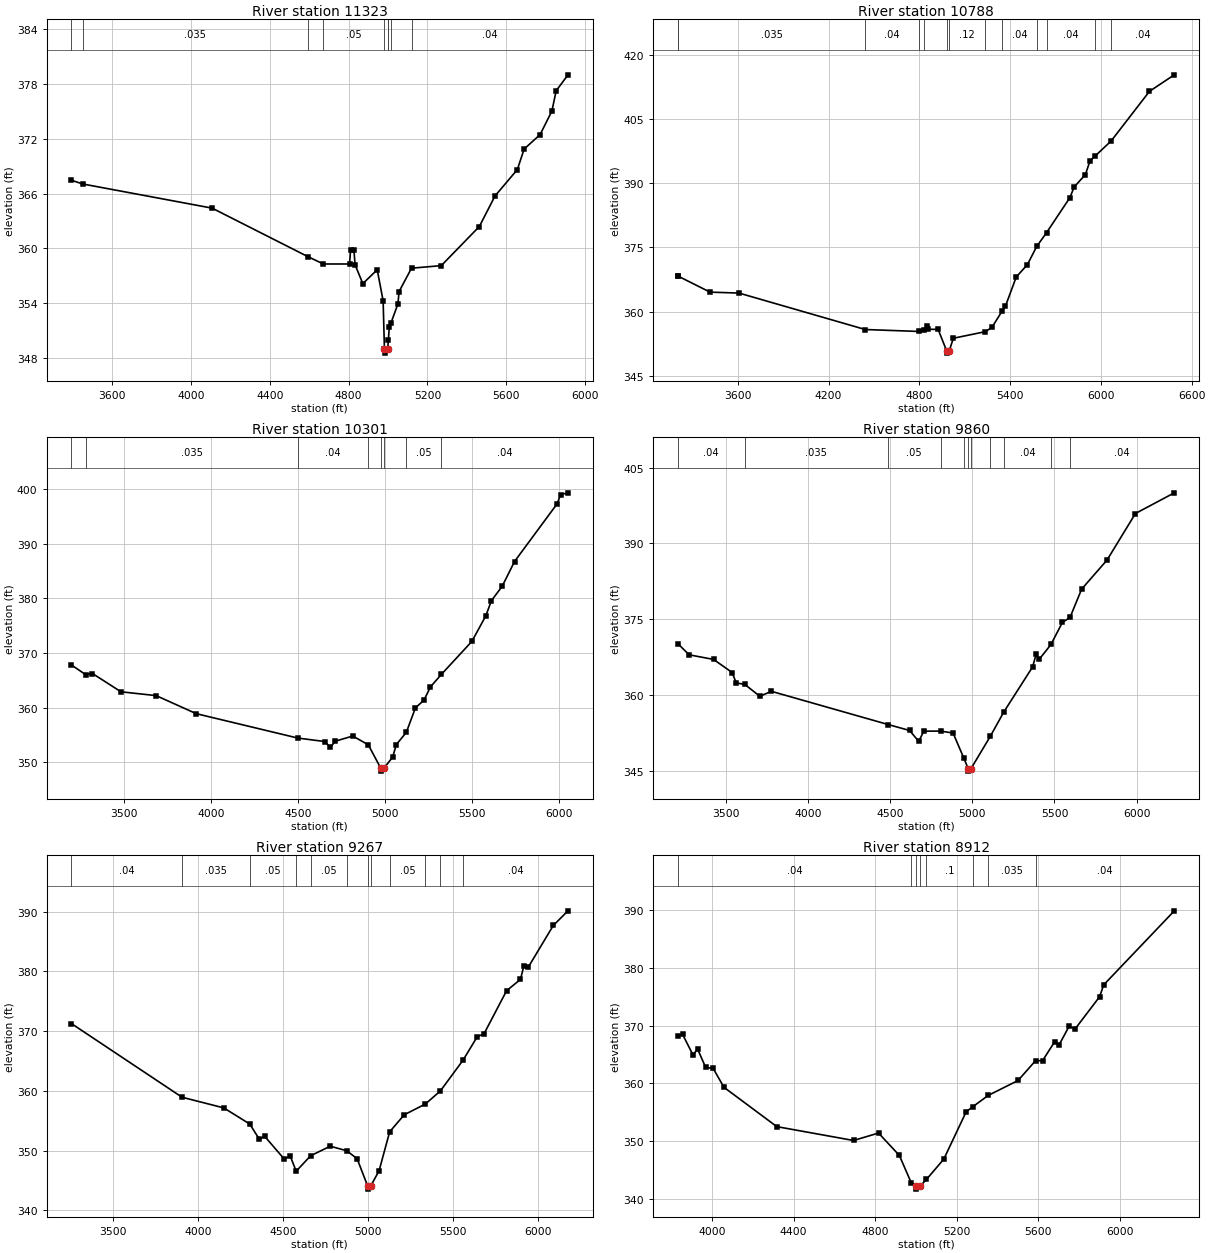
Type RM Length L Ch R = 1,11323,535,535,535
BEGIN DESCRIPTION:
Mapping XS e56684c2
END DESCRIPTION:
XS GIS Cut Line= 3
      2421795.84     13565068.73      2420359.24     13565771.85
      2419549.00     13566209.46
#Sta/Elev= 30
  3393.3  367.46  3450.5  367.05  4106.9  364.41  4593.6  359.10  4672.1  358.30
  4804.6  358.30  4810.2  359.87  4827.1  359.79  4832.7  358.22  4872.1  356.15
  4945.2  357.67  4975.2  354.27  4981.7  349.05  4982.2  348.55  4998.7  349.05
  5001.7  349.96  5006.6  351.45  5015.3  351.87  5050.3  353.93  5056.0  355.28
  5119.2  357.84  5270.3  358.12  5463.5  362.40  5543.1  365.74  5656.6  368.63
  5690.8  370.87  5771.8  372.45  5831.7  375.02  5853.6  377.25  5913.6  378.99
#Mann=9,-1,0
  3393.3    0.04       0  3450.5   0.035       0  4593.6    0.04       0
  4672.1    0.05       0  4981.7    0.05       0  4998.7    0.05       0
  5001.7    0.12       0  5015.3    0.05       0  5119.2    0.04       0
Bank Sta=4981.7,4998.7
Exp/Cntr=0.3,0.1

Type RM Length L Ch R = 1,10788,487,487,487
BEGIN DESCRIPTION:
Mapping XS d056c552
END DESCRIPTION:
XS GIS Cut Line= 4
      2421826.52     13565012.30      2420511.15     13565172.89
      2419664.79     13565520.11      2418719.29     13565958.16
#Sta/Elev= 30
  3203.5  368.32  3203.8  368.32  3416.6  364.54  3608.0  364.32  4442.7  355.78
  4795.7  355.33  4828.7  355.62  4848.7  356.68  4858.8  355.84  4924.4  355.81
  4980.7  350.75  4981.2  350.25  4997.8  350.75  5024.4  353.73  5236.5  355.28
  5280.4  356.31  5347.0  360.09  5368.5  361.19  5440.5  368.08  5514.7  371.01
  5576.3  375.27  5640.7  378.46  5795.2  386.68  5823.6  389.18  5897.9  392.09
  5928.1  395.29  5958.5  396.32  6067.1  399.92  6321.4  411.59  6485.5  415.45
#Mann=13,-1,0
  3203.5    0.04       0  3203.8   0.035       0  4442.7    0.04       0
  4795.7    0.05       0  4828.7    0.12       0  4980.7    0.05       0
  4997.8    0.12       0  5236.5    0.05       0  5347.0    0.04       0
  5576.3    0.03       0  5640.7    0.04       0  5958.5    0.03       0
  6067.1    0.04       0
Bank Sta=4980.7,4997.8
Exp/Cntr=0.3,0.1

Type RM Length L Ch R = 1,10301,441,441,441
BEGIN DESCRIPTION:
Mapping XS b73ad8ac
END DESCRIPTION:
XS GIS Cut Line= 5
      2421873.39     13564986.24      2421445.53     13564898.69
      2420658.72     13564942.85      2419816.70     13564916.81
      2419044.11     13564751.87
#Sta/Elev= 30
  3196.0  367.80  3276.9  366.05  3316.8  366.24  3480.9  362.90  3683.3  362.20
  3913.7  358.90  4497.9  354.44  4654.6  353.80  4684.6  352.72  4714.6  353.87
  4814.7  354.81  4904.1  353.20  4976.2  348.89  4976.7  348.39  4993.4  348.89
  5044.8  350.99  5064.8  353.22  5122.9  355.49  5174.9  359.94  5224.9  361.40
  5261.5  363.79  5324.7  366.09  5500.1  372.12  5580.0  376.78  5612.6  379.58
  5673.9  382.17  5745.5  386.73  5990.9  397.30  6010.3  398.97  6053.2  399.29
#Mann=8,-1,0
  3196.0    0.04       0  3276.9   0.035       0  4497.9    0.04       0
  4904.1    0.12       0  4976.2    0.05       0  4993.4    0.12       0
  5122.9    0.05       0  5324.7    0.04       0
Bank Sta=4976.2,4993.4
Exp/Cntr=0.3,0.1

Type RM Length L Ch R = 1,9860,593,593,593
BEGIN DESCRIPTION:
Mapping XS 54024de6
END DESCRIPTION:
XS GIS Cut Line= 4
      2422008.84     13564991.46      2421550.52     13564809.17
      2420827.99     13564756.22      2419135.40     13564139.95
#Sta/Elev= 30
  3209.7  370.19  3278.4  367.97  3426.9  367.06  3540.2  364.47  3564.5  362.42
  3617.0  362.12  3708.5  359.77  3778.7  360.75  4487.8  354.19  4618.9  353.01
  4674.7  350.85  4705.3  352.87  4807.1  352.89  4883.5  352.50  4947.7  347.62
  4975.4  345.47  4975.9  344.97  4992.6  345.47  5109.3  351.82  5191.6  356.65
  5367.1  365.58  5388.4  368.07  5407.2  367.07  5478.5  370.01  5548.0  374.37
  5594.5  375.36  5665.1  380.96  5819.4  386.70  5992.2  395.91  6228.7  400.00
#Mann=11,-1,0
  3209.7    0.04       0  3617.0   0.035       0  4487.8    0.05       0
  4807.1     0.1       0  4947.7    0.04       0  4975.4    0.04       0
  4992.6    0.04       0  5109.3     0.1       0  5191.6    0.04       0
  5478.5    0.05       0  5594.5    0.04       0
Bank Sta=4975.4,4992.6
Exp/Cntr=0.3,0.1

Type RM Length L Ch R = 1,9267,355,355,355
BEGIN DESCRIPTION:
Mapping XS 3df788f5
END DESCRIPTION:
XS GIS Cut Line= 5
      2422066.16     13564949.80      2420919.13     13564491.46
      2420567.57     13564027.05      2420437.36     13563957.61
      2419499.97     13563788.36
#Sta/Elev= 30
  3257.0  371.25  3906.9  358.93  4152.1  357.15  4304.5  354.45  4361.7  351.87
  4391.4  352.42  4507.0  348.60  4542.3  349.10  4577.4  346.56  4662.7  349.15
  4777.5  350.74  4874.8  349.98  4935.6  348.64  4997.7  344.06  4998.2  343.56
  5015.0  344.06  5064.5  346.63  5126.8  353.15  5212.5  356.00  5336.6  357.80
  5425.2  360.00  5558.1  365.14  5641.3  369.05  5681.9  369.58  5814.0  376.76
  5895.3  378.64  5915.6  380.92  5940.7  380.66  6088.4  387.67  6174.8  390.12
#Mann=12,-1,0
  3257.0    0.04       0  3906.9   0.035       0  4304.5    0.05       0
  4577.4     0.1       0  4662.7    0.05       0  4874.8     0.1       0
  4997.7    0.05       0  5015.0     0.1       0  5126.8    0.05       0
  5336.6   0.035       0  5425.2    0.05       0  5558.1    0.04       0
Bank Sta=4997.7,5015
Exp/Cntr=0.3,0.1

Type RM Length L Ch R = 1,8912,408,408,408
BEGIN DESCRIPTION:
Mapping XS 3916b0ce
END DESCRIPTION:
XS GIS Cut Line= 4
      2421860.94     13564200.65      2421209.93     13563883.82
      2420337.54     13563692.85      2419518.58     13563671.19
#Sta/Elev= 30
  3831.8  368.14  3855.6  368.45  3906.3  364.90  3928.8  365.94  3968.3  362.75
  4005.2  362.57  4058.5  359.29  4317.7  352.48  4693.9  350.08  4816.8  351.37
  4919.1  347.48  4977.1  342.75  5002.4  342.15  5002.9  341.65  5020.2  342.15
  5051.8  343.33  5137.0  346.85  5246.7  355.05  5277.8  355.89  5354.5  357.88
  5501.4  360.48  5587.2  363.91  5621.5  363.91  5681.5  367.22  5701.5  366.57
  5751.5  369.85  5781.5  369.42  5901.6  375.00  5921.6  377.05  6268.1  389.88
#Mann=8,-1,0
  3831.8    0.04       0  4977.1    0.05       0  5002.4    0.05       0
  5020.2    0.05       0  5051.8     0.1       0  5277.8    0.05       0
  5354.5   0.035       0  5587.2    0.04       0
Bank Sta=5002.4,5020.2
Exp/Cntr=0.3,0.1

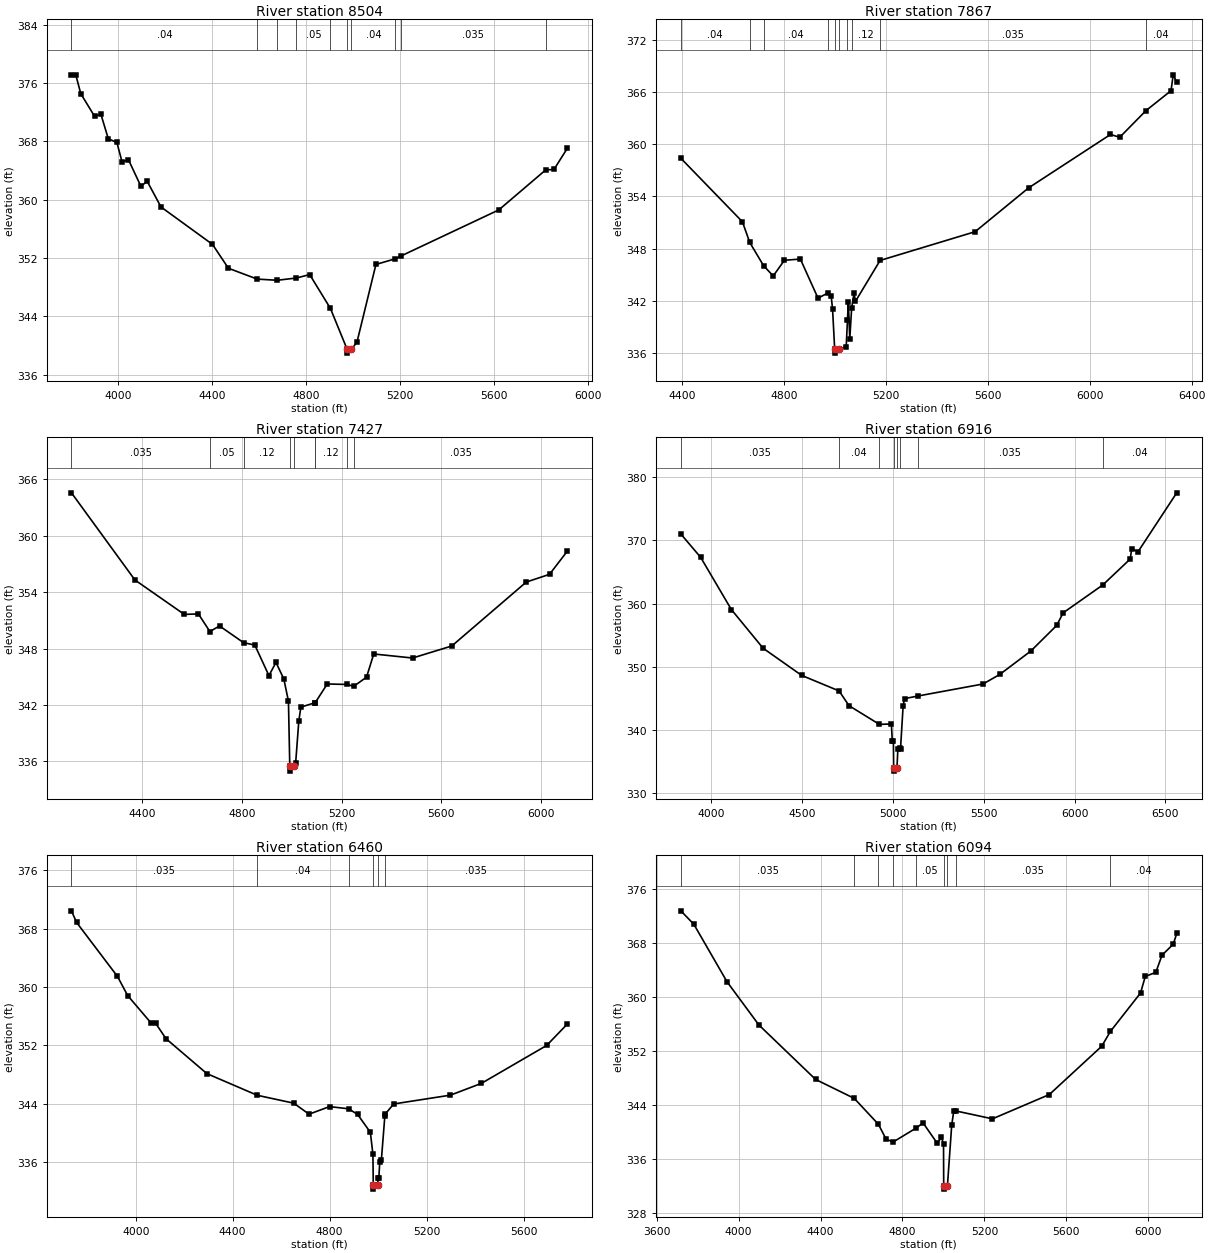
Type RM Length L Ch R = 1,8504,637,637,637
BEGIN DESCRIPTION:
Mapping XS 3e1f7ac4
END DESCRIPTION:
XS GIS Cut Line= 4
      2422091.03     13563862.13      2421505.07     13563514.90
      2420754.20     13563432.44      2420100.03     13563588.40
#Sta/Elev= 30
  3802.7  377.05  3821.0  377.12  3842.4  374.53  3900.9  371.44  3928.2  371.69
  3959.4  368.34  3995.7  367.86  4017.9  365.18  4045.1  365.48  4097.8  361.85
  4125.0  362.51  4183.5  359.00  4402.5  353.87  4470.1  350.60  4592.7  349.11
  4677.7  348.95  4759.4  349.26  4815.9  349.73  4904.2  345.08  4975.4  339.46
  4975.9  338.96  4993.2  339.46  5017.1  340.48  5097.6  351.12  5180.5  351.90
  5204.9  352.29  5620.3  358.60  5818.9  364.06  5855.2  364.16  5911.7  367.05
#Mann=10,-1,0
  3802.7    0.04       0  4592.7    0.05       0  4677.7    0.04       0
  4759.4    0.05       0  4904.2    0.04       0  4975.4    0.04       0
  4993.2    0.04       0  5180.5    0.05       0  5204.9   0.035       0
  5818.9    0.04       0
Bank Sta=4975.4,4993.2
Exp/Cntr=0.3,0.1

Type RM Length L Ch R = 1,7867,440,440,440
BEGIN DESCRIPTION:
LITTLE SALT CREEK 11.0
END DESCRIPTION:
XS GIS Cut Line= 3
      2421824.96     13563174.98      2421275.00     13562925.00
      2420075.04     13563524.98
#Sta/Elev= 30
  4395.8  358.38  4637.4  351.09  4666.1  348.72  4720.4  346.05  4758.2  344.87
  4802.2  346.67  4864.8  346.81  4934.0  342.32  4974.4  342.94  4985.6  342.57
  4991.1  341.07  4999.3  336.51  4999.8  336.01  5017.2  336.51  5044.6  336.74
  5049.6  339.82  5053.0  341.92  5058.6  337.61  5066.0  341.19  5075.4  342.90
  5081.0  341.96  5177.6  346.65  5550.5  349.95  5760.2  354.98  6081.6  361.11
  6117.9  360.79  6220.4  363.84  6319.2  366.14  6327.6  367.96  6341.5  367.12
#Mann=10,-1,0
  4395.8    0.04       0  4666.1    0.05       0  4720.4    0.04       0
  4974.4    0.12       0  4999.3    0.05       0  5017.2    0.12       0
  5049.6    0.04       0  5066.0    0.12       0  5177.6   0.035       0
  6220.4    0.04       0
Bank Sta=4999.3,5017.2
Exp/Cntr=0.3,0.1

Type RM Length L Ch R = 1,7427,511,511,511
BEGIN DESCRIPTION:
LITTLE SALT CREEK 10.0
END DESCRIPTION:
XS GIS Cut Line= 3
      2421924.97     13561975.03      2421325.00     13562575.00
      2420424.97     13563275.03
#Sta/Elev= 30
  4116.4  364.57  4370.9  355.30  4568.9  351.64  4625.5  351.69  4671.4  349.82
  4710.3  350.41  4806.9  348.63  4851.7  348.38  4908.3  345.13  4936.6  346.53
  4968.1  344.77  4986.6  342.41  4992.0  335.47  4992.5  334.97  5010.2  335.47
  5015.6  335.87  5028.2  340.31  5036.4  341.78  5092.8  342.24  5094.0  342.25
  5142.2  344.24  5219.6  344.19  5248.8  344.00  5299.7  344.96  5328.7  347.43
  5484.3  347.00  5641.7  348.28  5940.4  355.08  6033.6  355.90  6105.1  358.37
#Mann=9,-1,0
  4116.4   0.035       0  4671.4    0.05       0  4806.9    0.12       0
  4992.0    0.05       0  5010.2    0.12       0  5092.8    0.05       0
  5094.0    0.12       0  5219.6    0.05       0  5248.8   0.035       0
Bank Sta=4992,5010.2
Exp/Cntr=0.3,0.1

Type RM Length L Ch R = 1,6916,456,456,456
BEGIN DESCRIPTION:
LITTLE SALT CREEK 9.0
END DESCRIPTION:
XS GIS Cut Line= 3
      2421975.00     13561725.00      2420975.00     13562325.00
      2419775.03     13563324.97
#Sta/Elev= 30
  3833.7  371.02  3942.5  367.34  4111.6  359.07  4286.6  352.94  4498.4  348.65
  4704.3  346.19  4758.9  343.86  4926.0  340.90  4992.1  340.96  4997.0  338.25
  5003.1  338.25  5004.5  334.00  5005.0  333.50  5022.7  334.00  5027.9  337.08
  5039.8  337.09  5042.2  337.03  5056.5  343.76  5064.3  344.97  5136.4  345.38
  5496.5  347.29  5588.9  348.81  5759.4  352.51  5901.3  356.55  5937.1  358.55
  6155.1  362.96  6306.2  367.07  6314.0  368.68  6349.1  368.22  6561.9  377.54
#Mann=8,-1,0
  3833.7   0.035       0  4704.3    0.04       0  4926.0    0.05       0
  5004.5    0.05       0  5022.7    0.05       0  5039.8    0.12       0
  5136.4   0.035       0  6155.1    0.04       0
Bank Sta=5004.5,5022.7
Exp/Cntr=0.3,0.1

Type RM Length L Ch R = 1,6460,366,366,366
BEGIN DESCRIPTION:
LITTLE SALT CREEK 8.0
END DESCRIPTION:
XS GIS Cut Line= 3
      2421925.02     13561624.99      2420725.00     13562025.00
      2420124.97     13562525.03
#Sta/Elev= 30
  3734.8  370.43  3755.9  368.84  3924.6  361.44  3966.7  358.82  4061.6  355.12
  4082.7  354.99  4124.8  352.91  4293.5  348.12  4501.5  345.15  4651.9  344.07
  4715.1  342.56  4799.5  343.60  4877.9  343.30  4915.4  342.53  4968.1  340.07
  4978.6  337.06  4980.1  332.79  4980.6  332.29  4998.3  332.79  4999.7  333.83
  5003.0  333.83  5006.9  336.04  5013.4  336.24  5027.7  342.27  5030.3  342.61
  5064.2  343.96  5298.5  345.17  5426.0  346.78  5695.5  351.98  5780.8  354.92
#Mann=6,-1,0
  3734.8   0.035       0  4501.5    0.04       0  4877.9    0.12       0
  4980.1    0.05       0  4998.3    0.12       0  5030.3   0.035       0
Bank Sta=4980.1,4998.3
Exp/Cntr=0.3,0.1

Type RM Length L Ch R = 1,6094,557,557,557
BEGIN DESCRIPTION:
Mapping XS d8d15ae1
END DESCRIPTION:
XS GIS Cut Line= 4
      2421986.83     13561509.70      2421157.85     13561696.32
      2420502.47     13561691.98      2419669.60     13562073.71
#Sta/Elev= 30
  3717.9  372.77  3781.3  370.78  3943.5  362.25  4099.0  355.85  4375.8  347.78
  4564.6  344.97  4682.6  341.13  4720.5  338.90  4755.3  338.52  4866.8  340.57
  4900.5  341.34  4970.5  338.29  4990.5  339.25  5000.5  338.15  5001.4  332.02
  5001.9  331.52  5019.6  332.02  5040.5  341.01  5050.5  343.10  5063.4  343.09
  5239.5  341.94  5517.2  345.54  5773.0  352.70  5815.2  354.89  5962.5  360.59
  5985.5  363.04  6037.0  363.65  6067.3  366.19  6122.3  367.83  6139.2  369.41
#Mann=9,-1,0
  3717.9   0.035       0  4564.6    0.04       0  4682.6    0.05       0
  4755.3    0.04       0  4866.8    0.05       0  5001.4    0.05       0
  5019.6    0.05       0  5063.4   0.035       0  5815.2    0.04       0
Bank Sta=5001.4,5019.6
Exp/Cntr=0.3,0.1