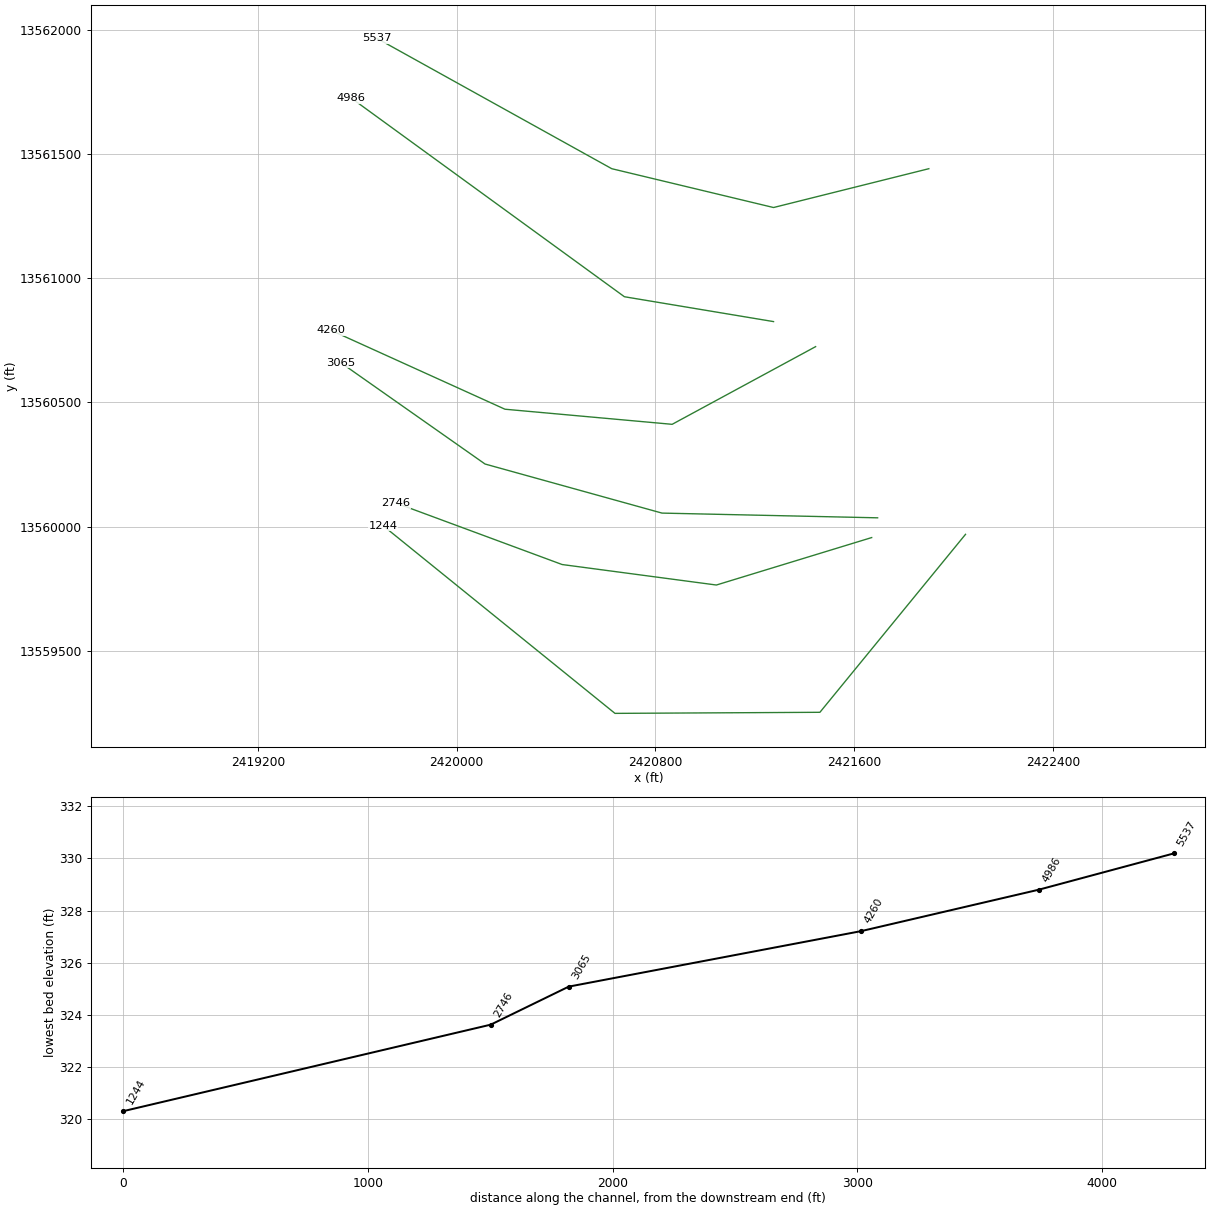
HEC-RAS study LITTLE SALT CREEK.prj: LITTLE SALT CREEK Base Level Engineering

--- LITTLE SALT CREEK.g01 (geometry) --- (continued)

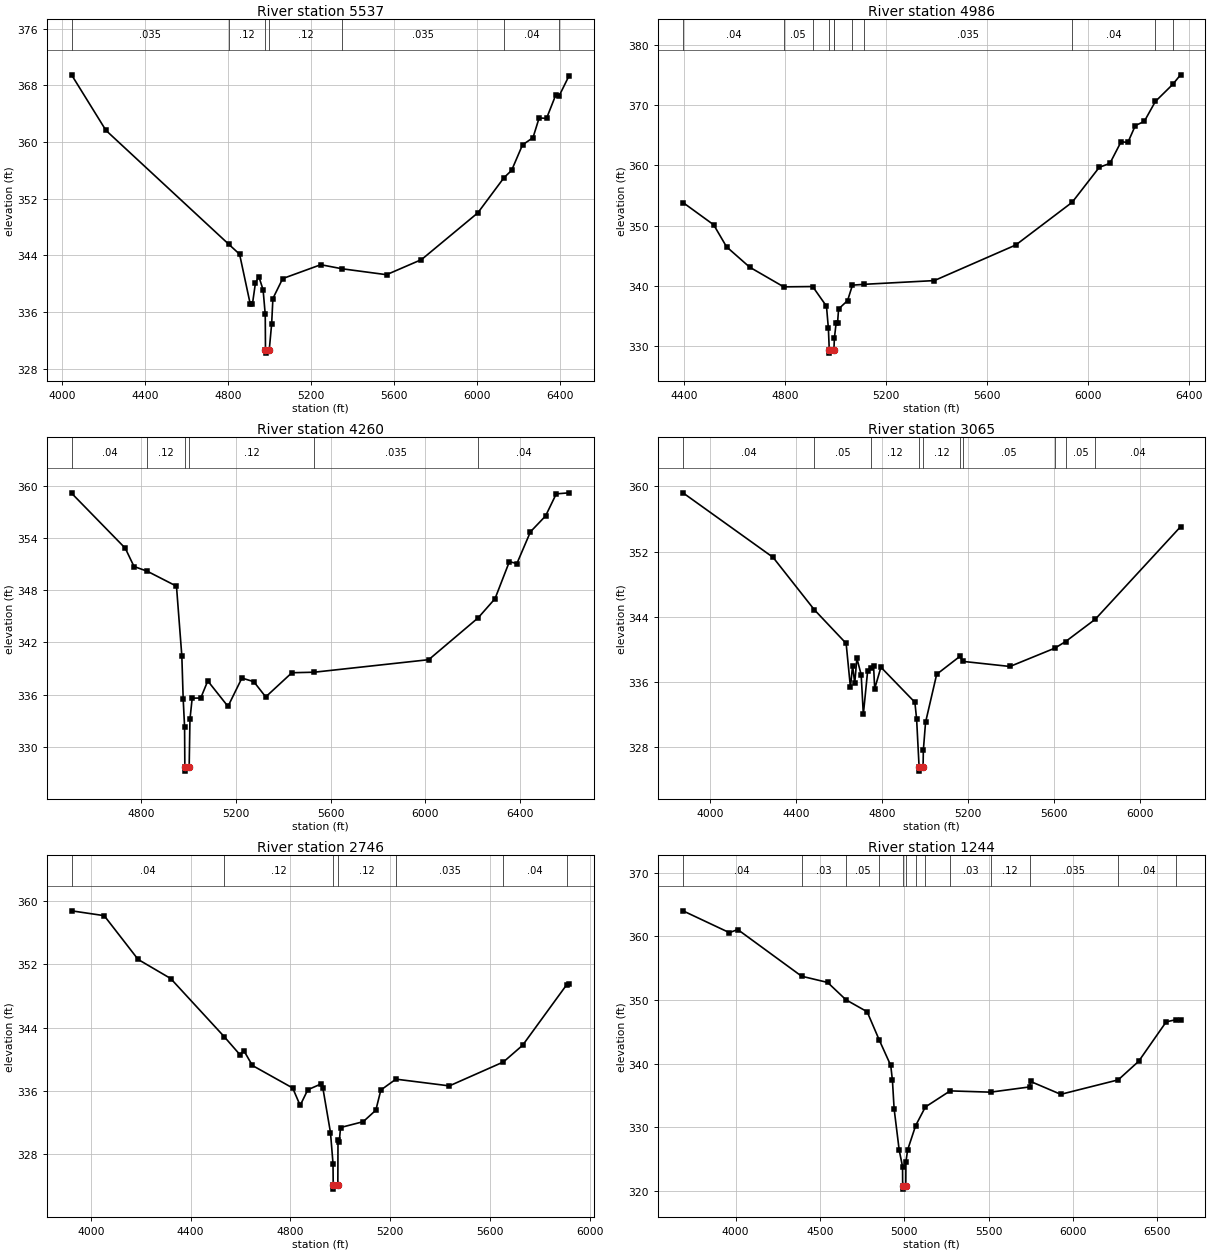
Type RM Length L Ch R = 1,5537,551,551,551
BEGIN DESCRIPTION:
Mapping XS 6aadb8d5
END DESCRIPTION:
XS GIS Cut Line= 4
      2421900.04     13561440.25      2421275.04     13561284.00
      2420623.99     13561440.25      2419678.88     13561964.83
#Sta/Elev= 30
  4047.4  369.47  4212.9  361.63  4805.0  345.53  4856.2  344.15  4907.6  337.10
  4917.9  337.09  4932.5  340.10  4948.8  340.99  4969.3  339.13  4979.6  335.65
  4980.8  330.69  4981.3  330.19  4999.1  330.69  5010.5  334.33  5016.5  337.90
  5063.6  340.71  5247.0  342.67  5350.5  342.09  5563.4  341.26  5731.6  343.39
  6002.8  349.99  6128.9  354.96  6165.3  355.98  6217.8  359.58  6268.3  360.60
  6297.9  363.39  6333.5  363.32  6377.9  366.63  6392.8  366.42  6442.1  369.35
#Mann=7,-1,0
  4047.4   0.035       0  4805.0    0.12       0  4980.8    0.05       0
  4999.1    0.12       0  5350.5   0.035       0  6128.9    0.04       0
  6392.8    0.03       0
Bank Sta=4980.8,4999.1
Exp/Cntr=0.3,0.1

Type RM Length L Ch R = 1,4986,726,726,726
BEGIN DESCRIPTION:
LITTLE SALT CREEK 5.0
END DESCRIPTION:
XS GIS Cut Line= 3
      2421274.99     13560825.00      2420675.00     13560925.00
      2419575.01     13561724.99
#Sta/Elev= 30
  4396.2  353.84  4517.8  350.13  4568.5  346.48  4659.8  343.10  4794.8  339.82
  4909.3  339.87  4963.9  336.60  4971.5  332.90  4975.0  329.30  4975.5  328.80
  4993.3  329.30  4995.2  331.28  5001.9  333.73  5007.6  333.73  5011.8  336.14
  5047.4  337.54  5066.6  340.10  5112.8  340.24  5390.5  340.86  5712.8  346.78
  5935.9  353.88  6043.1  359.69  6085.2  360.35  6129.3  363.94  6156.3  363.83
  6185.7  366.63  6221.3  367.33  6265.0  370.64  6333.5  373.47  6364.6  375.07
#Mann=11,-1,0
  4396.2    0.04       0  4794.8    0.05       0  4909.3    0.12       0
  4975.0    0.05       0  4993.3    0.12       0  4995.2    0.05       0
  5066.6    0.12       0  5112.8   0.035       0  5935.9    0.04       0
  6265.0    0.03       0  6333.5    0.04       0
Bank Sta=4975,4993.3
Exp/Cntr=0.3,0.1

Type RM Length L Ch R = 1,4260,1195,1195,1195
BEGIN DESCRIPTION:
Mapping XS 50687da6
END DESCRIPTION:
XS GIS Cut Line= 4
      2421444.35     13560724.13      2420867.05     13560411.60
      2420194.31     13560472.37      2419495.53     13560789.20
#Sta/Elev= 30
  4506.9  359.16  4733.6  352.83  4770.5  350.73  4826.2  350.19  4949.6  348.47
  4972.2  340.45  4977.9  335.51  4983.8  332.31  4984.9  327.71  4985.4  327.21
  5003.2  327.71  5006.5  333.17  5015.9  335.60  5052.0  335.61  5081.6  337.58
  5166.9  334.65  5225.7  337.91  5275.9  337.49  5326.1  335.74  5436.5  338.52
  5530.7  338.58  6013.8  340.02  6222.3  344.83  6293.5  347.03  6354.1  351.29
  6385.8  351.07  6443.0  354.72  6506.8  356.54  6551.8  359.08  6606.1  359.20
#Mann=6,-1,0
  4506.9    0.04       0  4826.2    0.12       0  4984.9    0.05       0
  5003.2    0.12       0  5530.7   0.035       0  6222.3    0.04       0
Bank Sta=4984.9,5003.2
Exp/Cntr=0.3,0.1

Type RM Length L Ch R = 1,3065,319,319,319
BEGIN DESCRIPTION:
Mapping XS d6cfcd2e
END DESCRIPTION:
XS GIS Cut Line= 4
      2421693.97     13560035.36      2420826.22     13560054.35
      2420114.16     13560251.83      2419534.58     13560659.00
#Sta/Elev= 30
  3875.1  359.20  4294.2  351.29  4485.8  344.88  4634.3  340.74  4654.3  335.35
  4664.3  338.01  4674.3  335.87  4684.3  338.92  4704.3  336.89  4714.3  332.03
  4734.3  337.34  4747.8  337.77  4762.0  337.96  4767.2  335.19  4796.2  337.82
  4954.2  333.52  4962.3  331.44  4973.8  325.58  4974.3  325.08  4992.3  325.58
  4993.6  327.65  5003.8  331.06  5055.6  336.95  5165.1  339.18  5175.8  338.54
  5396.6  337.91  5605.6  340.16  5655.2  340.96  5793.5  343.70  6190.3  355.04
#Mann=10,-1,0
  3875.1    0.04       0  4485.8    0.05       0  4747.8    0.12       0
  4973.8    0.05       0  4992.3    0.12       0  5165.1   0.035       0
  5175.8    0.05       0  5605.6   0.035       0  5655.2    0.05       0
  5793.5    0.04       0
Bank Sta=4973.8,4992.3
Exp/Cntr=0.3,0.1

Type RM Length L Ch R = 1,2746,1502,1502,1502
BEGIN DESCRIPTION:
Mapping XS 3eae6578
END DESCRIPTION:
XS GIS Cut Line= 4
      2421670.00     13559955.87      2421045.00     13559764.90
      2420424.34     13559847.37      2419755.90     13560094.78
#Sta/Elev= 30
  3923.3  358.77  4054.0  358.16  4189.9  352.63  4320.2  350.22  4534.5  342.88
  4597.0  340.62  4613.8  341.08  4647.4  339.24  4808.9  336.39  4838.7  334.19
  4869.4  336.17  4922.1  336.90  4929.9  336.35  4960.2  330.76  4970.3  326.85
  4971.1  324.12  4971.6  323.62  4989.6  324.12  4990.3  329.84  4995.3  329.61
  5000.5  331.40  5091.3  332.14  5141.8  333.59  5161.9  336.14  5222.3  337.51
  5436.2  336.66  5652.6  339.68  5729.6  341.79  5905.9  349.43  5915.7  349.48
#Mann=7,-1,0
  3923.3    0.04       0  4534.5    0.12       0  4971.1    0.05       0
  4989.6    0.12       0  5222.3   0.035       0  5652.6    0.04       0
  5905.9    0.05       0
Bank Sta=4971.1,4989.6
Exp/Cntr=0.3,0.1

Type RM Length L Ch R = 1,1244,0,0,0
BEGIN DESCRIPTION:
Mapping XS 36affcb4
END DESCRIPTION:
XS GIS Cut Line= 4
      2422047.60     13559968.89      2421461.67     13559252.75
      2420637.01     13559248.41      2419703.88     13560003.60
#Sta/Elev= 30
  3688.1  364.01  3963.3  360.58  4012.8  361.07  4391.6  353.74  4545.9  352.76
  4654.4  350.04  4780.1  348.16  4851.1  343.77  4920.1  339.72  4930.1  337.39
  4940.1  332.92  4970.1  326.45  4990.1  323.83  4990.8  320.80  4991.3  320.30
  5009.3  320.80  5010.1  324.56  5020.1  326.45  5068.0  330.29  5125.4  333.20
  5272.3  335.73  5511.9  335.53  5743.0  336.35  5749.4  337.21  5928.2  335.19
  6268.9  337.46  6390.3  340.38  6553.4  346.57  6614.3  346.93  6638.5  346.80
#Mann=13,-1,0
  3688.1    0.04       0  4391.6    0.03       0  4654.4    0.05       0
  4851.1    0.12       0  4990.8    0.05       0  5009.3    0.12       0
  5068.0    0.03       0  5125.4    0.12       0  5272.3    0.03       0
  5511.9    0.12       0  5743.0   0.035       0  6268.9    0.04       0
  6614.3    0.05       0
Bank Sta=4990.8,5009.3
Exp/Cntr=0.3,0.1

Chan Stop Cuts=-1