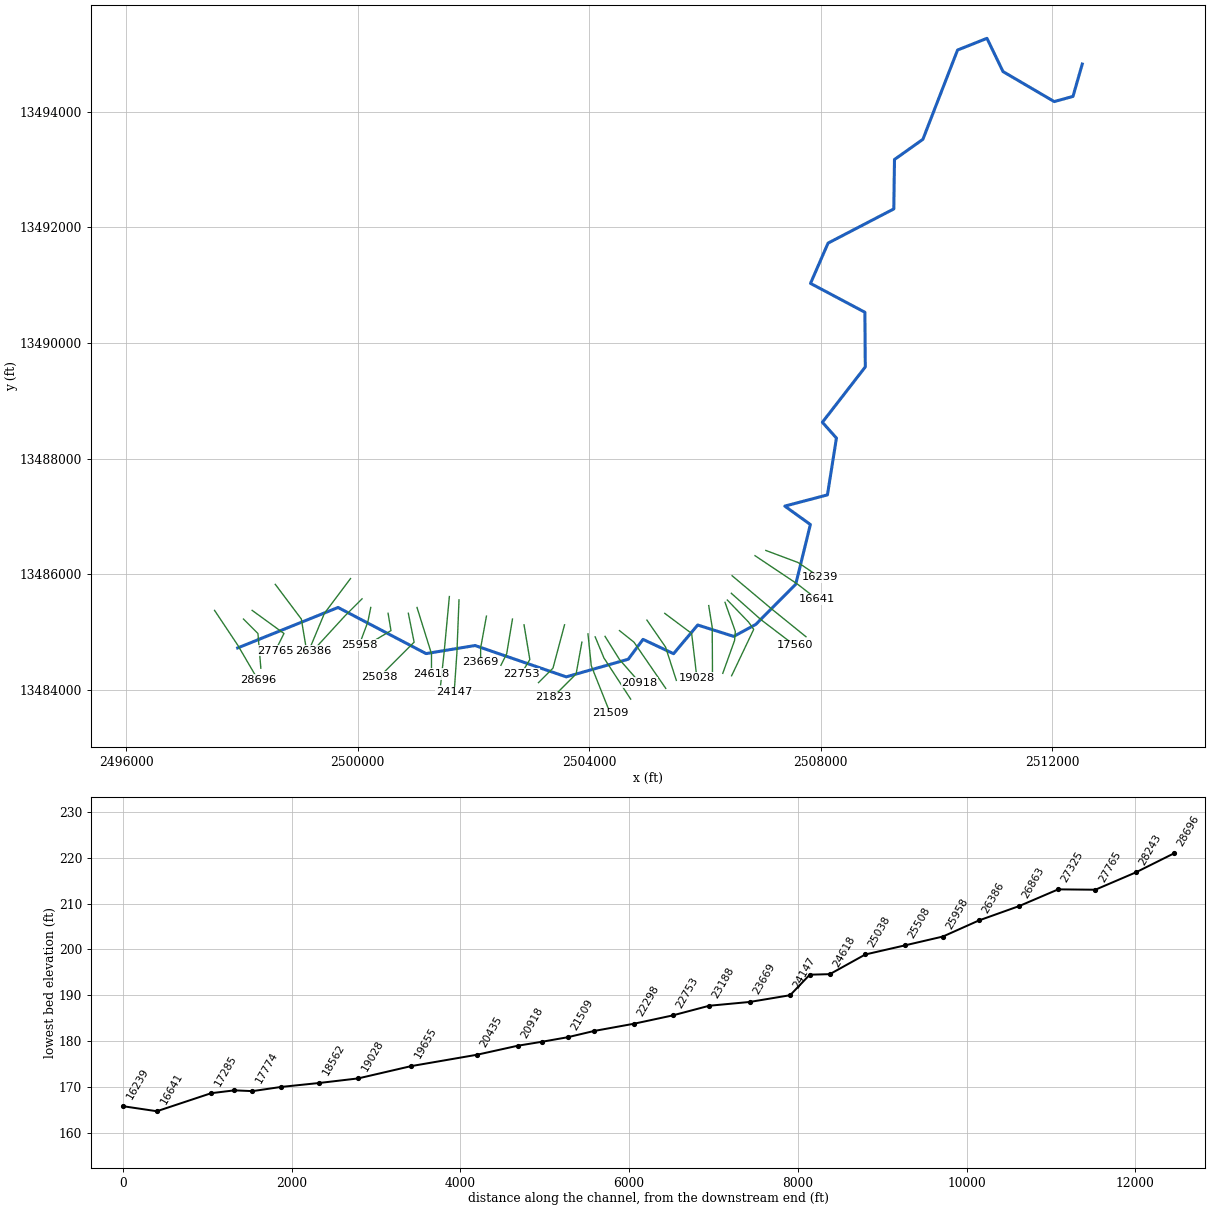
--- MILBY CREEK.prj (project) ---

Proj Title=MILBY CREEK Base Level Engineering
Current Plan=p01
Default Exp/Contr=0.3,0.1
English Units
Geom File=g01
Flow File=f01
Plan File=p01
Y Axis Title=Elevation
X Axis Title(PF)=Main Channel Distance
X Axis Title(XS)=Station
BEGIN DESCRIPTION:
MILBY CREEK
END DESCRIPTION:
DSS Export Rating Curves= 0
DSS Export Rating Curve Sorted= 0
DSS Export Volume Flow Curves= 0
DXF OffsetX= 0
DXF OffsetY= 0
DXF ScaleX= 1
DXF ScaleY= 10

--- MILBY CREEK.p01 (plan) ---

Plan Title=Multiple Run
Short Identifier=Multiple
Geom File=g01
Flow File=f01
Subcritical Flow
K Sum by GR= 0
Std Step Tol= 0.01
Critical Tol= 0.01
Num of Std Step Trials= 20
Max Error Tol= 0.3
Flow Tol Ratio= 0.001
Split Flow NTrial= 30
Split Flow Tol= 0.02
Split Flow Ratio= 0.02
Log Output Level= 0
Friction Slope Method= 1
Unsteady Friction Slope Method= 2
Unsteady Bridges Friction Slope Method= 1
Parabolic Critical Depth
Global Vel Dist=  1 , 1 , 1
Global Log Level= 0
CheckData=True
Encroach Param= -1, 0, 0, 0
BEGIN DESCRIPTION:
Multiple Run
END DESCRIPTION:

--- MILBY CREEK.f01 (steady flow) ---

Flow Title=Multiple
Number of Profiles=7
Profile Names=10-year,25-year,50-year,1pct_min,100-year,1pct_plu,500-year
River Rch & RM= MILBY CREEK,Reach-1,28696
     534     846    1124     723    1443    2880    2351
River Rch & RM= MILBY CREEK,Reach-1,25958
     860    1402    1897    1240    2475    4938    4171
River Rch & RM= MILBY CREEK,Reach-1,21823
    1298    2159    2959    1958    3907    7795    6743
River Rch & RM= MILBY CREEK,Reach-1,17560
    1767    2964    4085    2715    5417   10809    9431
River Rch & RM= MILBY CREEK,Reach-1,12224
    2221    3757    5207    3476    6936   13840   12189
River Rch & RM= MILBY CREEK,Reach-1,7805
    2379    4026    5581    3725    7433   14831   13058
Boundary for River Rch & Prof#=MILBY CREEK,Reach-1,1
Up Type=0
Dn Type=3
Dn Slope=0.005
Boundary for River Rch & Prof#=MILBY CREEK,Reach-1,2
Up Type=0
Dn Type=3
Dn Slope=0.005
Boundary for River Rch & Prof#=MILBY CREEK,Reach-1,3
Up Type=0
Dn Type=3
Dn Slope=0.005
Boundary for River Rch & Prof#=MILBY CREEK,Reach-1,4
Up Type=0
Dn Type=3
Dn Slope=0.005
Boundary for River Rch & Prof#=MILBY CREEK,Reach-1,5
Up Type=0
Dn Type=3
Dn Slope=0.005
Boundary for River Rch & Prof#=MILBY CREEK,Reach-1,6
Up Type=0
Dn Type=3
Dn Slope=0.005
Boundary for River Rch & Prof#=MILBY CREEK,Reach-1,7
Up Type=0
Dn Type=3
Dn Slope=0.005

--- MILBY CREEK.g01 (geometry) ---

Geom Title=Existing Conditions
Program Version=4.10

River Reach=MILBY CREEK     ,Reach-1
Reach XY= 30
        2497925.       13484725.      2499659.76     13485425.16
      2501180.93     13484627.26      2502028.32     13484766.96
      2503604.79     13484224.64      2504677.74     13484530.35
      2504931.17     13484873.24      2505459.79      13484625.5
      2505876.72     13485121.66      2506499.97      13484924.5
      2506881.32      13485132.5      2507571.53      13485826.5
      2507824.77     13486859.78       2507382.6     13487178.32
      2508119.66     13487372.26      2508275.04     13488355.02
       2508032.2     13488628.44      2508773.95     13489585.43
        2508767.     13490531.38      2507826.97      13491030.9
      2508130.45     13491727.45      2509266.87     13492318.93
      2509278.55     13493173.53      2509769.53     13493522.55
      2510368.81     13495067.19      2510877.44     13495269.61
      2511154.52     13494694.63      2512040.21     13494175.51
      2512364.25     13494265.29        2512525.       13494825.

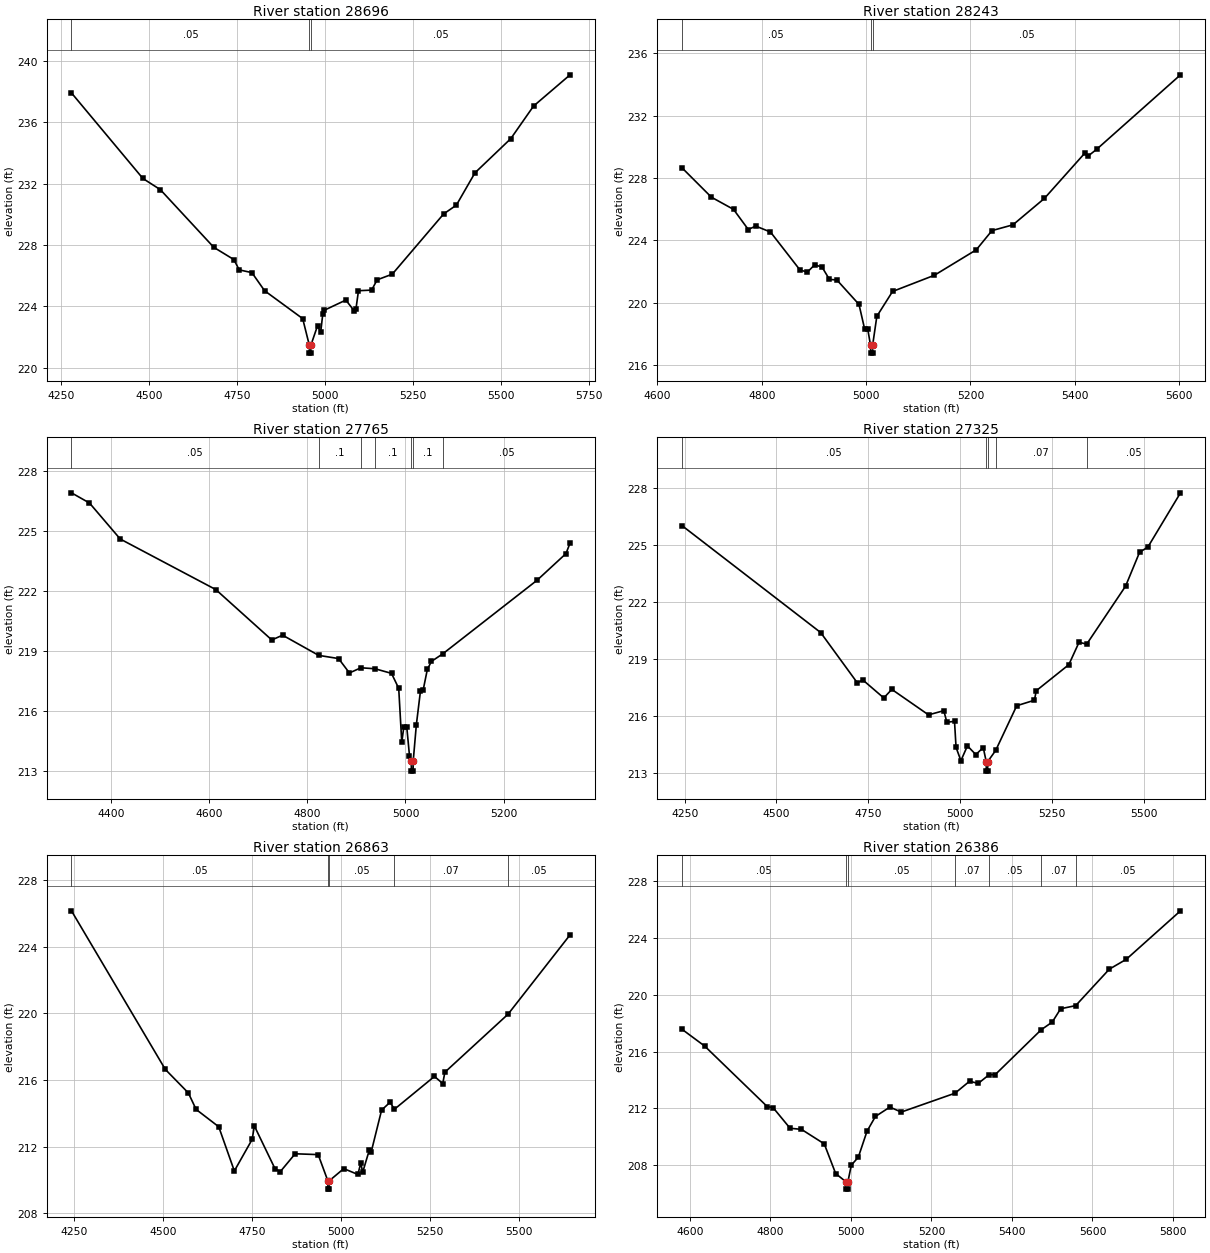
Type RM Length L Ch R = 1 ,28696   ,453,453,453
BEGIN DESCRIPTION:
MILBY CREEK 50.0
END DESCRIPTION:
XS GIS Cut Line= 3
      2497525.01     13485374.98        2497925.       13484775.
      2498274.99     13484175.01
#Sta/Elev= 30
  4280.2  237.91    4483  232.33  4532.6   231.6  4684.3  227.84  4741.4  227.04
  4756.4  226.37  4792.5  226.19  4828.5  225.01  4936.7  223.19  4955.7  221.44
    4956  220.94  4959.5  220.94  4959.7  221.44  4978.8  222.72  4987.8  222.31
  4993.8   223.5  4998.3  223.74  5059.2   224.4  5082.3  223.72  5088.1  223.85
  5095.1  225.01  5132.4  225.05  5148.1  225.72  5191.1  226.09    5337  230.02
    5373  230.59  5425.9   232.7  5527.6  234.93  5592.1  237.05  5695.9  239.09
#Mann= 3 ,-1 , 0
  4280.2     .05       0  4955.7     .05       0  4959.7     .05       0
Bank Sta=4955.7,4959.7
XS Rating Curve= 0 ,0
Exp/Cntr=0.3,0.1

Type RM Length L Ch R = 1 ,28243   ,478,478,478
BEGIN DESCRIPTION:
MILBY CREEK 49.0
END DESCRIPTION:
XS GIS Cut Line= 3
      2498024.97     13485225.03        2498275.       13484975.
        2498325.     13484374.98
#Sta/Elev= 30
  4646.9  228.66  4703.5  226.77  4745.9  225.99  4774.2   224.7  4788.4  224.92
  4816.7  224.54  4873.2  222.11  4887.4  221.97  4901.5  222.44  4915.6  222.29
  4929.8   221.5  4943.9  221.47  4986.4   219.9    4997  218.35    5003  218.35
  5008.5  217.28  5008.8  216.78  5012.3  216.78  5012.5  217.28  5020.6  219.14
  5050.7  220.73    5131  221.77  5211.2   223.4  5241.3  224.63  5281.5     225
  5341.7  226.69  5419.4   229.6  5424.5  229.38    5442  229.84  5602.6  234.61
#Mann= 3 ,-1 , 0
  4646.9     .05       0  5008.5     .05       0  5012.5     .05       0
Bank Sta=5008.5,5012.5
XS Rating Curve= 0 ,0
Exp/Cntr=0.3,0.1

Type RM Length L Ch R = 1 ,27765   ,440,440,440
BEGIN DESCRIPTION:
MILBY CREEK 48.0
END DESCRIPTION:
XS GIS Cut Line= 3
      2498175.02     13485374.99        2498725.       13484975.
      2498574.98     13484674.97
#Sta/Elev= 30
  4319.8  226.93  4356.5  226.42  4419.1  224.62  4613.8  222.09  4727.8  219.57
  4749.8  219.81  4823.3   218.8  4863.8  218.64  4885.9  217.92  4909.3  218.18
  4938.1  218.13  4971.6   217.9  4986.3  217.15  4992.5  214.45  4996.8  215.24
  5002.6  215.24  5008.2  213.79  5011.8  213.51  5012.1  213.01  5015.6  213.01
  5015.8  213.51  5022.2  215.33  5030.6  217.02  5036.2  217.08  5044.6   218.1
    5053   218.5  5076.2  218.88  5268.2  222.56  5326.9  223.89  5335.3  224.42
#Mann= 7 ,-1 , 0
  4319.8     .05       0  4823.3      .1       0  4909.3     .05       0
  4938.1      .1       0  5011.8     .05       0  5015.8      .1       0
  5076.2     .05       0
Bank Sta=5011.8,5015.8
XS Rating Curve= 0 ,0
Exp/Cntr=0.3,0.1

Type RM Length L Ch R = 1 ,27325   ,462,462,462
BEGIN DESCRIPTION:
MILBY CREEK 47.0
END DESCRIPTION:
XS GIS Cut Line= 3
        2498575.       13485825.        2499025.       13485225.
        2499125.     13484624.98
#Sta/Elev= 30
  4242.4  226.01  4620.5  220.38  4720.5  217.73  4735.1  217.89  4792.4  216.94
  4814.3  217.39  4914.3  216.05  4955.9  216.27  4964.3  215.66  4985.1  215.71
  4989.3  214.34  5002.5  213.64  5020.3  214.42  5043.1  213.96  5063.4  214.33
  5071.5  213.59  5071.8  213.09  5075.3  213.09  5075.5  213.59  5097.3  214.18
  5154.6  216.53  5202.8  216.82  5207.8  217.32  5296.5  218.69  5324.4  219.87
  5345.2  219.77  5451.1  222.82  5489.2   224.6    5512  224.88  5600.7  227.73
#Mann= 5 ,-1 , 0
  4242.4     .05       0  5071.5     .05       0  5075.5     .05       0
  5097.3     .07       0  5345.2     .05       0
Bank Sta=5071.5,5075.5
XS Rating Curve= 0 ,0
Exp/Cntr=0.3,0.1

Type RM Length L Ch R = 1 ,26863   ,477,477,477
BEGIN DESCRIPTION:
MILBY CREEK 46.0
END DESCRIPTION:
XS GIS Cut Line= 3
      2499874.98     13485924.98        2499425.       13485325.
      2499174.99     13484724.97
#Sta/Elev= 30
  4243.7  226.14  4507.2  216.63  4571.8  215.22  4593.7  214.23  4657.2  213.19
    4701  210.54    4751  212.43  4757.2  213.24  4815.5  210.66  4830.1   210.5
  4871.8  211.57  4936.4  211.52  4963.5  209.95  4963.8  209.45  4967.3  209.45
  4967.5  209.95  5008.3  210.68  5047.8  210.33    5056  211.01  5061.4  210.46
  5079.8  211.78  5085.2  211.67  5114.5  214.19  5138.3  214.66  5150.5  214.24
  5262.9  216.21  5286.2  215.78  5292.1  216.46  5469.5  219.94  5643.7   224.7
#Mann= 5 ,-1 , 0
  4243.7     .05       0  4963.5     .05       0  4967.5     .05       0
  5150.5     .07       0  5469.5     .05       0
Bank Sta=4963.5,4967.5
XS Rating Curve= 0 ,0
Exp/Cntr=0.3,0.1

Type RM Length L Ch R = 1 ,26386   ,428,428,428
BEGIN DESCRIPTION:
MILBY CREEK 45.0
END DESCRIPTION:
XS GIS Cut Line= 3
      2500075.03     13485575.03        2499775.       13485275.
      2499224.97     13484674.97
#Sta/Elev= 30
  4580.3  217.58  4636.9  216.39  4792.5  212.12  4806.6  212.06    4849   210.6
  4877.3  210.52  4933.9   209.5  4962.2  207.41  4988.5  206.81  4988.7  206.31
  4992.2  206.31  4992.5  206.81  5001.1     208  5018.5  208.56  5040.1  210.39
    5061  211.43  5096.8  212.09  5125.2  211.74  5258.7  213.07  5294.7  213.91
  5316.3  213.76  5343.7  214.38  5358.2  214.37  5472.7  217.54  5500.1  218.08
    5521  219.02  5558.3  219.24  5641.9  221.81  5683.8   222.5  5818.6  225.92
#Mann= 7 ,-1 , 0
  4580.3     .05       0  4988.5     .05       0  4992.5     .05       0
  5258.7     .07       0  5343.7     .05       0  5472.7     .07       0
  5558.3     .05       0
Bank Sta=4988.5,4992.5
XS Rating Curve= 0 ,0
Exp/Cntr=0.3,0.1

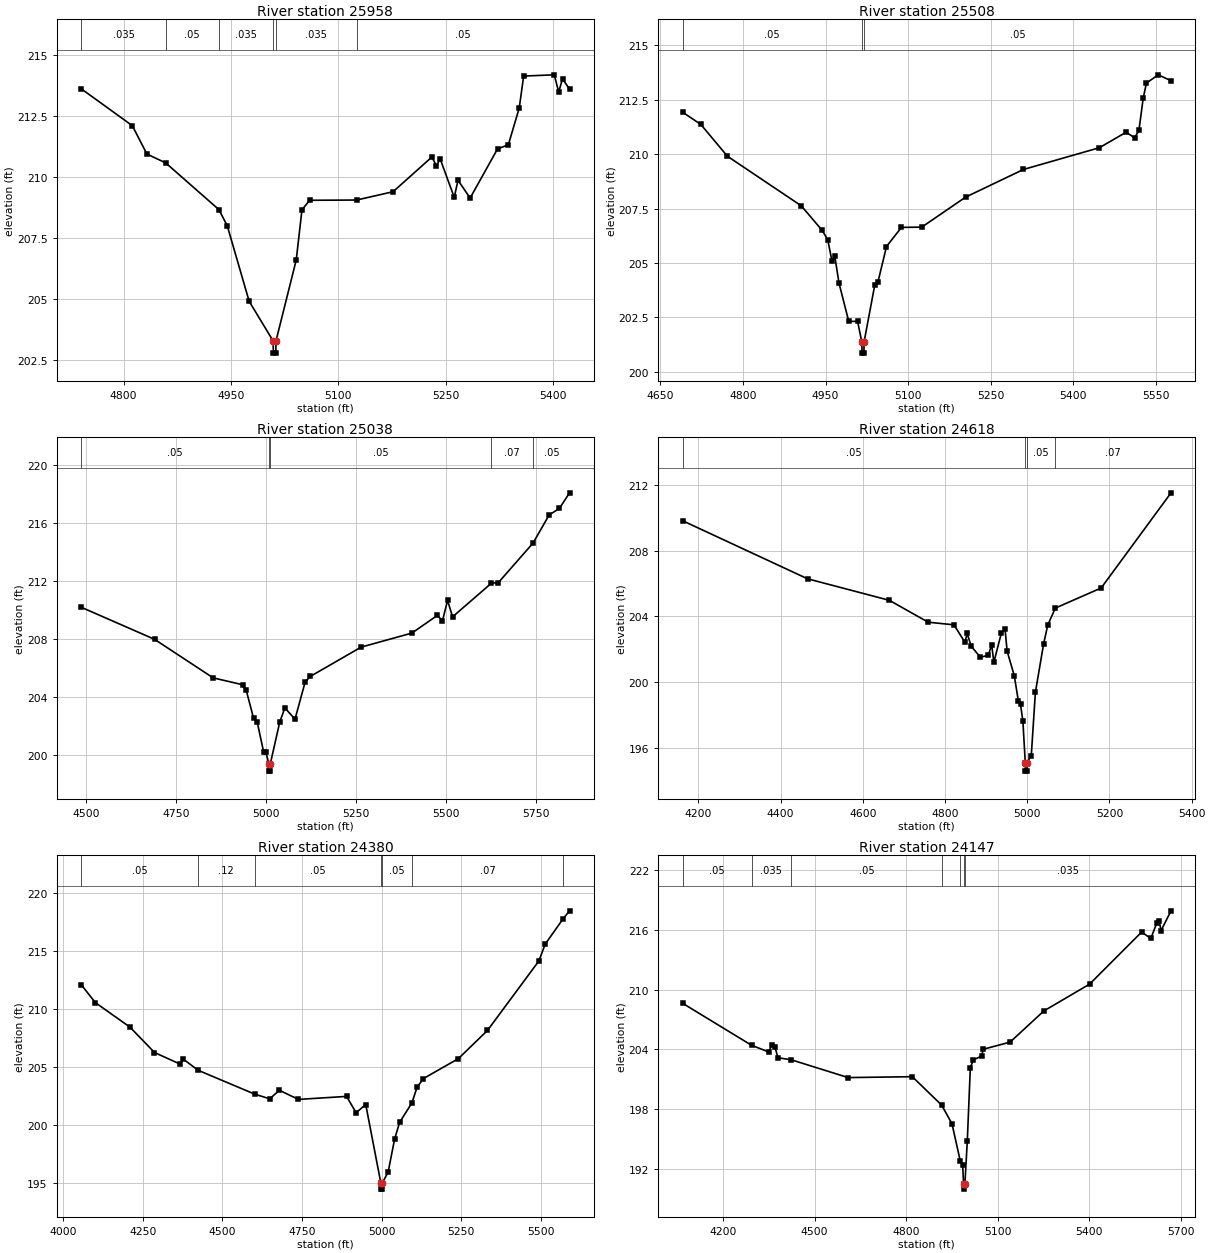
Type RM Length L Ch R = 1 ,25958   ,450,450,450
BEGIN DESCRIPTION:
MILBY CREEK 44.0
END DESCRIPTION:
XS GIS Cut Line= 3
      2500225.01     13485425.04        2500175.       13485175.
        2500025.     13484774.99
#Sta/Elev= 30
  4740.9   213.6  4812.3  212.09  4832.7  210.93  4858.9  210.57  4933.2  208.66
  4944.9     208  4975.5  204.91    5009  203.29  5009.3  202.79  5012.8  202.79
    5013  203.29  5041.3   206.6  5049.3  208.65    5060  209.04  5125.6  209.05
  5176.6  209.39  5230.8  210.81  5237.1  210.45  5242.4  210.73    5262  209.16
  5267.3  209.86  5284.2  209.13  5322.5  211.14  5337.6  211.31  5352.8  212.81
    5359  214.12  5401.7  214.17    5408  213.47  5413.3  214.01  5423.1  213.58
#Mann= 6 ,-1 , 0
  4740.9    .035       0  4858.9     .05       0  4933.2    .035       0
    5009    .035       0    5013    .035       0  5125.6     .05       0
Bank Sta=5009,5013
XS Rating Curve= 0 ,0
Exp/Cntr=0.3,0.1

Type RM Length L Ch R = 1 ,25508   ,470,470,470
BEGIN DESCRIPTION:
MILBY CREEK 43.0
END DESCRIPTION:
XS GIS Cut Line= 3
      2500524.99     13485325.05        2500575.       13485025.
      2500074.98     13484724.99
#Sta/Elev= 30
  4690.4  211.93  4723.4  211.37  4771.6  209.91  4905.9  207.63  4943.9   206.5
    4954  206.07  4961.6  205.09  4966.7  205.33  4974.3  204.09  4992.1  202.32
  5008.2  202.32  5015.9  201.36  5016.2  200.86  5019.7  200.86  5019.9  201.36
  5039.3  203.98  5045.1  204.12  5060.7  205.76  5087.9  206.64  5124.8  206.65
  5204.5  208.03  5309.5   209.3  5447.5   210.3    5496  211.01  5511.6  210.76
  5519.4   211.1  5527.1  212.57    5533  213.27  5554.4  213.65  5577.7  213.38
#Mann= 3 ,-1 , 0
  4690.4     .05       0  5015.9     .05       0  5019.9     .05       0
Bank Sta=5015.9,5019.9
XS Rating Curve= 0 ,0
Exp/Cntr=0.3,0.1

Type RM Length L Ch R = 1 ,25038   ,420,420,420
BEGIN DESCRIPTION:
MILBY CREEK 42.0
END DESCRIPTION:
XS GIS Cut Line= 3
        2500875.     13485324.98        2500975.       13484825.
      2500375.01     13484225.01
#Sta/Elev= 30
  4485.5  210.17  4689.4  207.96  4852.6   205.3  4934.2  204.83  4944.4  204.46
  4964.8  202.53    4975  202.26  4992.8  200.21  4998.9  200.21  5007.5  199.37
  5007.8  198.87  5011.3  198.87  5011.5  199.37  5037.8  202.26    5052  203.23
  5080.2  202.45  5108.5  205.02  5122.7   205.4  5264.1  207.42  5405.5  208.39
  5476.2  209.61  5490.4  209.23  5504.5  210.64  5518.6  209.51  5626.6  211.83
  5645.9  211.87  5742.5   214.6  5787.3  216.54  5815.6  216.98  5843.9  218.06
#Mann= 5 ,-1 , 0
  4485.5     .05       0  5007.5     .05       0  5011.5     .05       0
  5626.6     .07       0  5742.5     .05       0
Bank Sta=5007.5,5011.5
XS Rating Curve= 0 ,0
Exp/Cntr=0.3,0.1

Type RM Length L Ch R = 1 ,24618   ,238,238,238
BEGIN DESCRIPTION:
MILBY CREEK 41.0
END DESCRIPTION:
XS GIS Cut Line= 3
        2501025.       13485425.        2501275.       13484625.
        2501275.     13484275.05
#Sta/Elev= 30
  4161.7  209.81  4465.5  206.28  4664.6  204.97  4758.9  203.64  4821.7  203.48
  4848.5  202.41  4853.7  202.96  4863.6  202.18  4886.2   201.5  4905.6  201.64
  4913.4  202.28  4918.7   201.2    4937  202.98  4945.9  203.22  4951.1  201.87
  4968.4  200.39  4978.4  198.84  4983.6  198.64  4989.4  197.62  4995.2  195.08
  4995.5  194.58    4999  194.58  4999.2  195.08  5009.8  195.53  5019.8  199.37
  5039.8  202.32  5049.8  203.46  5068.4   204.5  5179.8  205.72  5349.8  211.51
#Mann= 4 ,-1 , 0
  4161.7     .05       0  4995.2     .05       0  4999.2     .05       0
  5068.4     .07       0
Bank Sta=4995.2,4999.2
XS Rating Curve= 0 ,0
Exp/Cntr=0.3,0.1

Type RM Length L Ch R = 1 ,24380   ,233,233,233
BEGIN DESCRIPTION:
Mapping XS 3d02e1e1
END DESCRIPTION:
XS GIS Cut Line= 3
      2501584.18     13485614.03      2501495.64     13484671.35
      2501433.25     13484089.01
#Sta/Elev= 30
  4057.1  212.12  4101.6  210.57  4210.3  208.45  4287.1  206.26  4367.5  205.26
  4377.5  205.69  4423.7  204.73  4601.1  202.67  4648.7  202.26  4678.9     203
  4738.8  202.21  4889.8  202.47  4919.9  201.06    4950  201.77  4997.6  194.96
  4997.8  194.46  5001.3  194.46  5001.6  194.96  5020.4  195.95  5040.5  198.77
  5056.2  200.22  5094.9  201.91  5110.9  203.25    5131  204.01  5240.6  205.73
  5332.1  208.17  5493.1  214.16  5513.2  215.62  5569.8  217.83  5589.6   218.5
#Mann= 7 ,-1 , 0
  4057.1     .05       0  4423.7     .12       0  4601.1     .05       0
  4997.6     .05       0  5001.6     .05       0  5094.9     .07       0
  5569.8     .05       0
Bank Sta=4997.6,5001.6
XS Rating Curve= 0 ,0
Exp/Cntr=0.3,0.1

Type RM Length L Ch R = 1 ,24147   ,478,478,478
BEGIN DESCRIPTION:
Mapping XS c208d2e3
END DESCRIPTION:
XS GIS Cut Line= 3
      2501750.85     13485556.81      2501714.39      13484640.1
      2501667.59     13483958.94
#Sta/Elev= 30
  4067.9  208.62  4293.6  204.41  4349.9  203.74  4359.9  204.44  4369.9  204.28
    4380  203.16  4423.2  202.96  4610.1  201.17  4820.3  201.26  4916.7   198.4
  4950.4  196.53  4977.1  192.85  4985.3   192.4  4988.3  190.48  4988.6  189.98
  4992.6  190.48  5000.5   194.8  5010.5  202.18  5020.5  202.95  5047.5  203.33
  5052.5  204.01  5140.8  204.73  5251.1  207.85  5401.4  210.55  5571.8  215.77
  5601.9  215.13  5621.9  216.71    5630  216.86    5635   215.9  5668.1   217.9
#Mann= 7 ,-1 , 0
  4067.9     .05       0  4293.6    .035       0  4423.2     .05       0
  4916.7      .1       0  4977.1    .035       0  4988.3    .035       0
  4992.6    .035       0
Bank Sta=4988.3,4992.6
XS Rating Curve= 0 ,0
Exp/Cntr=0.3,0.1

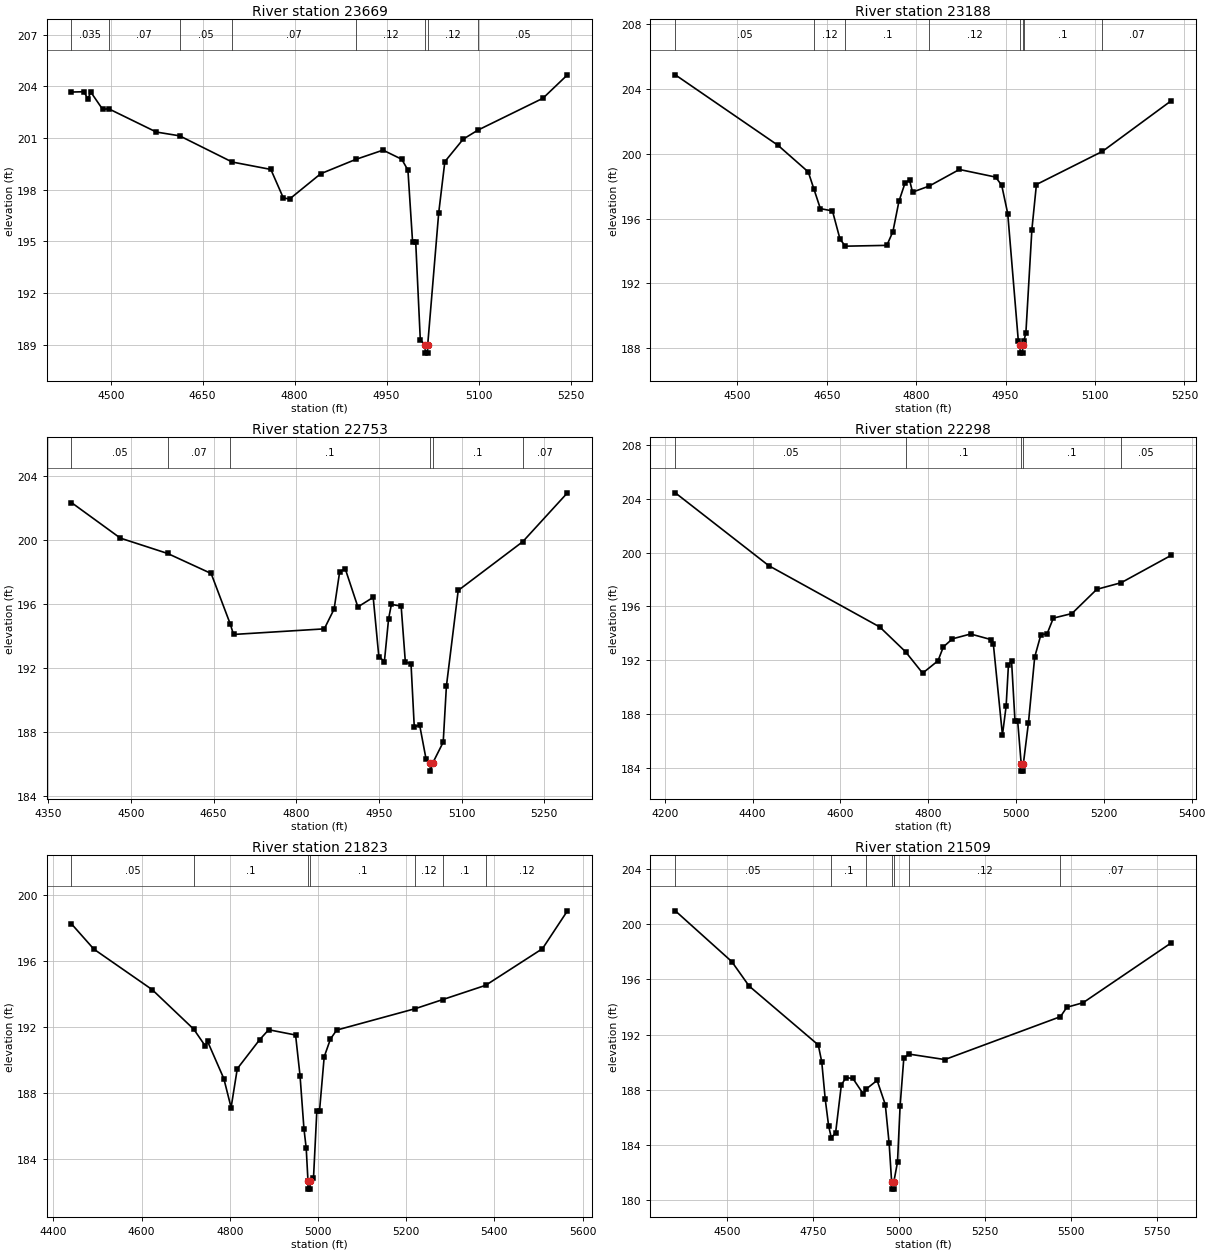
Type RM Length L Ch R = 1 ,23669   ,481,481,481
BEGIN DESCRIPTION:
MILBY CREEK 39.0
END DESCRIPTION:
XS GIS Cut Line= 3
      2502224.99     13485274.96        2502125.       13484725.
        2502125.     13484474.98
#Sta/Elev= 30
    4436  203.66  4456.3  203.68  4462.6  203.27  4467.7  203.65  4486.8  202.66
  4496.7  202.69  4574.4  201.34  4612.4  201.12  4698.1   199.6  4761.2  199.17
  4781.5  197.52  4791.7  197.45  4842.5  198.92  4899.6  199.75  4944.2  200.29
  4974.7  199.76  4984.8  199.13  4992.4  194.95  4997.5  194.95    5005  189.26
  5012.8  189.01  5013.1  188.51  5016.8  188.51  5017.1  189.01    5035  196.65
    5045  199.62    5075  200.93  5098.9  201.45    5205   203.3    5245  204.66
#Mann= 8 ,-1 , 0
    4436    .035       0  4496.7     .07       0  4612.4     .05       0
  4698.1     .07       0  4899.6     .12       0  5012.8     .05       0
  5017.1     .12       0  5098.9     .05       0
Bank Sta=5012.8,5017.1
XS Rating Curve= 0 ,0
Exp/Cntr=0.3,0.1

Type RM Length L Ch R = 1 ,23188   ,435,435,435
BEGIN DESCRIPTION:
MILBY CREEK 38.0
END DESCRIPTION:
XS GIS Cut Line= 3
        2502675.     13485225.01        2502575.       13484625.
        2502475.     13484424.99
#Sta/Elev= 30
    4396  204.88  4568.4  200.52    4619  198.88  4628.6  197.81  4639.3  196.61
  4659.6  196.47  4672.3  194.72  4681.3  194.29  4750.8  194.34    4761  195.19
  4771.1  197.06  4781.2  198.18  4788.9  198.38  4793.9  197.63  4822.1  198.01
  4872.5  199.03  4933.3  198.56  4943.5  198.05  4953.6   196.3  4971.3  188.45
  4974.2  188.18  4974.5  187.68  4978.4  187.68  4978.7  188.18  4980.4  188.41
    4984  188.91  4994.1  195.32  5001.7   198.1  5112.5  200.15  5227.9  203.28
#Mann= 8 ,-1 , 0
    4396     .05       0  4628.6     .12       0  4681.3      .1       0
  4822.1     .12       0  4974.2     .05       0  4978.7     .12       0
  4980.4      .1       0  5112.5     .07       0
Bank Sta=4974.2,4978.7
XS Rating Curve= 0 ,0
Exp/Cntr=0.3,0.1

Type RM Length L Ch R = 1 ,22753   ,455,455,455
BEGIN DESCRIPTION:
MILBY CREEK 37.0
END DESCRIPTION:
XS GIS Cut Line= 3
        2502875.     13485124.99        2502975.       13484525.
      2502825.01     13484275.01
#Sta/Elev= 30
  4392.2  202.34  4480.9  200.12  4566.7  199.16  4645.6  197.91  4680.2  194.76
  4686.2   194.1  4850.9  194.45  4868.7  195.69  4878.8  198.03    4889  198.19
  4911.8  195.82  4939.6  196.42  4949.8  192.72  4959.9  192.41  4967.5  195.07
  4972.6  195.98  4990.3  195.87  4997.9  192.38  5008.2  192.27  5014.1  188.32
  5023.8  188.45  5035.5  186.31  5042.9  186.06  5043.2  185.56  5047.5  186.06
  5066.6  187.37  5072.4  190.87  5093.8  196.85    5211   199.9    5292  202.95
#Mann= 6 ,-1 , 0
  4392.2     .05       0  4566.7     .07       0  4680.2      .1       0
  5042.9     .05       0  5047.5      .1       0    5211     .07       0
Bank Sta=5042.9,5047.5
XS Rating Curve= 0 ,0
Exp/Cntr=0.3,0.1

Type RM Length L Ch R = 1 ,22298   ,475,475,475
BEGIN DESCRIPTION:
MILBY CREEK 36.0
END DESCRIPTION:
XS GIS Cut Line= 3
      2503575.01     13485125.03        2503375.       13484375.
        2503125.       13484125.
#Sta/Elev= 30
  4223.8  204.44  4436.6  199.03  4689.6  194.47  4748.3  192.63  4787.2  191.04
  4822.2  191.96  4834.4  192.99  4855.1  193.59  4896.5  193.95  4942.5  193.54
  4948.3   193.2    4969  186.44  4977.4  188.59  4982.6  191.61  4989.7  191.98
  4997.5  187.52  5003.6  187.52  5011.8  184.26  5012.2  183.76  5016.2  183.76
  5016.5  184.26  5028.3  187.37  5042.5  192.24  5056.6   193.9  5070.8  193.97
  5084.9  195.13  5127.3  195.47  5183.9  197.27  5239.4  197.76  5353.6   199.8
#Mann= 5 ,-1 , 0
  4223.8     .05       0  4748.3      .1       0  5011.8     .05       0
  5016.5      .1       0  5239.4     .05       0
Bank Sta=5011.8,5016.5
XS Rating Curve= 0 ,0
Exp/Cntr=0.3,0.1

Type RM Length L Ch R = 1 ,21823   ,314,314,314
BEGIN DESCRIPTION:
MILBY CREEK 35.0
END DESCRIPTION:
XS GIS Cut Line= 3
      2503874.99     13484824.96        2503775.       13484275.
      2503374.97     13483874.97
#Sta/Elev= 30
  4441.1  198.23  4491.9   196.7    4624  194.25  4718.5  191.85  4744.7  190.83
  4749.8  191.11  4786.6  188.86  4803.1  187.11  4817.1  189.46  4867.9  191.22
  4888.3  191.82  4949.3   191.5  4959.4  189.04  4968.3  185.82  4973.4  184.65
  4977.4  182.67  4977.7  182.17  4981.7  182.17  4982.1  182.67  4989.9  182.82
  4997.5  186.91  5003.6  186.91  5014.2  190.18  5028.4  191.26  5042.5   191.8
  5221.1   193.1  5283.4  193.65  5380.3  194.51  5509.2  196.73  5565.8  199.02
#Mann= 7 ,-1 , 0
  4441.1     .05       0  4718.5      .1       0  4977.4     .05       0
  4982.1      .1       0  5221.1     .12       0  5283.4      .1       0
  5380.3     .12       0
Bank Sta=4977.4,4982.1
XS Rating Curve= 0 ,0
Exp/Cntr=0.3,0.1

Type RM Length L Ch R = 1 ,21509   ,303,303,303
BEGIN DESCRIPTION:
Mapping XS d2962bd8
END DESCRIPTION:
XS GIS Cut Line= 3
      2503980.02     13484968.23      2504037.31     13484416.14
      2504365.44      13483593.2
#Sta/Elev= 30
  4350.3  200.97  4514.4  197.29  4564.7  195.52  4765.7  191.25  4775.8  190.02
  4785.9  187.32  4795.9  185.36  4803.5  184.54    4816  184.87  4832.8  188.36
  4846.2  188.88  4866.3  188.82  4896.4   187.7  4905.8  188.07  4936.6  188.68
  4960.4  186.93  4971.6  184.11  4978.9   181.3  4979.4   180.8  4984.5   180.8
    4985   181.3  4995.9  182.76  5003.5  186.85  5014.2  190.29  5028.4  190.59
  5133.3  190.19  5469.3   193.3  5487.9  193.98    5535  194.31  5791.3  198.65
#Mann= 7 ,-1 , 0
  4350.3     .05       0  4803.5      .1       0  4905.8     .05       0
  4978.9     .05       0    4985     .05       0  5028.4     .12       0
  5469.3     .07       0
Bank Sta=4978.9,4985
XS Rating Curve= 0 ,0
Exp/Cntr=0.3,0.1

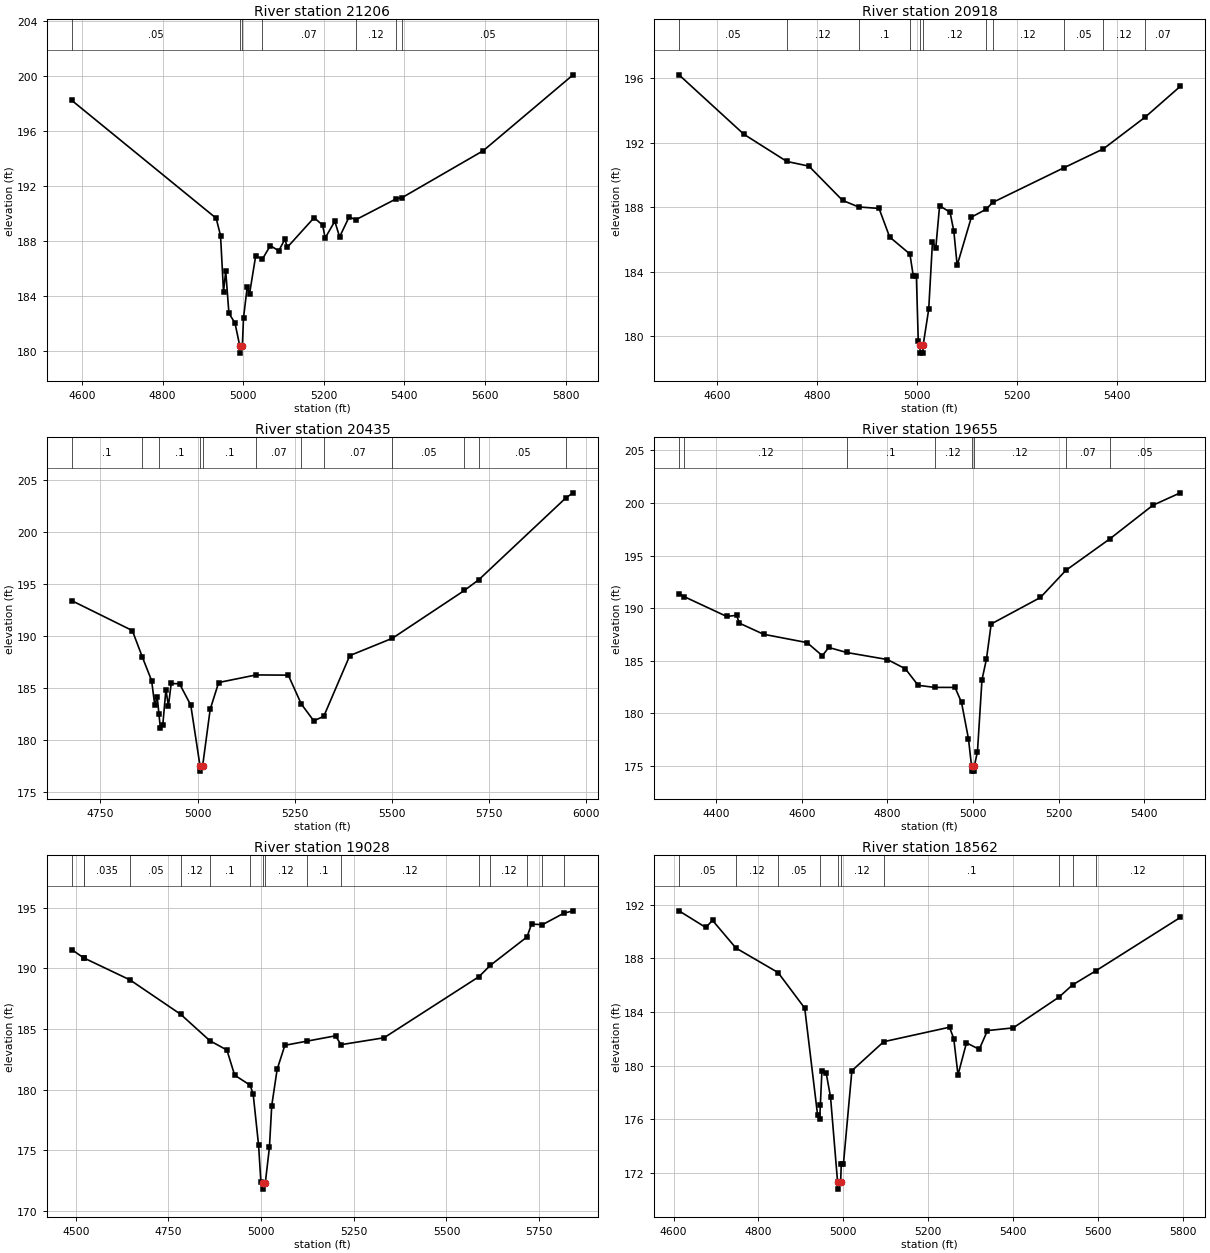
Type RM Length L Ch R = 1 ,21206   ,288,288,288
BEGIN DESCRIPTION:
Mapping XS 52a14524
END DESCRIPTION:
XS GIS Cut Line= 3
      2504105.02     13484916.14      2504256.06     13484551.56
      2504718.93     13483839.04
#Sta/Elev= 30
  4574.3  198.24  4932.7  189.65  4943.6  188.39    4951  184.29  4956.5   185.8
  4964.4  182.72  4979.4  182.02  4991.5  180.32    4992  179.82  4997.7  180.32
  5000.6  182.39  5009.7  184.61  5015.7  184.16  5030.8   186.9  5047.7  186.68
  5067.1  187.65  5088.2  187.28  5103.3  188.12  5109.3  187.53  5175.8  189.69
  5196.9  189.15  5203.3  188.21  5227.2  189.43  5239.1  188.29    5263  189.76
  5278.7  189.53  5379.3  191.06  5394.1  191.15  5595.6  194.57  5818.6   200.1
#Mann= 7 ,-1 , 0
  4574.3     .05       0  4991.5     .05       0  4997.7     .05       0
  5047.7     .07       0  5278.7     .12       0  5379.3     .07       0
  5394.1     .05       0
Bank Sta=4991.5,4997.7
XS Rating Curve= 0 ,0
Exp/Cntr=0.3,0.1

Type RM Length L Ch R = 1 ,20918   ,483,483,483
BEGIN DESCRIPTION:
MILBY CREEK 33.0
END DESCRIPTION:
XS GIS Cut Line= 3
      2504275.02     13484924.96        2504525.       13484525.
      2504875.02     13484124.97
#Sta/Elev= 30
  4523.9   196.2  4653.6  192.52  4739.7  190.83  4783.9  190.54  4851.1  188.42
  4883.3  188.01  4924.2  187.92  4945.4  186.15    4986  185.09  4992.6  183.75
  4998.9  183.75  5002.7  179.68  5006.1  179.45  5006.6  178.95    5012  178.95
  5012.5  179.45  5023.6  181.67  5031.1  185.83  5037.8  185.48  5045.4  188.09
  5066.3  187.68  5073.9   186.5  5080.5  184.39    5109  187.38  5138.1  187.86
  5151.6  188.29  5294.2  190.44    5373  191.61  5456.8  193.58  5527.1  195.49
#Mann= 11 ,-1 , 0
  4523.9     .05       0  4739.7     .12       0  4883.3      .1       0
    4986     .12       0  5006.1     .05       0  5012.5     .12       0
  5138.1     .05       0  5151.6     .12       0  5294.2     .05       0
    5373     .12       0  5456.8     .07       0
Bank Sta=5006.1,5012.5
XS Rating Curve= 0 ,0
Exp/Cntr=0.3,0.1

Type RM Length L Ch R = 1 ,20435   ,780,780,780
BEGIN DESCRIPTION:
MILBY CREEK 32.0
END DESCRIPTION:
XS GIS Cut Line= 3
      2504525.03     13485024.98        2504775.       13484825.
      2505324.98     13484025.03
#Sta/Elev= 30
    4676  193.39    4832  190.51  4857.6  187.98  4881.7  185.69  4889.7  183.35
  4896.1  184.12  4900.4  182.52  4904.1  181.15  4910.5  181.45  4918.5  184.83
  4924.9  183.24  4932.1  185.42  4953.7  185.38  4982.5  183.33  5006.3  177.48
  5006.8  176.98    5013  177.48  5032.5  182.93  5054.3  185.51  5150.6  186.24
  5233.6  186.22  5266.9  183.45  5299.2  181.82    5325  182.26  5391.9   188.1
  5501.6  189.77  5686.9  194.37  5724.3  195.41  5948.5  203.29  5966.9  203.77
#Mann= 12 ,-1 , 0
    4676      .1       0  4857.6     .12       0  4900.4      .1       0
  5006.3     .05       0    5013      .1       0  5150.6     .07       0
  5266.9     .12       0    5325     .07       0  5501.6     .05       0
  5686.9     .07       0  5724.3     .05       0  5948.5     .12       0
Bank Sta=5006.3,5013
XS Rating Curve= 0 ,0
Exp/Cntr=0.3,0.1

Type RM Length L Ch R = 1 ,19655   ,627,627,627
BEGIN DESCRIPTION:
Mapping XS 8bcc8bfc
END DESCRIPTION:
XS GIS Cut Line= 3
      2504999.62     13485205.72      2505320.81      13484741.3
      2505507.46     13484163.99
#Sta/Elev= 30
  4312.9  191.37    4325  191.09  4424.2  189.21  4447.5  189.31  4453.9  188.57
  4510.7  187.51  4612.1  186.72  4647.9  185.47  4662.7  186.26  4704.6  185.78
  4799.9  185.11  4841.8  184.23  4871.6  182.66  4910.3  182.46  4957.8  182.46
    4973  181.04  4989.3  177.56  4996.4     175  4996.9   174.5  5002.6   174.5
  5003.1     175  5010.3  176.36  5020.8  183.18  5031.3  185.16  5042.3  188.49
  5157.4  191.01  5216.6  193.58  5319.8  196.59  5420.2  199.78  5484.3  200.96
#Mann= 8 ,-1 , 0
  4312.9     .07       0    4325     .12       0  4704.6      .1       0
  4910.3     .12       0  4996.4     .05       0  5003.1     .12       0
  5216.6     .07       0  5319.8     .05       0
Bank Sta=4996.4,5003.1
XS Rating Curve= 0 ,0
Exp/Cntr=0.3,0.1

Type RM Length L Ch R = 1 ,19028   ,466,466,466
BEGIN DESCRIPTION:
Mapping XS c44d84d7
END DESCRIPTION:
XS GIS Cut Line= 3
      2505307.81     13485322.88       2505772.2     13484975.67
       2505863.2     13484208.68
#Sta/Elev= 30
  4489.3  191.54  4521.2  190.86  4521.4  190.86  4646.6  189.04  4783.2  186.21
  4861.7  184.04  4907.8  183.27  4928.7   181.2  4970.3  180.38  4978.7  179.63
  4993.3  175.42  4999.5  172.38  5004.4  172.32  5004.9  171.82  5011.3  172.32
  5022.5  175.26  5028.7  178.69  5043.3  181.68  5064.1  183.66  5123.4     184
  5200.7  184.44  5215.5  183.71  5331.6  184.28  5587.6  189.31  5618.2  190.24
  5717.2  192.58  5729.4  193.64  5758.9  193.59  5816.2  194.53  5841.5  194.73
#Mann= 16 ,-1 , 0
  4489.3    .035       0  4521.2     .05       0  4521.4    .035       0
  4646.6     .05       0  4783.2     .12       0  4861.7      .1       0
  4970.3     .12       0  5004.4     .05       0  5011.3     .12       0
  5123.4      .1       0  5215.5     .12       0  5587.6      .1       0
  5618.2     .12       0  5717.2     .05       0  5758.9     .12       0
  5816.2     .05       0
Bank Sta=5004.4,5011.3
XS Rating Curve= 0 ,0
Exp/Cntr=0.3,0.1

Type RM Length L Ch R = 1 ,18562   ,446,446,446
BEGIN DESCRIPTION:
Mapping XS ec44191a
END DESCRIPTION:
XS GIS Cut Line= 3
      2506067.34     13485457.42       2506128.1     13485079.84
      2506132.45     13484281.19
#Sta/Elev= 30
  4612.8  191.54    4676   190.3  4691.8  190.83  4746.9  188.77  4846.3  186.94
    4909  184.29  4939.3  176.33  4944.3  176.03  4945.8  177.06  4949.5  179.59
  4959.6  179.45  4969.8  177.67  4986.5  171.31    4987  170.81  4993.5  171.31
  4995.2  172.69  5000.2  172.69  5020.1  179.63    5095  181.79  5250.1  182.87
  5260.1  182.02  5270.1  179.32  5290.1  181.71  5320.1  181.22  5339.5  182.62
  5400.1  182.82  5507.9  185.11  5539.9  186.02  5595.8  187.09  5793.9  191.05
#Mann= 10 ,-1 , 0
  4612.8     .05       0  4746.9     .12       0  4846.3     .05       0
  4945.8     .12       0  4986.5     .05       0  4993.5     .12       0
    5095      .1       0  5507.9     .12       0  5539.9      .1       0
  5595.8     .12       0
Bank Sta=4986.5,4993.5
XS Rating Curve= 0 ,0
Exp/Cntr=0.3,0.1

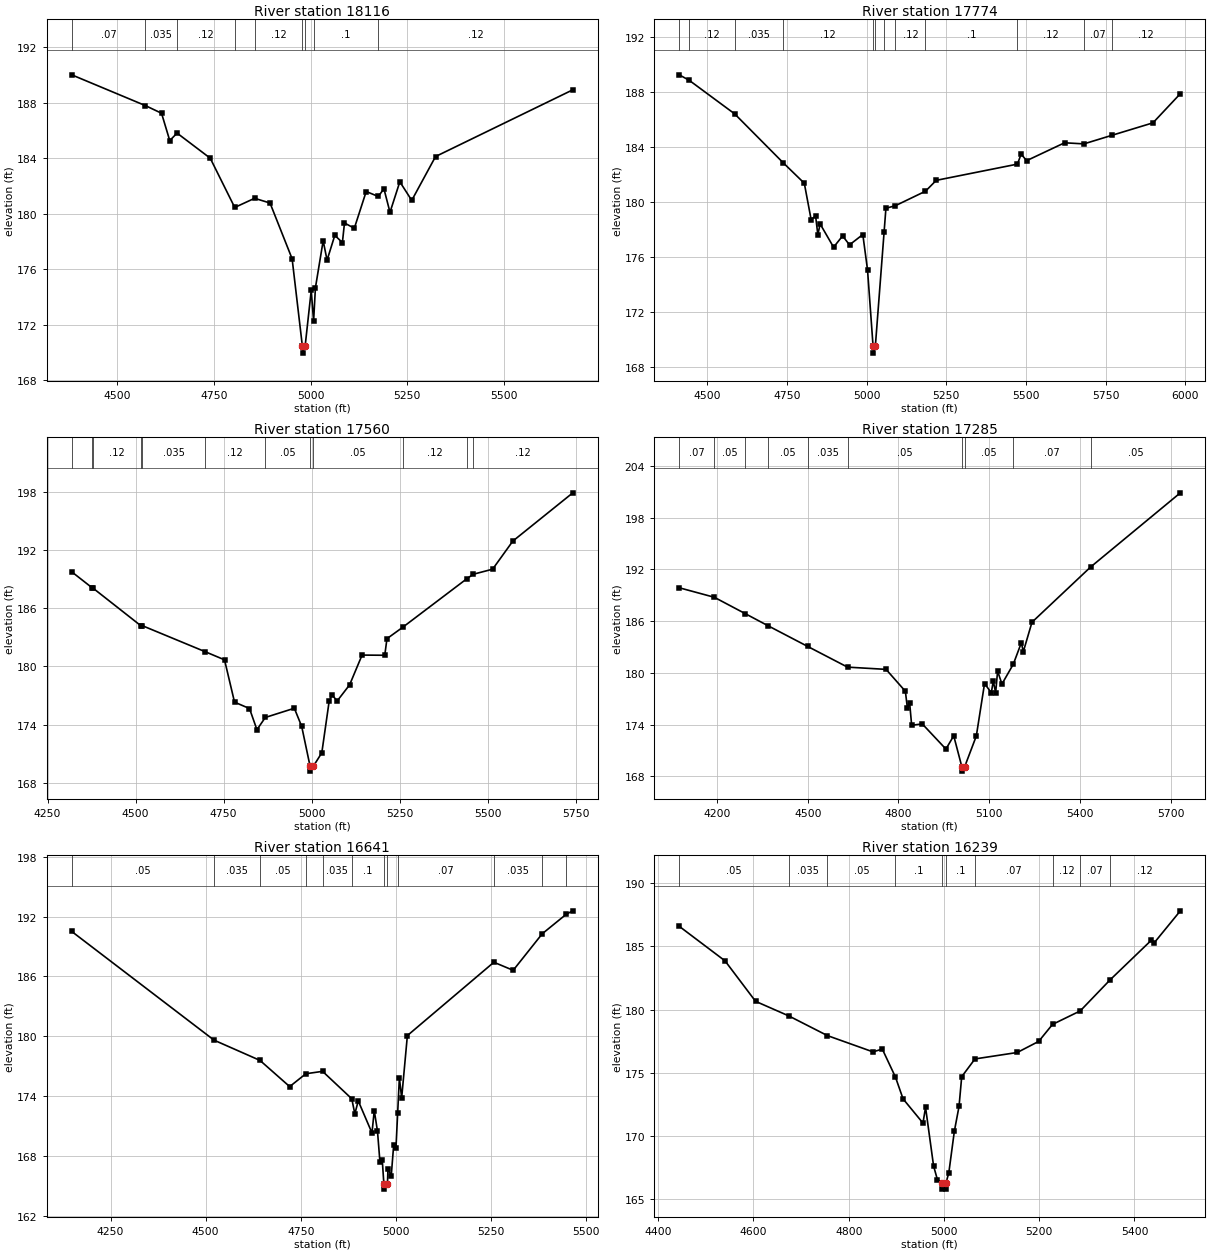
Type RM Length L Ch R = 1 ,18116   ,342,342,342
BEGIN DESCRIPTION:
Mapping XS 31ebd31e
END DESCRIPTION:
XS GIS Cut Line= 4
      2506349.47     13485513.82      2506527.41     13485010.39
      2506514.39     13484854.14       2506310.4     13484285.57
#Sta/Elev= 30
  4382.7  190.02  4573.2   187.8  4614.8  187.25    4636  185.28  4654.9  185.82
  4740.6  184.01  4803.9  180.46  4855.2  181.12  4895.1  180.78  4952.2  176.76
  4978.7  170.46  4979.2  169.96  4985.8  170.46  5001.6  174.48  5007.7  172.26
  5012.4  174.67  5032.4  178.06  5042.5  176.66  5062.5  178.45  5082.1  177.93
  5087.5  179.34  5112.9  178.96  5143.6  181.61  5174.9  181.25  5189.4  181.81
  5205.1  180.11  5230.5  182.31  5261.3  180.97  5322.8  184.13  5677.5  188.94
#Mann= 9 ,-1 , 0
  4382.7     .07       0  4573.2    .035       0  4654.9     .12       0
  4803.9      .1       0  4855.2     .12       0  4978.7     .05       0
  4985.8     .12       0  5007.7      .1       0  5174.9     .12       0
Bank Sta=4978.7,4985.8
XS Rating Curve= 0 ,0
Exp/Cntr=0.3,0.1

Type RM Length L Ch R = 1 ,17774   ,214,214,214
BEGIN DESCRIPTION:
Mapping XS a0853028
END DESCRIPTION:
XS GIS Cut Line= 4
      2506388.86     13485553.91      2506756.06     13485172.21
      2506845.03     13485046.34      2506463.07     13484243.34
#Sta/Elev= 30
  4411.9  189.27  4443.2  188.87  4585.9  186.43  4737.6  182.89  4804.4  181.39
  4825.8  178.75  4839.9  179.01  4846.9  177.64  4854.1  178.43  4896.3  176.74
  4924.6  177.56  4946.3  176.91  4988.1  177.66  5002.9  175.09  5020.3  169.54
  5020.8  169.04  5027.4  169.54  5054.9  177.84  5060.6  179.57  5090.6  179.76
  5184.8  180.81  5218.6   181.6  5473.5  182.78  5485.1  183.51  5502.3  183.03
  5621.4  184.33  5682.1  184.25    5771  184.88  5898.9  185.78  5984.9   187.9
#Mann= 12 ,-1 , 0
  4411.9     .07       0  4443.2     .12       0  4585.9    .035       0
  4737.6     .12       0  5020.3     .05       0  5027.4     .12       0
  5054.9     .05       0  5090.6     .12       0  5184.8      .1       0
  5473.5     .12       0  5682.1     .07       0    5771     .12       0
Bank Sta=5020.3,5027.4
XS Rating Curve= 0 ,0
Exp/Cntr=0.3,0.1

Type RM Length L Ch R = 1 ,17560   ,275,275,275
BEGIN DESCRIPTION:
Mapping XS 5e1974c6
END DESCRIPTION:
XS GIS Cut Line= 3
      2506457.94     13485670.14      2506970.12     13485214.39
      2507556.06     13484767.34
#Sta/Elev= 30
  4318.7  189.75  4376.4  188.11  4380.1  188.04  4515.1  184.19  4519.1   184.2
  4696.7  181.53  4752.5  180.68  4780.9  176.32  4823.4  175.66  4844.5  173.48
  4868.3  174.74  4950.7  175.69  4971.6  173.82  4995.4  169.71  4995.9  169.21
  5004.6  169.71  5028.7   171.1  5049.5   176.4  5057.7  177.07  5072.3  176.44
  5107.6   178.1    5143  181.17  5207.4  181.15  5213.7  182.86    5259  184.05
  5441.3  189.06  5458.8   189.5  5513.6  190.02  5571.1  192.92  5741.3  197.89
#Mann= 12 ,-1 , 0
  4318.7     .05       0  4376.4     .07       0  4380.1     .12       0
  4515.1     .07       0  4519.1    .035       0  4696.7     .12       0
  4868.3     .05       0  4995.4     .05       0  5004.6     .05       0
    5259     .12       0  5441.3     .07       0  5458.8     .12       0
Bank Sta=4995.4,5004.6
XS Rating Curve= 0 ,0
Exp/Cntr=0.3,0.1

Type RM Length L Ch R = 1 ,17285   ,644,644,644
BEGIN DESCRIPTION:
Mapping XS 4c9a7a91
END DESCRIPTION:
XS GIS Cut Line= 3
      2506471.69     13485973.76      2507166.16     13485390.41
      2507748.34     13484919.12
#Sta/Elev= 30
  4075.5  189.87  4191.1  188.77  4293.4  186.87  4368.5  185.47    4500  183.06
  4631.5  180.66  4758.9   180.4  4822.7  177.86  4829.2  175.97    4837  176.45
  4843.5  173.91  4878.6  174.07  4956.7  171.15  4982.5  172.69  5009.4  169.09
  5009.9  168.59  5018.6  169.09  5057.2  172.67  5084.4  178.76  5106.7  177.68
  5113.2  179.04  5121.1  177.69  5127.5   180.2  5141.9   178.7  5179.4     181
  5205.9  183.48  5212.6  182.46  5241.1  185.87  5434.6  192.27  5731.5  200.89
#Mann= 10 ,-1 , 0
  4075.5     .07       0  4191.1     .05       0  4293.4     .12       0
  4368.5     .05       0    4500    .035       0  4631.5     .05       0
  5009.4     .05       0  5018.6     .05       0  5179.4     .07       0
  5434.6     .05       0
Bank Sta=5009.4,5018.6
XS Rating Curve= 0 ,0
Exp/Cntr=0.3,0.1

Type RM Length L Ch R = 1 ,16641   ,402,402,402
BEGIN DESCRIPTION:
Mapping XS 7567f7aa
END DESCRIPTION:
XS GIS Cut Line= 3
      2506867.52     13486320.99      2507603.66     13485827.91
      2507943.92     13485564.04
#Sta/Elev= 30
  4148.1  190.51  4522.1   179.6  4642.7  177.57  4720.8  174.94  4763.3  176.23
  4807.2  176.47  4883.9  173.72    4892   172.2  4900.9  173.51    4937  170.29
    4943  172.53  4951.5  170.46    4958  167.34    4964  167.59  4968.3  165.15
  4968.8  164.65  4977.7  165.15    4979  166.71  4987.6  165.98    4994  169.06
    5000  168.74  5004.5  172.29    5009  175.83    5015   173.8    5030  180.06
  5257.3  187.42    5308  186.61  5384.4  190.28  5447.9  192.25  5464.7  192.58
#Mann= 12 ,-1 , 0
  4148.1     .05       0  4522.1    .035       0  4642.7     .05       0
  4763.3      .1       0  4807.2    .035       0  4883.9      .1       0
  4968.3     .05       0  4977.7      .1       0  5004.5     .07       0
  5257.3    .035       0  5384.4     .07       0  5447.9    .035       0
Bank Sta=4968.3,4977.7
XS Rating Curve= 0 ,0
Exp/Cntr=0.3,0.1

Type RM Length L Ch R = 1 ,16239   ,309,309,309
BEGIN DESCRIPTION:
Mapping XS 7341976f
END DESCRIPTION:
XS GIS Cut Line= 3
      2507055.03     13486411.25       2507610.6     13486202.91
      2507991.24     13485946.85
#Sta/Elev= 30
  4444.2   186.6  4540.3  183.86  4604.4  180.65  4674.3  179.49  4755.3  177.93
  4850.9  176.64  4870.5  176.86  4898.1  174.64  4914.1  172.91  4955.9  170.99
  4961.3  172.24  4978.2  167.58  4986.2   166.5  4994.8  166.25  4995.3  165.75
  5003.8  165.75  5004.3  166.25  5010.2  167.06  5021.8  170.35  5031.6  172.31
  5037.2  174.67  5065.1  176.08  5153.8  176.59  5198.8  177.47  5227.9  178.82
  5286.1  179.89  5348.7  182.35  5435.7  185.51  5441.8  185.31  5496.3  187.83
#Mann= 10 ,-1 , 0
  4444.2     .05       0  4674.3    .035       0  4755.3     .05       0
  4898.1      .1       0  4994.8     .05       0  5004.3      .1       0
  5065.1     .07       0  5227.9     .12       0  5286.1     .07       0
  5348.7     .12       0
Bank Sta=4994.8,5004.3
XS Rating Curve= 0 ,0
Exp/Cntr=0.3,0.1