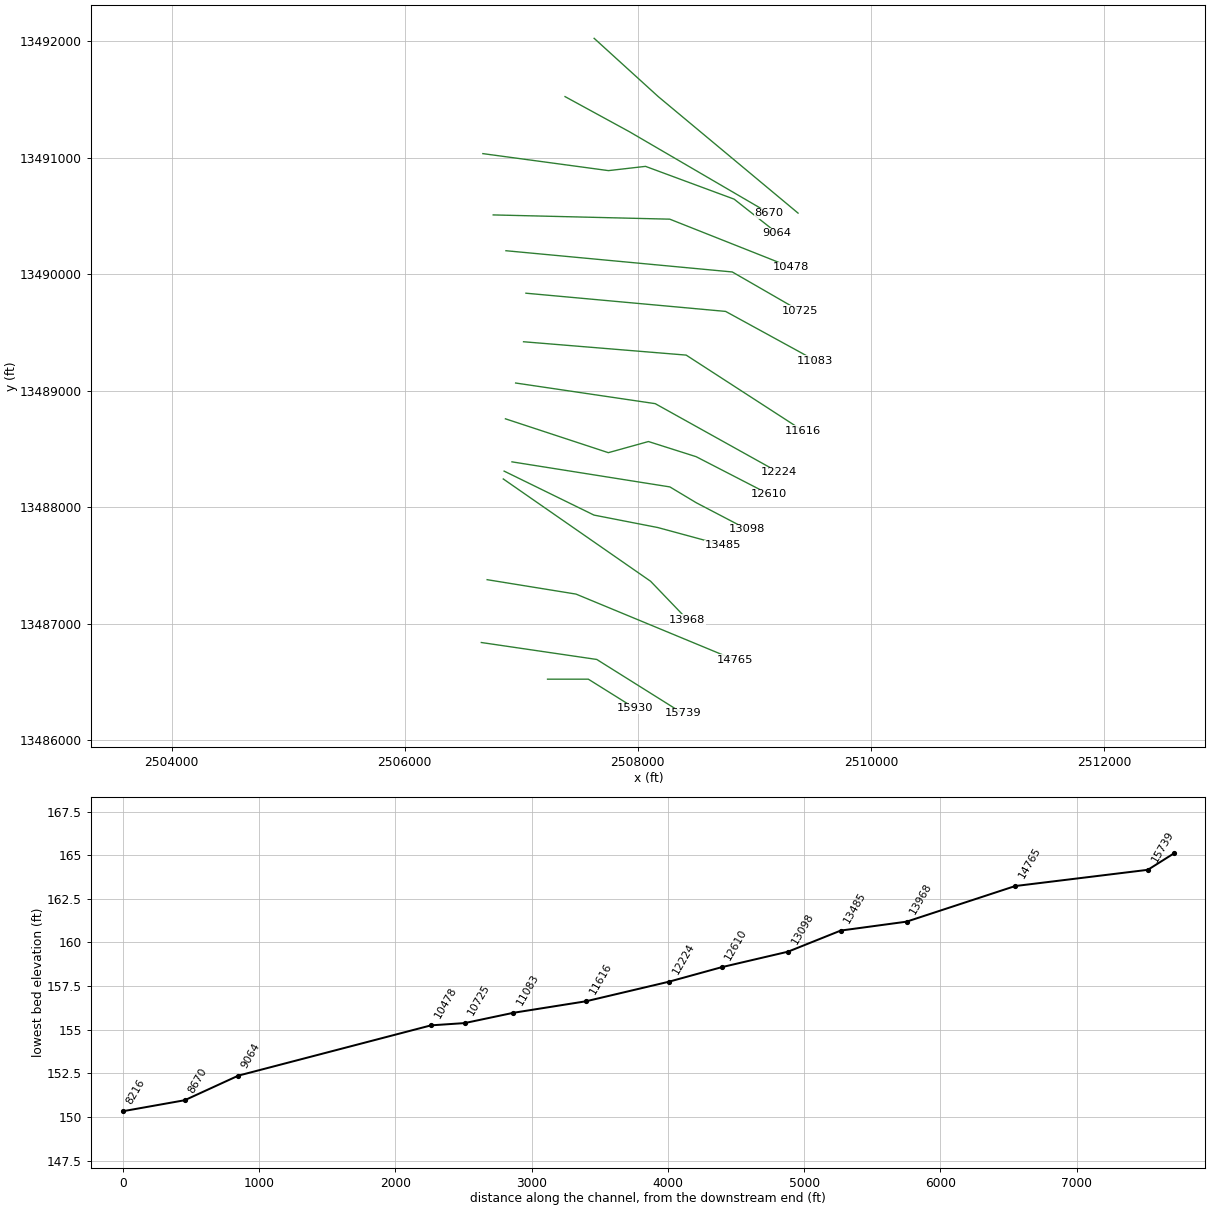
HEC-RAS study MILBY CREEK.prj: MILBY CREEK Base Level Engineering

--- MILBY CREEK.g01 (geometry) --- (continued)

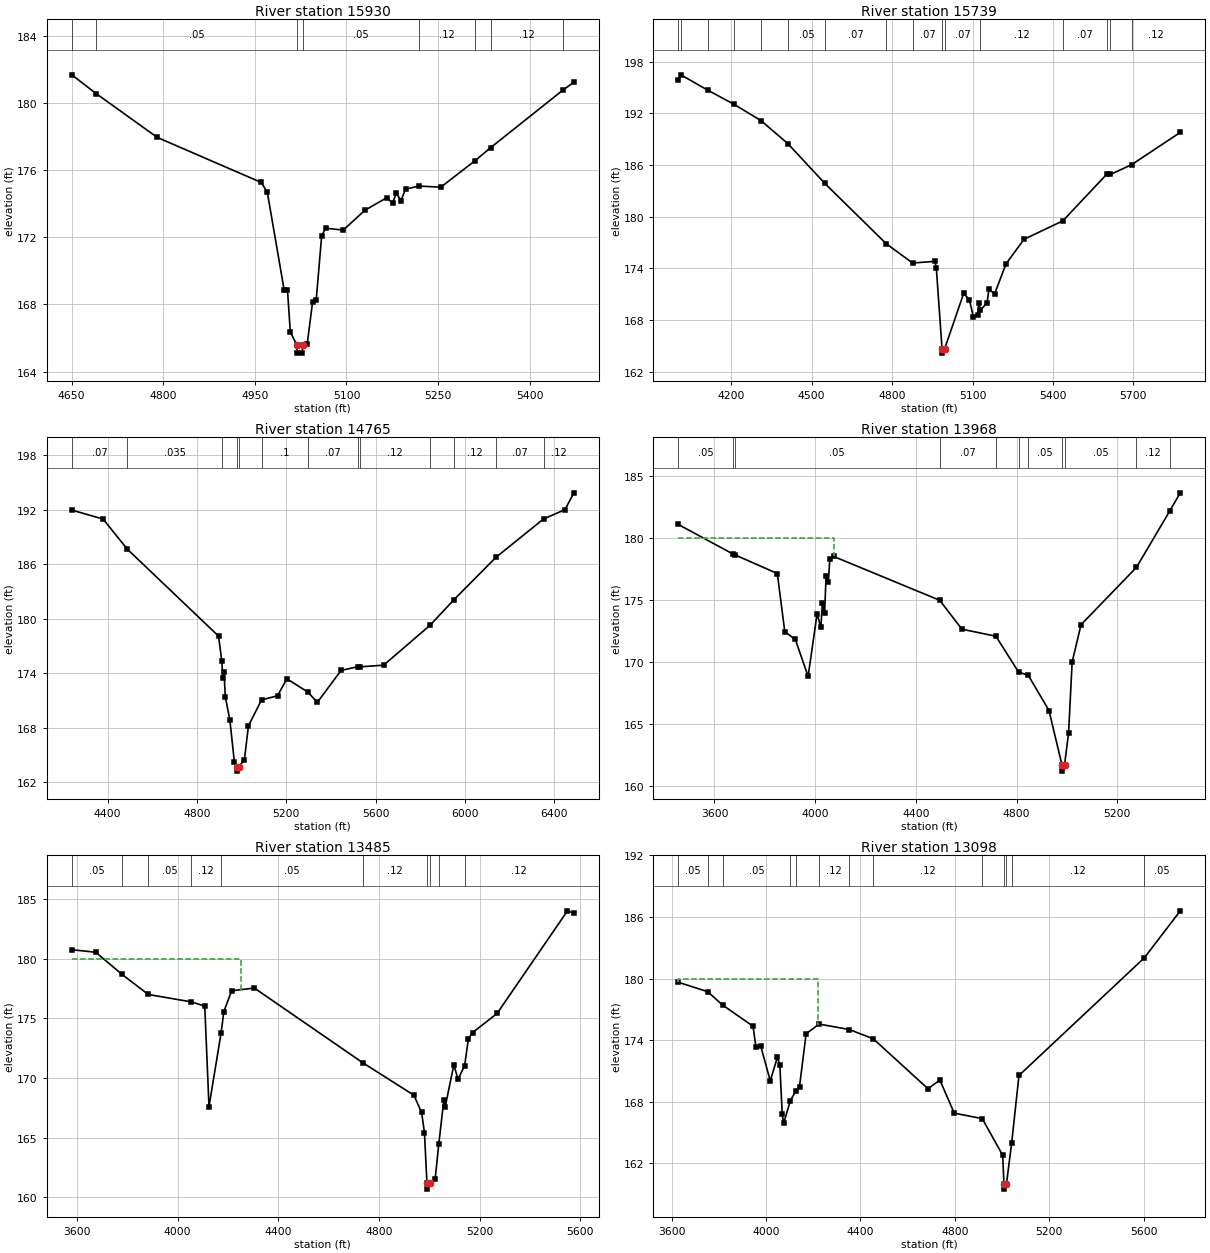
Type RM Length L Ch R = 1 ,15930   ,191,191,191
BEGIN DESCRIPTION:
MILBY CREEK 22.0
END DESCRIPTION:
XS GIS Cut Line= 3
        2507225.       13486525.        2507575.       13486525.
        2507975.       13486275.
#Sta/Elev= 30
  4650.4  181.68  4690.4  180.56  4790.4  177.95  4960.4  175.27  4970.4  174.69
  4997.9  168.88  5003.4  168.88  5008.1  166.36  5018.6   165.6  5019.1   165.1
  5027.7   165.1  5028.2   165.6  5035.8  165.67  5044.6  168.17  5050.5  168.28
  5059.4   172.1  5065.9  172.54  5094.7  172.43  5130.1  173.61  5166.1  174.36
  5175.5  174.03  5181.4  174.64  5189.1  174.19  5196.7  174.87  5218.2  175.05
  5254.5  174.99  5310.6  176.57  5336.2  177.35  5454.2  180.77  5472.1  181.24
#Mann= 8 ,-1 , 0
  4650.4    .035       0  4690.4     .05       0  5018.6     .05       0
  5028.2     .05       0  5218.2     .12       0  5310.6     .07       0
  5336.2     .12       0  5454.2     .07       0
Bank Sta=5018.6,5028.2
XS Rating Curve= 0 ,0
Exp/Cntr=0.3,0.1

Type RM Length L Ch R = 1 ,15739   ,974,974,974
BEGIN DESCRIPTION:
MILBY CREEK 21.0
END DESCRIPTION:
XS GIS Cut Line= 3
      2506656.81     13486839.57      2507647.44     13486694.22
      2508385.62     13486231.43
#Sta/Elev= 30
  4002.4   195.9    4012  196.46  4114.2  194.65  4211.5  193.02  4311.3  191.14
  4411.1  188.48  4549.3  183.85    4778  176.86  4876.5  174.62  4959.8  174.81
  4964.8  174.09  4986.3  164.66  4986.8  164.16  4995.9  164.66  5066.9  171.09
  5088.1  170.37  5103.4  168.33  5118.7  168.64  5124.6  169.94  5128.9  169.14
  5154.2  169.99  5161.1  171.58  5182.4  171.04    5225  174.53    5292  177.37
  5436.7  179.51  5601.4  184.95  5614.3   184.9  5693.2  186.03  5874.9  189.78
#Mann= 16 ,-1 , 0
  4002.4     .07       0    4012    .035       0  4114.2     .07       0
  4211.5    .035       0  4311.3     .07       0  4411.1     .05       0
  4549.3     .07       0    4778     .05       0  4876.5     .07       0
  4986.3     .05       0  4995.9     .07       0  5128.9     .12       0
  5436.7     .07       0  5601.4     .12       0  5614.3     .07       0
  5693.2     .12       0
Bank Sta=4986.3,4995.9
XS Rating Curve= 0 ,0
Exp/Cntr=0.3,0.1

Type RM Length L Ch R = 1 ,14765   ,797,797,797
BEGIN DESCRIPTION:
MILBY CREEK 20.0
END DESCRIPTION:
XS GIS Cut Line= 3
       2506706.6     13487378.84       2507469.3     13487255.23
      2508831.54     13486691.05
#Sta/Elev= 30
  4239.6  191.98  4379.8  190.99  4488.4  187.67  4896.5   178.1  4911.1  175.34
  4915.8  173.44  4920.9  174.15  4926.8   171.4  4947.1  168.87  4967.4  164.23
  4977.5  163.73    4978  163.23  4987.6  163.73  5012.3  164.49  5030.3  168.22
  5088.9  171.07  5160.6  171.53  5202.4   173.4  5296.5  171.93  5338.6   170.8
    5445  174.32  5519.5  174.73  5528.1  174.71  5635.4   174.9  5842.5  179.28
  5950.1  182.11  6138.2  186.78    6351     191  6447.2  192.03  6486.7  193.88
#Mann= 13 ,-1 , 0
  4239.6     .07       0  4488.4    .035       0  4911.1     .15       0
  4977.5     .05       0  4987.6     .15       0  5088.9      .1       0
  5296.5     .07       0  5519.5      .1       0  5528.1     .12       0
  5842.5     .07       0  5950.1     .12       0  6138.2     .07       0
    6351     .12       0
Bank Sta=4977.5,4987.6
XS Rating Curve= 0 ,0
Exp/Cntr=0.3,0.1

Type RM Length L Ch R = 1 ,13968   ,483,483,483
BEGIN DESCRIPTION:
Mapping XS c2e4e436
END DESCRIPTION:
XS GIS Cut Line= 3
      2506845.04     13488243.37      2508109.61     13487365.23
      2508424.72      13487037.1
#Sta/Elev= 30
  3456.2  181.09  3674.1   178.7  3679.9  178.65  3849.8  177.13  3879.5  172.44
  3921.4  171.81  3972.1  168.83  4007.8  173.88  4022.7  172.78  4028.8  174.72
  4037.6  173.96  4043.6  176.93  4052.4  176.44  4058.5  178.32  4073.3  178.51
    4495  174.97  4583.2  172.64  4718.2  172.07  4808.2  169.18  4846.7  168.92
    4929  166.08  4980.6  161.69  4981.1  161.19  4990.8  161.69  5006.9  164.28
    5021  169.99  5056.3     173  5276.6  177.63  5409.7  182.21  5450.7  183.64
#Mann= 11 ,-1 , 0
  3456.2     .05       0  3674.1     .12       0  3679.9     .05       0
    4495     .07       0  4718.2     .05       0  4808.2     .07       0
  4846.7     .05       0  4980.6     .05       0  4990.8     .05       0
  5276.6     .12       0  5409.7     .07       0
#XS Ineff= 2 , 0
       0  4073.3     180               0
Permanent Ineff=
       F       F
Bank Sta=4980.6,4990.8
XS Rating Curve= 0 ,0
Exp/Cntr=0.3,0.1

Type RM Length L Ch R = 1 ,13485   ,387,387,387
BEGIN DESCRIPTION:
Mapping XS 10b616a2
END DESCRIPTION:
XS GIS Cut Line= 4
      2506852.29     13488310.74       2507623.5     13487933.27
      2508172.11     13487826.17      2508729.41     13487675.13
#Sta/Elev= 30
  3579.5  180.74  3674.7  180.53  3779.3  178.67  3883.6  176.99  4054.6  176.37
  4107.9  176.02  4124.8  167.59  4172.8  173.77  4183.7  175.55  4214.8   177.3
  4304.9  177.53  4735.1  171.28  4938.9  168.55  4969.5  167.11  4980.9  165.42
  4990.8  161.18  4991.3  160.68  5001.3  161.18  5023.3   161.5    5038  164.49
    5058  168.17  5063.2  167.56  5097.8  171.11  5114.1  169.88  5140.6  171.03
  5155.5  173.28  5172.3   173.8  5269.5   175.4  5549.2     184  5574.5  183.79
#Mann= 10 ,-1 , 0
  3579.5     .05       0  3779.3     .12       0  3883.6     .05       0
  4054.6     .12       0  4172.8     .05       0  4735.1     .12       0
  4990.8     .05       0  5001.3     .07       0    5038      .1       0
  5140.6     .12       0
#XS Ineff= 2 , 0
       0  4250.5     180               0
Permanent Ineff=
       F       F
Bank Sta=4990.8,5001.3
XS Rating Curve= 0 ,0
Exp/Cntr=0.3,0.1

Type RM Length L Ch R = 1 ,13098   ,488,488,488
BEGIN DESCRIPTION:
MILBY CREEK 17.0
END DESCRIPTION:
XS GIS Cut Line= 4
       2506919.7     13488390.17        2508275.       13488175.
      2508501.79     13488038.93      2508937.34     13487811.53
#Sta/Elev= 30
  3627.7  179.64  3752.2  178.72  3815.4  177.42  3944.8  175.35  3957.1  173.29
  3977.3  173.43  4017.8  170.02  4048.2  172.34  4058.3  171.57  4068.5   166.8
  4074.4  165.88  4102.8  168.07  4125.3  169.02  4141.7  169.46  4169.7  174.62
  4225.3  175.56  4352.1  175.03  4454.1  174.13  4686.1  169.26  4736.7   170.1
  4797.5  166.88  4916.4  166.34  5002.9  162.77  5008.3  159.97  5008.8  159.47
  5018.8  159.97    5041  163.97  5071.9  170.55    5603  182.01  5755.8   186.6
#Mann= 13 ,-1 , 0
  3627.7     .05       0  3752.2     .12       0  3815.4     .05       0
  4102.8     .12       0  4125.3     .05       0  4225.3     .12       0
  4352.1    .035       0  4454.1     .12       0  4916.4     .15       0
  5008.3     .05       0  5018.8     .15       0    5041     .12       0
    5603     .05       0
#XS Ineff= 2 , 0
       0  4220.3     180               0
Permanent Ineff=
       F       F
Bank Sta=5008.3,5018.8
XS Rating Curve= 0 ,0
Exp/Cntr=0.3,0.1

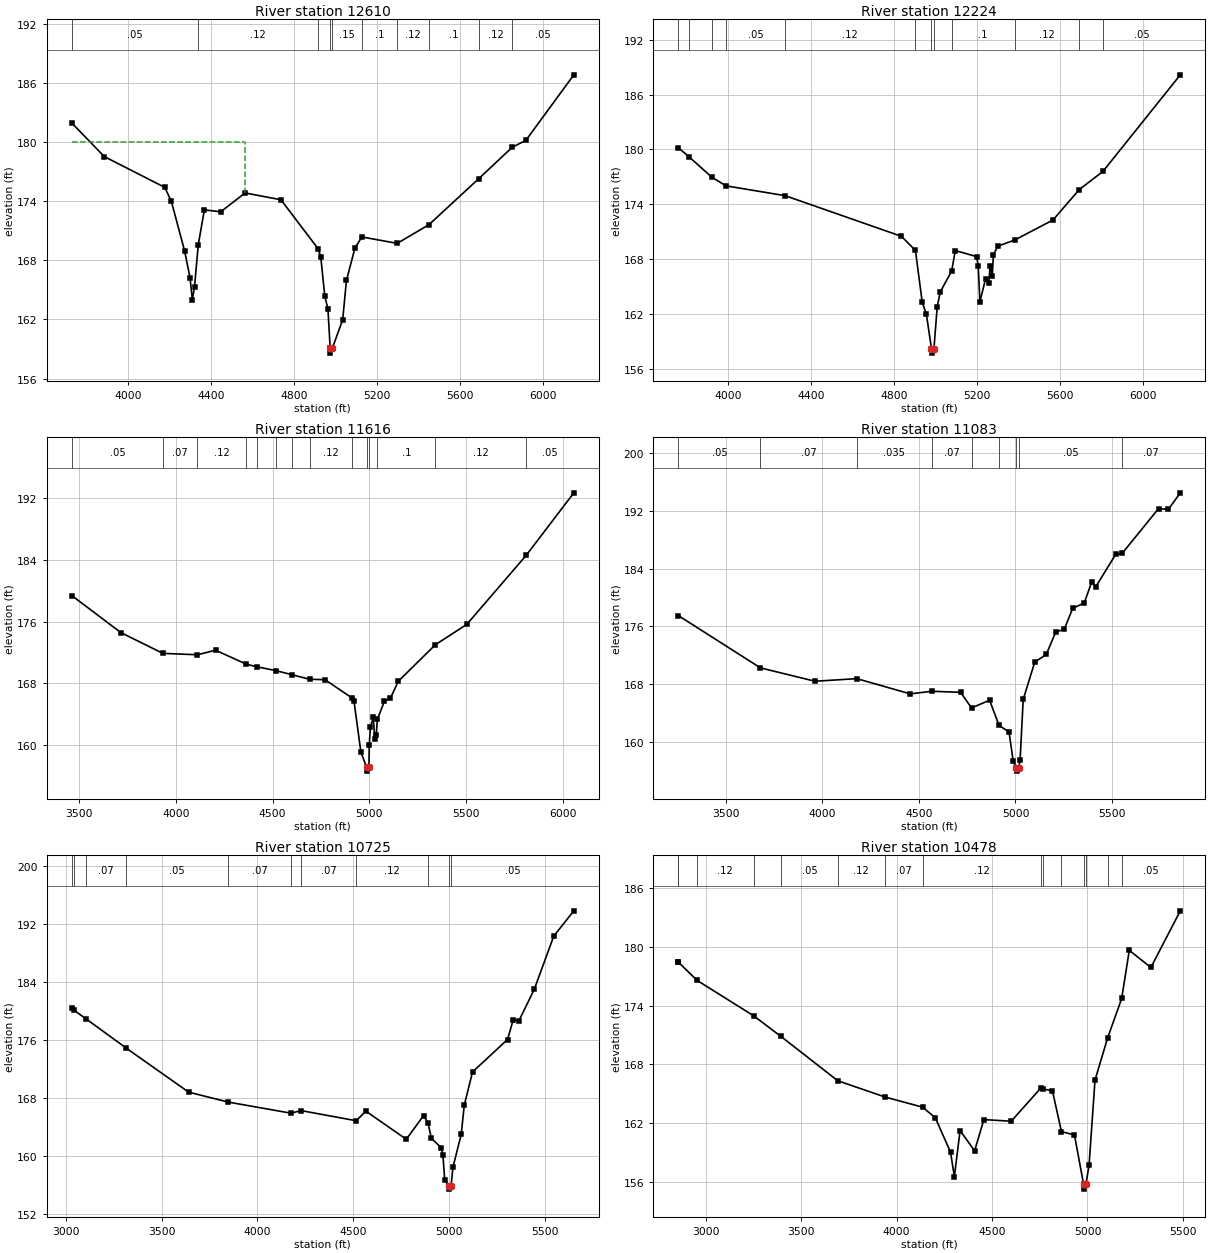
Type RM Length L Ch R = 1 ,12610   ,386,386,386
BEGIN DESCRIPTION:
Mapping XS 04e48fdd
END DESCRIPTION:
XS GIS Cut Line= 5
      2506863.41     13488759.55      2507746.88     13488468.89
      2508091.11      13488564.5      2508500.35     13488434.46
      2509123.81     13488113.18
#Sta/Elev= 30
  3730.6  181.96    3887  178.55  4178.4  175.42  4210.2     174  4273.8  168.98
  4300.3  166.22  4311.3  164.02  4321.8  165.33    4340  169.61  4369.2  173.13
  4448.1  172.94  4565.2  174.85    4738  174.16  4917.8  169.16  4930.1  168.31
  4949.3  164.34  4964.3  163.09  4975.1  159.08  4975.6  158.58  4985.7  159.08
  5035.3  161.97  5053.5  165.96  5094.5  169.27  5128.1  170.38  5298.1  169.73
    5451  171.63  5691.2  176.31  5851.8  179.49  5917.5  180.19  6148.7  186.85
#Mann= 10 ,-1 , 0
  3730.6     .05       0    4340     .12       0  4917.8     .15       0
  4975.1     .05       0  4985.7     .15       0  5128.1      .1       0
  5298.1     .12       0    5451      .1       0  5691.2     .12       0
  5851.8     .05       0
#XS Ineff= 2 , 0
       0  4565.2     180               0
Permanent Ineff=
       F       F
Bank Sta=4975.1,4985.7
XS Rating Curve= 0 ,0
Exp/Cntr=0.3,0.1

Type RM Length L Ch R = 1 ,12224   ,608,608,608
BEGIN DESCRIPTION:
Mapping XS ad958ecd
END DESCRIPTION:
XS GIS Cut Line= 3
      2506951.24     13489066.75      2508149.14     13488889.67
      2509206.45     13488301.11
#Sta/Elev= 30
  3759.4  180.19  3810.2  179.22  3921.7  176.96  3990.3  176.02  4274.7  174.95
  4835.5  170.51  4903.1  168.98  4935.8  163.33    4956  161.99  4980.5  158.25
    4981  157.75  4992.4  158.25  5008.2  162.81  5022.8  164.43  5078.1  166.73
  5095.1  168.96    5198  168.29  5205.9   167.3    5214  163.35  5241.4  165.87
  5257.4  165.43  5263.2  167.28  5273.5   166.2  5279.2   168.5  5300.9  169.44
  5381.4   170.1  5566.2  172.29  5693.5  175.62  5807.8  177.61  6180.4  188.15
#Mann= 12 ,-1 , 0
  3759.4     .07       0  3810.2     .05       0  3921.7     .07       0
  3990.3     .05       0  4274.7     .12       0  4903.1     .05       0
  4980.5     .05       0  4992.4     .05       0  5078.1      .1       0
  5381.4     .12       0  5693.5     .07       0  5807.8     .05       0
Bank Sta=4980.5,4992.4
XS Rating Curve= 0 ,0
Exp/Cntr=0.3,0.1

Type RM Length L Ch R = 1 ,11616   ,533,533,533
BEGIN DESCRIPTION:
Mapping XS f340b0d1
END DESCRIPTION:
XS GIS Cut Line= 3
      2507018.98     13489420.91      2508414.77     13489306.33
      2509419.97     13488655.29
#Sta/Elev= 30
  3460.5   179.4  3714.2   174.6  3932.1   171.9  4110.9  171.72  4204.5  172.31
  4364.5  170.49  4416.6  170.17  4515.5  169.67  4599.4  169.14  4691.2  168.54
  4770.9  168.49    4913  166.08  4920.8  165.74  4956.6   159.1  4986.3  157.13
  4986.8  156.63  4998.3  157.13  4999.8  159.96  5005.8  162.31  5020.9   163.6
  5028.1  160.84  5036.1  161.36  5041.8  163.33  5078.3  165.69  5108.6  166.06
  5150.9   168.3  5341.5  173.01  5504.6  175.66  5812.3  184.62  6058.6  192.72
#Mann= 14 ,-1 , 0
  3460.5     .05       0  3932.1     .07       0  4110.9     .12       0
  4364.5    .035       0  4416.6     .07       0  4515.5     .12       0
  4599.4     .07       0  4691.2     .12       0    4913     .05       0
  4986.3     .05       0  4998.3     .05       0  5041.8      .1       0
  5341.5     .12       0  5812.3     .05       0
Bank Sta=4986.3,4998.3
XS Rating Curve= 0 ,0
Exp/Cntr=0.3,0.1

Type RM Length L Ch R = 1 ,11083   ,358,358,358
BEGIN DESCRIPTION:
Mapping XS a5be20b1
END DESCRIPTION:
XS GIS Cut Line= 3
      2507039.77     13489837.58      2508753.31     13489681.33
      2509523.64     13489259.74
#Sta/Elev= 30
  3254.5  177.51  3680.1  170.26  3962.7  168.41  4178.8  168.77  4454.7  166.67
  4567.5  167.02  4715.8  166.88  4772.6  164.72  4866.4  165.78  4914.9   162.3
  4966.8  161.39  4988.5  157.31  5005.2  156.47  5005.7  155.97  5017.3  156.47
    5024  157.48  5040.1  165.89  5099.8  171.06  5159.5  172.12  5208.9  175.25
  5252.5  175.59  5296.3  178.51  5355.9  179.24  5393.8  182.08  5415.7  181.49
    5519  185.98    5553  186.13  5740.9  192.32  5791.2  192.19  5853.3  194.49
#Mann= 9 ,-1 , 0
  3254.5     .05       0  3680.1     .07       0  4178.8    .035       0
  4567.5     .07       0  4772.6     .12       0  4914.9     .05       0
  5005.2     .05       0  5017.3     .05       0    5553     .07       0
Bank Sta=5005.2,5017.3
XS Rating Curve= 0 ,0
Exp/Cntr=0.3,0.1

Type RM Length L Ch R = 1 ,10725   ,247,247,247
BEGIN DESCRIPTION:
Mapping XS 2ddb7aa4
END DESCRIPTION:
XS GIS Cut Line= 3
      2506867.93     13490202.16       2508810.6     13490019.88
      2509388.68     13489686.57
#Sta/Elev= 30
    3032  180.36  3041.8   180.1  3106.5  178.88  3313.5  174.89  3641.7  168.76
  3848.8  167.39  4175.8  165.86  4227.5  166.22  4515.3  164.82  4565.8  166.14
  4776.7  162.26  4867.1  165.54  4890.6  164.44  4907.3  162.41  4957.5  161.12
  4967.5  160.11  4977.2  156.63  4998.2  155.88  4998.7  155.38  5010.3  155.88
  5020.1  158.42  5063.2  162.94    5079  166.96  5122.1  171.55  5304.5  176.03
  5334.6  178.77  5363.4  178.58  5443.8  182.94  5545.8   190.3  5650.5  193.79
#Mann= 11 ,-1 , 0
    3032     .07       0  3041.8     .05       0  3106.5     .07       0
  3313.5     .05       0  3848.8     .07       0  4175.8    .035       0
  4227.5     .07       0  4515.3     .12       0  4890.6     .05       0
  4998.2     .05       0  5010.3     .05       0
Bank Sta=4998.2,5010.3
XS Rating Curve= 0 ,0
Exp/Cntr=0.3,0.1

Type RM Length L Ch R = 1 ,10478   ,1414,1414,1414
BEGIN DESCRIPTION:
Mapping XS 858ebc3c
END DESCRIPTION:
XS GIS Cut Line= 4
      2506758.51     13490509.46      2508274.14       13490473.
      2509128.31     13490134.46      2509310.31     13490061.66
#Sta/Elev= 30
  2855.6  178.47  2856.4  178.45  2954.8  176.58    3250  172.98  3393.8  170.86
  3691.5  166.33  3938.8  164.67  4135.6  163.63  4202.5  162.55  4282.5  159.02
  4302.5  156.53  4332.5  161.24  4408.6  159.17  4457.2  162.36  4600.4  162.19
  4756.7  165.61  4766.4   165.5  4816.5  165.29  4863.7  161.13  4931.9  160.78
  4979.7  155.75  4980.2  155.25  4991.8  155.75  5008.3  157.69  5039.5   166.4
  5105.7  170.71  5179.3  174.74  5219.1  179.66  5332.4  177.91  5486.5   183.7
#Mann= 15 ,-1 , 0
  2855.6     .07       0  2856.4     .05       0  2954.8     .12       0
    3250     .07       0  3393.8     .05       0  3691.5     .12       0
  3938.8     .07       0  4135.6     .12       0  4756.7     .05       0
  4766.4     .12       0  4863.7     .05       0  4979.7     .05       0
  4991.8     .05       0  5105.7     .12       0  5179.3     .05       0
Bank Sta=4979.7,4991.8
XS Rating Curve= 0 ,0
Exp/Cntr=0.3,0.1

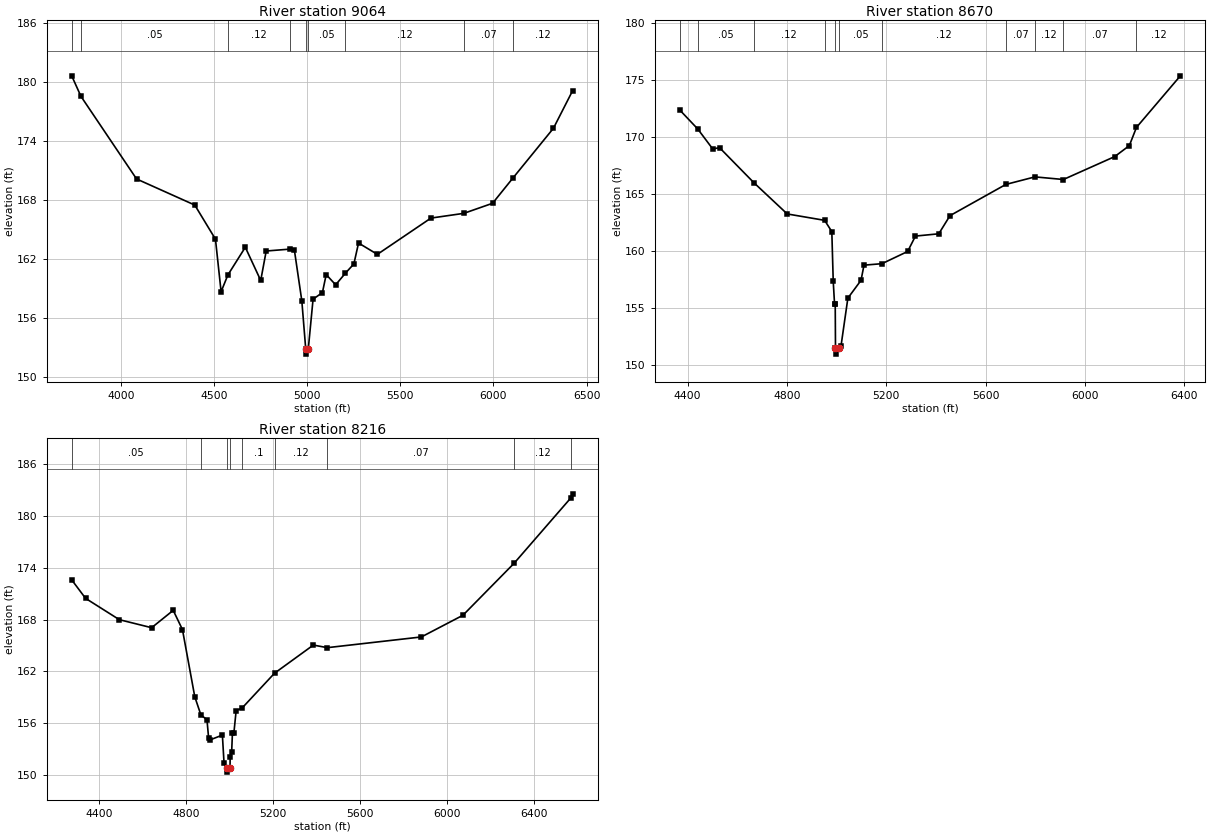
Type RM Length L Ch R = 1 ,9064    ,394,394,394
BEGIN DESCRIPTION:
Mapping XS fc754f2a
END DESCRIPTION:
XS GIS Cut Line= 5
      2506669.96      13491035.5       2507748.1     13490889.67
      2508065.81     13490926.13      2508826.23     13490644.88
      2509196.03      13490353.2
#Sta/Elev= 30
  3734.9   180.6  3784.5  178.52  4083.1  170.14  4395.9  167.49  4506.9  164.03
  4537.2   158.7  4573.6   160.4  4667.2  163.21    4750  159.84  4779.4  162.83
  4905.5  163.02  4930.5  162.96  4970.7  157.78  4991.8  152.87  4992.3  152.37
  5005.3  152.87  5031.1  157.94  5081.4  158.62  5101.6  160.44  5152.4   159.4
  5205.2  160.59  5250.3  161.52  5275.3  163.64  5376.4  162.49  5664.2  166.17
  5840.7  166.65    5995  167.67  6105.6  170.26    6322  175.28  6424.4  179.07
#Mann= 9 ,-1 , 0
  3734.9     .07       0  3784.5     .05       0  4573.6     .12       0
  4905.5     .05       0  4991.8     .05       0  5005.3     .05       0
  5205.2     .12       0  5840.7     .07       0  6105.6     .12       0
Bank Sta=4991.8,5005.3
XS Rating Curve= 0 ,0
Exp/Cntr=0.3,0.1

Type RM Length L Ch R = 1 ,8670    ,454,454,454
BEGIN DESCRIPTION:
MILBY CREEK 12.0
END DESCRIPTION:
XS GIS Cut Line= 3
      2507374.98     13491525.01        2507925.       13491225.
      2509125.03     13490524.98
#Sta/Elev= 30
  4367.8  172.38  4440.9   170.7  4501.2  168.95  4528.7  169.06  4666.4     166
  4801.1  163.25  4951.7  162.69  4980.6   161.7  4986.3  157.33  4991.5  155.38
  4994.3  155.38  4995.4  151.46  4995.9  150.96  5008.9  151.46  5017.5  151.66
  5045.2  155.87  5098.1  157.43  5110.1  158.76  5182.4  158.89  5285.8  159.96
  5317.2  161.31  5411.1  161.51  5456.2   163.1  5681.3  165.84  5798.2   166.5
  5912.7  166.27  6119.4  168.28  6178.1  169.24  6206.9  170.84  6383.6  175.36
#Mann= 11 ,-1 , 0
  4367.8     .07       0  4440.9     .05       0  4666.4     .12       0
  4951.7     .05       0  4995.4     .05       0  5008.9     .05       0
  5182.4     .12       0  5681.3     .07       0  5798.2     .12       0
  5912.7     .07       0  6206.9     .12       0
Bank Sta=4995.4,5008.9
XS Rating Curve= 0 ,0
Exp/Cntr=0.3,0.1

Type RM Length L Ch R = 1 ,8216    ,411,411,411
BEGIN DESCRIPTION:
MILBY CREEK 11.0
END DESCRIPTION:
XS GIS Cut Line= 3
      2507625.01     13492024.99        2508175.       13491525.
      2509374.97     13490525.02
#Sta/Elev= 30
  4273.9  172.59  4337.7  170.45  4493.2  167.98  4641.8  167.05  4741.2  169.06
  4783.7  166.83  4840.5  159.05  4868.5  156.96  4896.6  156.39    4904  154.32
  4910.8  154.06  4967.5  154.62    4975  151.43  4989.1  150.83  4989.6  150.33
  5002.7  150.83  5003.3  152.13  5010.1  152.61  5013.8  154.86  5020.4  154.86
  5030.9  157.46  5058.2  157.75  5207.5  161.78  5386.2  165.04  5450.6  164.74
  5883.5  165.98  6074.8  168.49    6310   174.5  6571.7  182.08  6579.2  182.55
#Mann= 9 ,-1 , 0
  4273.9     .05       0  4868.5     .07       0  4989.1     .05       0
  5002.7     .07       0  5058.2      .1       0  5207.5     .12       0
  5450.6     .07       0    6310     .12       0  6571.7    .035       0
Bank Sta=4989.1,5002.7
XS Rating Curve= 0 ,0
Exp/Cntr=0.3,0.1