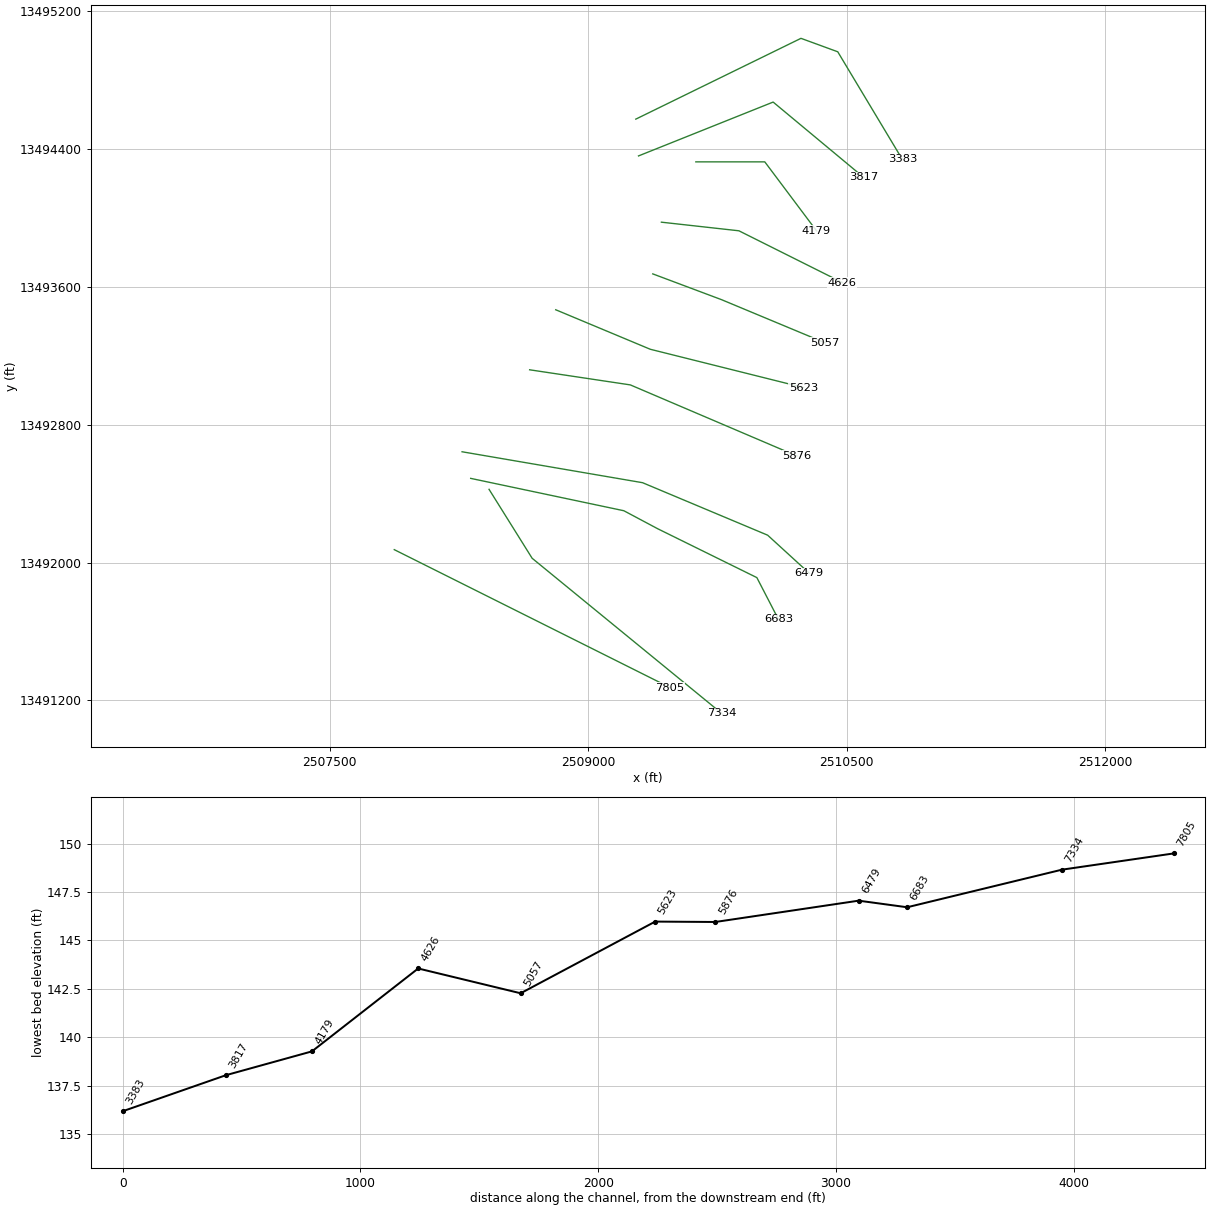
HEC-RAS study MILBY CREEK.prj: MILBY CREEK Base Level Engineering

--- MILBY CREEK.g01 (geometry) --- (continued)

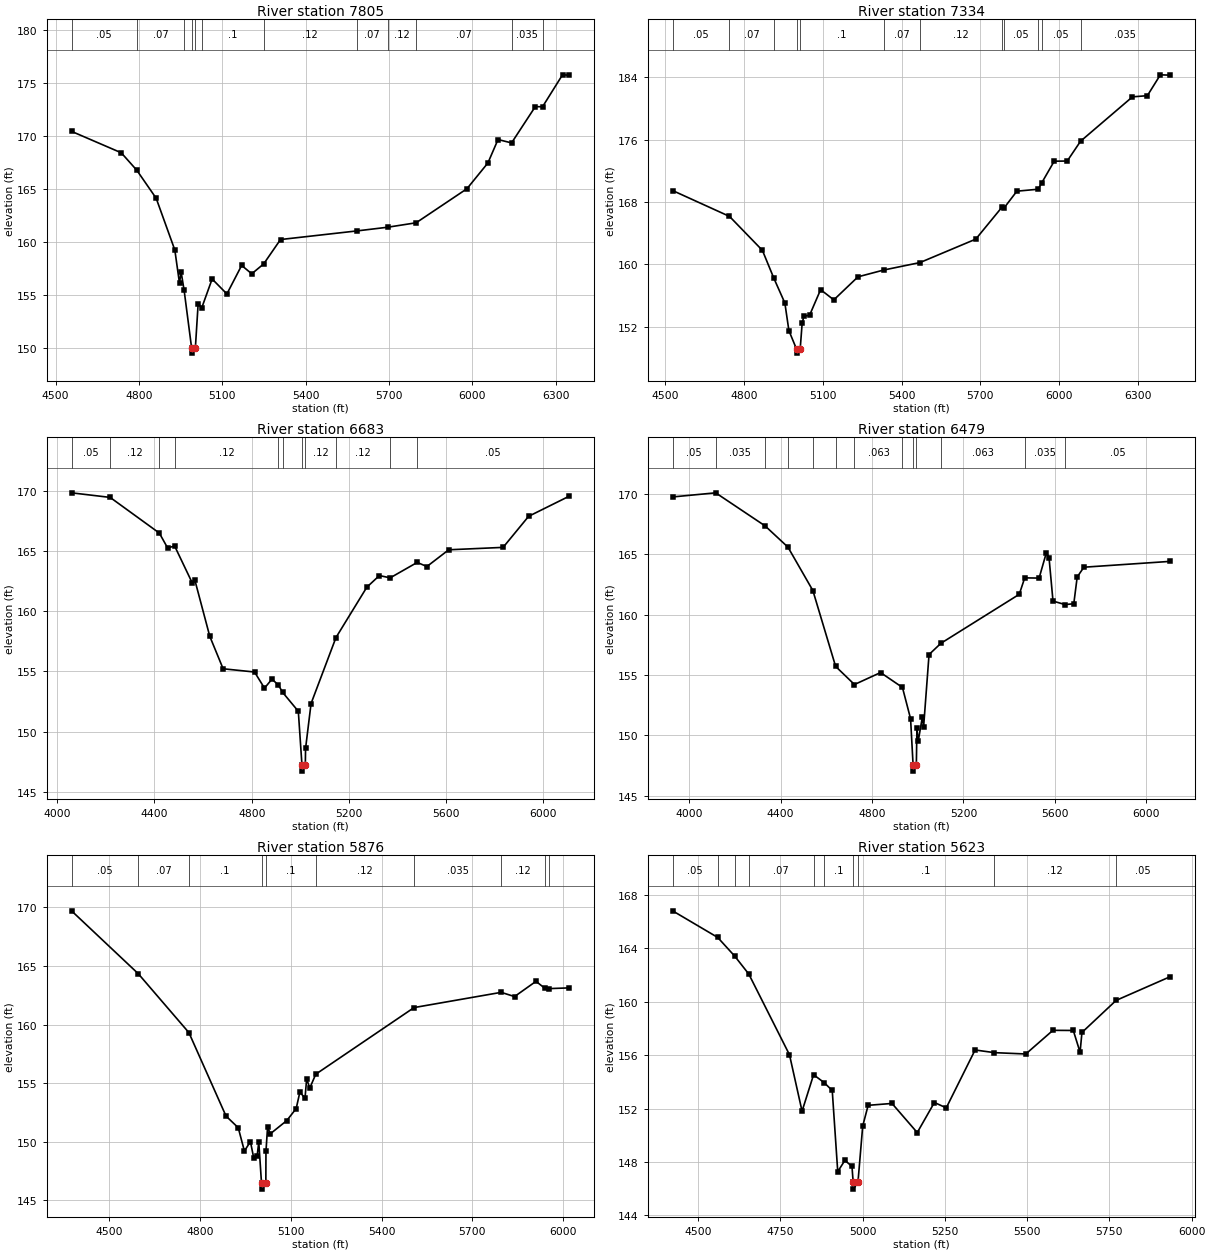
Type RM Length L Ch R = 1 ,7805    ,471,471,471
BEGIN DESCRIPTION:
MILBY CREEK 10.0
END DESCRIPTION:
XS GIS Cut Line= 3
      2507875.01     13492074.99        2508275.       13491875.
      2509474.97     13491275.02
#Sta/Elev= 30
  4557.4   170.4  4736.3  168.38  4792.4  166.73    4862  164.09  4929.1  159.21
  4945.9  156.07  4951.5  157.17  4962.5  155.42  4989.4  149.99  4989.9  149.49
    5003  149.99    5013  154.16  5025.8  153.75  5063.3  156.48  5116.4  155.07
  5169.5  157.76  5205.8  156.97  5248.7   157.9  5309.3   160.2  5583.2  161.01
  5694.7  161.36  5797.3  161.78  5980.1  164.99  6055.5  167.42  6091.9  169.63
  6140.6  169.31    6226  172.73  6252.1  172.72  6323.9  175.73  6346.2   175.7
#Mann= 12 ,-1 , 0
  4557.4     .05       0  4792.4     .07       0  4962.5     .05       0
  4989.4     .05       0    5003     .05       0  5025.8      .1       0
  5248.7     .12       0  5583.2     .07       0  5694.7     .12       0
  5797.3     .07       0  6140.6    .035       0  6252.1     .05       0
Bank Sta=4989.4,5003
XS Rating Curve= 0 ,0
Exp/Cntr=0.3,0.1

Type RM Length L Ch R = 1 ,7334    ,651,651,651
BEGIN DESCRIPTION:
MILBY CREEK 9.0
END DESCRIPTION:
XS GIS Cut Line= 3
      2508425.02     13492424.97        2508675.       13492025.
      2509774.97     13491125.02
#Sta/Elev= 30
  4528.2  169.47  4744.8  166.16  4870.1  161.81  4913.2  158.28  4955.6  155.07
    4971  151.53  5000.2  149.15  5000.7  148.65  5013.9  149.15  5021.4  152.47
  5027.9  153.35  5050.1  153.53  5091.7  156.78    5142  155.47  5233.9  158.42
  5331.7  159.29  5470.2  160.25  5682.5  163.25  5781.2   167.3  5790.1  167.24
    5839  169.39  5920.1  169.64  5933.8  170.47  5981.1  173.23  6030.6  173.25
  6081.5  175.79    6279  181.47  6335.7  181.62  6385.2  184.29  6421.1  184.25
#Mann= 12 ,-1 , 0
  4528.2     .05       0  4744.8     .07       0  4913.2      .1       0
  5000.2     .05       0  5013.9      .1       0  5331.7     .07       0
  5470.2     .12       0  5781.2     .07       0  5790.1     .05       0
  5920.1    .035       0  5933.8     .05       0  6081.5    .035       0
Bank Sta=5000.2,5013.9
XS Rating Curve= 0 ,0
Exp/Cntr=0.3,0.1

Type RM Length L Ch R = 1 ,6683    ,204,204,204
BEGIN DESCRIPTION:
Mapping XS 6699e198
END DESCRIPTION:
XS GIS Cut Line= 5
      2508318.51     13492488.52      2509207.15     13492300.78
      2509403.24     13492196.47      2509979.01     13491912.76
      2510104.19     13491670.76
#Sta/Elev= 30
    4059  169.82  4217.8  169.44    4420  166.48    4454  165.25  4483.1   165.4
  4556.2  162.31  4566.5  162.55  4627.5  157.91  4682.4  155.21  4811.7  154.94
  4852.6   153.6  4883.3  154.35  4909.7  153.86  4927.6  153.24  4991.7  151.68
  5006.7  147.21  5007.2  146.71  5020.5  147.21  5021.5  148.59  5044.1  152.32
  5146.5   157.8  5273.4  161.98  5325.1  162.95  5369.5  162.76  5480.6  164.04
  5520.5   163.7  5610.3  165.09  5833.9  165.29  5938.9  167.87  6103.7  169.52
#Mann= 11 ,-1 , 0
    4059     .05       0  4217.8     .12       0    4420    .063       0
  4483.1     .12       0  4909.7      .1       0  4927.6     .12       0
  5006.7     .05       0  5020.5     .12       0  5146.5     .12       0
  5369.5     .07       0  5480.6     .05       0
Bank Sta=5006.7,5020.5
XS Rating Curve= 0 ,0
Exp/Cntr=0.3,0.1

Type RM Length L Ch R = 1 ,6479    ,603,603,603
BEGIN DESCRIPTION:
Mapping XS 195105c8
END DESCRIPTION:
XS GIS Cut Line= 4
      2508268.43      13492642.9      2509315.63      13492463.5
       2510041.6     13492158.92      2510282.38      13491938.9
#Sta/Elev= 30
  3927.2  169.72  4115.7  170.06  4331.7  167.33    4432  165.57  4541.1  161.98
  4640.6  155.71  4723.1  154.21  4837.3   155.2  4933.1  153.97  4968.7  151.38
  4979.7  147.55  4980.2  147.05  4993.9  147.55  4996.5  150.59    5002  149.51
  5020.3  151.53  5025.7   150.7  5049.5  156.69  5101.5  157.62  5444.4  161.67
  5468.2  163.03  5531.2  163.01  5562.8   165.1  5574.6  164.71    5592  161.11
  5644.9  160.82    5683  160.89  5697.9   163.1  5727.1  163.91  6103.1  164.39
#Mann= 13 ,-1 , 0
  3927.2     .05       0  4115.7    .035       0  4331.7     .12       0
    4432     .05       0  4541.1     .07       0  4640.6      .1       0
  4723.1    .063       0  4933.1      .1       0  4979.7     .05       0
  4993.9      .1       0  5101.5    .063       0  5468.2    .035       0
  5644.9     .05       0
Bank Sta=4979.7,4993.9
XS Rating Curve= 0 ,0
Exp/Cntr=0.3,0.1

Type RM Length L Ch R = 1 ,5876    ,253,253,253
BEGIN DESCRIPTION:
Mapping XS 6fd679b9
END DESCRIPTION:
XS GIS Cut Line= 3
      2508660.55     13493118.54       2509244.7     13493030.92
      2510211.29     13492618.45
#Sta/Elev= 30
  4376.5  169.71  4596.9  164.34  4764.1  159.31  4886.6  152.19    4927  151.19
  4947.3   149.2  4967.2  150.01  4978.4  148.57  4989.3  148.77  4994.8  149.97
  5003.8  146.45  5004.3  145.95  5018.1  146.45  5018.5  149.17  5023.9  151.27
  5032.7  150.67  5087.1   151.8  5118.3  152.83  5130.6  154.25  5147.4  153.69
  5152.8  155.36  5163.2  154.58  5182.9  155.76  5507.5  161.45  5795.1  162.75
  5839.3  162.39  5910.1  163.69  5940.2  163.08  5954.6  163.07  6018.1  163.13
#Mann= 10 ,-1 , 0
  4376.5     .05       0  4596.9     .07       0  4764.1      .1       0
  5003.8     .05       0  5018.1      .1       0  5182.9     .12       0
  5507.5    .035       0  5795.1     .12       0  5940.2    .035       0
  5954.6     .05       0
Bank Sta=5003.8,5018.1
XS Rating Curve= 0 ,0
Exp/Cntr=0.3,0.1

Type RM Length L Ch R = 1 ,5623    ,566,566,566
BEGIN DESCRIPTION:
Mapping XS bfb77059
END DESCRIPTION:
XS GIS Cut Line= 3
      2508811.98     13493466.81       2509360.6     13493237.63
      2510249.48     13493015.41
#Sta/Elev= 30
  4422.7  166.79  4559.7   164.8  4611.5   163.4  4654.2  162.06  4777.9  156.02
  4816.1   151.8  4851.1  154.53  4883.1  153.94  4907.8  153.35  4924.5  147.28
  4946.2  148.12  4967.8  147.67  4971.4  146.47  4971.9  145.97  4985.9  146.47
  5000.4  150.69  5016.9  152.24  5089.4  152.38  5166.1   150.2  5218.2  152.45
  5254.3  152.05  5341.9  156.38  5400.6  156.18    5496  156.08  5578.4  157.85
  5640.3  157.84  5660.9  156.21  5666.6  157.69  5770.5  160.09  5933.5  161.85
#Mann= 10 ,-1 , 0
  4422.7     .05       0  4559.7      .1       0  4611.5     .05       0
  4654.2     .07       0  4851.1     .12       0  4883.1      .1       0
  4971.4     .05       0  4985.9      .1       0  5400.6     .12       0
  5770.5     .05       0
Bank Sta=4971.4,4985.9
XS Rating Curve= 0 ,0
Exp/Cntr=0.3,0.1

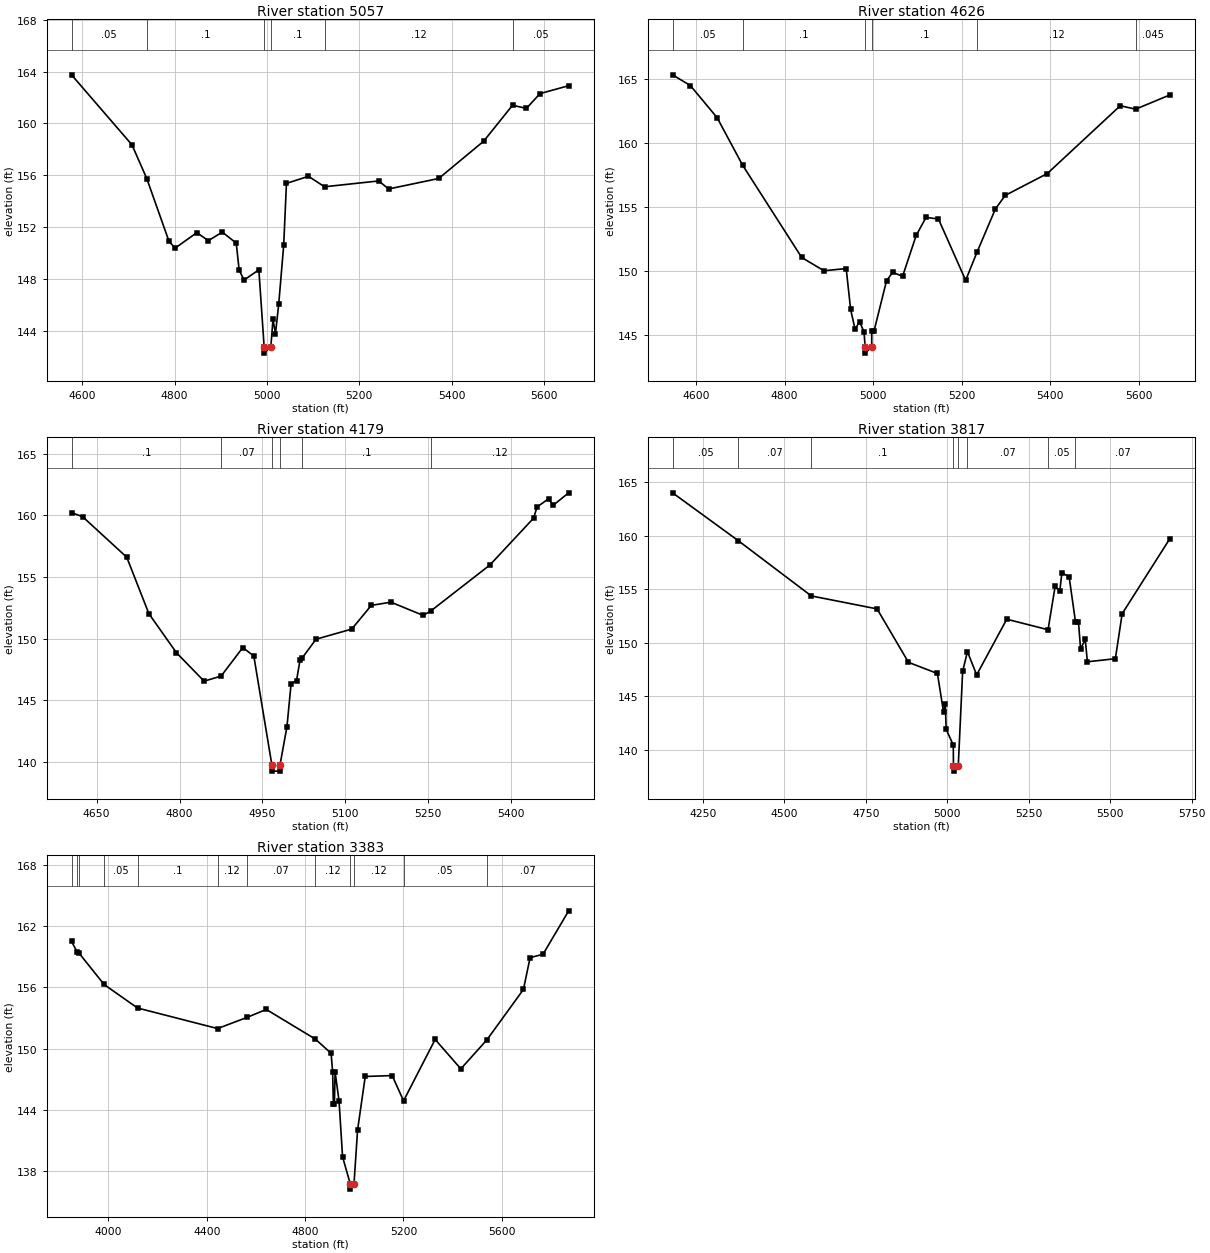
Type RM Length L Ch R = 1 ,5057    ,431,431,431
BEGIN DESCRIPTION:
MILBY CREEK 5.0
END DESCRIPTION:
XS GIS Cut Line= 3
      2509374.96     13493675.02        2509775.       13493525.
      2510374.96     13493275.02
#Sta/Elev= 30
  4576.6  163.75  4707.5  158.35  4739.7  155.74  4787.6  150.92  4800.9  150.37
  4848.1  151.57    4873  150.95  4903.3  151.61  4933.5  150.76  4939.8  148.68
  4950.4  147.91  4982.5   148.7  4993.9  142.77  4994.4  142.27  5008.5  142.77
  5013.1  144.87  5018.5  143.78  5025.5  146.04  5036.3  150.58  5042.3  155.37
    5090  155.92  5124.8  155.11  5242.2  155.56  5263.8  154.94  5372.2  155.75
  5469.7  158.63  5532.1   161.4  5562.3  161.16  5591.6   162.3  5653.8  162.91
#Mann= 6 ,-1 , 0
  4576.6     .05       0  4739.7      .1       0  4993.9     .05       0
  5008.5      .1       0  5124.8     .12       0  5532.1     .05       0
Bank Sta=4993.9,5008.5
XS Rating Curve= 0 ,0
Exp/Cntr=0.3,0.1

Type RM Length L Ch R = 1 ,4626    ,447,447,447
BEGIN DESCRIPTION:
MILBY CREEK 4.0
END DESCRIPTION:
XS GIS Cut Line= 3
      2509425.02       13493975.        2509875.       13493925.
      2510475.02     13493624.99
#Sta/Elev= 30
  4546.8  165.34    4587   164.5  4647.4  161.99    4705  158.27  4838.6  151.04
  4888.9     150  4939.2  150.17  4949.2  146.97  4959.3  145.41  4969.4  146.02
  4979.4  145.21  4982.1  144.05  4982.6  143.55  4996.8  144.05    4997  145.31
  5002.3  145.31  5030.3  149.21  5044.3  149.88  5066.6  149.56  5097.4  152.77
  5119.7  154.18  5147.7  154.05  5209.2  149.25  5235.3  151.49  5276.3  154.83
  5298.6   155.9  5393.7  157.61  5558.6  162.92  5593.3  162.65  5670.4  163.76
#Mann= 6 ,-1 , 0
  4546.8     .05       0    4705      .1       0  4982.1     .05       0
  4996.8      .1       0  5235.3     .12       0  5593.3    .045       0
Bank Sta=4982.1,4996.8
XS Rating Curve= 0 ,0
Exp/Cntr=0.3,0.1

Type RM Length L Ch R = 1 ,4179    ,362,362,362
BEGIN DESCRIPTION:
MILBY CREEK 3.0
END DESCRIPTION:
XS GIS Cut Line= 3
      2509624.96       13494325.        2510025.       13494325.
      2510324.98     13493925.03
#Sta/Elev= 30
  4604.5  160.21  4624.5  159.89  4704.5   156.6  4744.5  152.03  4794.5  148.86
  4844.5  146.56  4875.3  146.97  4914.5  149.28  4934.5   148.6  4967.2  139.77
  4967.7  139.27  4981.4  139.27  4981.9  139.77  4994.5  142.87    5002  146.36
  5011.8   146.6  5018.1  148.25  5021.9  148.43  5047.2  149.96  5111.8  150.78
  5147.2   152.7  5182.7  152.96    5241  151.89  5254.7  152.24  5361.8  155.97
    5441  159.77  5447.2  160.67  5468.1  161.34  5476.4  160.81  5504.5  161.82
#Mann= 6 ,-1 , 0
  4604.5      .1       0  4875.3     .07       0  4967.2     .05       0
  4981.9     .07       0  5021.9      .1       0  5254.7     .12       0
Bank Sta=4967.2,4981.9
XS Rating Curve= 0 ,0
Exp/Cntr=0.3,0.1

Type RM Length L Ch R = 1 ,3817    ,434,434,434
BEGIN DESCRIPTION:
Mapping XS 5ee443a3
END DESCRIPTION:
XS GIS Cut Line= 3
      2509292.26     13494359.42      2510073.47      13494671.9
      2510599.52     13494234.39
#Sta/Elev= 30
  4157.1  163.98  4358.7  159.52  4582.8  154.37  4784.7  153.16    4881  148.18
  4969.8  147.14  4988.7  143.52  4994.1  144.27  4996.6  141.94  5018.5  140.47
    5019  138.54  5019.5  138.04  5033.8  138.54  5047.2  147.33  5061.9  149.18
  5090.2  147.01  5182.6   152.2  5309.3  151.22    5331  155.25  5345.3  154.83
  5351.8  156.53    5374  156.15  5393.4  151.97  5402.6  151.97  5409.1  149.43
  5423.5  150.31    5430  148.23  5515.9  148.52  5536.7  152.71  5682.7  159.69
#Mann= 8 ,-1 , 0
  4157.1     .05       0  4358.7     .07       0  4582.8      .1       0
    5019     .05       0  5033.8      .1       0  5061.9     .07       0
  5309.3     .05       0  5393.4     .07       0
Bank Sta=5019,5033.8
XS Rating Curve= 0 ,0
Exp/Cntr=0.3,0.1

Type RM Length L Ch R = 1 ,3383    ,0,0,0
BEGIN DESCRIPTION:
MILBY CREEK 2.0
END DESCRIPTION:
XS GIS Cut Line= 4
      2509276.61     13494572.95      2510234.93     13495041.69
      2510448.47     13494963.57      2510823.02     13494339.31
#Sta/Elev= 30
  3850.1  160.52  3873.9  159.45  3880.4  159.38  3982.6  156.29  4118.5  153.98
  4444.1  151.96  4563.4  153.05  4642.1  153.84  4841.5  150.93  4905.9  149.53
  4912.2  147.71    4915  144.56  4919.4  144.56  4922.1  147.71  4938.3  144.83
  4952.6  139.36    4984  136.68  4984.5  136.18    4999  136.68  5013.7     142
  5044.8  147.25  5154.3  147.34  5200.7  144.86  5329.2  150.89  5433.6     148
  5539.9  150.86  5688.2   155.8  5715.4  158.93  5767.9  159.26  5872.3  163.53
#Mann= 12 ,-1 , 0
  3850.1     .07       0  3873.9     .05       0  3880.4     .07       0
  3982.6     .05       0  4118.5      .1       0  4444.1     .12       0
  4563.4     .07       0  4841.5     .12       0    4984     .05       0
    4999     .12       0  5200.7     .05       0  5539.9     .07       0
Bank Sta=4984,4999
XS Rating Curve= 0 ,0
Exp/Cntr=0.3,0.1

Chan Stop Cuts=-1
Use User Specified Reach Order=0
Composite Channel Slope=5