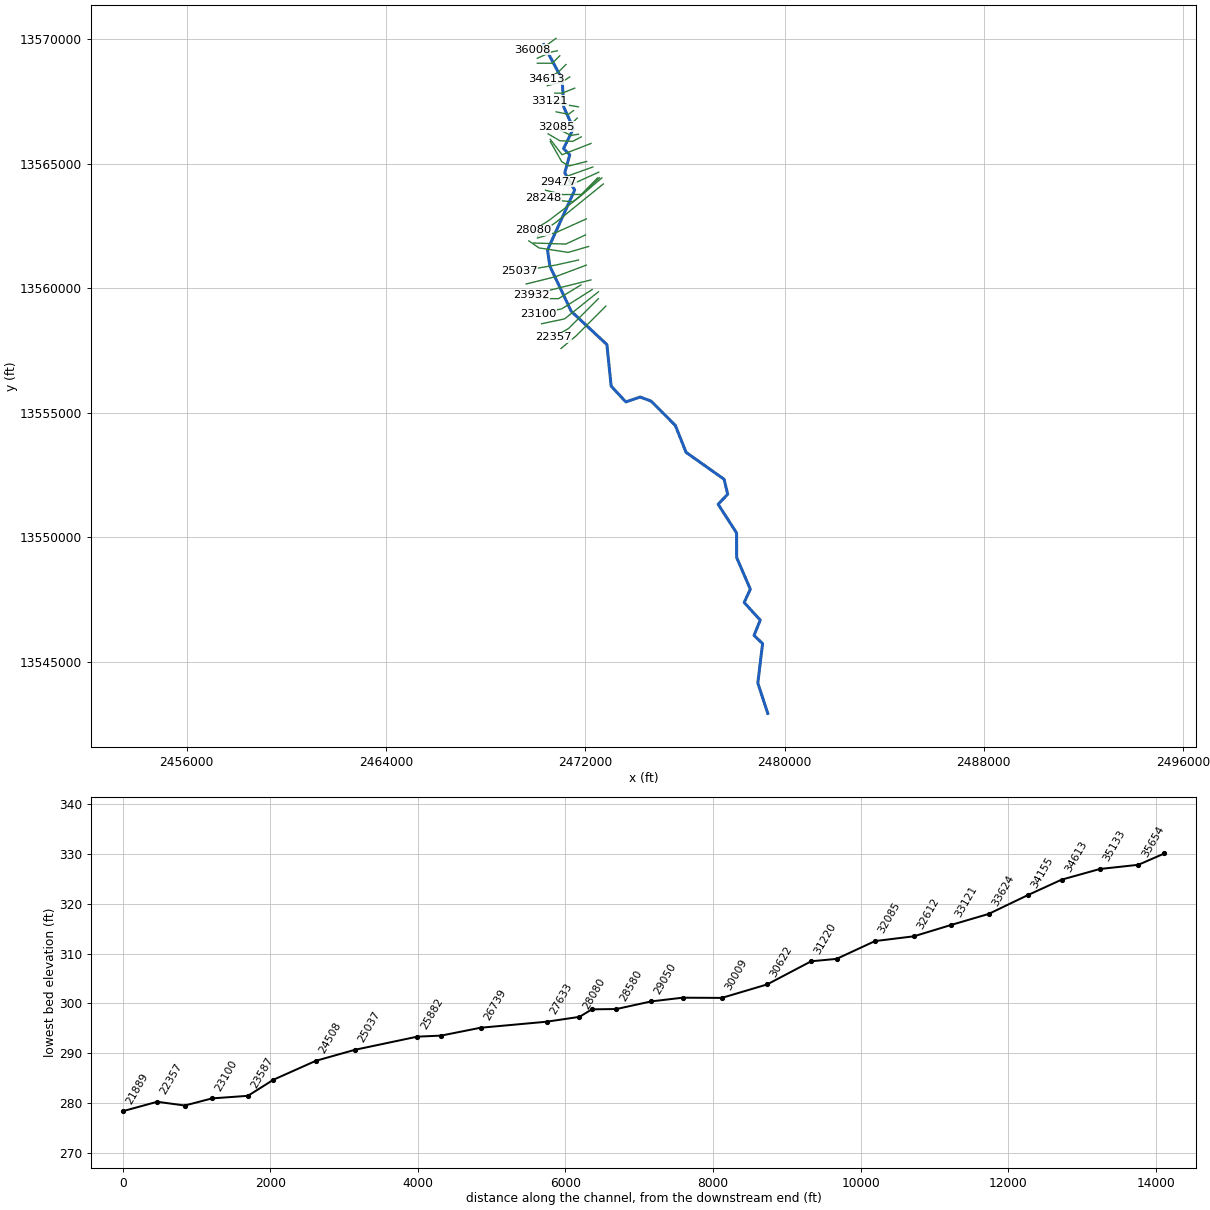
--- SHILOH CREEK.prj (project) ---

Proj Title=SHILOH CREEK Base Level Engineering
Current Plan=p01
Default Exp/Contr=0.3,0.1
English Units
Geom File=g01
Flow File=f01
Plan File=p01
Y Axis Title=Elevation
X Axis Title(PF)=Main Channel Distance
X Axis Title(XS)=Station
BEGIN DESCRIPTION:
SHILOH CREEK
END DESCRIPTION:
DSS Export Rating Curves= 0
DSS Export Rating Curve Sorted= 0
DSS Export Volume Flow Curves= 0
DXF OffsetX= 0
DXF OffsetY= 0
DXF ScaleX= 1
DXF ScaleY= 10

--- SHILOH CREEK.p01 (plan) ---

Plan Title=Multiple Run
Short Identifier=Multiple
Geom File=g01
Flow File=f01
Subcritical Flow
K Sum by GR= 0
Std Step Tol= 0.01
Critical Tol= 0.01
Num of Std Step Trials= 20
Max Error Tol= 0.3
Flow Tol Ratio= 0.001
Split Flow NTrial= 30
Split Flow Tol= 0.02
Split Flow Ratio= 0.02
Log Output Level= 0
Friction Slope Method= 1
Unsteady Friction Slope Method= 2
Unsteady Bridges Friction Slope Method= 1
Parabolic Critical Depth
Global Vel Dist=  1 , 1 , 1
Global Log Level= 0
CheckData=True
Encroach Param= -1, 0, 0, 0
BEGIN DESCRIPTION:
Multiple Run
END DESCRIPTION:

--- SHILOH CREEK.f01 (steady flow) ---

Flow Title=Multiple
Number of Profiles=7
Profile Names=10-year,25-year,50-year,1pct_min,100-year,1pct_plu,500-year
River Rch & RM= SHILOH CREEK,Reach-1,36008
     365     570     749     478     953    1902    1527
River Rch & RM= SHILOH CREEK,Reach-1,33624
     527     841    1121     724    1444    2881    2374
River Rch & RM= SHILOH CREEK,Reach-1,29477
     923    1516    2060    1353    2700    5388    4601
River Rch & RM= SHILOH CREEK,Reach-1,25037
    1023    1688    2301    1516    3024    6033    5178
River Rch & RM= SHILOH CREEK,Reach-1,22731
    1091    1802    2457    1618    3229    6443    5530
River Rch & RM= SHILOH CREEK,Reach-1,18647
    1616    2720    3757    2502    4993    9962    8751
River Rch & RM= SHILOH CREEK,Reach-1,14897
    1806    3053    4228    2823    5633   11240    9922
River Rch & RM= SHILOH CREEK,Reach-1,12458
    2163    3684    5127    3439    6861   13690   12193
River Rch & RM= SHILOH CREEK,Reach-1,9707
    2530    4311    6003    4025    8031   16023   14237
River Rch & RM= SHILOH CREEK,Reach-1,7266
    2632    4494    6266    4206    8392   16745   14914
River Rch & RM= SHILOH CREEK,Reach-1,6010
    2789    4783    6688    4500    8980   17917   16043
River Rch & RM= SHILOH CREEK,Reach-1,402
    2906    4977    6953    4675    9327   18610   16628
Boundary for River Rch & Prof#=SHILOH CREEK,Reach-1,1
Up Type=0
Dn Type=3
Dn Slope=0.002
Boundary for River Rch & Prof#=SHILOH CREEK,Reach-1,2
Up Type=0
Dn Type=3
Dn Slope=0.002
Boundary for River Rch & Prof#=SHILOH CREEK,Reach-1,3
Up Type=0
Dn Type=3
Dn Slope=0.002
Boundary for River Rch & Prof#=SHILOH CREEK,Reach-1,4
Up Type=0
Dn Type=3
Dn Slope=0.002
Boundary for River Rch & Prof#=SHILOH CREEK,Reach-1,5
Up Type=0
Dn Type=3
Dn Slope=0.002
Boundary for River Rch & Prof#=SHILOH CREEK,Reach-1,6
Up Type=0
Dn Type=3
Dn Slope=0.002
Boundary for River Rch & Prof#=SHILOH CREEK,Reach-1,7
Up Type=0
Dn Type=3
Dn Slope=0.002

--- SHILOH CREEK.g01 (geometry) ---

Geom Title=Existing Conditions

River Reach=SHILOH CREEK,Reach-1
Reach XY= 30
      2470325.00     13569775.00      2471071.46     13568373.53
      2471132.99     13567271.65      2471525.47     13566404.84
      2471124.50     13565599.96      2471375.32     13565350.12
      2471175.00     13564625.00      2471574.24     13563935.69
      2470482.98     13561528.35      2470576.58     13560881.05
      2471435.77     13559065.30      2472866.11     13557731.93
      2473038.64     13556061.66      2473626.42     13555428.50
      2474199.89     13555625.32      2474638.56     13555461.54
      2475614.48     13554485.00      2476044.77     13553404.87
      2477571.87     13552323.38      2477717.40     13551721.66
      2477332.58     13551321.65      2478072.76     13550169.07
      2478076.65     13549181.04      2478624.62     13547909.73
      2478378.53     13547376.45      2479022.95     13546669.16
      2478774.52     13546054.84      2479117.45     13545725.00
      2478925.09     13544140.40      2479325.00     13542925.00

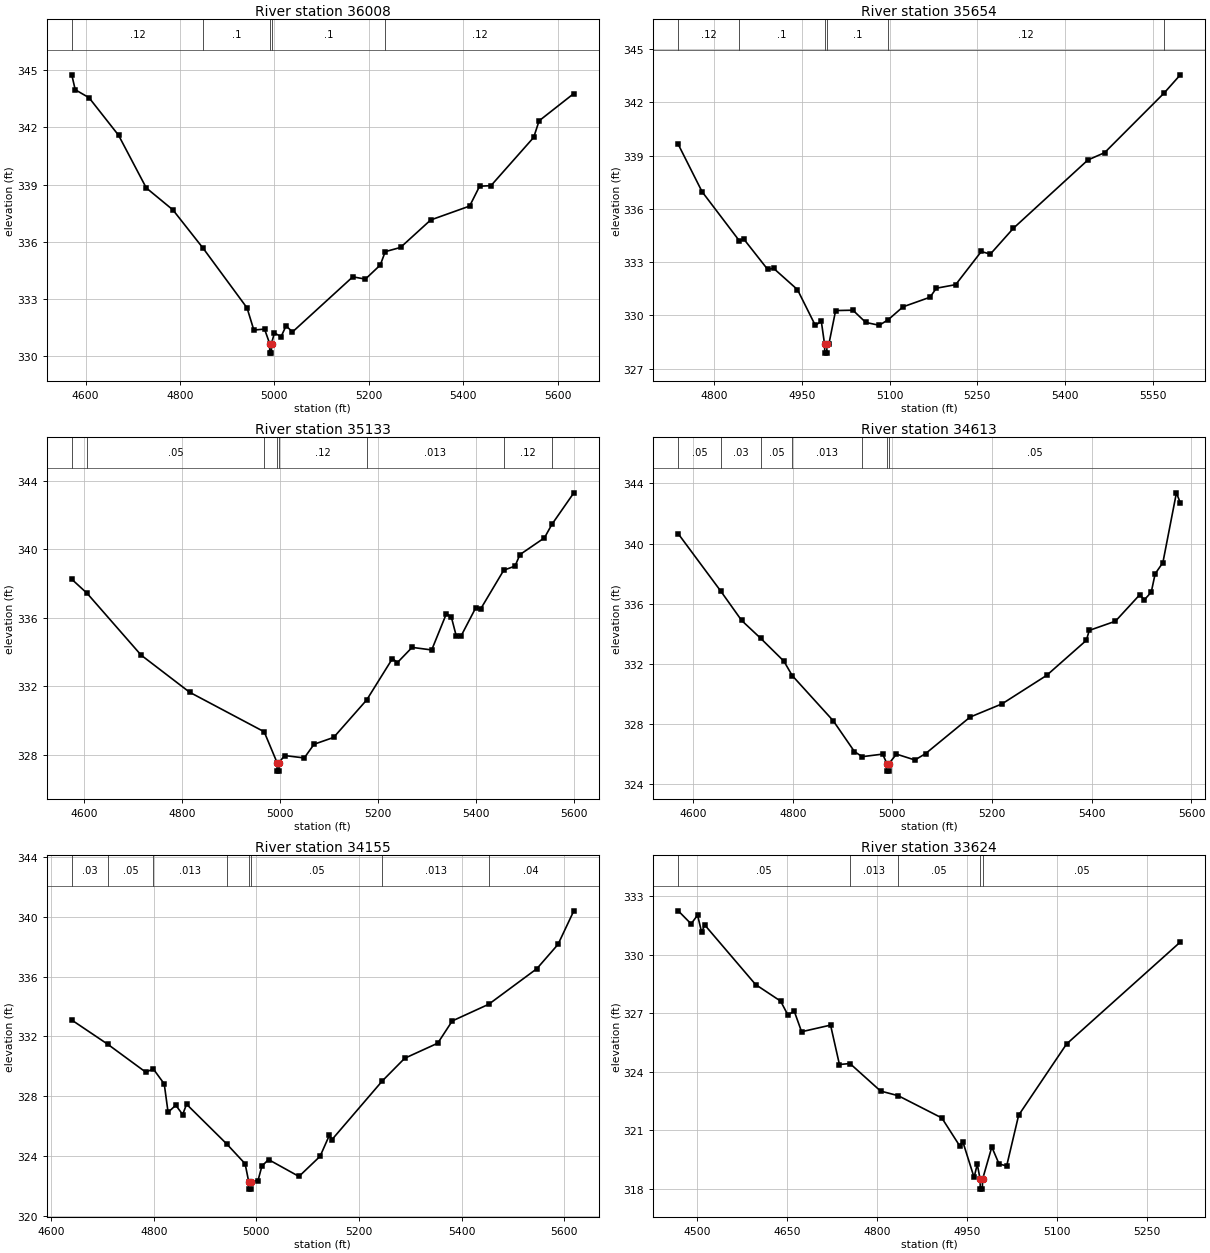
Type RM Length L Ch R = 1,36008,354,354,354
BEGIN DESCRIPTION:
SHILOH CREEK 72.0
END DESCRIPTION:
XS GIS Cut Line= 3
      2470824.96     13570024.97      2470476.44     13569770.54
      2469875.04     13569575.01
#Sta/Elev= 30
  4570.7  344.75  4578.0  343.97  4607.3  343.55  4669.9  341.58  4728.6  338.82
  4785.0  337.67  4849.3  335.65  4942.1  332.53  4956.5  331.37  4979.2  331.42
  4990.0  330.66  4990.2  330.16  4993.7  330.16  4994.0  330.66  5000.0  331.22
  5014.2  331.02  5024.8  331.59  5038.4  331.27  5166.2  334.16  5192.9  334.04
  5224.5  334.78  5234.9  335.48  5267.3  335.70  5331.2  337.14  5413.8  337.87
  5434.9  338.91  5459.0  338.94  5549.5  341.47  5561.0  342.34  5634.6  343.77
#Mann=5,-1,0
  4570.7    0.12       0  4849.3     0.1       0  4990.0    0.05       0
  4994.0     0.1       0  5234.9    0.12       0
Bank Sta=4990,4994
Exp/Cntr=0.3,0.1

Type RM Length L Ch R = 1,35654,521,521,521
BEGIN DESCRIPTION:
SHILOH CREEK 71.0
END DESCRIPTION:
XS GIS Cut Line= 3
      2470875.04     13569525.01      2470625.00     13569475.00
      2470075.04     13569225.02
#Sta/Elev= 30
  4738.2  339.64  4779.0  336.97  4842.6  334.21  4850.4  334.30  4891.2  332.59
  4901.4  332.65  4942.2  331.45  4972.8  329.43  4983.0  329.67  4988.6  328.37
  4988.9  327.87  4992.4  327.87  4992.6  328.37  4995.9  328.37  5007.5  330.27
  5037.1  330.29  5059.1  329.60  5082.2  329.44  5097.7  329.76  5122.8  330.48
  5168.9  331.02  5179.9  331.53  5212.9  331.73  5256.8  333.60  5272.2  333.45
  5311.7  334.91  5439.2  338.76  5467.7  339.17  5569.5  342.53  5597.3  343.56
#Mann=6,-1,0
  4738.2    0.12       0  4842.6     0.1       0  4988.6    0.05       0
  4992.6     0.1       0  5097.7    0.12       0  5569.5   0.013       0
Bank Sta=4988.6,4992.6
Exp/Cntr=0.3,0.1

Type RM Length L Ch R = 1,35133,520,520,520
BEGIN DESCRIPTION:
SHILOH CREEK 70.0
END DESCRIPTION:
XS GIS Cut Line= 3
      2470975.02     13569325.02      2470675.00     13569025.00
      2470074.99     13569025.00
#Sta/Elev= 30
  4575.6  338.24  4606.8  337.42  4717.0  333.81  4816.0  331.64  4968.1  329.33
  4994.4  327.53  4994.6  327.03  4998.1  327.03  4998.4  327.53  5009.9  327.94
  5049.9  327.80  5069.9  328.60  5109.9  329.00  5177.3  331.19  5229.9  333.61
  5239.9  333.37  5269.9  334.26  5309.9  334.11  5339.9  336.23  5349.9  336.04
  5359.9  334.94  5369.9  334.93  5399.9  336.58  5409.9  336.51  5456.9  338.77
  5479.9  339.01  5489.9  339.68  5539.9  340.66  5555.2  341.45  5599.9  343.29
#Mann=8,-1,0
  4575.6    0.12       0  4606.8    0.05       0  4968.1    0.12       0
  4994.4    0.05       0  4998.4    0.12       0  5177.3   0.013       0
  5456.9    0.12       0  5555.2    0.04       0
Bank Sta=4994.4,4998.4
Exp/Cntr=0.3,0.1

Type RM Length L Ch R = 1,34613,458,458,458
BEGIN DESCRIPTION:
SHILOH CREEK 69.0
END DESCRIPTION:
XS GIS Cut Line= 3
      2471224.97     13568974.97      2470925.00     13568675.00
      2470425.01     13568375.01
#Sta/Elev= 30
  4570.3  340.65  4655.4  336.85  4697.5  334.89  4735.8  333.70  4782.4  332.18
  4798.9  331.23  4881.4  328.22  4923.8  326.18  4939.3  325.84  4980.4  326.01
  4989.0  325.38  4989.2  324.88  4992.7  324.88  4993.0  325.38  5008.1  326.01
  5045.1  325.62  5066.4  326.04  5155.8  328.47  5220.0  329.35  5309.4  331.24
  5389.1  333.57  5394.9  334.23  5447.4  334.84  5496.0  336.59  5505.7  336.27
  5519.3  336.77  5527.1  337.99  5542.6  338.73  5569.8  343.37  5577.6  342.70
#Mann=7,-1,0
  4570.3    0.05       0  4655.4    0.03       0  4735.8    0.05       0
  4798.9   0.013       0  4939.3    0.05       0  4989.0    0.05       0
  4993.0    0.05       0
Bank Sta=4989,4993
Exp/Cntr=0.3,0.1

Type RM Length L Ch R = 1,34155,531,531,531
BEGIN DESCRIPTION:
SHILOH CREEK 68.0
END DESCRIPTION:
XS GIS Cut Line= 3
      2471374.98     13568474.99      2471075.00     13568275.00
      2470475.00     13568125.00
#Sta/Elev= 30
  4640.0  333.10  4710.1  331.48  4784.2  329.61  4799.1  329.82  4820.3  328.82
  4827.8  326.92  4842.8  327.39  4856.3  326.77  4863.8  327.46  4942.1  324.80
  4978.0  323.47  4985.0  322.27  4985.3  321.77  4988.8  321.77  4989.0  322.27
  5003.1  322.34  5010.8  323.32  5023.7  323.75  5083.0  322.62  5124.2  323.97
  5142.3  325.38  5147.4  325.09  5245.5  329.02  5289.2  330.54  5353.6  331.55
  5381.9  333.04  5453.1  334.16  5546.8  336.54  5588.1  338.17  5619.0  340.42
#Mann=8,-1,0
  4640.0    0.03       0  4710.1    0.05       0  4799.1   0.013       0
  4942.1    0.05       0  4985.0    0.05       0  4989.0    0.05       0
  5245.5   0.013       0  5453.1    0.04       0
Bank Sta=4985,4989
Exp/Cntr=0.3,0.1

Type RM Length L Ch R = 1,33624,503,503,503
BEGIN DESCRIPTION:
SHILOH CREEK 67.0
END DESCRIPTION:
XS GIS Cut Line= 3
      2471574.97     13568024.99      2471075.00     13567825.00
      2470774.99     13567825.00
#Sta/Elev= 30
  4467.9  332.26  4489.4  331.59  4500.2  332.04  4506.9  331.17  4512.3  331.53
  4597.1  328.48  4638.9  327.63  4651.0  326.92  4661.7  327.11  4673.9  326.06
  4722.3  326.40  4737.1  324.38  4754.7  324.43  4805.8  323.02  4835.3  322.78
  4908.1  321.64  4937.7  320.22  4943.1  320.43  4962.0  318.59  4967.3  319.27
  4972.1  318.49  4972.3  317.99  4975.8  317.99  4976.1  318.49  4991.6  320.15
  5003.7  319.28  5016.4  319.18  5036.4  321.78  5116.4  325.43  5306.4  330.66
#Mann=5,-1,0
  4467.9    0.05       0  4754.7   0.013       0  4835.3    0.05       0
  4972.1    0.05       0  4976.1    0.05       0
Bank Sta=4972.1,4976.1
Exp/Cntr=0.3,0.1

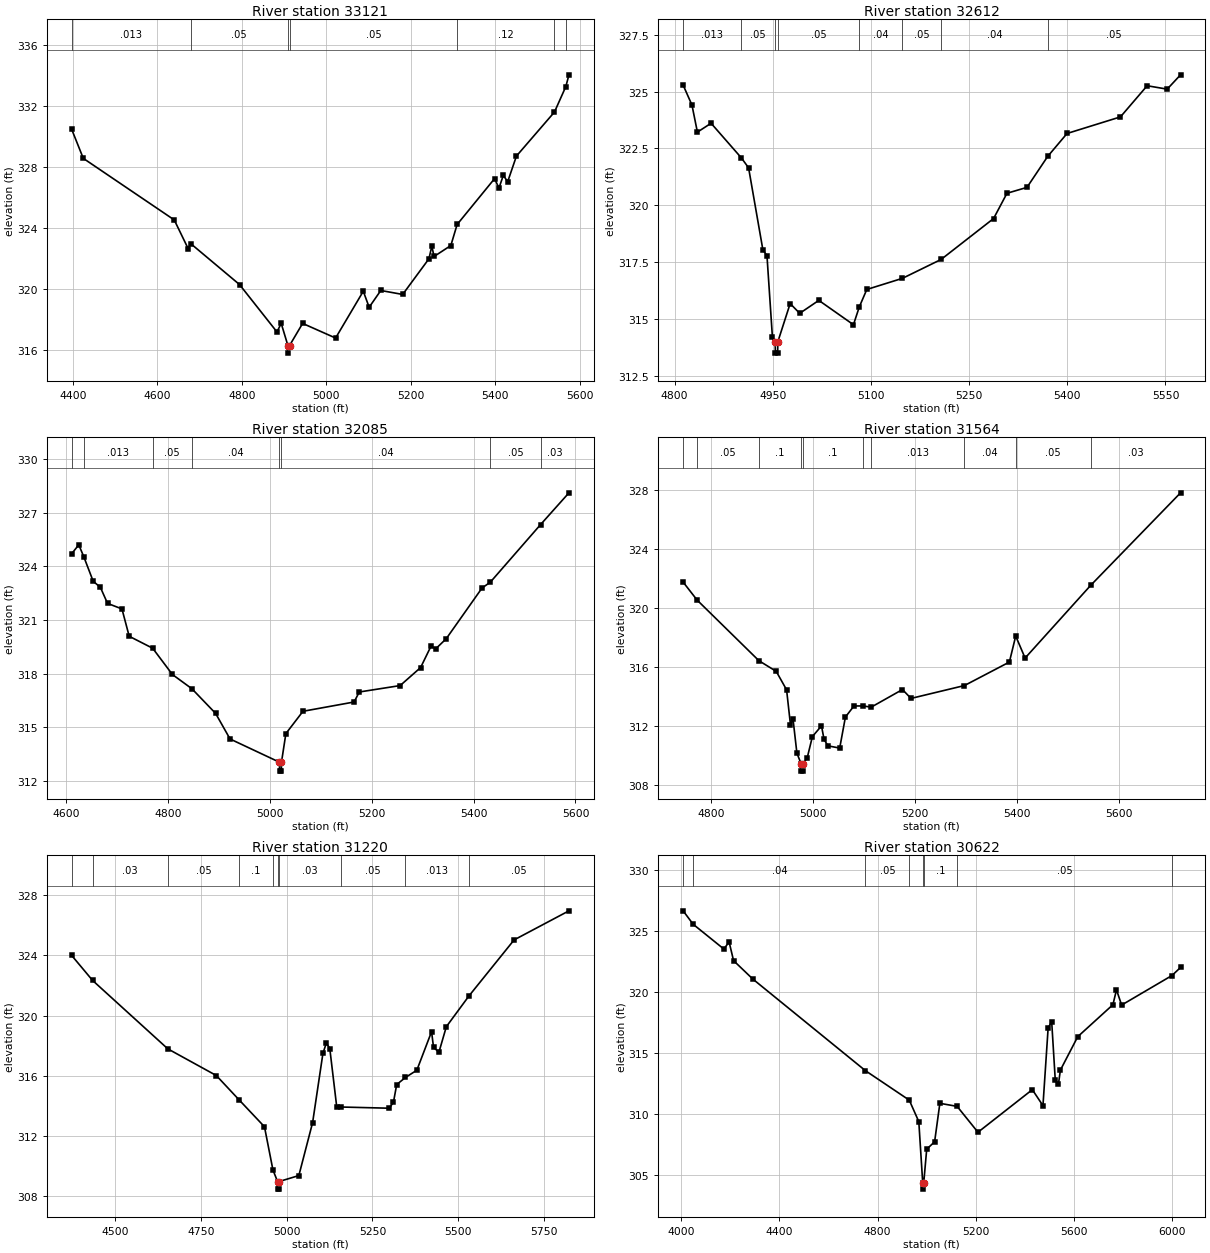
Type RM Length L Ch R = 1,33121,509,509,509
BEGIN DESCRIPTION:
SHILOH CREEK 66.0
END DESCRIPTION:
XS GIS Cut Line= 3
      2471724.95     13567275.01      2471125.00     13567375.00
      2470575.02     13567525.00
#Sta/Elev= 30
  4396.7  330.51  4424.5  328.58  4640.0  324.54  4672.9  322.66  4678.8  322.99
  4794.6  320.30  4883.3  317.19  4893.4  317.75  4909.2  316.30  4909.4  315.80
  4913.2  316.30  4944.1  317.75  5022.2  316.79  5087.8  319.86  5101.7  318.81
  5129.3  319.91  5181.1  319.65  5243.3  321.99  5250.2  322.82  5255.4  322.14
  5295.2  322.86  5310.1  324.24  5398.8  327.25  5409.2  326.63  5419.5  327.46
  5429.9  327.05  5450.6  328.73  5540.7  331.62  5567.6  333.29  5575.0  334.06
#Mann=7,-1,0
  4396.7   0.013       0  4678.8    0.05       0  4909.2    0.05       0
  4913.2    0.05       0  5310.1    0.12       0  5540.7    0.04       0
  5567.6    0.12       0
Bank Sta=4909.2,4913.2
Exp/Cntr=0.3,0.1

Type RM Length L Ch R = 1,32612,527,527,527
BEGIN DESCRIPTION:
SHILOH CREEK 65.0
END DESCRIPTION:
XS GIS Cut Line= 3
      2471524.97     13567124.98      2471325.00     13566975.00
      2470824.96     13567075.01
#Sta/Elev= 30
  4813.1  325.29  4826.6  324.41  4834.9  323.22  4855.8  323.61  4902.0  322.09
  4913.1  321.65  4934.9  318.05  4941.2  317.78  4949.5  314.21  4953.8  314.00
  4954.0  313.50  4957.5  313.50  4957.8  314.00  4976.6  315.68  4991.2  315.25
  5020.4  315.82  5073.3  314.75  5082.2  315.53  5093.7  316.30  5148.2  316.79
  5207.2  317.62  5287.4  319.42  5307.8  320.53  5338.4  320.79  5370.0  322.15
  5399.6  323.16  5481.2  323.89  5522.0  325.26  5552.6  325.11  5573.0  325.74
#Mann=8,-1,0
  4813.1   0.013       0  4902.0    0.05       0  4953.8    0.05       0
  4957.8    0.05       0  5082.2    0.04       0  5148.2    0.05       0
  5207.2    0.04       0  5370.0    0.05       0
Bank Sta=4953.8,4957.8
Exp/Cntr=0.3,0.1

Type RM Length L Ch R = 1,32085,521,521,521
BEGIN DESCRIPTION:
SHILOH CREEK 64.0
END DESCRIPTION:
XS GIS Cut Line= 3
      2471675.03     13566825.03      2471375.00     13566525.00
      2470824.97     13566475.00
#Sta/Elev= 30
  4610.6  324.70  4624.8  325.21  4634.7  324.54  4653.1  323.17  4667.2  322.83
  4681.3  321.93  4709.6  321.62  4723.8  320.09  4769.9  319.42  4808.6  317.95
  4847.0  317.15  4893.5  315.77  4921.8  314.34  5018.8  313.04  5019.0  312.54
  5022.5  312.54  5022.8  313.04  5031.4  314.64  5065.0  315.89  5165.4  316.41
  5175.5  316.97  5255.8  317.33  5296.0  318.34  5316.1  319.52  5326.1  319.40
  5346.2  319.95  5416.5  322.79  5432.9  323.12  5531.4  326.34  5587.2  328.12
#Mann=8,-1,0
  4610.6    0.05       0  4634.7   0.013       0  4769.9    0.05       0
  4847.0    0.04       0  5018.8    0.04       0  5022.8    0.04       0
  5432.9    0.05       0  5531.4    0.03       0
Bank Sta=5018.8,5022.8
Exp/Cntr=0.3,0.1

Type RM Length L Ch R = 1,31564,344,344,344
BEGIN DESCRIPTION:
SHILOH CREEK 63.0
END DESCRIPTION:
XS GIS Cut Line= 3
      2471724.99     13566175.00      2471425.00     13566125.00
      2470824.96     13566425.02
#Sta/Elev= 30
  4745.5  321.75  4773.0  320.53  4894.1  316.43  4928.0  315.71  4948.3  314.46
  4955.9  312.10  4960.9  312.48  4968.5  310.18  4976.7  309.46  4976.9  308.96
  4980.4  308.96  4980.7  309.46  4988.8  309.87  4998.9  311.30  5016.7  312.02
  5021.8  311.10  5029.4  310.67  5052.4  310.52  5063.6  312.62  5080.4  313.37
  5098.0  313.37  5114.2  313.29  5175.4  314.48  5192.2  313.88  5296.9  314.75
  5385.0  316.34  5397.4  318.10  5415.8  316.61  5544.1  321.52  5720.5  327.79
#Mann=10,-1,0
  4745.5   0.013       0  4773.0    0.05       0  4894.1     0.1       0
  4976.7    0.05       0  4980.7     0.1       0  5098.0    0.05       0
  5114.2   0.013       0  5296.9    0.04       0  5397.4    0.05       0
  5544.1    0.03       0
Bank Sta=4976.7,4980.7
Exp/Cntr=0.3,0.1

Type RM Length L Ch R = 1,31220,598,598,598
BEGIN DESCRIPTION:
Mapping XS b33c6ebb
END DESCRIPTION:
XS GIS Cut Line= 4
      2471832.56     13566066.23      2471494.06     13565888.30
      2470977.57     13565914.34      2470504.46     13566192.13
#Sta/Elev= 30
  4373.8  324.00  4435.1  322.33  4654.1  317.79  4795.3  316.02  4861.4  314.41
  4935.5  312.62  4960.1  309.76  4973.6  308.98  4973.8  308.48  4977.3  308.48
  4977.6  308.98  5035.6  309.38  5075.7  312.90  5105.7  317.49  5115.7  318.18
  5125.7  317.81  5145.8  313.96  5157.3  313.93  5299.0  313.85  5311.1  314.26
  5320.5  315.42  5345.9  315.89  5379.1  316.37  5422.0  318.93  5427.8  317.88
  5443.5  317.57  5465.0  319.26  5531.5  321.32  5662.3  325.02  5822.0  326.95
#Mann=10,-1,0
  4373.8    0.05       0  4435.1    0.03       0  4654.1    0.05       0
  4861.4     0.1       0  4960.1    0.03       0  4973.6    0.03       0
  4977.6    0.03       0  5157.3    0.05       0  5345.9   0.013       0
  5531.5    0.05       0
Bank Sta=4973.6,4977.6
Exp/Cntr=0.3,0.1

Type RM Length L Ch R = 1,30622,613,613,613
BEGIN DESCRIPTION:
SHILOH CREEK 62.0
END DESCRIPTION:
XS GIS Cut Line= 3
      2472229.60     13565805.13      2471065.94     13565352.58
      2470593.95     13565970.33
#Sta/Elev= 30
  4008.0  326.62  4048.8  325.52  4173.9  323.49  4195.3  324.07  4213.4  322.54
  4291.9  321.03  4750.8  313.52  4929.1  311.11  4967.9  309.35  4983.9  304.32
  4984.1  303.82  4987.9  304.32  5000.1  307.09  5032.3  307.70  5053.7  310.85
  5124.0  310.60  5208.9  308.48  5430.3  311.97  5473.6  310.66  5494.7  317.03
  5509.2  317.53  5523.7  312.77  5536.5  312.40  5544.6  313.57  5615.3  316.31
  5758.6  318.93  5773.1  320.15  5794.0  318.90  5999.0  321.32  6034.0  321.98
#Mann=8,-1,0
  4008.0   0.013       0  4048.8    0.04       0  4750.8    0.05       0
  4929.1     0.1       0  4983.9    0.05       0  4987.9     0.1       0
  5124.0    0.05       0  5999.0   0.013       0
Bank Sta=4983.9,4987.9
Exp/Cntr=0.3,0.1

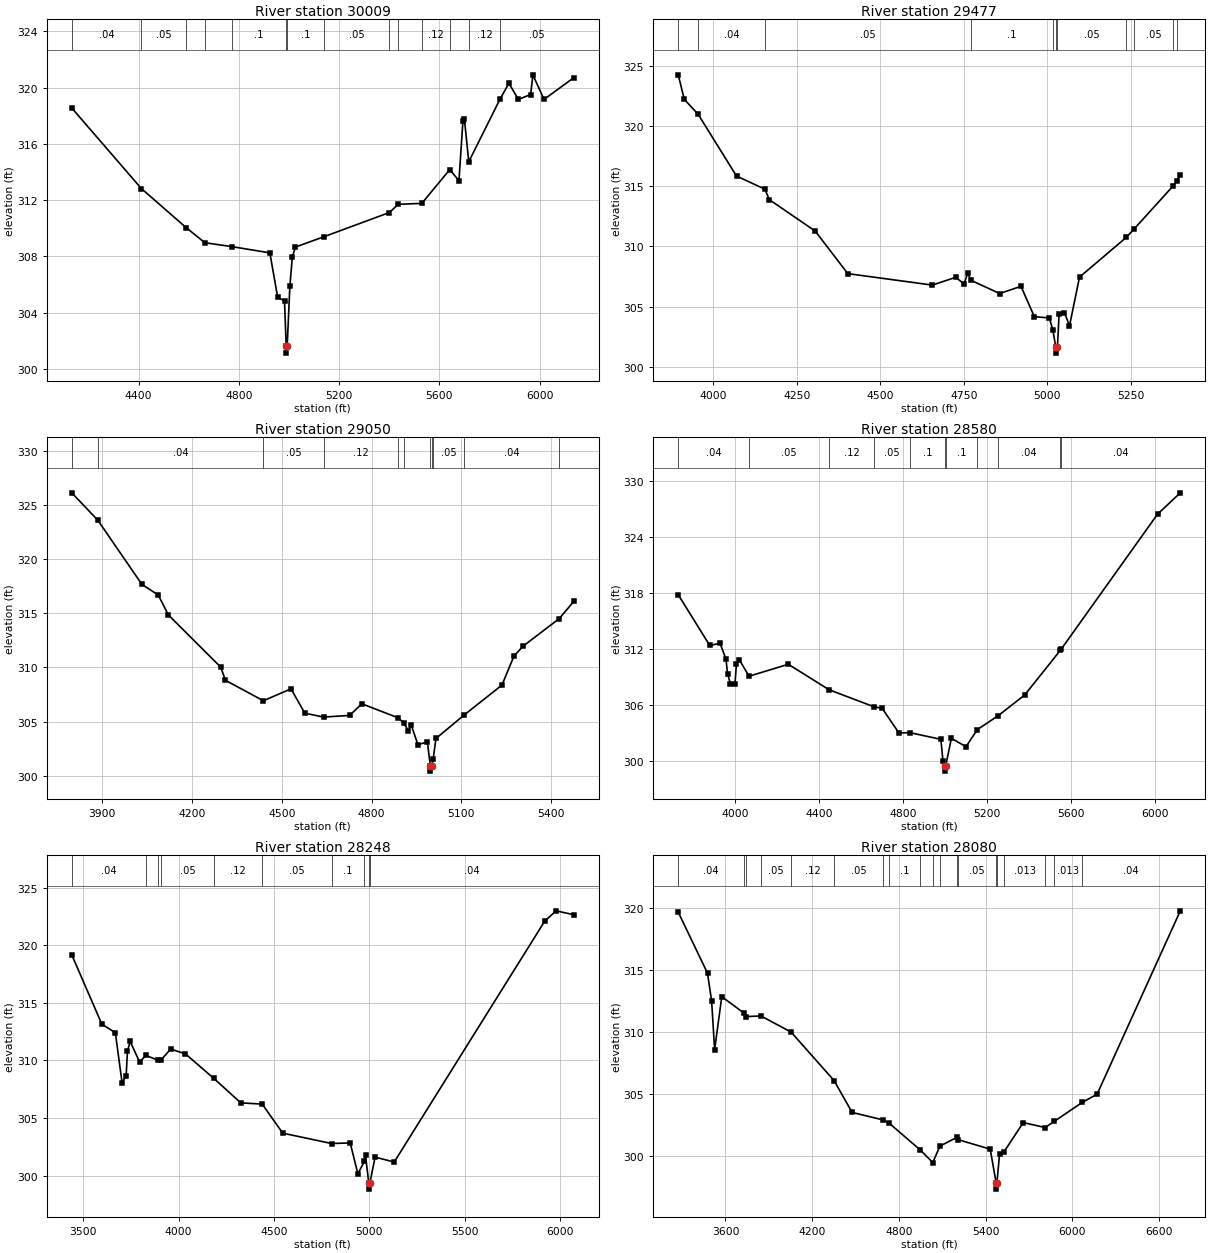
Type RM Length L Ch R = 1,30009,532,532,532
BEGIN DESCRIPTION:
SHILOH CREEK 61.0
END DESCRIPTION:
XS GIS Cut Line= 4
      2472052.05     13565081.74      2471343.72     13564901.19
      2471052.05     13565074.80      2470593.70     13565887.33
#Sta/Elev= 30
  4133.6  318.55  4411.5  312.82  4589.7  310.05  4664.9  308.97  4773.7  308.69
  4924.0  308.25  4955.2  305.08  4982.4  304.84  4989.1  301.62  4989.4  301.12
  4993.1  301.62  5003.8  305.88  5013.6  307.95  5026.0  308.66  5138.5  309.39
  5401.2  311.12  5435.6  311.70  5530.4  311.77  5641.7  314.17  5678.5  313.38
  5694.4  317.65  5700.2  317.76  5717.7  314.73  5842.3  319.18  5877.9  320.31
  5915.4  319.16  5964.5  319.51  5973.5  320.91  6018.0  319.16  6136.9  320.71
#Mann=14,-1,0
  4133.6    0.04       0  4411.5    0.05       0  4589.7    0.04       0
  4664.9    0.05       0  4773.7     0.1       0  4989.1    0.05       0
  4993.1     0.1       0  5138.5    0.05       0  5401.2    0.12       0
  5435.6    0.05       0  5530.4    0.12       0  5641.7    0.05       0
  5717.7    0.12       0  5842.3    0.05       0
Bank Sta=4989.1,4993.1
Exp/Cntr=0.3,0.1

Type RM Length L Ch R = 1,29477,427,427,427
BEGIN DESCRIPTION:
SHILOH CREEK 60.0
END DESCRIPTION:
XS GIS Cut Line= 3
      2472302.07     13564859.53      2471225.00     13564475.00
      2470925.01     13564275.01
#Sta/Elev= 30
  3894.8  324.23  3912.9  322.20  3954.4  320.96  4069.4  315.84  4154.5  314.75
  4167.8  313.88  4305.1  311.28  4402.8  307.75  4656.2  306.80  4725.7  307.44
  4751.2  306.91  4762.4  307.82  4770.6  307.21  4857.9  306.10  4921.7  306.70
  4961.5  304.19  5006.6  304.07  5017.2  303.09  5025.8  301.66  5026.2  301.16
  5030.9  301.66  5035.8  304.39  5052.0  304.52  5067.0  303.42  5097.0  307.46
  5237.4  310.76  5261.5  311.48  5377.5  315.02  5388.5  315.44  5399.0  315.96
#Mann=11,-1,0
  3894.8    0.05       0  3954.4    0.04       0  4154.5    0.05       0
  4770.6     0.1       0  5017.2    0.05       0  5025.8    0.05       0
  5030.9    0.05       0  5237.4    0.04       0  5261.5    0.05       0
  5377.5    0.12       0  5388.5    0.05       0
Bank Sta=5025.8,5030.9
Exp/Cntr=0.3,0.1

Type RM Length L Ch R = 1,29050,470,470,470
BEGIN DESCRIPTION:
SHILOH CREEK 59.0
END DESCRIPTION:
XS GIS Cut Line= 3
      2472538.20     13564651.21      2471375.00     13564125.00
      2470974.99     13564125.00
#Sta/Elev= 30
  3798.8  326.15  3885.7  323.62  4032.8  317.69  4087.5  316.70  4121.6  314.85
  4296.2  310.03  4312.0  308.81  4438.6  306.92  4530.9  308.02  4577.1  305.77
  4639.6  305.41  4726.7  305.56  4767.4  306.64  4887.9  305.35  4906.7  304.90
  4922.6  304.15  4932.8  304.65  4954.8  302.85  4986.4  303.12  4996.1  300.91
  4996.5  300.41  5001.2  300.91  5005.8  301.56  5015.0  303.43  5109.6  305.61
  5235.5  308.37  5275.5  311.05  5305.5  311.96  5426.4  314.51  5475.5  316.11
#Mann=11,-1,0
  3798.8    0.05       0  3885.7    0.04       0  4438.6    0.05       0
  4639.6    0.12       0  4887.9    0.05       0  4906.7     0.1       0
  4996.1    0.05       0  5001.2     0.1       0  5005.8    0.05       0
  5109.6    0.04       0  5426.4    0.05       0
Bank Sta=4996.1,5001.2
Exp/Cntr=0.3,0.1

Type RM Length L Ch R = 1,28580,332,332,332
BEGIN DESCRIPTION:
Mapping XS d1f186a1
END DESCRIPTION:
XS GIS Cut Line= 4
      2472496.69     13564425.65      2471841.29     13563757.23
      2471094.76     13563752.88      2470404.63     13563926.50
#Sta/Elev= 30
  3728.3  317.80  3878.5  312.36  3927.9  312.59  3956.2  310.86  3963.3  309.34
  3977.5  308.23  3998.6  308.19  4005.8  310.33  4019.9  310.81  4066.1  309.06
  4253.2  310.34  4447.5  307.61  4661.9  305.78  4700.7  305.62  4780.7  302.98
  4834.8  303.00  4980.7  302.29  4990.7  299.98  4998.2  299.38  4998.6  298.88
  5003.3  299.38  5030.7  302.40  5100.7  301.50  5154.3  303.33  5253.1  304.81
  5380.7  307.05  5549.8  311.82  5553.6  311.93  6014.0  326.44  6122.6  328.73
#Mann=11,-1,0
  3728.3    0.04       0  4066.1    0.05       0  4447.5    0.12       0
  4661.9    0.05       0  4834.8     0.1       0  4998.2    0.05       0
  5003.3     0.1       0  5154.3    0.05       0  5253.1    0.04       0
  5549.8    0.05       0  5553.6    0.04       0
Bank Sta=4998.2,5003.3
Exp/Cntr=0.3,0.1

Type RM Length L Ch R = 1,28248,168,168,168
BEGIN DESCRIPTION:
Mapping XS 85b4a4f1
END DESCRIPTION:
XS GIS Cut Line= 6
      2472564.92     13564428.15      2471837.50     13563731.03
      2471546.52     13563502.70      2471491.94     13563466.00
      2470877.75     13563514.17      2470313.53     13563618.33
#Sta/Elev= 30
  3439.6  319.16  3597.3  313.14  3668.1  312.40  3703.3  308.07  3724.7  308.64
  3731.6  310.79  3745.8  311.64  3795.5  309.85  3827.8  310.43  3890.4  310.02
  3908.1  310.04  3958.1  310.98  4035.7  310.56  4184.0  308.44  4325.9  306.31
  4438.5  306.20  4545.8  303.68  4802.1  302.78  4899.8  302.83  4939.9  300.15
  4974.1  301.23  4980.0  301.75  4997.4  299.32  4997.8  298.82  5002.7  299.32
  5030.2  301.60  5130.5  301.17  5920.1  322.09  5979.6  322.98  6072.6  322.64
#Mann=10,-1,0
  3439.6    0.04       0  3827.8    0.05       0  3890.4   0.013       0
  3908.1    0.05       0  4184.0    0.12       0  4438.5    0.05       0
  4802.1     0.1       0  4974.1    0.04       0  4997.4    0.04       0
  5002.7    0.04       0
Bank Sta=4997.4,5002.7
Exp/Cntr=0.3,0.1

Type RM Length L Ch R = 1,28080,447,447,447
BEGIN DESCRIPTION:
Mapping XS b9a4e76e
END DESCRIPTION:
XS GIS Cut Line= 4
      2472663.18     13564422.03      2471753.44     13563644.24
      2470532.37     13562707.19      2469905.49     13562320.57
#Sta/Elev= 30
  3273.5  319.70  3475.9  314.77  3504.4  312.52  3525.2  308.59  3574.6  312.87
  3728.7  311.54  3741.0  311.26  3845.8  311.31  4054.8  310.00  4351.1  306.09
  4476.1  303.51  4689.0  302.91  4732.5  302.64  4947.0  300.48  5033.9  299.46
  5083.7  300.79  5202.0  301.50  5206.8  301.32  5431.4  300.54  5472.3  297.81
  5472.7  297.31  5477.6  297.81  5495.8  300.11  5526.3  300.32  5659.8  302.69
  5811.7  302.29  5874.5  302.79  6067.5  304.32  6170.4  304.98  6746.1  319.81
#Mann=19,-1,0
  3273.5    0.04       0  3728.7    0.05       0  3741.0   0.013       0
  3845.8    0.05       0  4054.8    0.12       0  4351.1    0.05       0
  4689.0   0.013       0  4732.5     0.1       0  4947.0    0.04       0
  5033.9     0.1       0  5083.7    0.04       0  5202.0   0.013       0
  5206.8    0.05       0  5472.3    0.04       0  5477.6    0.05       0
  5526.3   0.013       0  5811.7    0.05       0  5874.5   0.013       0
  6067.5    0.04       0
Bank Sta=5472.3,5477.6
Exp/Cntr=0.3,0.1

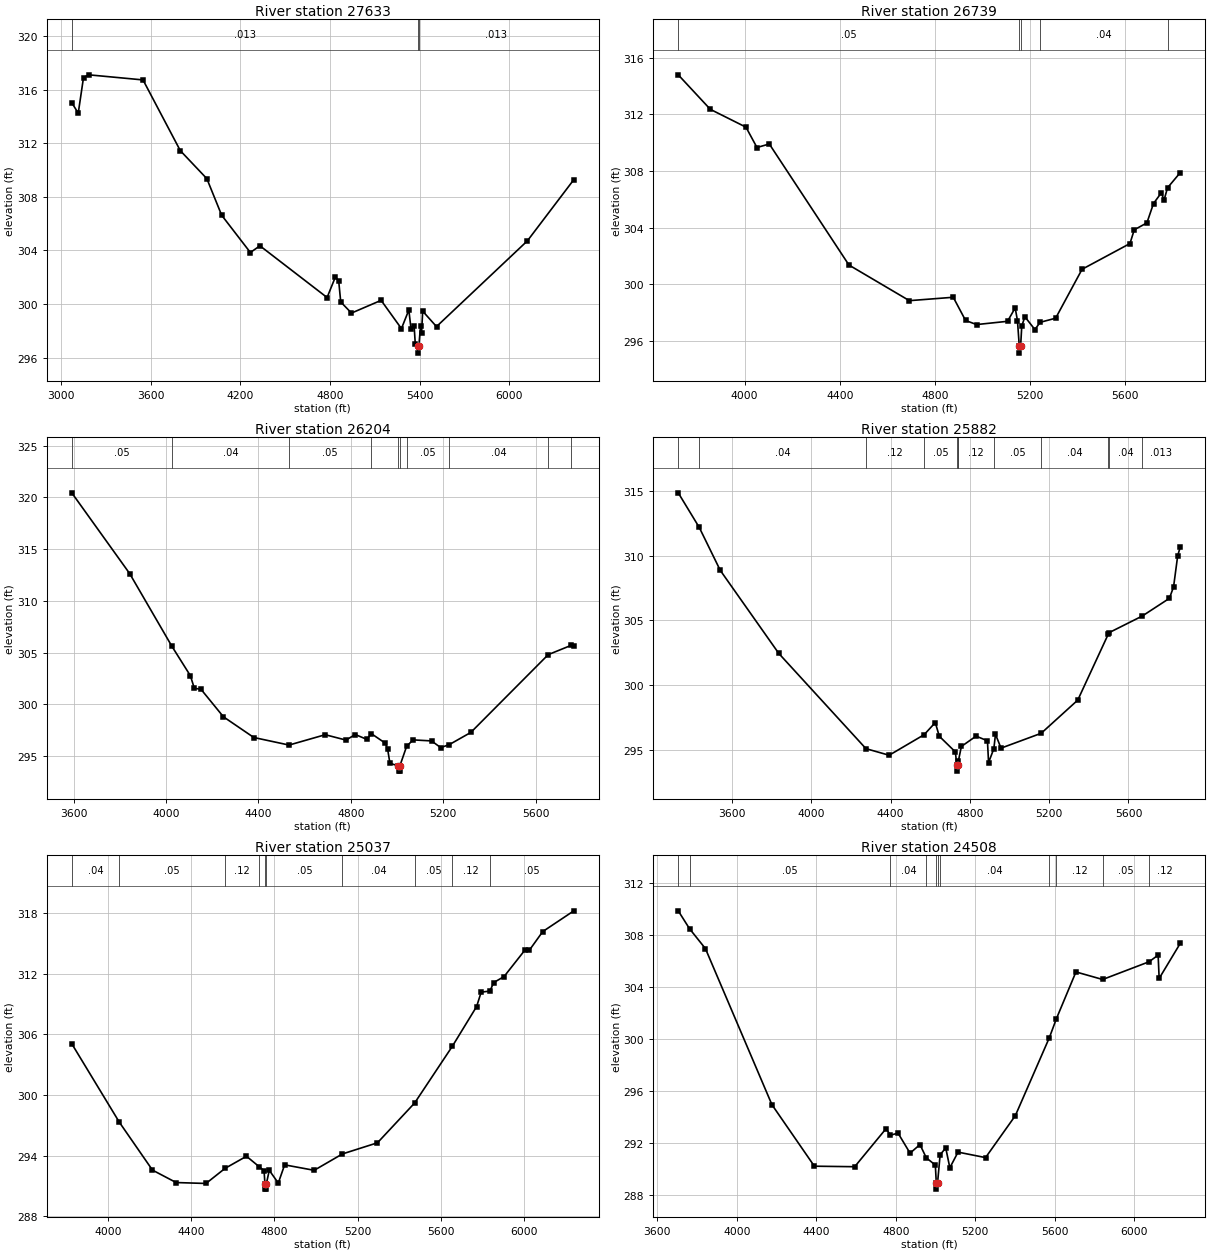
Type RM Length L Ch R = 1,27633,894,894,894
BEGIN DESCRIPTION:
Mapping XS 06148377
END DESCRIPTION:
XS GIS Cut Line= 3
      2472722.39     13564178.25      2470873.40     13562680.84
      2470083.44     13562103.56
#Sta/Elev= 30
  3072.9  315.02  3116.2  314.24  3151.4  316.90  3186.6  317.10  3549.4  316.72
  3798.8  311.44  3976.3  309.35  4075.4  306.62  4267.3  303.84  4331.2  304.34
  4780.4  300.48  4836.4  302.03  4858.2  301.70  4871.6  300.15  4943.5  299.32
  5141.7  300.27  5277.6  298.16  5327.1  299.55  5341.5  298.16  5362.3  298.37
  5370.3  297.00  5388.3  296.83  5388.8  296.33  5393.8  296.83  5405.5  298.37
  5411.9  297.82  5419.8  299.46  5512.1  298.31  6119.9  304.71  6430.6  309.28
#Mann=3,-1,0
  3072.9   0.013       0  5388.3    0.03       0  5393.8   0.013       0
Bank Sta=5388.3,5393.8
Exp/Cntr=0.3,0.1

Type RM Length L Ch R = 1,26739,535,535,535
BEGIN DESCRIPTION:
Mapping XS 80f9d969
END DESCRIPTION:
XS GIS Cut Line= 3
      2472040.98     13562776.34      2470856.04     13562242.47
      2470079.55     13562008.22
#Sta/Elev= 30
  3721.2  314.80  3856.1  312.36  4005.9  311.10  4052.2  309.66  4104.0  309.91
  4438.9  301.35  4692.9  298.83  4877.4  299.07  4929.1  297.43  4975.4  297.14
  5105.5  297.37  5137.7  298.32  5147.3  297.42  5154.9  295.62  5155.3  295.12
  5160.6  295.62  5165.4  297.04  5178.6  297.69  5220.4  296.79  5242.9  297.30
  5307.8  297.59  5418.9  301.05  5620.3  302.87  5638.2  303.84  5691.4  304.33
  5719.2  305.70  5752.2  306.46  5763.5  305.94  5778.1  306.81  5831.9  307.89
#Mann=5,-1,0
  3721.2    0.05       0  5154.9    0.05       0  5160.6    0.05       0
  5242.9    0.04       0  5778.1   0.013       0
Bank Sta=5154.9,5160.6
Exp/Cntr=0.3,0.1

Type RM Length L Ch R = 1,26204,322,322,322
BEGIN DESCRIPTION:
Mapping XS e9c5b613
END DESCRIPTION:
XS GIS Cut Line= 3
      2472010.52     13562133.94      2471216.29     13561765.04
      2469919.24     13561808.42
#Sta/Elev= 30
  3591.8  320.44  3842.3  312.64  4025.4  305.60  4105.1  302.77  4122.5  301.54
  4150.9  301.46  4248.4  298.79  4379.9  296.79  4532.5  296.06  4688.9  297.06
  4779.0  296.54  4819.0  297.08  4869.0  296.61  4888.9  297.16  4949.1  296.24
  4959.1  295.67  4969.1  294.30  5006.2  294.04  5006.7  293.54  5011.5  293.54
  5012.0  294.04  5041.5  295.94  5069.2  296.56  5149.2  296.46  5189.2  295.81
  5226.6  296.11  5319.3  297.28  5654.4  304.80  5752.9  305.69  5765.3  305.62
#Mann=10,-1,0
  3591.8    0.05       0  4025.4    0.04       0  4532.5    0.05       0
  4888.9    0.12       0  5006.2    0.05       0  5012.0    0.12       0
  5041.5    0.05       0  5226.6    0.04       0  5654.4    0.05       0
  5752.9   0.013       0
Bank Sta=5006.2,5012
Exp/Cntr=0.3,0.1

Type RM Length L Ch R = 1,25882,845,845,845
BEGIN DESCRIPTION:
Mapping XS d81f1fca
END DESCRIPTION:
XS GIS Cut Line= 4
      2472132.06     13561669.54      2471311.77     13561430.84
      2470141.16     13561612.70      2469733.98     13561890.70
#Sta/Elev= 30
  3329.4  314.88  3435.4  312.20  3541.2  308.88  3836.7  302.44  4276.1  295.07
  4393.0  294.56  4569.4  296.15  4625.7  297.09  4646.0  296.03  4726.9  294.82
  4734.1  293.83  4734.6  293.33  4739.9  293.83  4742.3  294.13  4757.3  295.24
  4831.4  296.04  4888.8  295.68  4894.4  293.99  4921.0  295.07  4929.3  296.18
  4957.3  295.11  5159.8  296.26  5344.2  298.83  5498.8  303.96  5501.8  304.05
  5669.6  305.34  5806.3  306.71  5827.3  307.59  5848.3  310.02  5861.4  310.69
#Mann=12,-1,0
  3329.4    0.05       0  3435.4    0.04       0  4276.1    0.12       0
  4569.4    0.05       0  4734.1    0.05       0  4739.9    0.05       0
  4742.3    0.12       0  4921.0    0.05       0  5159.8    0.04       0
  5498.8    0.05       0  5501.8    0.04       0  5669.6   0.013       0
Bank Sta=4734.1,4739.9
Exp/Cntr=0.3,0.1

Type RM Length L Ch R = 1,25037,529,529,529
BEGIN DESCRIPTION:
SHILOH CREEK 51.0
END DESCRIPTION:
XS GIS Cut Line= 3
      2471724.99     13561125.00      2470825.00     13560925.00
      2469354.20     13560674.63
#Sta/Elev= 30
  3825.7  305.06  4054.5  297.30  4213.7  292.57  4327.6  291.34  4471.1  291.25
  4562.5  292.74  4665.7  293.94  4727.1  292.90  4750.2  292.51  4754.5  291.19
  4755.0  290.69  4760.6  290.69  4761.1  291.19  4775.2  292.55  4818.6  291.29
  4849.1  293.09  4991.1  292.55  5127.1  294.17  5295.4  295.27  5474.4  299.21
  5655.7  304.82  5772.2  308.74  5794.0  310.16  5836.2  310.27  5854.2  311.11
  5904.0  311.70  6005.5  314.35  6024.8  314.28  6090.1  316.15  6239.6  318.20
#Mann=10,-1,0
  3825.7    0.04       0  4054.5    0.05       0  4562.5    0.12       0
  4727.1    0.05       0  4754.5    0.05       0  4761.1    0.05       0
  5127.1    0.04       0  5474.4    0.05       0  5655.7    0.12       0
  5836.2    0.05       0
Bank Sta=4754.5,4761.1
Exp/Cntr=0.3,0.1

Type RM Length L Ch R = 1,24508,576,576,576
BEGIN DESCRIPTION:
Mapping XS 3f7eb32b
END DESCRIPTION:
XS GIS Cut Line= 3
      2472036.60     13560918.68      2470799.62     13560454.27
      2469628.92     13560163.77
#Sta/Elev= 30
  3705.3  309.84  3762.0  308.47  3842.2  306.94  4177.0  294.96  4390.6  290.24
  4593.6  290.20  4751.4  293.12  4773.6  292.62  4811.8  292.78  4872.3  291.24
  4922.2  291.90  4954.1  290.88  4999.5  290.33  5004.3  288.98  5004.8  288.48
  5010.9  288.98  5023.7  291.12  5052.0  291.64  5072.6  290.12  5113.8  291.32
  5252.4  290.90  5402.3  294.12  5573.4  300.10  5609.3  301.57  5707.4  305.15
  5841.8  304.57  6075.5  305.93  6121.1  306.44  6126.3  304.65  6232.8  307.35
#Mann=11,-1,0
  3705.3    0.04       0  3762.0    0.05       0  4773.6    0.04       0
  4954.1    0.05       0  5004.3    0.05       0  5010.9    0.05       0
  5023.7    0.04       0  5573.4    0.05       0  5609.3    0.12       0
  5841.8    0.05       0  6075.5    0.12       0
Bank Sta=5004.3,5010.9
Exp/Cntr=0.3,0.1

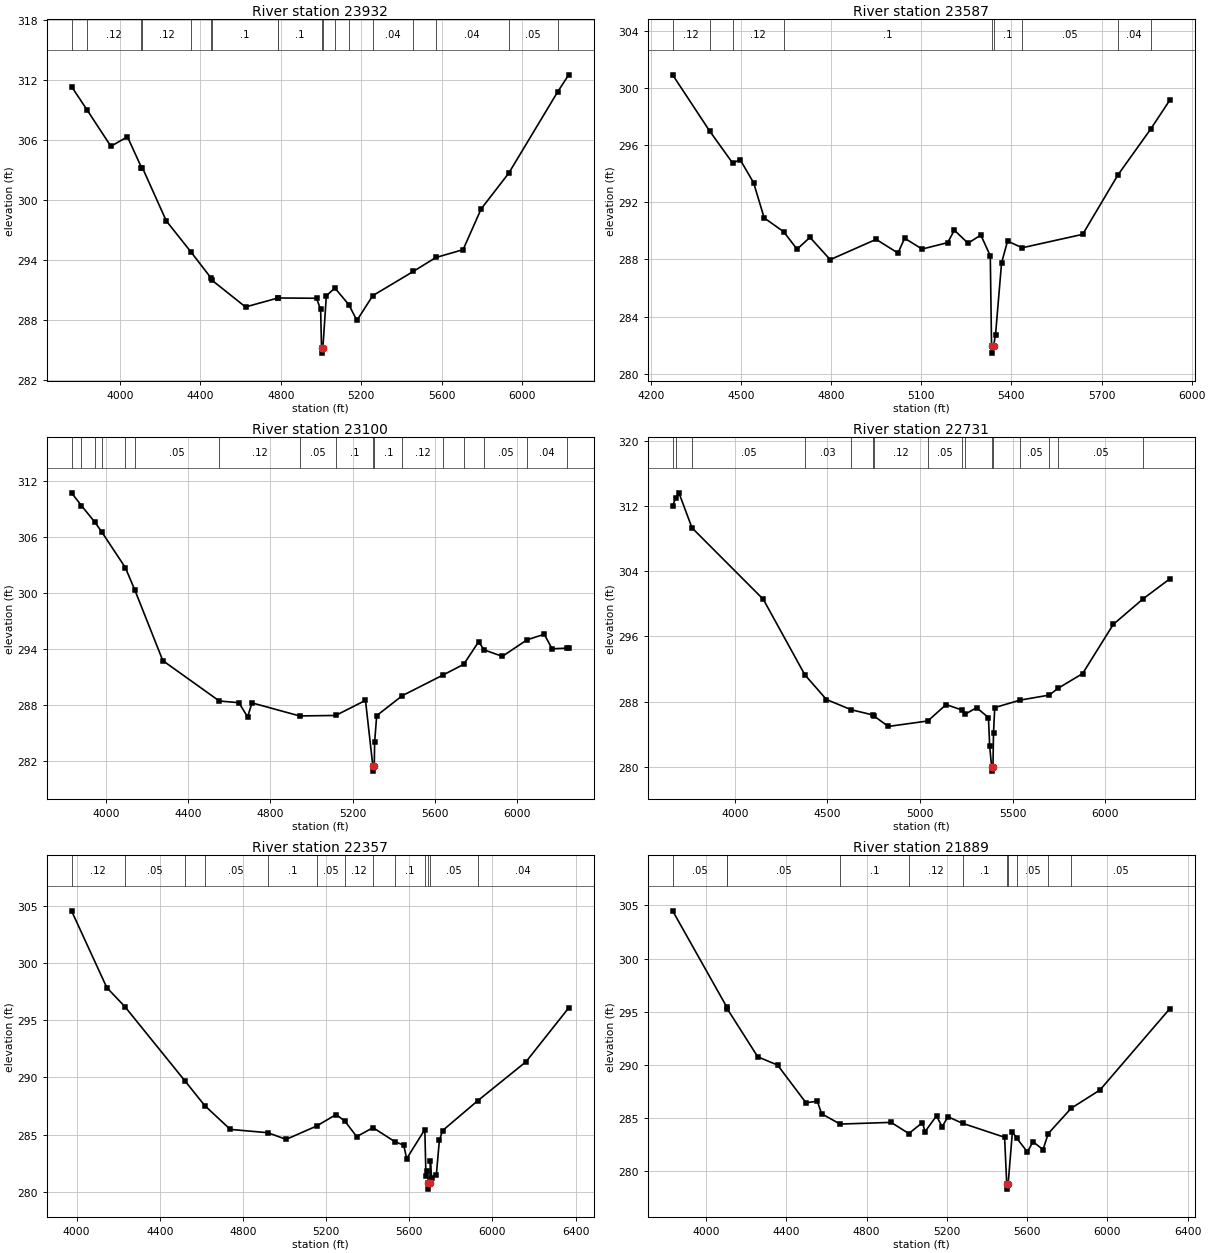
Type RM Length L Ch R = 1,23932,345,345,345
BEGIN DESCRIPTION:
SHILOH CREEK 49.0
END DESCRIPTION:
XS GIS Cut Line= 3
      2472224.98     13560325.00      2471025.00     13560025.00
      2469825.04     13559725.01
#Sta/Elev= 30
  3758.4  311.35  3834.6  309.04  3954.2  305.37  4036.7  306.32  4106.5  303.24
  4110.9  303.23  4230.0  297.90  4351.3  294.83  4452.0  292.20  4458.2  291.95
  4624.2  289.29  4784.1  290.18  4784.6  290.19  4977.3  290.16  4997.9  289.05
  5002.3  285.17  5002.8  284.67  5008.9  285.17  5026.2  290.40  5068.5  291.19
  5138.0  289.52  5178.3  287.94  5257.2  290.42  5458.5  292.84  5571.1  294.24
  5706.5  295.02  5796.7  299.11  5933.8  302.68  6177.6  310.83  6232.2  312.52
#Mann=18,-1,0
  3758.4    0.05       0  3834.6    0.12       0  4106.5    0.05       0
  4110.9    0.12       0  4351.3     0.1       0  4452.0    0.05       0
  4458.2     0.1       0  4784.1    0.05       0  4784.6     0.1       0
  5002.3    0.05       0  5008.9     0.1       0  5068.5    0.05       0
  5138.0     0.1       0  5257.2    0.04       0  5458.5    0.05       0
  5571.1    0.04       0  5933.8    0.05       0  6177.6    0.12       0
Bank Sta=5002.3,5008.9
Exp/Cntr=0.3,0.1

Type RM Length L Ch R = 1,23587,487,487,487
BEGIN DESCRIPTION:
SHILOH CREEK 48.0
END DESCRIPTION:
XS GIS Cut Line= 3
      2471824.98     13560124.99      2470925.00     13559575.00
      2470325.02     13559575.00
#Sta/Elev= 30
  4272.6  300.91  4396.1  296.97  4472.6  294.73  4497.1  294.98  4542.1  293.36
  4577.3  290.90  4642.3  289.93  4686.7  288.71  4729.6  289.54  4797.0  287.98
  4949.9  289.40  5022.6  288.44  5044.7  289.48  5102.8  288.72  5188.0  289.17
  5210.1  290.04  5255.7  289.13  5298.3  289.70  5329.8  288.25  5334.0  281.94
  5334.5  281.44  5340.6  281.94  5347.3  282.74  5367.3  287.75  5387.3  289.28
  5435.9  288.81  5637.3  289.75  5754.4  293.90  5863.8  297.12  5927.3  299.14
#Mann=9,-1,0
  4272.6    0.12       0  4396.1    0.05       0  4472.6    0.12       0
  4642.3     0.1       0  5334.0    0.05       0  5340.6     0.1       0
  5435.9    0.05       0  5754.4    0.04       0  5863.8    0.05       0
Bank Sta=5334,5340.6
Exp/Cntr=0.3,0.1

Type RM Length L Ch R = 1,23100,369,369,369
BEGIN DESCRIPTION:
Mapping XS 0ffebdd1
END DESCRIPTION:
XS GIS Cut Line= 3
      2472275.35     13559937.80      2471055.70     13559165.21
      2470098.25     13558974.59
#Sta/Elev= 30
  3831.7  310.77  3880.2  309.39  3946.1  307.60  3979.3  306.56  4093.6  302.75
  4139.0  300.39  4276.1  292.77  4551.1  288.44  4646.4  288.26  4688.8  286.73
  4710.0  288.24  4941.8  286.84  5117.4  286.89  5262.5  288.51  5298.6  281.42
  5299.1  280.92  5305.2  281.42  5307.0  284.03  5317.0  286.87  5441.5  289.01
  5641.0  291.24  5740.7  292.38  5812.9  294.79  5840.4  293.92  5928.7  293.23
  6048.6  295.00  6132.7  295.60  6170.6  294.04  6241.3  294.11  6251.7  294.12
#Mann=17,-1,0
  3831.7    0.05       0  3880.2    0.12       0  3946.1    0.05       0
  3979.3    0.12       0  4093.6    0.03       0  4139.0    0.05       0
  4551.1    0.12       0  4941.8    0.05       0  5117.4     0.1       0
  5298.6    0.05       0  5305.2     0.1       0  5441.5    0.12       0
  5641.0    0.05       0  5740.7    0.12       0  5840.4    0.05       0
  6048.6    0.04       0  6241.3    0.05       0
Bank Sta=5298.6,5305.2
Exp/Cntr=0.3,0.1

Type RM Length L Ch R = 1,22731,374,374,374
BEGIN DESCRIPTION:
Mapping XS c65fde79
END DESCRIPTION:
XS GIS Cut Line= 3
      2472527.06     13559850.98      2471168.54     13558761.57
      2470244.03     13558566.24
#Sta/Elev= 30
  3663.5  312.01  3679.4  312.95  3697.6  313.61  3768.0  309.32  4153.2  300.56
  4377.9  291.30  4494.6  288.27  4627.9  287.02  4748.1  286.36  4751.2  286.25
  4829.1  284.97  5042.5  285.64  5141.1  287.65  5225.8  286.99  5244.2  286.47
  5306.0  287.27  5370.0  286.05  5376.4  282.57  5387.2  279.99  5387.7  279.49
  5394.3  279.99  5397.2  284.19  5403.9  287.28  5541.4  288.20  5697.9  288.81
  5745.8  289.64  5878.7  291.45  6044.3  297.48  6205.8  300.62  6349.8  303.06
#Mann=16,-1,0
  3663.5    0.05       0  3679.4    0.12       0  3768.0    0.05       0
  4377.9    0.03       0  4627.9    0.12       0  4748.1    0.05       0
  4751.2    0.12       0  5042.5    0.05       0  5225.8    0.12       0
  5244.2     0.1       0  5387.2    0.05       0  5394.3     0.1       0
  5541.4    0.05       0  5697.9    0.12       0  5745.8    0.05       0
  6205.8    0.04       0
Bank Sta=5387.2,5394.3
Exp/Cntr=0.3,0.1

Type RM Length L Ch R = 1,22357,468,468,468
BEGIN DESCRIPTION:
SHILOH CREEK 45.0
END DESCRIPTION:
XS GIS Cut Line= 3
      2472524.99     13559574.99      2471325.00     13558375.00
      2470724.97     13558024.98
#Sta/Elev= 30
  3975.2  304.56  4144.9  297.85  4231.7  296.19  4521.6  289.68  4616.0  287.54
  4738.9  285.46  4919.0  285.17  5007.6  284.59  5155.0  285.76  5248.0  286.76
  5290.2  286.18  5347.0  284.83  5425.5  285.61  5530.4  284.39  5573.2  284.08
  5587.4  282.90  5674.7  285.45  5680.1  281.37  5685.9  281.85  5691.8  280.74
  5692.3  280.24  5698.9  280.74  5701.6  282.66  5707.4  281.25  5730.1  281.48
  5744.6  284.50  5760.3  285.36  5928.9  287.96  6161.4  291.37  6366.9  296.08
#Mann=13,-1,0
  3975.2    0.12       0  4231.7    0.05       0  4521.6    0.03       0
  4616.0    0.05       0  4919.0     0.1       0  5155.0    0.05       0
  5290.2    0.12       0  5425.5    0.05       0  5530.4     0.1       0
  5674.7    0.05       0  5691.8    0.05       0  5698.9    0.05       0
  5928.9    0.04       0
Bank Sta=5691.8,5698.9
Exp/Cntr=0.3,0.1

Type RM Length L Ch R = 1,21889,535,535,535
BEGIN DESCRIPTION:
SHILOH CREEK 44.0
END DESCRIPTION:
XS GIS Cut Line= 3
      2472824.98     13559274.98      2471625.00     13558075.00
      2471024.97     13557574.97
#Sta/Elev= 30
  3832.9  304.48  4101.5  295.49  4106.1  295.25  4257.1  290.77  4356.1  289.99
  4497.6  286.45  4554.1  286.60  4575.3  285.42  4667.7  284.45  4921.8  284.61
  5010.1  283.56  5077.4  284.58  5091.5  283.75  5148.1  285.22  5176.4  284.19
  5204.7  285.14  5278.3  284.52  5487.5  283.21  5498.1  278.84  5498.6  278.34
  5505.2  278.84  5526.4  283.72  5547.3  283.14  5600.9  281.84  5629.5  282.79
  5679.0  282.05  5705.1  283.56  5819.7  285.94  5962.8  287.65  6311.0  295.29
#Mann=11,-1,0
  3832.9    0.05       0  4101.5    0.12       0  4106.1    0.05       0
  4667.7     0.1       0  5010.1    0.12       0  5278.3     0.1       0
  5498.1    0.05       0  5505.2     0.1       0  5547.3    0.05       0
  5705.1    0.12       0  5819.7    0.05       0
Bank Sta=5498.1,5505.2
Exp/Cntr=0.3,0.1