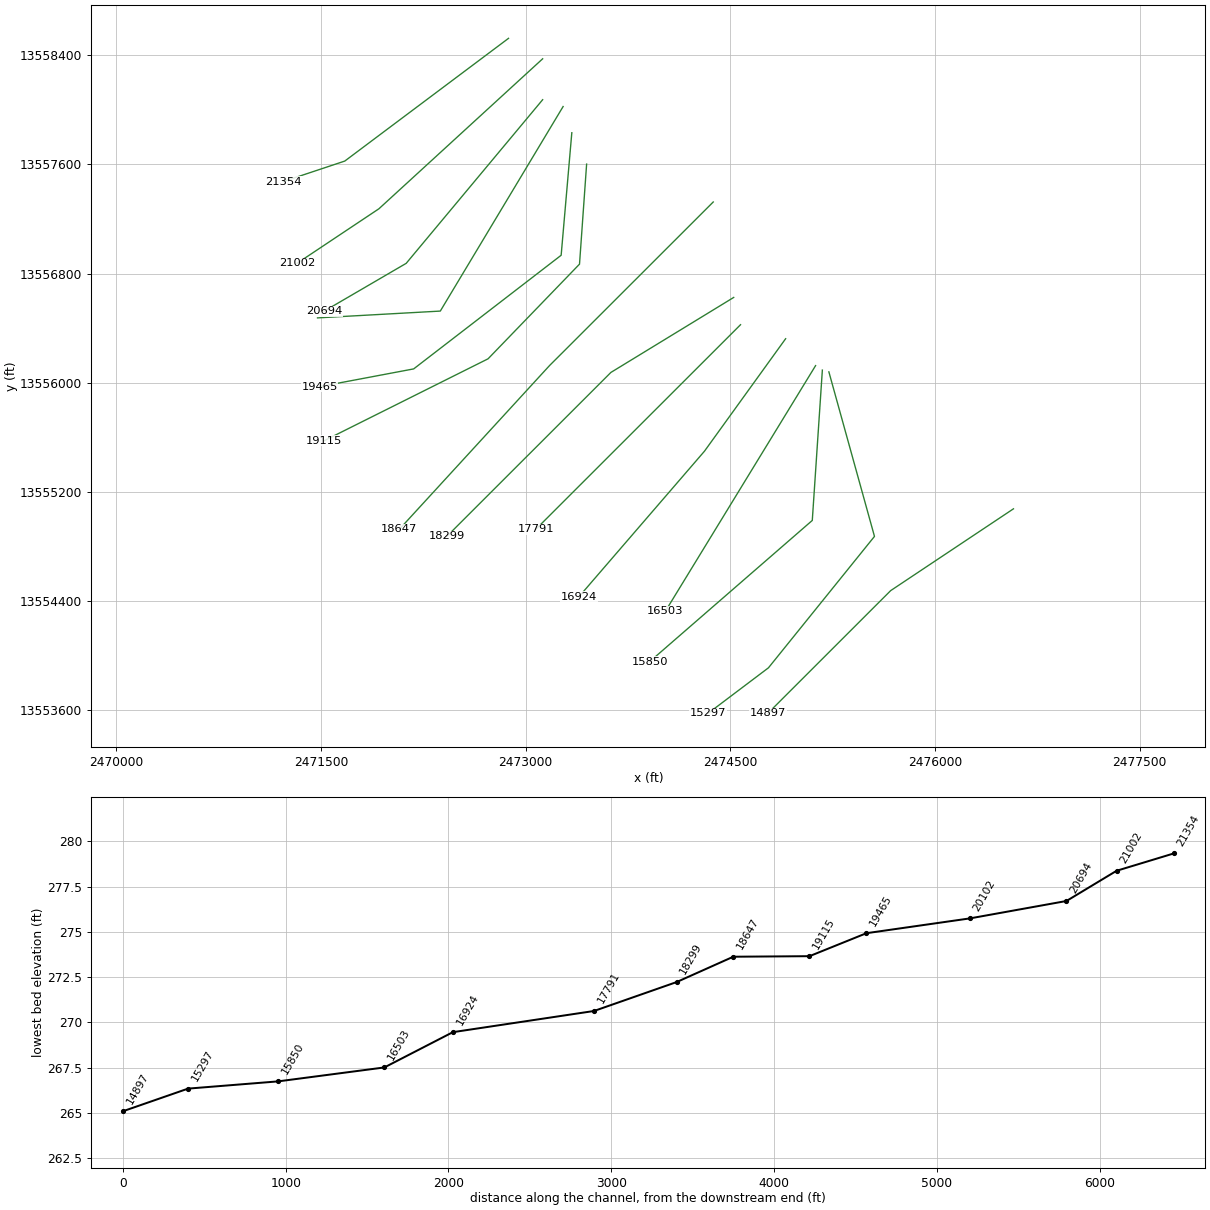
HEC-RAS study SHILOH CREEK.prj: SHILOH CREEK Base Level Engineering

--- SHILOH CREEK.g01 (geometry) --- (continued)

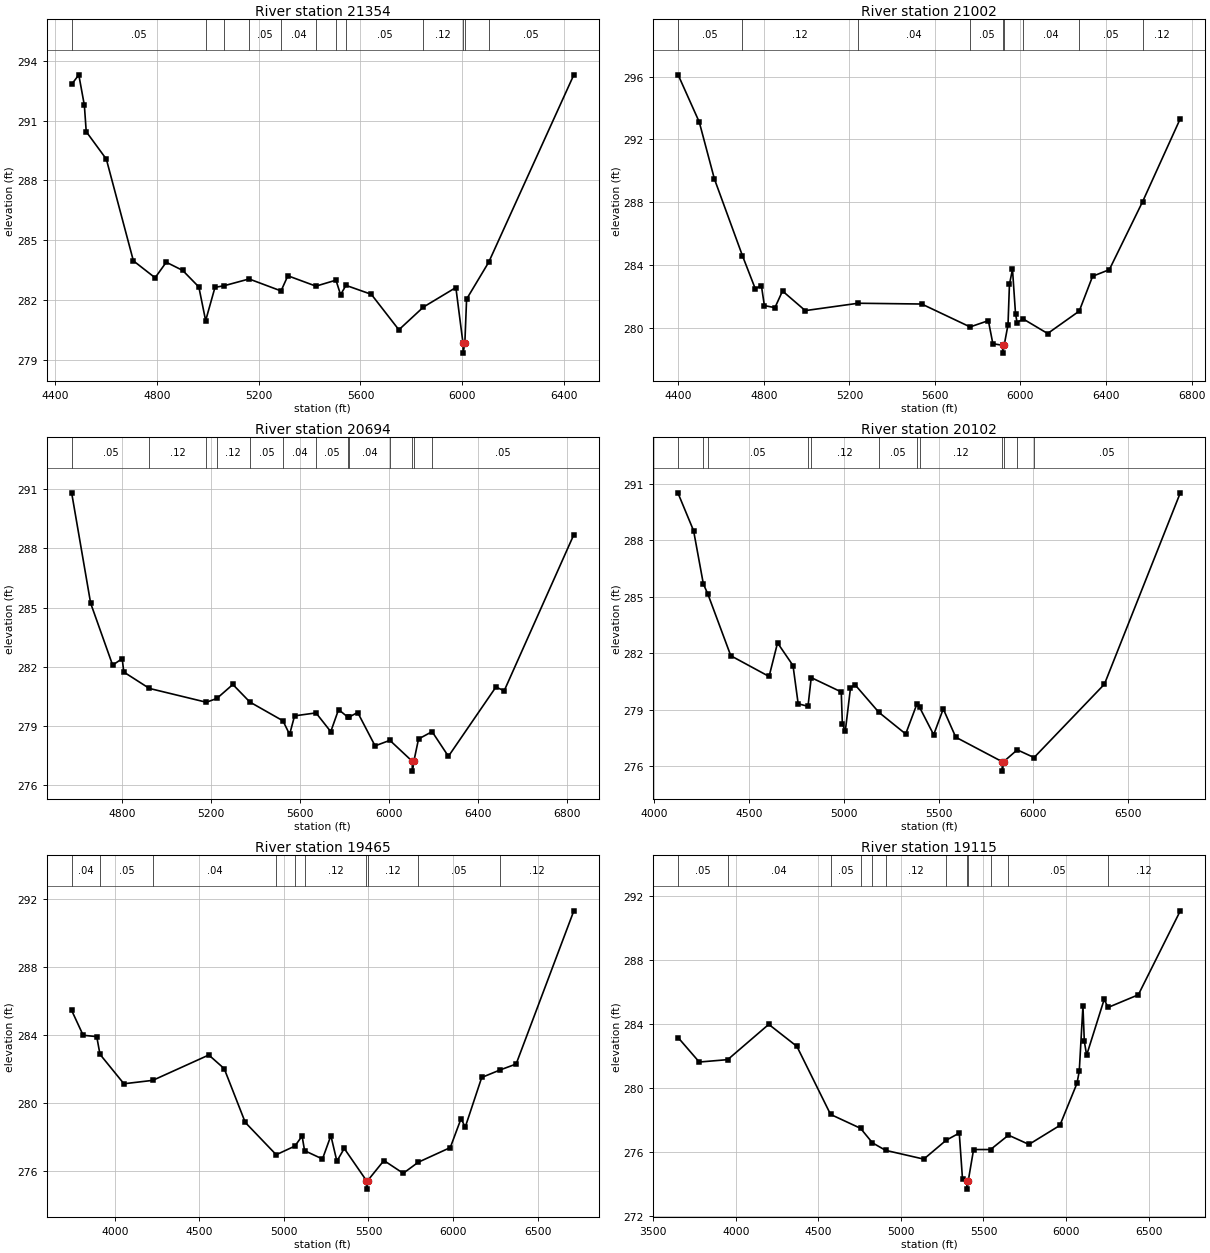
Type RM Length L Ch R = 1,21354,352,352,352
BEGIN DESCRIPTION:
SHILOH CREEK 43.0
END DESCRIPTION:
XS GIS Cut Line= 3
      2472874.98     13558524.99      2471675.00     13557625.00
      2471225.02     13557475.01
#Sta/Elev= 30
  4464.6  292.82  4492.7  293.30  4514.6  291.77  4521.9  290.45  4601.0  289.07
  4707.3  283.97  4792.7  283.12  4836.5  283.90  4901.0  283.49  4964.6  282.66
  4991.4  280.97  5028.1  282.64  5063.9  282.72  5162.2  283.06  5287.8  282.46
  5314.6  283.22  5425.0  282.70  5503.7  283.00  5521.9  282.27  5542.9  282.74
  5642.7  282.29  5751.0  280.51  5847.5  281.65  5975.1  282.63  6003.1  279.84
  6003.6  279.34  6010.4  279.84  6017.3  282.05  6104.2  283.90  6438.9  293.30
#Mann=12,-1,0
  4464.6    0.05       0  4991.4    0.04       0  5063.9    0.12       0
  5162.2    0.05       0  5287.8    0.04       0  5425.0    0.05       0
  5503.7    0.04       0  5542.9    0.05       0  5847.5    0.12       0
  6003.1    0.04       0  6010.4    0.12       0  6104.2    0.05       0
Bank Sta=6003.1,6010.4
Exp/Cntr=0.3,0.1

Type RM Length L Ch R = 1,21002,308,308,308
BEGIN DESCRIPTION:
SHILOH CREEK 42.0
END DESCRIPTION:
XS GIS Cut Line= 3
      2473124.98     13558374.98      2471925.00     13557275.00
      2471324.97     13556874.98
#Sta/Elev= 30
  4398.6  296.12  4497.5  293.11  4568.4  289.48  4699.2  284.60  4759.6  282.48
  4788.0  282.69  4802.1  281.41  4851.5  281.28  4886.9  282.34  4993.3  281.09
  5240.9  281.56  5538.1  281.51  5764.4  280.05  5849.8  280.45  5870.8  278.98
  5916.4  278.88  5916.9  278.38  5923.7  278.88  5941.7  280.19  5948.4  282.76
  5962.6  283.73  5976.8  280.89  5984.2  280.33  6012.4  280.56  6127.1  279.63
  6274.9  281.06  6337.4  283.28  6415.6  283.70  6571.4  288.04  6747.6  293.33
#Mann=9,-1,0
  4398.6    0.05       0  4699.2    0.12       0  5240.9    0.04       0
  5764.4    0.05       0  5916.4    0.05       0  5923.7    0.05       0
  6012.4    0.04       0  6274.9    0.05       0  6571.4    0.12       0
Bank Sta=5916.4,5923.7
Exp/Cntr=0.3,0.1

Type RM Length L Ch R = 1,20694,592,592,592
BEGIN DESCRIPTION:
SHILOH CREEK 41.0
END DESCRIPTION:
XS GIS Cut Line= 3
      2473125.00     13558075.00      2472125.00     13556875.00
      2471524.97     13556524.99
#Sta/Elev= 30
  4574.9  290.81  4660.2  285.22  4759.1  282.08  4802.0  282.41  4809.2  281.73
  4924.1  280.90  5180.1  280.20  5227.2  280.39  5299.3  281.10  5375.8  280.21
  5524.3  279.26  5554.4  278.57  5576.6  279.51  5672.9  279.66  5739.3  278.71
  5774.4  279.83  5816.5  279.44  5821.4  279.45  5860.3  279.68  5938.4  277.99
  6004.9  278.27  6105.3  277.21  6105.8  276.71  6112.7  277.21  6133.7  278.34
  6194.7  278.71  6268.0  277.46  6481.4  280.97  6518.6  280.78  6831.6  288.69
#Mann=13,-1,0
  4574.9    0.05       0  4924.1    0.12       0  5180.1    0.05       0
  5227.2    0.12       0  5375.8    0.05       0  5524.3    0.04       0
  5672.9    0.05       0  5816.5    0.12       0  5821.4    0.04       0
  6004.9    0.12       0  6105.3    0.05       0  6112.7    0.12       0
  6194.7    0.05       0
Bank Sta=6105.3,6112.7
Exp/Cntr=0.3,0.1

Type RM Length L Ch R = 1,20102,637,637,637
BEGIN DESCRIPTION:
SHILOH CREEK 40.0
END DESCRIPTION:
XS GIS Cut Line= 3
      2473275.01     13558025.02      2472375.00     13556525.00
      2471475.00     13556475.00
#Sta/Elev= 30
  4125.3  290.48  4207.0  288.50  4258.5  285.68  4282.7  285.13  4403.3  281.87
  4605.4  280.77  4650.1  282.55  4731.7  281.35  4759.0  279.32  4810.9  279.19
  4827.9  280.71  4986.4  279.95  4992.2  278.26  5007.7  277.87  5035.0  280.15
  5058.3  280.34  5184.7  278.87  5326.5  277.72  5385.0  279.29  5399.6  279.14
  5474.2  277.68  5524.8  279.05  5590.8  277.55  5835.9  276.25  5836.4  275.75
  5843.3  276.25  5915.4  276.88  6004.1  276.47  6375.4  280.36  6776.0  290.51
#Mann=12,-1,0
  4125.3    0.05       0  4258.5    0.04       0  4282.7    0.05       0
  4810.9    0.04       0  4827.9    0.12       0  5184.7    0.05       0
  5385.0    0.04       0  5399.6    0.12       0  5835.9    0.05       0
  5843.3    0.12       0  5915.4     0.1       0  6004.1    0.05       0
Bank Sta=5835.9,5843.3
Exp/Cntr=0.3,0.1

Type RM Length L Ch R = 1,19465,350,350,350
BEGIN DESCRIPTION:
Mapping XS 1d3898c4
END DESCRIPTION:
XS GIS Cut Line= 4
      2473338.68     13557832.74      2473260.56     13556934.31
      2472179.83     13556100.98      2471489.83     13555970.79
#Sta/Elev= 30
  3745.5  285.43  3813.5  283.97  3893.8  283.89  3913.0  282.85  4054.4  281.12
  4224.9  281.32  4556.3  282.81  4647.3  282.01  4771.7  278.85  4954.8  276.95
  5065.3  277.46  5107.8  278.05  5122.4  277.19  5228.2  276.70  5278.0  278.07
  5313.4  276.57  5356.9  277.32  5488.1  275.43  5488.6  274.93  5495.5  275.43
  5591.5  276.61  5705.6  275.86  5794.5  276.51  5983.7  277.37  6047.5  279.07
  6072.1  278.57  6169.6  281.49  6277.8  281.93  6373.1  282.28  6714.2  291.28
#Mann=10,-1,0
  3745.5    0.04       0  3913.0    0.05       0  4224.9    0.04       0
  4954.8    0.12       0  5065.3    0.05       0  5122.4    0.12       0
  5488.1    0.05       0  5495.5    0.12       0  5794.5    0.05       0
  6277.8    0.12       0
Bank Sta=5488.1,5495.5
Exp/Cntr=0.3,0.1

Type RM Length L Ch R = 1,19115,468,468,468
BEGIN DESCRIPTION:
SHILOH CREEK 39.0
END DESCRIPTION:
XS GIS Cut Line= 4
      2473447.19     13557602.72      2473395.11     13556869.20
      2472725.00     13556175.00      2471524.97     13555574.98
#Sta/Elev= 30
  3650.5  283.15  3778.5  281.62  3950.9  281.77  4199.6  283.98  4370.0  282.60
  4573.9  278.34  4755.3  277.47  4827.5  276.56  4907.1  276.09  5138.6  275.54
  5273.9  276.72  5353.5  277.17  5373.1  274.29  5400.1  274.16  5400.6  273.66
  5407.6  274.16  5440.2  276.14  5543.1  276.14  5651.5  277.04  5775.6  276.46
  5962.8  277.65  6066.3  280.28  6080.2  281.03  6102.6  285.12  6111.0  282.92
  6125.0  282.05  6231.2  285.54  6255.0  285.04  6438.0  285.83  6692.4  291.09
#Mann=12,-1,0
  3650.5    0.05       0  3950.9    0.04       0  4573.9    0.05       0
  4755.3    0.04       0  4827.5    0.05       0  4907.1    0.12       0
  5273.9     0.1       0  5400.1    0.05       0  5407.6     0.1       0
  5543.1    0.12       0  5651.5    0.05       0  6255.0    0.12       0
Bank Sta=5400.1,5407.6
Exp/Cntr=0.3,0.1

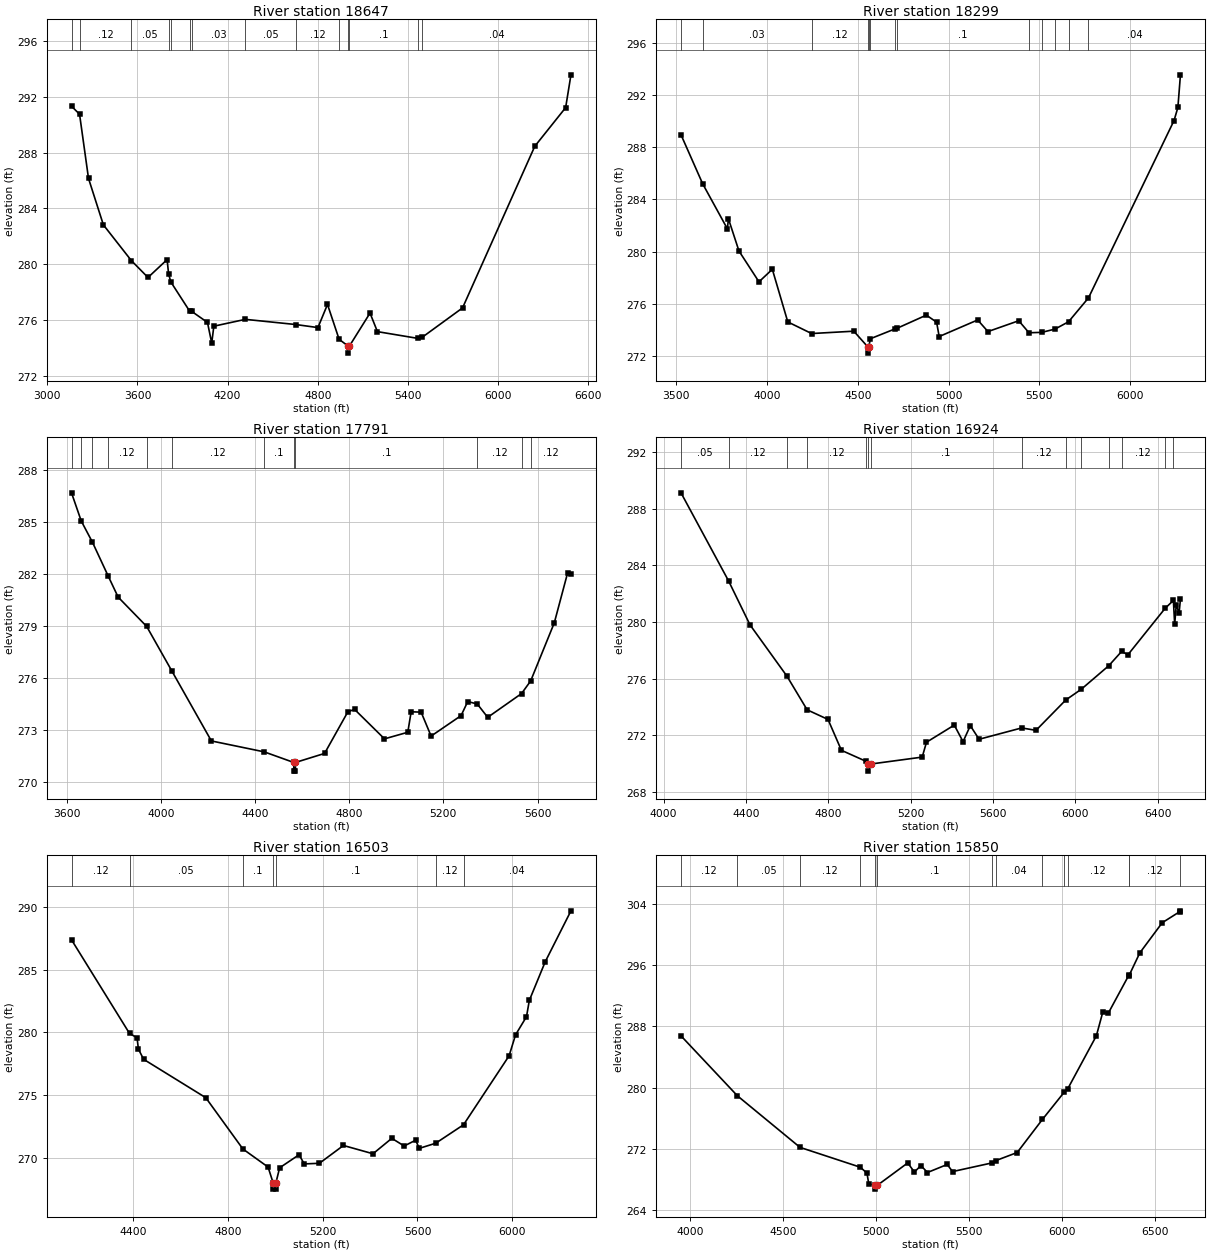
Type RM Length L Ch R = 1,18647,348,348,348
BEGIN DESCRIPTION:
SHILOH CREEK 38.0
END DESCRIPTION:
XS GIS Cut Line= 3
      2474374.99     13557324.99      2473175.00     13556125.00
      2472075.01     13554925.01
#Sta/Elev= 30
  3161.1  291.32  3214.6  290.75  3274.2  286.15  3373.2  282.82  3559.5  280.26
  3670.2  279.05  3797.5  280.33  3807.3  279.32  3821.7  278.74  3946.8  276.65
  3960.0  276.63  4066.2  275.83  4094.5  274.35  4108.6  275.56  4318.6  276.05
  4653.3  275.68  4801.6  275.46  4865.2  277.12  4942.6  274.62  5003.3  274.13
  5003.8  273.63  5010.8  274.13  5148.3  276.50  5197.6  275.17  5470.2  274.68
  5496.3  274.77  5764.3  276.87  6245.2  288.45  6450.6  291.22  6486.0  293.57
#Mann=14,-1,0
  3161.1    0.05       0  3214.6    0.12       0  3559.5    0.05       0
  3807.3    0.12       0  3821.7    0.05       0  3946.8    0.12       0
  3960.0    0.03       0  4318.6    0.05       0  4653.3    0.12       0
  4942.6     0.1       0  5003.3    0.05       0  5010.8     0.1       0
  5470.2    0.12       0  5496.3    0.04       0
Bank Sta=5003.3,5010.8
Exp/Cntr=0.3,0.1

Type RM Length L Ch R = 1,18299,508,508,508
BEGIN DESCRIPTION:
SHILOH CREEK 37.0
END DESCRIPTION:
XS GIS Cut Line= 3
      2474525.02     13556625.01      2473625.00     13556075.00
      2472425.02     13554875.02
#Sta/Elev= 30
  3525.8  288.95  3645.1  285.20  3781.3  281.75  3787.1  282.52  3845.2  280.05
  3955.4  277.69  4029.0  278.65  4114.2  274.62  4245.4  273.73  4478.0  273.91
  4553.6  272.73  4554.1  272.23  4561.1  272.73  4568.9  273.33  4705.7  274.09
  4717.4  274.14  4877.6  275.14  4934.1  274.60  4948.3  273.50  5160.4  274.77
  5217.0  273.88  5386.7  274.71  5443.0  273.79  5513.3  273.82  5586.4  274.07
  5660.9  274.63  5770.9  276.46  6242.3  290.04  6263.5  291.04  6277.6  293.54
#Mann=13,-1,0
  3525.8    0.05       0  3645.1    0.03       0  4245.4    0.12       0
  4553.6    0.05       0  4561.1    0.12       0  4568.9    0.05       0
  4705.7    0.12       0  4717.4     0.1       0  5443.0    0.12       0
  5513.3    0.05       0  5586.4    0.04       0  5660.9    0.05       0
  5770.9    0.04       0
Bank Sta=4553.6,4561.1
Exp/Cntr=0.3,0.1

Type RM Length L Ch R = 1,17791,867,867,867
BEGIN DESCRIPTION:
SHILOH CREEK 36.0
END DESCRIPTION:
XS GIS Cut Line= 3
      2474574.99     13556424.99      2473975.00     13555825.00
      2473075.00     13554925.00
#Sta/Elev= 30
  3620.6  286.67  3661.8  285.05  3709.6  283.82  3775.8  281.89  3818.6  280.66
  3939.8  278.97  4046.0  276.42  4214.6  272.37  4439.1  271.74  4564.4  271.13
  4564.9  270.63  4571.4  270.63  4571.9  271.13  4695.4  271.65  4794.4  274.05
  4822.7  274.19  4949.9  272.49  5048.9  272.87  5063.1  274.05  5105.5  274.03
  5147.9  272.65  5275.2  273.83  5303.5  274.64  5344.0  274.50  5388.3  273.73
  5532.0  275.10  5570.9  275.83  5671.2  279.18  5727.8  282.06  5741.9  282.00
#Mann=12,-1,0
  3620.6    0.03       0  3661.8    0.05       0  3709.6    0.03       0
  3775.8    0.12       0  3939.8    0.03       0  4046.0    0.12       0
  4439.1     0.1       0  4564.4    0.05       0  4571.9     0.1       0
  5344.0    0.12       0  5532.0     0.1       0  5570.9    0.12       0
Bank Sta=4564.4,4571.9
Exp/Cntr=0.3,0.1

Type RM Length L Ch R = 1,16924,421,421,421
BEGIN DESCRIPTION:
Mapping XS a6d86c2a
END DESCRIPTION:
XS GIS Cut Line= 3
      2474905.55     13556322.36      2474310.90     13555497.68
      2473390.77     13554429.97
#Sta/Elev= 30
  4084.7  289.11  4316.2  282.88  4419.8  279.79  4599.6  276.16  4697.4  273.79
  4798.9  273.11  4863.9  270.93  4982.5  270.16  4994.4  269.96  4994.9  269.46
  5005.8  269.96  5256.4  270.45  5277.2  271.50  5412.2  272.71  5454.9  271.54
  5490.1  272.67  5532.8  271.71  5739.6  272.51  5809.3  272.34  5953.7  274.48
  6029.1  275.24  6162.5  276.90  6225.1  277.91  6255.9  277.68  6436.2  280.95
  6476.6  281.51  6482.9  279.82  6490.6  281.22  6504.3  280.62  6510.9  281.61
#Mann=14,-1,0
  4084.7    0.05       0  4316.2    0.12       0  4599.6    0.05       0
  4697.4    0.12       0  4982.5     0.1       0  4994.4    0.05       0
  5005.8     0.1       0  5739.6    0.12       0  5953.7     0.1       0
  6029.1    0.12       0  6162.5    0.05       0  6225.1    0.12       0
  6436.2     0.1       0  6476.6    0.12       0
Bank Sta=4994.4,5005.8
Exp/Cntr=0.3,0.1

Type RM Length L Ch R = 1,16503,653,653,653
BEGIN DESCRIPTION:
SHILOH CREEK 34.0
END DESCRIPTION:
XS GIS Cut Line= 3
      2475125.01     13556125.02      2474575.00     13555225.00
      2474025.01     13554325.02
#Sta/Elev= 30
  4138.8  287.39  4383.9  279.92  4415.6  279.58  4421.4  278.67  4443.5  277.86
  4705.9  274.80  4862.7  270.71  4969.0  269.27  4990.4  268.01  4990.9  267.51
  5001.6  267.51  5002.1  268.01  5017.8  269.21  5099.8  270.25  5121.9  269.52
  5185.8  269.57  5287.3  270.99  5412.2  270.33  5491.6  271.56  5543.8  270.95
  5592.3  271.41  5607.7  270.76  5677.0  271.17  5794.5  272.64  5987.0  278.14
  6014.2  279.81  6060.5  281.26  6072.5  282.56  6139.9  285.65  6248.3  289.70
#Mann=7,-1,0
  4138.8    0.12       0  4383.9    0.05       0  4862.7     0.1       0
  4990.4    0.05       0  5002.1     0.1       0  5677.0    0.12       0
  5794.5    0.04       0
Bank Sta=4990.4,5002.1
Exp/Cntr=0.3,0.1

Type RM Length L Ch R = 1,15850,553,553,553
BEGIN DESCRIPTION:
Mapping XS 7a4416fc
END DESCRIPTION:
XS GIS Cut Line= 3
      2475174.62     13556092.25      2475100.84     13554989.86
      2473908.62     13553953.72
#Sta/Elev= 30
  3950.8  286.75  4254.1  278.92  4590.6  272.19  4914.6  269.60  4950.3  268.83
  4960.3  267.39  4994.5  267.24  4995.0  266.74  5006.3  267.24  5169.4  270.16
  5205.2  268.97  5240.3  269.82  5275.4  268.91  5381.8  269.96  5410.3  269.03
  5621.8  270.16  5642.6  270.46  5757.8  271.52  5893.7  275.85  6009.6  279.37
  6030.2  279.87  6183.2  286.75  6218.3  289.89  6246.8  289.68  6356.4  294.60
  6360.3  294.69  6416.8  297.58  6537.4  301.52  6632.0  302.97  6635.2  303.07
#Mann=14,-1,0
  3950.8    0.12       0  4254.1    0.05       0  4590.6    0.12       0
  4914.6     0.1       0  4994.5    0.05       0  5006.3     0.1       0
  5621.8    0.12       0  5642.6    0.04       0  5893.7    0.12       0
  6009.6    0.04       0  6030.2    0.12       0  6356.4    0.05       0
  6360.3    0.12       0  6632.0    0.05       0
Bank Sta=4994.5,5006.3
Exp/Cntr=0.3,0.1

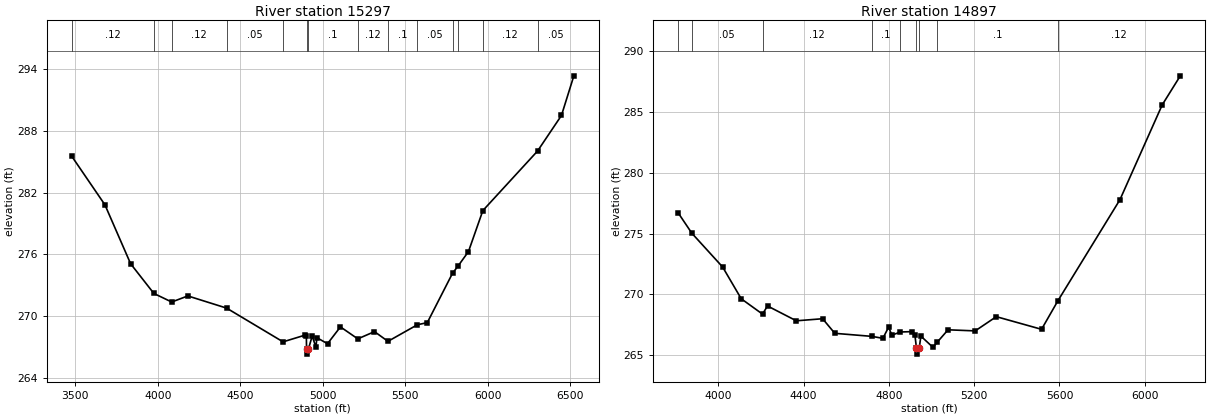
Type RM Length L Ch R = 1,15297,400,400,400
BEGIN DESCRIPTION:
Mapping XS f821f220
END DESCRIPTION:
XS GIS Cut Line= 4
      2475222.37     13556079.25      2475556.56     13554872.68
      2474779.65     13553909.13      2474338.48     13553576.09
#Sta/Elev= 30
  3478.0  285.53  3679.6  280.81  3835.2  275.10  3976.1  272.22  4084.2  271.39
  4181.9  271.98  4416.8  270.80  4758.8  267.53  4893.7  268.19  4900.1  268.06
  4901.0  266.84  4901.5  266.34  4912.8  266.84  4935.3  268.10  4957.7  267.01
  4964.1  267.93  5028.1  267.35  5106.4  268.98  5211.6  267.82  5312.7  268.52
  5394.5  267.58  5572.9  269.19  5632.6  269.39  5785.6  274.18  5818.3  274.86
  5882.1  276.28  5969.2  280.25  6300.5  286.02  6445.5  289.47  6520.5  293.31
#Mann=14,-1,0
  3478.0    0.12       0  3976.1    0.05       0  4084.2    0.12       0
  4416.8    0.05       0  4758.8     0.1       0  4901.0    0.05       0
  4912.8     0.1       0  5211.6    0.12       0  5394.5     0.1       0
  5572.9    0.05       0  5785.6    0.12       0  5818.3    0.05       0
  5969.2    0.12       0  6300.5    0.05       0
Bank Sta=4901,4912.8
Exp/Cntr=0.3,0.1

Type RM Length L Ch R = 1,14897,454,454,454
BEGIN DESCRIPTION:
SHILOH CREEK 31.0
END DESCRIPTION:
XS GIS Cut Line= 3
      2476575.00     13555075.00      2475675.00     13554475.00
      2474774.97     13553574.97
#Sta/Elev= 30
  3812.0  276.71  3876.4  275.03  4020.8  272.25  4108.0  269.64  4207.7  268.38
  4231.1  269.05  4366.3  267.83  4489.5  268.00  4546.6  266.80  4720.3  266.55
  4772.0  266.39  4799.0  267.31  4814.0  266.65  4854.6  266.91  4907.8  266.94
  4921.9  266.68  4929.6  265.59  4930.1  265.09  4942.5  265.59  4950.2  266.57
  5006.8  265.65  5027.8  266.09  5077.5  267.09  5204.8  267.00  5303.8  268.17
  5515.9  267.13  5592.4  269.47  5883.6  277.79  6081.6  285.58  6166.5  287.97
#Mann=9,-1,0
  3812.0    0.12       0  3876.4    0.05       0  4207.7    0.12       0
  4720.3     0.1       0  4854.6    0.12       0  4929.6    0.05       0
  4942.5    0.12       0  5027.8     0.1       0  5592.4    0.12       0
Bank Sta=4929.6,4942.5
Exp/Cntr=0.3,0.1