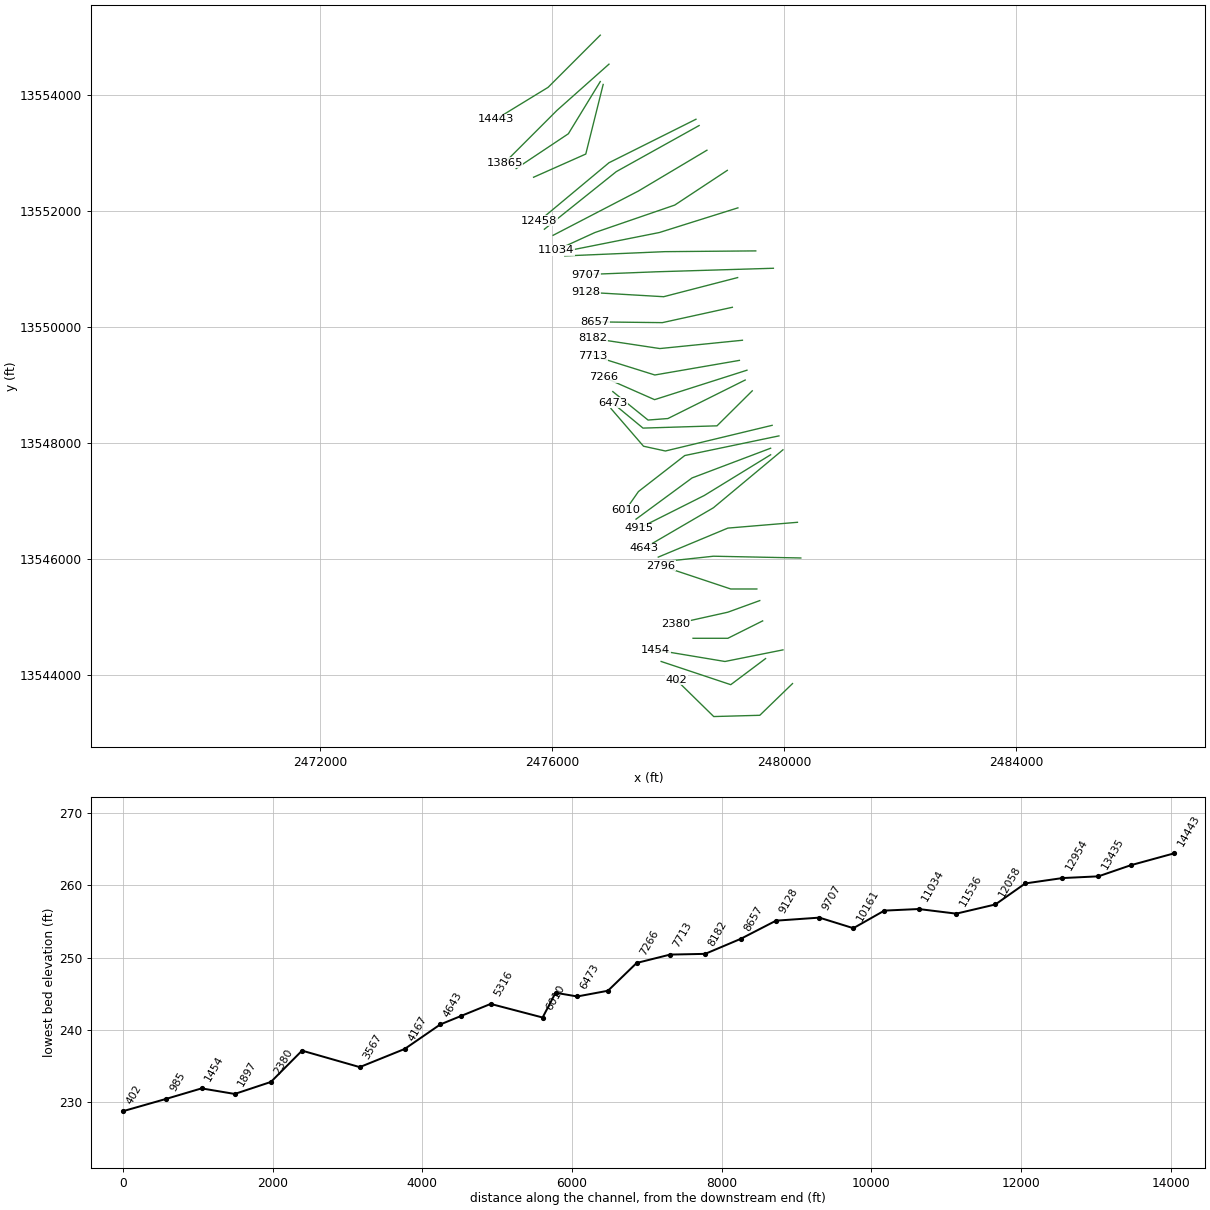
HEC-RAS study SHILOH CREEK.prj: SHILOH CREEK Base Level Engineering

--- SHILOH CREEK.g01 (geometry) --- (continued)

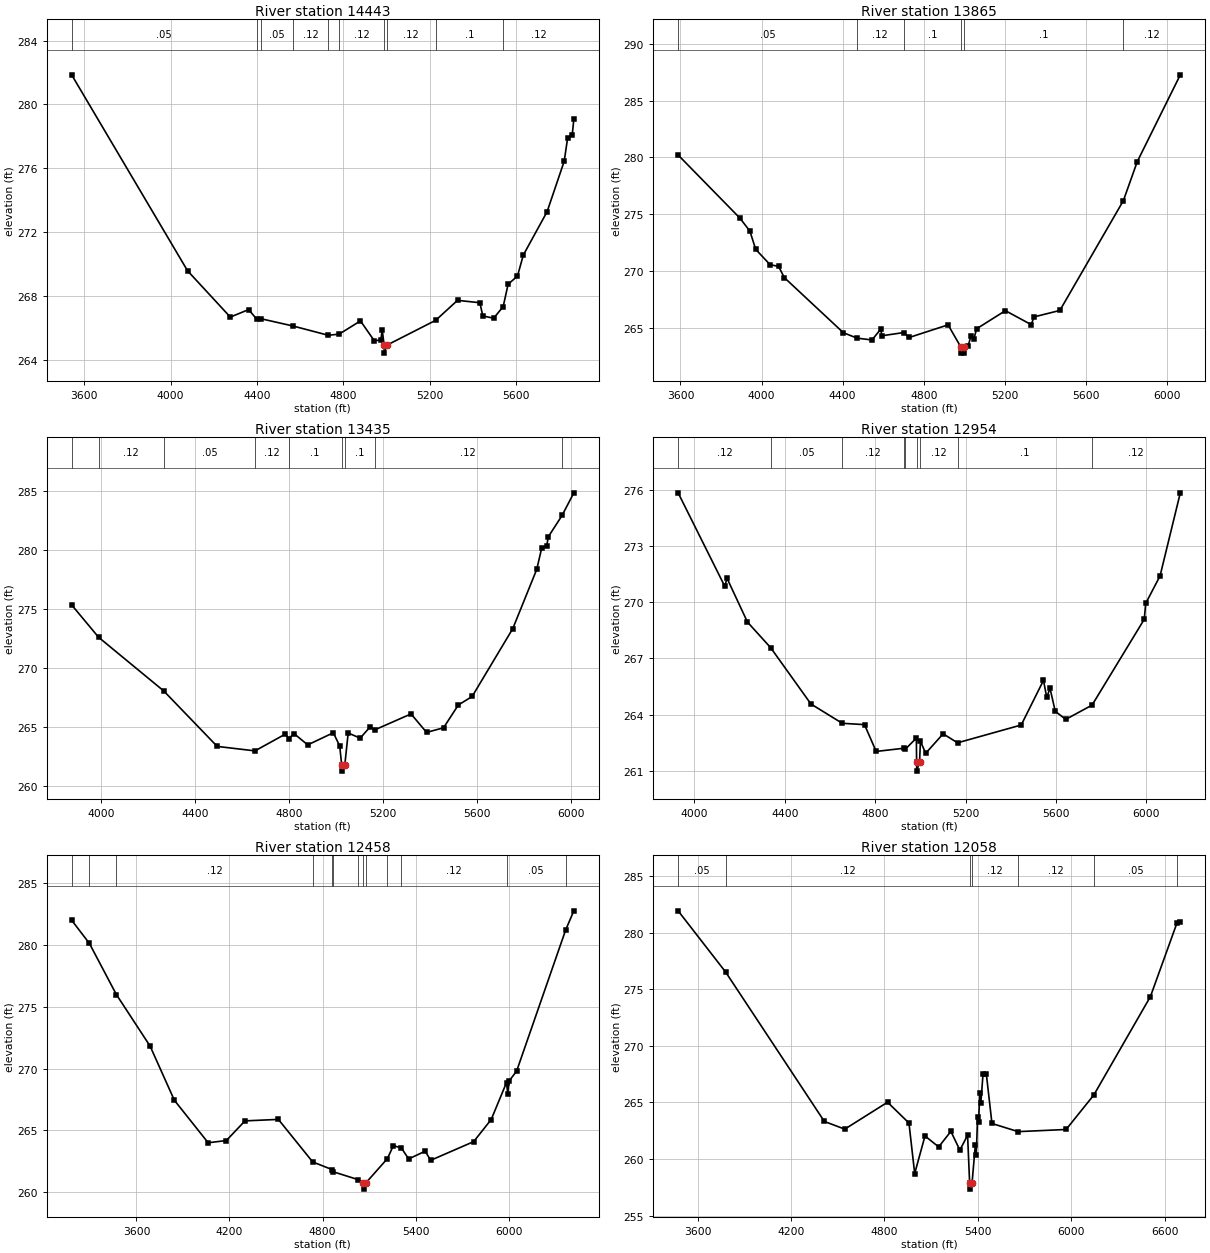
Type RM Length L Ch R = 1,14443,578,578,578
BEGIN DESCRIPTION:
SHILOH CREEK 30.0
END DESCRIPTION:
XS GIS Cut Line= 3
      2476825.02     13555025.02      2475925.00     13554125.00
      2475024.98     13553574.99
#Sta/Elev= 30
  3541.4  281.85  4078.8  269.56  4276.8  266.66  4361.7  267.13  4399.7  266.52
  4420.8  266.55  4567.6  266.10  4730.8  265.52  4781.1  265.59  4880.0  266.42
  4943.9  265.18  4974.8  265.22  4980.7  265.87  4989.7  264.90  4990.2  264.40
  5002.6  264.90  5228.9  266.46  5329.9  267.71  5433.5  267.56  5447.1  266.73
  5497.4  266.59  5541.6  267.32  5564.3  268.72  5607.7  269.23  5634.9  270.55
  5745.1  273.27  5824.5  276.44  5839.9  277.87  5861.3  278.06  5869.0  279.07
#Mann=10,-1,0
  3541.4    0.05       0  4399.7    0.12       0  4420.8    0.05       0
  4567.6    0.12       0  4730.8     0.1       0  4781.1    0.12       0
  4989.7    0.05       0  5002.6    0.12       0  5228.9     0.1       0
  5541.6    0.12       0
Bank Sta=4989.7,5002.6
Exp/Cntr=0.3,0.1

Type RM Length L Ch R = 1,13865,430,430,430
BEGIN DESCRIPTION:
SHILOH CREEK 29.0
END DESCRIPTION:
XS GIS Cut Line= 3
      2476975.02     13554525.02      2476075.00     13553725.00
      2475174.99     13552824.99
#Sta/Elev= 30
  3588.5  280.21  3893.3  274.65  3942.7  273.50  3971.1  271.90  4042.2  270.55
  4084.0  270.40  4112.4  269.41  4403.4  264.56  4471.0  264.08  4544.7  263.92
  4587.4  264.86  4594.1  264.29  4700.7  264.57  4728.7  264.14  4920.0  265.25
  4984.2  263.26  4984.7  262.76  4996.7  262.76  4997.2  263.26  5019.0  263.38
  5033.1  264.30  5047.2  264.03  5061.4  264.91  5202.8  266.50  5330.1  265.27
  5344.2  265.95  5471.5  266.52  5784.7  276.19  5853.3  279.63  6065.5  287.27
#Mann=6,-1,0
  3588.5    0.05       0  4471.0    0.12       0  4700.7     0.1       0
  4984.2    0.05       0  4997.2     0.1       0  5784.7    0.12       0
Bank Sta=4984.2,4997.2
Exp/Cntr=0.3,0.1

Type RM Length L Ch R = 1,13435,481,481,481
BEGIN DESCRIPTION:
SHILOH CREEK 28.0
END DESCRIPTION:
XS GIS Cut Line= 3
      2476824.98     13554224.97      2476275.00     13553325.00
      2475374.99     13552724.99
#Sta/Elev= 30
  3873.9  275.35  3988.5  272.60  4265.7  268.04  4493.1  263.33  4653.7  262.95
  4783.5  264.38  4797.2  264.00  4820.2  264.41  4878.3  263.46  4987.2  264.49
  5014.3  263.36  5022.8  261.73  5023.3  261.23  5035.8  261.73  5050.3  264.47
  5101.4  264.03  5145.0  265.02  5162.8  264.73  5317.7  266.09  5383.8  264.52
  5455.9  264.91  5519.0  266.85  5577.6  267.57  5750.4  273.33  5852.5  278.37
  5873.6  280.18  5894.6  280.36  5902.1  281.15  5960.3  282.95  6010.3  284.87
#Mann=9,-1,0
  3873.9    0.05       0  3988.5    0.12       0  4265.7    0.05       0
  4653.7    0.12       0  4797.2     0.1       0  5022.8    0.05       0
  5035.8     0.1       0  5162.8    0.12       0  5960.3    0.05       0
Bank Sta=5022.8,5035.8
Exp/Cntr=0.3,0.1

Type RM Length L Ch R = 1,12954,496,496,496
BEGIN DESCRIPTION:
SHILOH CREEK 27.0
END DESCRIPTION:
XS GIS Cut Line= 3
      2476875.00     13554175.01      2476575.00     13552975.00
      2475675.02     13552575.01
#Sta/Elev= 30
  3928.5  275.83  4134.7  270.85  4145.0  271.27  4235.2  268.94  4338.1  267.57
  4516.1  264.57  4654.8  263.54  4753.1  263.47  4804.7  262.04  4927.2  262.21
  4933.0  262.15  4982.5  262.75  4983.6  261.49  4984.1  260.99  4996.8  261.49
  5000.5  262.59  5023.7  261.94  5101.0  262.98  5164.8  262.50  5446.5  263.45
  5545.0  265.83  5559.4  264.92  5573.8  265.41  5597.0  264.18  5643.5  263.75
  5759.9  264.51  5991.0  269.09  5997.1  269.93  6060.7  271.40  6150.3  275.83
#Mann=9,-1,0
  3928.5    0.12       0  4338.1    0.05       0  4654.8    0.12       0
  4927.2    0.05       0  4933.0    0.12       0  4983.6    0.05       0
  4996.8    0.12       0  5164.8     0.1       0  5759.9    0.12       0
Bank Sta=4983.6,4996.8
Exp/Cntr=0.3,0.1

Type RM Length L Ch R = 1,12458,400,400,400
BEGIN DESCRIPTION:
SHILOH CREEK 26.0
END DESCRIPTION:
XS GIS Cut Line= 3
      2478475.01     13553575.00      2476975.00     13552825.00
      2475775.01     13551825.00
#Sta/Elev= 30
  3182.0  282.00  3296.2  280.13  3470.4  275.99  3687.9  271.82  3844.4  267.44
  4062.5  264.00  4179.9  264.18  4300.0  265.77  4515.3  265.89  4736.6  262.45
  4861.9  261.83  4870.0  261.65  5029.4  261.02  5064.3  260.75  5064.8  260.25
  5079.5  260.75  5218.7  262.72  5256.7  263.76  5308.3  263.59  5355.7  262.69
  5462.4  263.32  5497.5  262.58  5774.8  264.09  5888.1  265.88  5986.8  268.87
  5994.8  267.94  6002.6  268.98  6052.1  269.80  6368.6  281.22  6421.1  282.76
#Mann=13,-1,0
  3182.0    0.04       0  3296.2    0.05       0  3470.4    0.12       0
  4736.6     0.1       0  4861.9    0.12       0  4870.0     0.1       0
  5029.4    0.12       0  5064.3    0.05       0  5079.5    0.12       0
  5218.7    0.04       0  5308.3    0.12       0  5986.8    0.05       0
  6368.6    0.12       0
Bank Sta=5064.3,5079.5
Exp/Cntr=0.3,0.1

Type RM Length L Ch R = 1,12058,522,522,522
BEGIN DESCRIPTION:
Mapping XS b593fa85
END DESCRIPTION:
XS GIS Cut Line= 3
      2478529.65     13553466.42      2477101.70     13552672.16
      2475861.46     13551679.10
#Sta/Elev= 30
  3475.6  281.93  3780.6  276.52  4414.0  263.32  4545.1  262.64  4819.7  265.02
  4957.0  263.18  4993.8  258.72  5060.0  262.04  5147.6  261.07  5226.0  262.44
  5283.7  260.79  5333.3  262.10  5346.5  257.84  5347.0  257.34  5361.7  257.84
  5382.9  261.24  5389.3  260.39  5397.3  263.72  5403.7  263.26  5411.7  265.83
  5418.1  264.93  5432.5  267.53  5453.3  267.55  5489.7  263.14  5657.6  262.42
  5965.5  262.61  6143.5  265.66  6506.5  274.35  6677.6  280.88  6698.4  280.93
#Mann=7,-1,0
  3475.6    0.05       0  3780.6    0.12       0  5346.5    0.05       0
  5361.7    0.12       0  5657.6    0.12       0  6143.5    0.05       0
  6677.6    0.12       0
Bank Sta=5346.5,5361.7
Exp/Cntr=0.3,0.1

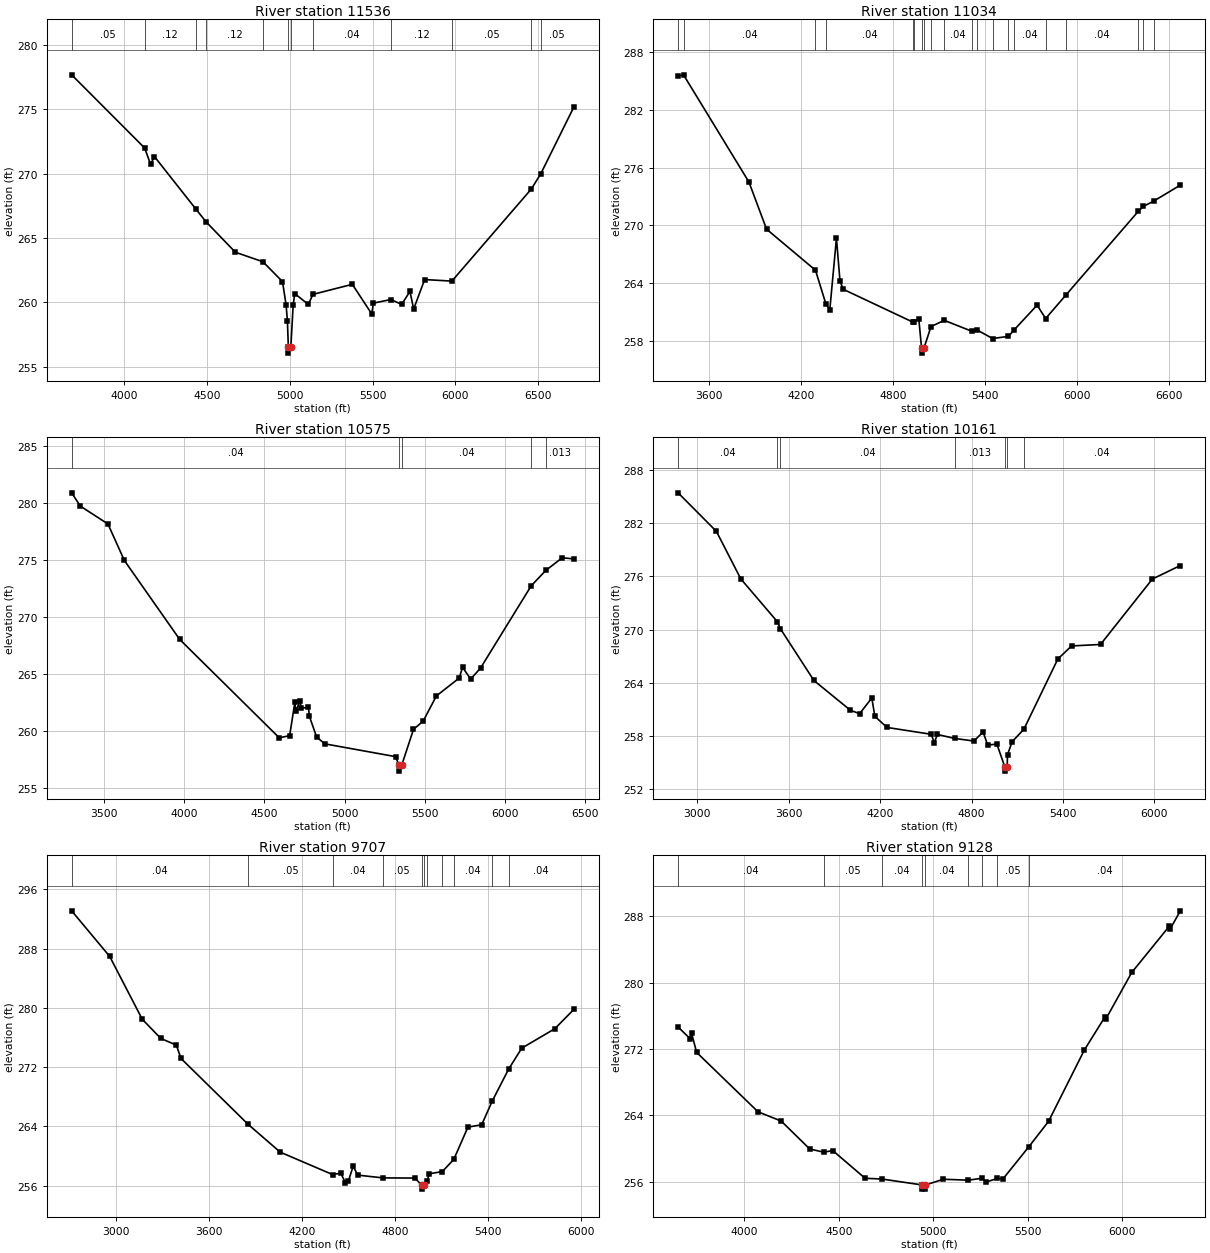
Type RM Length L Ch R = 1,11536,502,502,502
BEGIN DESCRIPTION:
Mapping XS 413ca704
END DESCRIPTION:
XS GIS Cut Line= 3
      2478664.24     13553041.10      2477483.65     13552337.95
      2476012.26     13551574.05
#Sta/Elev= 30
  3683.6  277.67  4124.4  271.99  4160.3  270.72  4183.2  271.33  4433.0  267.26
  4494.5  266.27  4672.1  263.90  4838.7  263.16  4956.6  261.62  4978.0  259.84
  4986.3  258.58  4991.8  256.57  4992.3  256.07  5007.0  256.57  5021.2  259.83
  5030.6  260.69  5112.5  259.85  5140.4  260.63  5378.1  261.41  5495.6  259.11
  5505.1  259.95  5611.0  260.23  5675.9  259.85  5726.3  260.86  5748.5  259.49
  5814.8  261.78  5979.3  261.66  6458.4  268.80  6515.6  269.98  6715.6  275.17
#Mann=12,-1,0
  3683.6    0.05       0  4124.4    0.12       0  4433.0    0.05       0
  4494.5    0.12       0  4838.7    0.05       0  4991.8    0.05       0
  5007.0    0.05       0  5140.4    0.04       0  5611.0    0.12       0
  5979.3    0.05       0  6458.4    0.04       0  6515.6    0.05       0
Bank Sta=4991.8,5007
Exp/Cntr=0.3,0.1

Type RM Length L Ch R = 1,11034,459,459,459
BEGIN DESCRIPTION:
Mapping XS bc4e442f
END DESCRIPTION:
XS GIS Cut Line= 4
      2479015.73     13552693.83      2478108.65     13552094.90
      2476732.78     13551621.81      2476069.33     13551318.27
#Sta/Elev= 30
  3401.6  285.53  3436.8  285.65  3863.0  274.50  3977.7  269.60  4296.4  265.33
  4364.0  261.84  4389.8  261.23  4433.0  268.65  4456.1  264.21  4477.1  263.35
  4932.9  259.92  4935.1  259.98  4969.3  260.31  4987.6  257.21  4988.1  256.71
  5002.9  257.21  5048.9  259.47  5135.1  260.12  5318.7  258.96  5347.4  259.13
  5450.4  258.23  5553.4  258.45  5590.3  259.12  5740.2  261.70  5795.9  260.31
  5926.8  262.73  6400.6  271.48  6431.4  271.96  6499.9  272.52  6673.1  274.18
#Mann=20,-1,0
  3401.6    0.05       0  3436.8    0.04       0  4296.4    0.05       0
  4364.0    0.04       0  4932.9    0.05       0  4935.1    0.04       0
  4987.6    0.04       0  5002.9    0.04       0  5048.9    0.05       0
  5135.1    0.04       0  5318.7    0.05       0  5347.4    0.04       0
  5450.4    0.05       0  5553.4    0.12       0  5590.3    0.04       0
  5795.9    0.05       0  5926.8    0.04       0  6400.6    0.05       0
  6431.4    0.04       0  6499.9    0.05       0
Bank Sta=4987.6,5002.9
Exp/Cntr=0.3,0.1

Type RM Length L Ch R = 1,10575,414,414,414
BEGIN DESCRIPTION:
Mapping XS 07dd0100
END DESCRIPTION:
XS GIS Cut Line= 3
      2479198.03     13552047.15      2477843.89     13551621.81
      2476164.19     13551287.60
#Sta/Elev= 30
  3298.0  280.88  3351.8  279.72  3524.3  278.15  3626.8  274.95  3972.0  268.03
  4592.8  259.41  4657.6  259.60  4690.0  262.51  4695.3  261.77  4724.0  262.64
  4729.1  262.00  4775.1  262.09  4780.2  261.31  4826.2  259.47  4877.3  258.88
  5317.8  257.76  5340.6  256.99  5341.1  256.49  5356.1  256.99  5430.0  260.15
  5490.7  260.88  5572.7  263.08  5715.4  264.65  5735.8  265.59  5786.8  264.56
  5848.0  265.52  6164.1  272.73  6256.0  274.09  6357.8  275.19  6430.0  275.09
#Mann=5,-1,0
  3298.0    0.04       0  5340.6    0.04       0  5356.1    0.04       0
  6164.1    0.05       0  6256.0   0.013       0
Bank Sta=5340.6,5356.1
Exp/Cntr=0.3,0.1

Type RM Length L Ch R = 1,10161,454,454,454
BEGIN DESCRIPTION:
Mapping XS 34cf07cb
END DESCRIPTION:
XS GIS Cut Line= 3
      2479506.18     13551304.97      2477939.38     13551291.95
      2476211.91     13551218.16
#Sta/Elev= 30
  2874.4  285.41  3125.6  281.07  3285.6  275.72  3524.9  270.91  3546.0  270.09
  3765.6  264.27  4005.6  260.91  4065.6  260.53  4145.6  262.30  4165.6  260.23
  4245.6  258.98  4535.7  258.21  4555.7  257.27  4575.8  258.19  4690.5  257.74
  4816.0  257.45  4876.0  258.48  4906.1  256.98  4966.1  257.12  5018.2  254.56
  5018.7  254.06  5034.1  254.56  5036.2  255.90  5066.2  257.37  5143.7  258.78
  5366.5  266.69  5456.6  268.16  5646.7  268.33  5987.0  275.70  6170.3  277.22
#Mann=7,-1,0
  2874.4    0.04       0  3524.9   0.013       0  3546.0    0.04       0
  4690.5   0.013       0  5018.2    0.03       0  5034.1   0.013       0
  5143.7    0.04       0
Bank Sta=5018.2,5034.1
Exp/Cntr=0.3,0.1

Type RM Length L Ch R = 1,9707,579,579,579
BEGIN DESCRIPTION:
Mapping XS c13331b4
END DESCRIPTION:
XS GIS Cut Line= 3
      2479810.07     13551005.49      2477796.15     13550944.73
      2476572.22     13550896.98
#Sta/Elev= 30
  2715.2  293.09  2960.4  286.94  3170.5  278.46  3290.5  275.86  3390.6  274.96
  3420.6  273.16  3853.5  264.27  4060.9  260.51  4398.3  257.49  4451.1  257.67
  4481.1  256.40  4501.1  256.65  4531.1  258.61  4561.1  257.41  4722.3  257.04
  4931.3  257.01  4973.3  256.02  4973.8  255.52  4989.4  256.02  5008.2  256.55
  5021.4  257.59  5106.5  257.89  5180.4  259.53  5271.6  263.89  5360.5  264.21
  5427.6  267.37  5533.7  271.70  5618.9  274.55  5832.0  277.17  5954.9  279.78
#Mann=11,-1,0
  2715.2    0.04       0  3853.5    0.05       0  4398.3    0.04       0
  4722.3    0.05       0  4973.3    0.05       0  4989.4    0.05       0
  5008.2    0.04       0  5106.5    0.05       0  5180.4    0.04       0
  5427.6    0.05       0  5533.7    0.04       0
Bank Sta=4973.3,4989.4
Exp/Cntr=0.3,0.1

Type RM Length L Ch R = 1,9128,471,471,471
BEGIN DESCRIPTION:
Mapping XS 4d989e53
END DESCRIPTION:
XS GIS Cut Line= 3
      2479193.71     13550844.90      2477917.68     13550515.04
      2476578.22     13550593.06
#Sta/Elev= 30
  3649.3  274.66  3712.0  273.27  3720.3  273.92  3747.4  271.60  4072.5  264.43
  4195.4  263.31  4346.6  259.94  4420.6  259.56  4468.5  259.75  4639.5  256.41
  4728.2  256.32  4942.9  255.60  4943.4  255.10  4958.5  255.10  4959.0  255.60
  5053.9  256.29  5186.8  256.18  5257.5  256.41  5280.5  255.96  5340.4  256.39
  5370.6  256.35  5507.4  260.23  5611.0  263.27  5801.4  271.91  5909.5  275.86
  5914.5  275.62  6051.8  281.24  6251.7  286.85  6256.7  286.54  6309.0  288.68
#Mann=9,-1,0
  3649.3    0.04       0  4420.6    0.05       0  4728.2    0.04       0
  4942.9    0.04       0  4959.0    0.04       0  5186.8    0.05       0
  5257.5    0.12       0  5340.4    0.05       0  5507.4    0.04       0
Bank Sta=4942.9,4959
Exp/Cntr=0.3,0.1

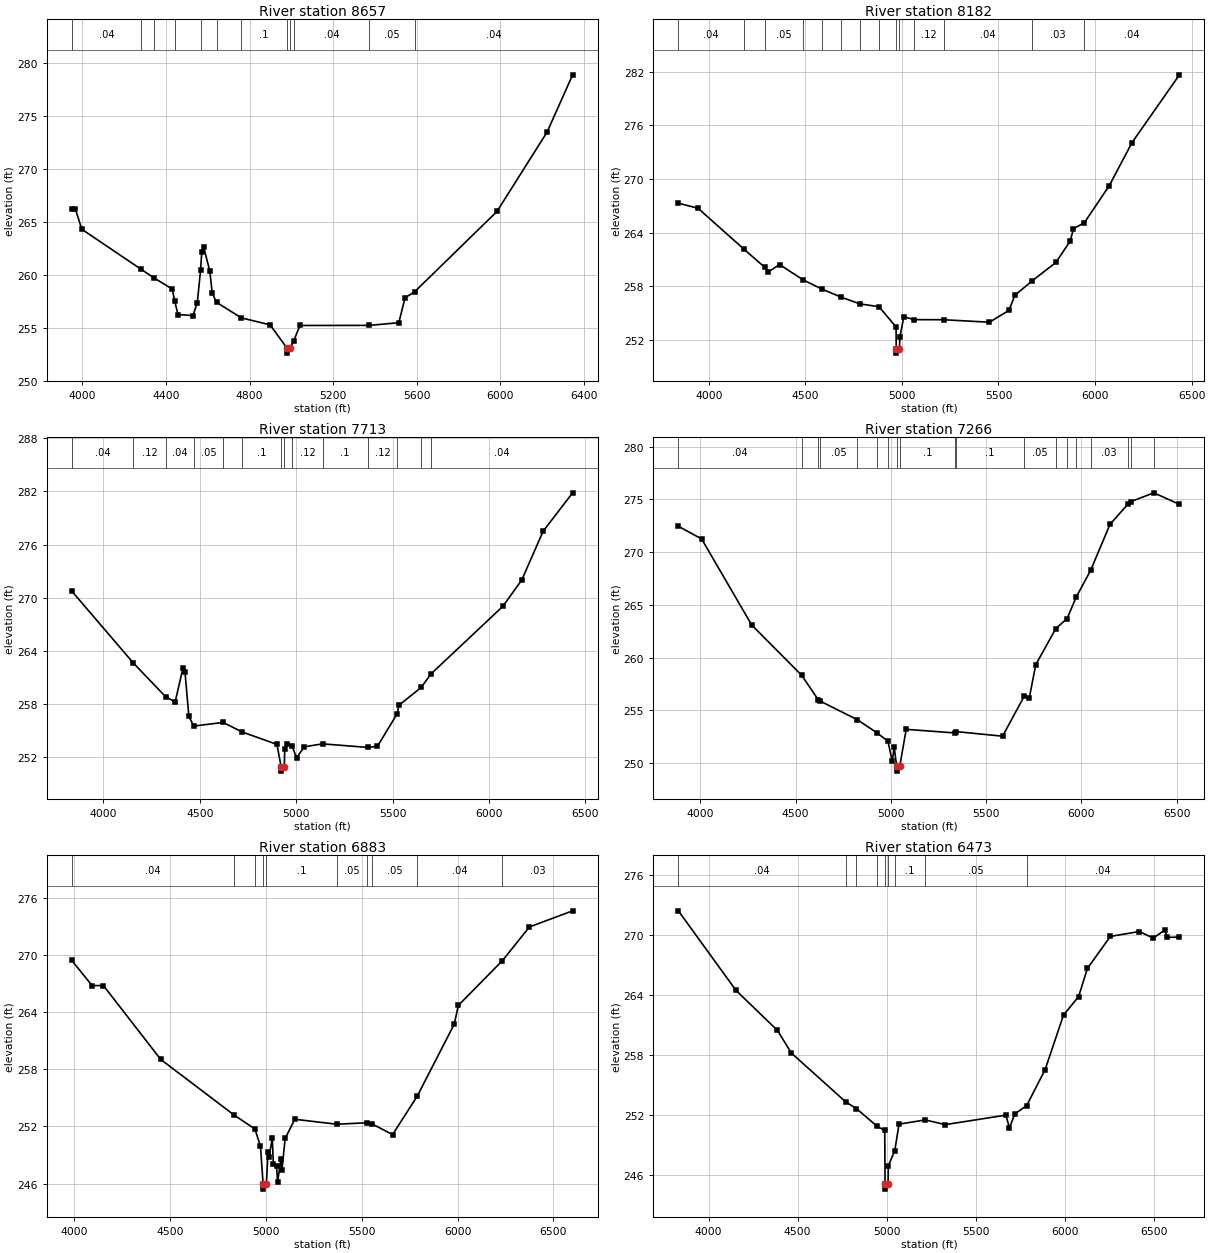
Type RM Length L Ch R = 1,8657,475,475,475
BEGIN DESCRIPTION:
Mapping XS 081a660d
END DESCRIPTION:
XS GIS Cut Line= 3
      2479102.55     13550332.74      2477895.97     13550067.99
      2476732.83     13550081.01
#Sta/Elev= 30
  3948.3  266.17  3966.3  266.21  3997.0  264.29  4280.9  260.51  4342.2  259.70
  4429.9  258.65  4442.3  257.47  4457.7  256.23  4529.4  256.14  4549.8  257.33
  4565.7  260.41  4571.5  262.18  4580.5  262.62  4610.2  260.30  4621.5  258.26
  4642.4  257.38  4760.9  255.92  4898.6  255.26  4978.2  253.09  4978.7  252.59
  4994.4  253.09  5012.3  253.78  5041.2  255.20  5372.3  255.21  5514.6  255.46
  5544.6  257.82  5591.4  258.40  5984.6  265.97  6224.6  273.47  6346.8  278.87
#Mann=12,-1,0
  3948.3    0.04       0  4280.9    0.12       0  4342.2    0.05       0
  4442.3     0.1       0  4565.7    0.05       0  4642.4    0.04       0
  4760.9     0.1       0  4978.2    0.05       0  4994.4     0.1       0
  5012.3    0.04       0  5372.3    0.05       0  5591.4    0.04       0
Bank Sta=4978.2,4994.4
Exp/Cntr=0.3,0.1

Type RM Length L Ch R = 1,8182,469,469,469
BEGIN DESCRIPTION:
Mapping XS d608c4b1
END DESCRIPTION:
XS GIS Cut Line= 3
      2479276.19     13549764.17      2477852.57     13549620.94
      2476702.41     13549794.55
#Sta/Elev= 30
  3843.0  267.30  3944.7  266.73  4184.0  262.12  4291.2  260.10  4306.5  259.57
  4366.8  260.43  4487.4  258.73  4586.0  257.68  4684.5  256.79  4783.1  256.02
  4881.6  255.71  4969.9  253.44  4971.0  251.01  4971.5  250.51  4987.3  251.01
  4990.0  252.34  5010.1  254.58  5063.8  254.26  5216.4  254.25  5453.4  253.97
  5554.5  255.30  5584.9  256.98  5674.0  258.59  5797.2  260.66  5871.8  263.06
  5888.3  264.44  5944.8  265.11  6073.4  269.25  6191.7  274.09  6437.0  281.67
#Mann=14,-1,0
  3843.0    0.04       0  4184.0    0.12       0  4291.2    0.05       0
  4487.4    0.12       0  4586.0    0.04       0  4684.5    0.12       0
  4783.1    0.04       0  4881.6     0.1       0  4971.0    0.05       0
  4987.3     0.1       0  5063.8    0.12       0  5216.4    0.04       0
  5674.0    0.03       0  5944.8    0.04       0
Bank Sta=4971,4987.3
Exp/Cntr=0.3,0.1

Type RM Length L Ch R = 1,7713,447,447,447
BEGIN DESCRIPTION:
Mapping XS 1b629d20
END DESCRIPTION:
XS GIS Cut Line= 3
      2479224.10     13549416.95      2477765.77     13549165.21
      2476699.00     13549499.12
#Sta/Elev= 30
  3835.9  270.77  4155.8  262.63  4323.4  258.81  4372.8  258.23  4413.4  262.06
  4423.6  261.65  4443.9  256.60  4469.3  255.50  4621.3  255.91  4720.6  254.83
  4900.5  253.43  4922.2  250.91  4922.7  250.41  4938.6  250.91  4941.1  252.96
  4951.3  253.53  4980.3  253.20  5002.0  251.91  5042.6  253.16  5137.2  253.49
  5370.4  253.09  5421.4  253.21  5524.4  256.91  5532.1  257.84  5648.2  259.86
  5698.2  261.37  6072.3  269.04  6169.7  272.00  6280.6  277.51  6433.6  281.85
#Mann=14,-1,0
  3835.9    0.04       0  4155.8    0.12       0  4323.4    0.04       0
  4469.3    0.05       0  4621.3    0.04       0  4720.6     0.1       0
  4922.2    0.05       0  4938.6     0.1       0  4980.3    0.12       0
  5137.2     0.1       0  5370.4    0.12       0  5524.4    0.04       0
  5648.2    0.03       0  5698.2    0.04       0
Bank Sta=4922.2,4938.6
Exp/Cntr=0.3,0.1

Type RM Length L Ch R = 1,7266,383,383,383
BEGIN DESCRIPTION:
Mapping XS 2ca55266
END DESCRIPTION:
XS GIS Cut Line= 3
      2479354.33     13549247.68      2477761.43     13548739.86
      2476884.65     13549126.17
#Sta/Elev= 30
  3884.7  272.45  4006.7  271.25  4269.6  263.10  4532.3  258.32  4619.5  255.99
  4628.4  255.89  4824.1  254.12  4926.4  252.89  4984.7  252.08  5007.1  250.19
  5017.6  251.52  5030.1  249.75  5030.6  249.25  5047.0  249.75  5080.5  253.21
  5335.6  252.87  5341.1  253.00  5586.3  252.56  5701.0  256.38  5726.3  256.15
  5760.6  259.34  5865.6  262.75  5925.1  263.71  5972.6  265.73  6048.5  268.27
  6150.2  272.63  6244.7  274.56  6260.3  274.79  6380.2  275.62  6514.7  274.53
#Mann=19,-1,0
  3884.7    0.04       0  4532.3    0.05       0  4619.5    0.12       0
  4628.4    0.05       0  4824.1     0.1       0  4926.4    0.12       0
  4984.7     0.1       0  5030.1    0.05       0  5047.0     0.1       0
  5335.6    0.05       0  5341.1     0.1       0  5701.0    0.05       0
  5865.6    0.04       0  5925.1    0.03       0  5972.6    0.04       0
  6048.5    0.03       0  6244.7    0.04       0  6260.3    0.03       0
  6380.2    0.04       0
Bank Sta=5030.1,5047
Exp/Cntr=0.3,0.1

Type RM Length L Ch R = 1,6883,410,410,410
BEGIN DESCRIPTION:
Mapping XS ae598ba1
END DESCRIPTION:
XS GIS Cut Line= 4
      2479323.89     13549078.39      2477991.46     13548414.34
      2477648.58     13548388.30      2477040.93     13548878.76
#Sta/Elev= 30
  3987.0  269.43  4093.7  266.77  4153.4  266.76  4451.8  259.02  4834.8  253.18
  4943.2  251.72  4972.2  249.90  4986.1  245.91  4986.6  245.41  5003.0  245.91
  5011.4  249.31  5017.0  248.83  5033.8  250.73  5039.4  248.06  5056.2  247.81
  5061.7  246.15  5078.5  248.55  5084.1  247.40  5100.9  250.73  5151.3  252.74
  5370.2  252.22  5527.1  252.37  5554.5  252.25  5661.4  251.13  5790.5  255.19
  5983.2  262.73  6004.1  264.68  6234.4  269.39  6375.0  272.92  6600.5  274.61
#Mann=10,-1,0
  3987.0    0.04       0  4834.8    0.12       0  4943.2     0.1       0
  4986.1    0.05       0  5003.0     0.1       0  5370.2    0.05       0
  5527.1     0.1       0  5554.5    0.05       0  5790.5    0.04       0
  6234.4    0.03       0
Bank Sta=4986.1,5003
Exp/Cntr=0.3,0.1

Type RM Length L Ch R = 1,6473,290,290,290
BEGIN DESCRIPTION:
Mapping XS c6a7cc0f
END DESCRIPTION:
XS GIS Cut Line= 4
      2479445.45     13548891.77      2478837.81     13548288.48
      2477561.77     13548249.41      2477036.61     13548683.43
#Sta/Elev= 30
  3830.5  272.45  4153.8  264.50  4387.1  260.49  4465.0  258.23  4770.7  253.34
  4830.1  252.68  4947.7  250.89  4989.7  250.49  4991.2  245.12  4991.7  244.62
  5008.2  245.12  5009.7  246.96  5046.0  248.47  5069.8  251.12  5217.4  251.54
  5329.9  251.07  5670.0  252.02  5690.0  250.74  5720.1  252.14  5786.4  252.97
  5890.1  256.56  5993.7  262.03  6078.3  263.87  6127.9  266.69  6256.8  269.89
  6419.7  270.38  6497.8  269.72  6561.6  270.53  6576.0  269.80  6644.7  269.82
#Mann=9,-1,0
  3830.5    0.04       0  4770.7    0.12       0  4830.1    0.04       0
  4947.7    0.05       0  4991.2    0.05       0  5008.2    0.05       0
  5046.0     0.1       0  5217.4    0.05       0  5786.4    0.04       0
Bank Sta=4991.2,5008.2
Exp/Cntr=0.3,0.1

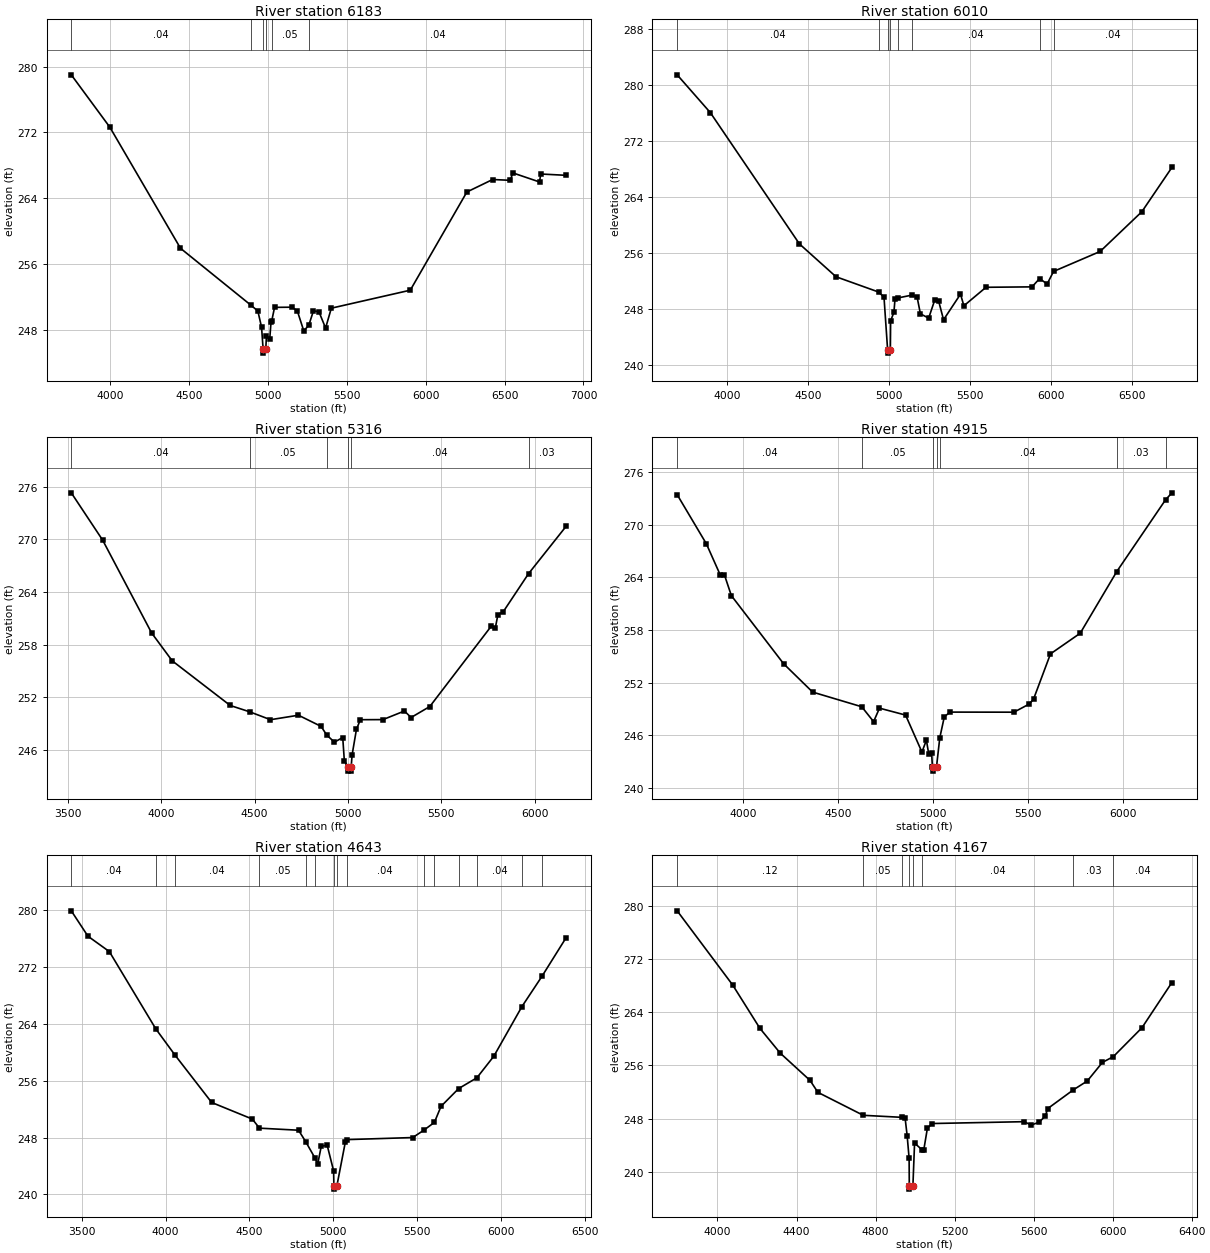
Type RM Length L Ch R = 1,6183,173,173,173
BEGIN DESCRIPTION:
Mapping XS 314959b0
END DESCRIPTION:
XS GIS Cut Line= 4
      2479788.36     13548297.16      2477948.06     13547854.45
      2477570.45     13547936.91      2477009.47     13548586.24
#Sta/Elev= 30
  3751.7  279.00  3996.5  272.62  4444.3  257.89  4889.2  250.99  4934.8  250.26
  4958.5  248.28  4968.2  245.63  4968.7  245.13  4985.2  245.63  4989.4  247.22
  5010.0  246.79  5018.6  248.96  5023.1  249.07  5040.8  250.70  5149.6  250.72
  5184.8  250.29  5225.9  247.85  5257.6  248.50  5287.7  250.29  5322.6  250.15
  5364.5  248.18  5400.8  250.60  5901.6  252.79  6260.4  264.74  6423.9  266.26
  6536.9  266.16  6551.1  267.07  6721.2  265.96  6728.8  266.93  6889.1  266.77
#Mann=6,-1,0
  3751.7    0.04       0  4889.2    0.12       0  4968.2    0.05       0
  4985.2    0.12       0  5023.1    0.05       0  5257.6    0.04       0
Bank Sta=4968.2,4985.2
Exp/Cntr=0.3,0.1

Type RM Length L Ch R = 1,6010,694,694,694
BEGIN DESCRIPTION:
Mapping XS a88ffda6
END DESCRIPTION:
XS GIS Cut Line= 4
      2479905.52     13548114.86      2478282.26     13547776.32
      2477483.65     13547155.66      2477262.71     13546839.42
#Sta/Elev= 30
  3692.2  281.40  3897.0  276.01  4447.1  257.29  4673.4  252.60  4936.7  250.42
  4969.6  249.68  4991.8  242.21  4992.3  241.71  5008.8  242.21  5010.5  246.32
  5030.9  247.54  5037.3  249.37  5053.6  249.57  5143.1  249.99  5173.9  249.72
  5194.4  247.32  5245.4  246.70  5282.3  249.24  5306.7  249.16  5337.4  246.47
  5442.0  250.12  5462.9  248.46  5599.5  251.10  5883.7  251.16  5930.8  252.35
  5976.9  251.56  6016.6  253.36  6304.5  256.21  6562.1  261.88  6747.6  268.19
#Mann=8,-1,0
  3692.2    0.04       0  4936.7    0.12       0  4991.8    0.05       0
  5008.8    0.12       0  5053.6    0.05       0  5143.1    0.04       0
  5930.8    0.05       0  6016.6    0.04       0
Bank Sta=4991.8,5008.8
Exp/Cntr=0.3,0.1

Type RM Length L Ch R = 1,5316,401,401,401
BEGIN DESCRIPTION:
Mapping XS f08b7d11
END DESCRIPTION:
XS GIS Cut Line= 3
      2479762.28     13547902.19      2478408.13     13547390.04
      2477441.46     13546679.13
#Sta/Elev= 30
  3519.4  275.30  3687.6  269.90  3949.5  259.33  4059.5  256.16  4370.0  251.07
  4473.9  250.35  4585.6  249.45  4735.3  249.96  4856.2  248.69  4886.7  247.70
  4927.7  246.89  4972.2  247.42  4980.7  244.79  4999.2  244.09  4999.7  243.59
  5016.9  243.59  5017.4  244.09  5022.4  245.45  5045.5  248.34  5066.3  249.45
  5187.5  249.46  5302.4  250.44  5337.9  249.70  5438.2  250.95  5766.1  260.08
  5789.2  259.94  5802.7  261.43  5830.9  261.74  5966.6  266.09  6167.1  271.47
#Mann=6,-1,0
  3519.4    0.04       0  4473.9    0.05       0  4886.7    0.04       0
  4999.2    0.04       0  5017.4    0.04       0  5966.6    0.03       0
Bank Sta=4999.2,5017.4
Exp/Cntr=0.3,0.1

Type RM Length L Ch R = 1,4915,272,272,272
BEGIN DESCRIPTION:
Mapping XS f289118d
END DESCRIPTION:
XS GIS Cut Line= 3
      2479762.33     13547789.37      2478616.46     13547086.22
      2477492.33     13546521.98
#Sta/Elev= 30
  3653.2  273.42  3806.7  267.82  3880.1  264.25  3901.4  264.30  3938.2  261.91
  4213.2  254.14  4365.8  250.91  4624.0  249.24  4686.4  247.54  4717.3  249.08
  4854.6  248.29  4940.7  244.07  4964.1  245.44  4976.5  243.83  4991.9  243.93
  4995.5  242.42  4999.1  242.40  4999.6  241.90  5017.3  242.40  5034.6  245.71
  5058.4  248.10  5088.8  248.63  5424.4  248.62  5505.1  249.55  5527.5  250.10
  5616.8  255.27  5773.1  257.62  5965.6  264.66  6221.9  272.83  6255.4  273.63
#Mann=7,-1,0
  3653.2    0.04       0  4624.0    0.05       0  4999.1    0.05       0
  5017.3    0.05       0  5034.6    0.04       0  5965.6    0.03       0
  6221.9    0.04       0
Bank Sta=4999.1,5017.3
Exp/Cntr=0.3,0.1

Type RM Length L Ch R = 1,4643,476,476,476
BEGIN DESCRIPTION:
SHILOH CREEK 10.0
END DESCRIPTION:
XS GIS Cut Line= 3
      2479974.99     13547874.99      2478775.00     13546875.00
      2477574.99     13546174.99
#Sta/Elev= 30
  3437.7  279.87  3537.3  276.30  3664.8  274.14  3941.8  263.28  4056.5  259.59
  4275.3  252.93  4517.5  250.60  4560.4  249.32  4793.4  249.03  4836.2  247.42
  4890.8  245.15  4908.0  244.31  4928.8  246.75  4963.9  246.96  5002.6  243.32
  5004.3  241.25  5004.8  240.75  5022.5  241.25  5072.1  247.31  5082.4  247.71
  5474.4  248.00  5538.9  249.00  5603.9  250.13  5643.5  252.39  5748.8  254.89
  5857.4  256.40  5958.6  259.44  6126.3  266.42  6244.9  270.64  6389.0  276.07
#Mann=15,-1,0
  3437.7    0.04       0  3941.8    0.03       0  4056.5    0.04       0
  4560.4    0.05       0  4836.2     0.1       0  4890.8    0.05       0
  5004.3    0.05       0  5022.5    0.05       0  5082.4    0.04       0
  5538.9    0.03       0  5603.9    0.04       0  5748.8    0.03       0
  5857.4    0.04       0  6126.3    0.03       0  6244.9    0.04       0
Bank Sta=5004.3,5022.5
Exp/Cntr=0.3,0.1

Type RM Length L Ch R = 1,4167,600,600,600
BEGIN DESCRIPTION:
SHILOH CREEK 9.0
END DESCRIPTION:
XS GIS Cut Line= 3
      2480224.96     13546625.00      2479025.00     13546525.00
      2477825.02     13546025.01
#Sta/Elev= 30
  3795.9  279.32  4076.8  268.14  4214.8  261.60  4317.7  257.86  4468.2  253.76
  4508.3  251.95  4737.9  248.49  4935.5  248.18  4949.8  248.03  4959.9  245.44
  4969.9  242.01  4970.8  237.86  4971.3  237.36  4989.1  237.86  4997.5  244.29
  5035.4  243.30  5043.9  243.23  5062.3  246.52  5086.1  247.25  5552.5  247.53
  5587.7  247.01  5628.4  247.46  5659.2  248.38  5671.7  249.51  5801.7  252.34
  5871.6  253.66  5948.5  256.47  6003.3  257.33  6148.4  261.69  6300.0  268.51
#Mann=8,-1,0
  3795.9    0.12       0  4737.9    0.05       0  4935.5     0.1       0
  4970.8    0.05       0  4989.1     0.1       0  5035.4    0.04       0
  5801.7    0.03       0  6003.3    0.04       0
Bank Sta=4970.8,4989.1
Exp/Cntr=0.3,0.1

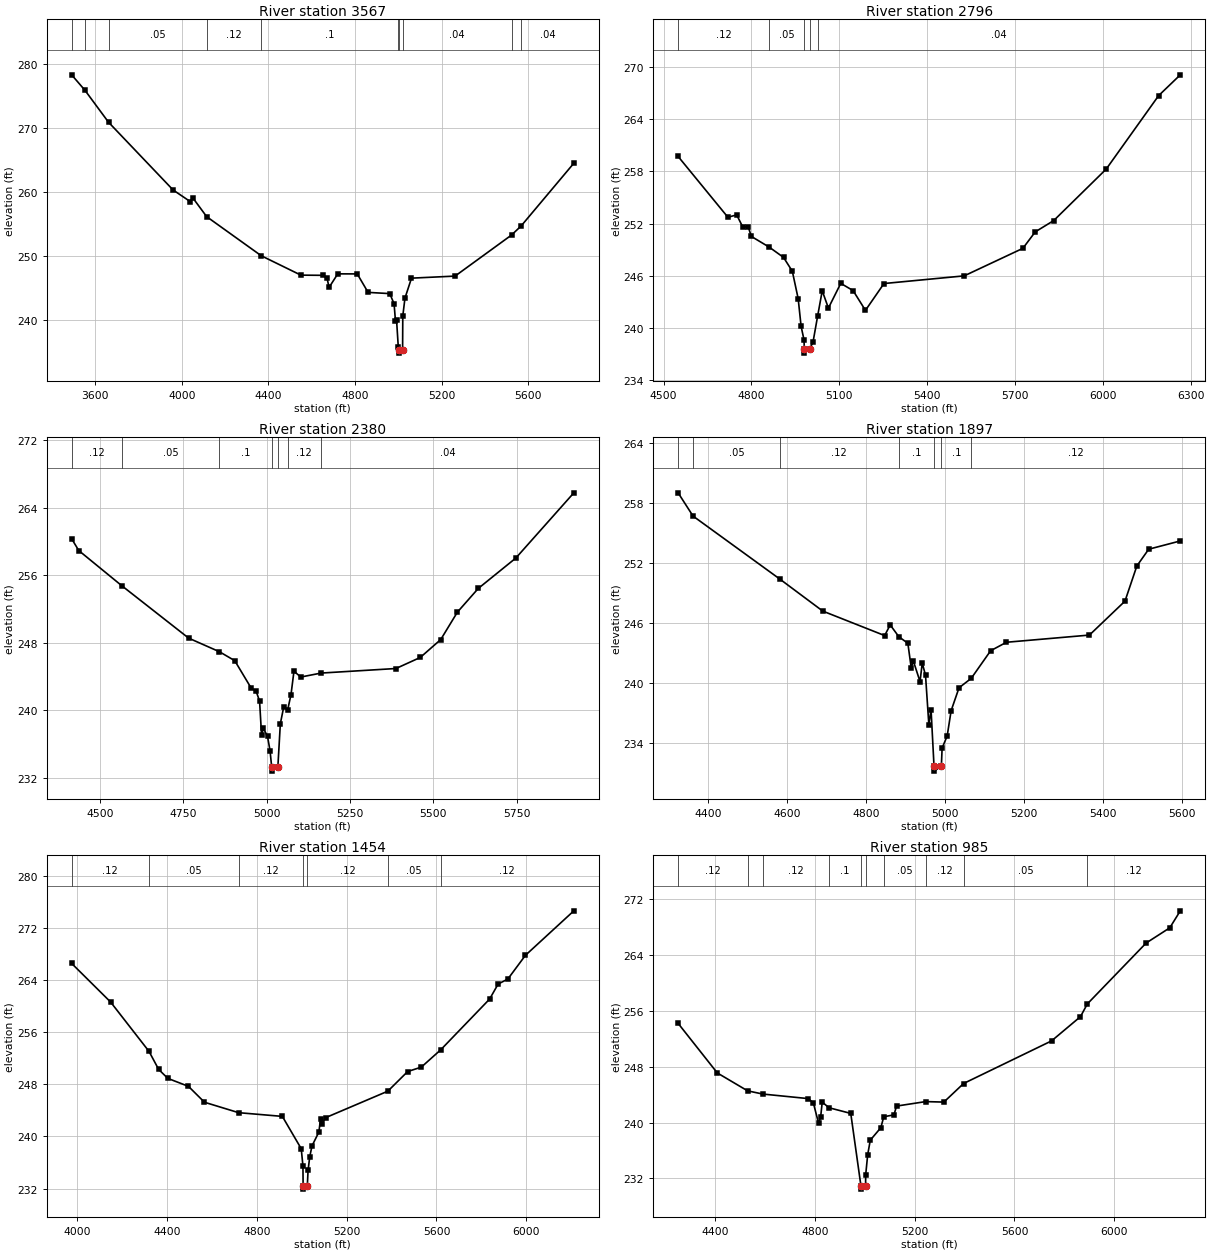
Type RM Length L Ch R = 1,3567,771,771,771
BEGIN DESCRIPTION:
Mapping XS 3c7c5c52
END DESCRIPTION:
XS GIS Cut Line= 3
      2480283.12     13546009.83      2478777.05     13546040.21
      2477969.88     13545953.42
#Sta/Elev= 30
  3491.5  278.24  3552.9  275.83  3661.7  270.85  3959.7  260.29  4039.7  258.46
  4049.7  259.11  4114.7  256.13  4366.8  250.03  4549.8  247.01  4649.9  246.98
  4669.9  246.61  4679.9  245.10  4719.9  247.21  4809.9  247.20  4859.9  244.32
  4959.9  244.13  4979.9  242.55  4986.2  239.91  4991.2  240.08  4999.2  235.87
  5000.8  235.35  5001.3  234.85  5019.2  235.35  5020.1  240.63  5030.1  243.42
  5060.3  246.54  5261.4  246.86  5522.0  253.26  5566.2  254.67  5809.7  264.46
#Mann=10,-1,0
  3491.5    0.05       0  3552.9    0.12       0  3661.7    0.05       0
  4114.7    0.12       0  4366.8     0.1       0  4999.2    0.04       0
  5000.8    0.04       0  5019.2    0.04       0  5522.0    0.03       0
  5566.2    0.04       0
Bank Sta=5000.8,5019.2
Exp/Cntr=0.3,0.1

Type RM Length L Ch R = 1,2796,416,416,416
BEGIN DESCRIPTION:
SHILOH CREEK 6.0
END DESCRIPTION:
XS GIS Cut Line= 3
      2479524.97     13545475.00      2479075.00     13545475.00
      2477874.99     13545875.00
#Sta/Elev= 30
  4549.7  259.71  4719.7  252.73  4749.7  253.00  4769.7  251.66  4789.7  251.57
  4799.7  250.53  4861.2  249.29  4909.7  248.12  4939.7  246.53  4959.7  243.38
  4969.7  240.20  4979.7  238.64  4980.5  237.63  4981.0  237.13  4998.9  237.63
  5010.2  238.37  5026.3  241.42  5041.8  244.29  5062.9  242.30  5105.1  245.14
  5147.2  244.31  5189.4  242.04  5252.7  245.12  5526.7  246.00  5727.0  249.16
  5769.2  251.05  5832.4  252.35  6011.6  258.26  6190.8  266.70  6264.6  269.08
#Mann=5,-1,0
  4549.7    0.12       0  4861.2    0.05       0  4980.5    0.05       0
  4998.9    0.05       0  5026.3    0.04       0
Bank Sta=4980.5,4998.9
Exp/Cntr=0.3,0.1

Type RM Length L Ch R = 1,2380,483,483,483
BEGIN DESCRIPTION:
SHILOH CREEK 5.0
END DESCRIPTION:
XS GIS Cut Line= 3
      2479575.04     13545275.01      2479025.00     13545075.00
      2478125.03     13544875.01
#Sta/Elev= 30
  4414.7  260.34  4436.0  258.94  4564.6  254.79  4765.9  248.56  4858.1  246.95
  4904.2  245.89  4954.1  242.60  4968.1  242.30  4978.7  241.10  4984.7  237.05
  4990.0  237.89  5002.5  236.92  5010.2  235.21  5015.0  233.30  5015.5  232.80
  5033.6  233.30  5041.0  238.41  5051.2  240.42  5063.1  240.08  5073.0  241.86
  5081.9  244.64  5102.4  243.95  5163.2  244.42  5388.0  244.96  5461.0  246.27
  5522.4  248.39  5572.4  251.64  5635.1  254.45  5747.8  258.05  5921.9  265.78
#Mann=7,-1,0
  4414.7    0.12       0  4564.6    0.05       0  4858.1     0.1       0
  5015.0    0.05       0  5033.6     0.1       0  5063.1    0.12       0
  5163.2    0.04       0
Bank Sta=5015,5033.6
Exp/Cntr=0.3,0.1

Type RM Length L Ch R = 1,1897,443,443,443
BEGIN DESCRIPTION:
SHILOH CREEK 4.0
END DESCRIPTION:
XS GIS Cut Line= 3
      2479625.04     13544925.02      2479025.00     13544625.00
      2478424.96     13544625.00
#Sta/Elev= 30
  4323.9  259.02  4361.7  256.69  4581.3  250.38  4690.1  247.17  4846.6  244.72
  4860.6  245.79  4882.6  244.60  4905.3  243.95  4913.7  241.52  4919.3  242.16
  4936.1  240.11  4941.7  241.96  4950.0  240.75  4958.4  235.81  4964.0  237.31
  4971.5  231.64  4972.0  231.14  4990.1  231.64  4992.0  233.45  5004.8  234.66
  5014.8  237.19  5034.8  239.49  5065.6  240.43  5114.8  243.20  5154.8  244.05
  5364.8  244.77  5454.8  248.17  5484.8  251.69  5514.8  253.37  5594.8  254.20
#Mann=7,-1,0
  4323.9    0.12       0  4361.7    0.05       0  4581.3    0.12       0
  4882.6     0.1       0  4971.5    0.05       0  4990.1     0.1       0
  5065.6    0.12       0
Bank Sta=4971.5,4990.1
Exp/Cntr=0.3,0.1

Type RM Length L Ch R = 1,1454,469,469,469
BEGIN DESCRIPTION:
SHILOH CREEK 3.0
END DESCRIPTION:
XS GIS Cut Line= 3
      2479975.05     13544425.01      2478975.00     13544225.00
      2477775.00     13544425.00
#Sta/Elev= 30
  3975.4  266.54  4148.8  260.62  4320.0  253.04  4363.0  250.27  4403.8  248.90
  4495.5  247.68  4566.9  245.24  4719.0  243.64  4913.7  243.07  4997.8  238.11
  5005.4  235.47  5006.2  232.41  5006.7  231.91  5024.9  232.41  5028.2  234.77
  5035.8  236.91  5045.9  238.55  5076.4  240.67  5084.0  242.74  5089.0  241.88
  5106.8  242.88  5383.5  246.94  5471.7  249.95  5532.6  250.63  5618.5  253.27
  5836.7  261.07  5874.7  263.38  5917.8  264.14  5996.4  267.79  6211.8  274.61
#Mann=7,-1,0
  3975.4    0.12       0  4320.0    0.05       0  4719.0    0.12       0
  5006.2    0.05       0  5024.9    0.12       0  5383.5    0.05       0
  5618.5    0.12       0
Bank Sta=5006.2,5024.9
Exp/Cntr=0.3,0.1

Type RM Length L Ch R = 1,985,583,583,583
BEGIN DESCRIPTION:
SHILOH CREEK 2.0
END DESCRIPTION:
XS GIS Cut Line= 3
      2479675.03     13544275.02      2479075.00     13543825.00
      2477874.95     13544225.02
#Sta/Elev= 30
  4250.5  254.20  4407.8  247.10  4529.3  244.54  4590.3  244.08  4772.4  243.43
  4793.2  242.81  4814.1  239.89  4822.4  240.80  4828.7  242.93  4855.9  242.12
  4943.2  241.31  4983.9  230.97  4984.4  230.47  5002.6  230.97  5003.2  232.54
  5011.1  235.39  5021.6  237.48  5063.8  239.26  5075.7  240.83  5116.5  241.10
  5127.0  242.36  5243.8  243.00  5316.8  242.93  5395.9  245.59  5748.9  251.69
  5864.9  255.16  5892.4  256.98  6128.4  265.70  6223.3  267.88  6265.5  270.31
#Mann=10,-1,0
  4250.5    0.12       0  4529.3    0.05       0  4590.3    0.12       0
  4855.9     0.1       0  4983.9    0.05       0  5002.6     0.1       0
  5075.7    0.05       0  5243.8    0.12       0  5395.9    0.05       0
  5892.4    0.12       0
Bank Sta=4983.9,5002.6
Exp/Cntr=0.3,0.1

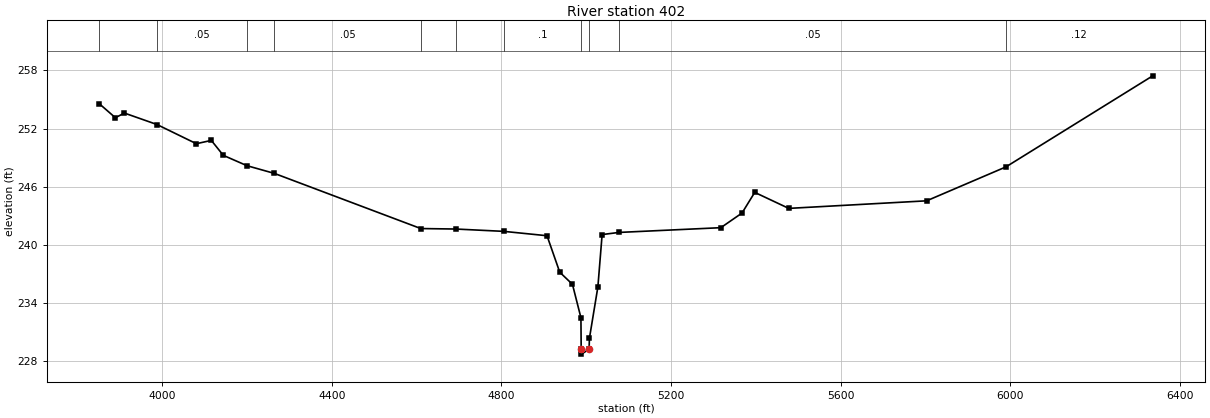
Type RM Length L Ch R = 1,402,0,0,0
BEGIN DESCRIPTION:
SHILOH CREEK 1.0
END DESCRIPTION:
XS GIS Cut Line= 4
      2480139.92     13543844.05      2479575.66     13543297.16
      2478781.39     13543275.45      2478134.68     13543909.15
#Sta/Elev= 30
  3850.9  254.58  3889.0  253.13  3910.3  253.61  3987.1  252.43  4080.1  250.45
  4115.4  250.79  4143.7  249.25  4199.7  248.18  4264.0  247.39  4609.7  241.70
  4692.6  241.65  4805.5  241.41  4907.5  240.96  4937.5  237.20  4967.5  235.95
  4987.5  232.50  4988.1  229.25  4988.6  228.75  5006.8  229.25  5007.5  230.37
  5027.5  235.68  5037.5  241.08  5077.2  241.30  5317.6  241.79  5367.6  243.30
  5397.6  245.43  5477.9  243.78  5803.2  244.56  5990.4  248.06  6336.7  257.45
#Mann=11,-1,0
  3850.9    0.12       0  3987.1    0.05       0  4199.7    0.12       0
  4264.0    0.05       0  4609.7    0.12       0  4692.6    0.05       0
  4805.5     0.1       0  4988.1    0.05       0  5006.8     0.1       0
  5077.2    0.05       0  5990.4    0.12       0
Bank Sta=4988.1,5006.8
Exp/Cntr=0.3,0.1

Chan Stop Cuts=-1