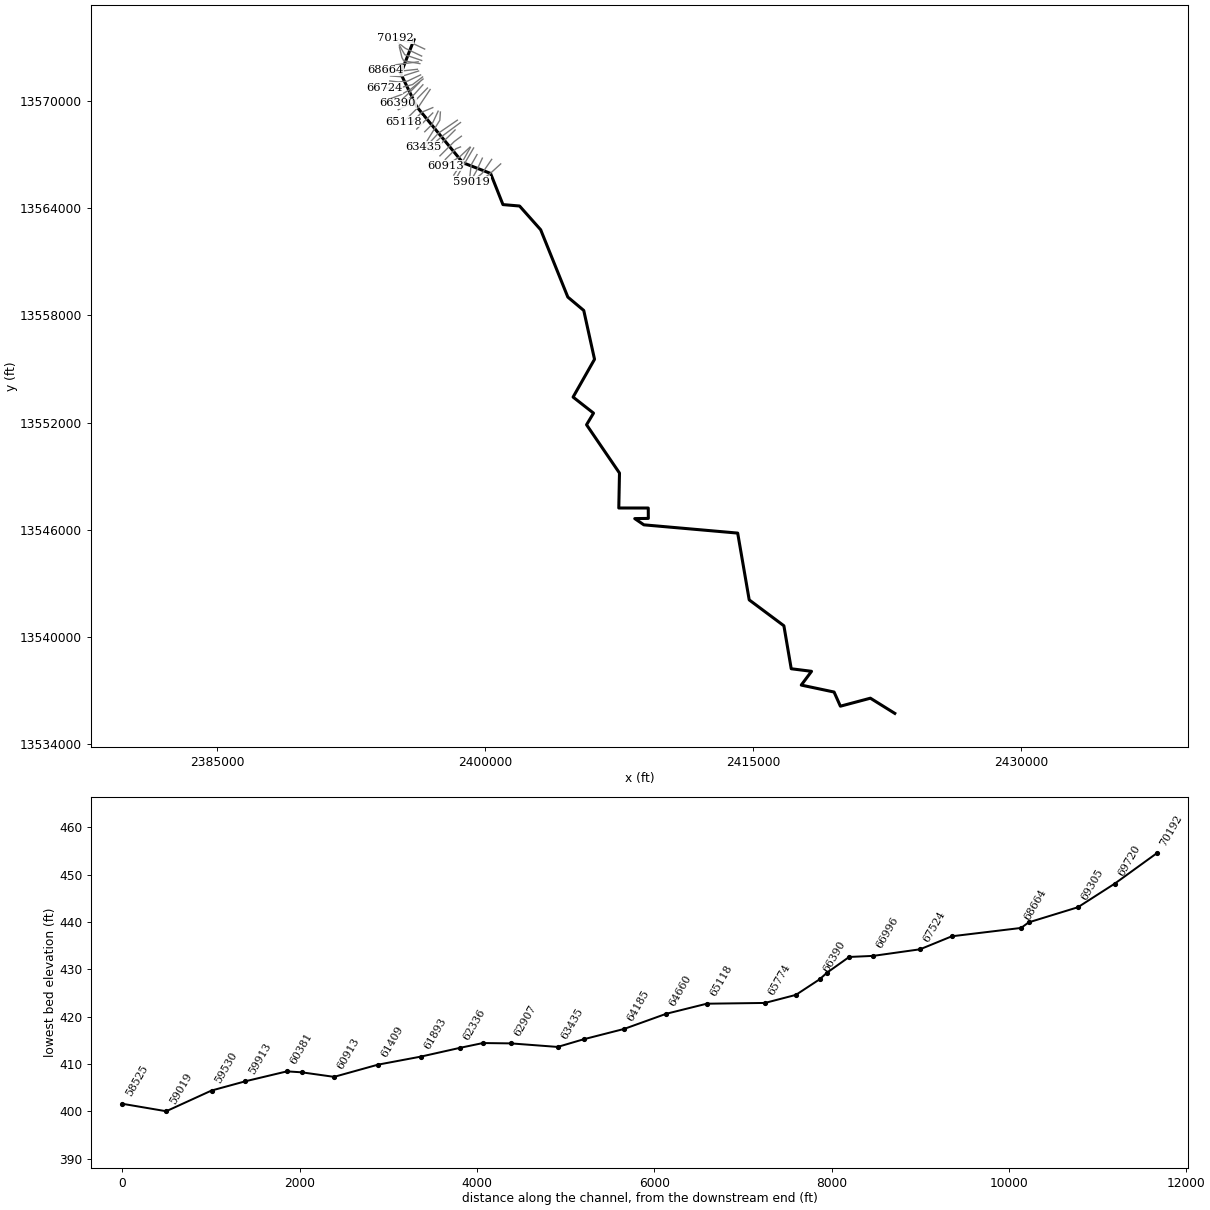
--- THOMAS CREEK.prj (project) ---

Proj Title=THOMAS CREEK Base Level Engineering
Current Plan=p01
Default Exp/Contr=0.3,0.1
English Units
Geom File=g01
Flow File=f01
Plan File=p01
Y Axis Title=Elevation
X Axis Title(PF)=Main Channel Distance
X Axis Title(XS)=Station
BEGIN DESCRIPTION:
THOMAS CREEK
END DESCRIPTION:
DSS Export Rating Curves= 0
DSS Export Rating Curve Sorted= 0
DSS Export Volume Flow Curves= 0
DXF OffsetX= 0
DXF OffsetY= 0
DXF ScaleX= 1
DXF ScaleY= 10

--- THOMAS CREEK.p01 (plan) ---

Plan Title=Multiple Run
Short Identifier=Multiple
Geom File=g01
Flow File=f01
Subcritical Flow
K Sum by GR= 0
Std Step Tol= 0.01
Critical Tol= 0.01
Num of Std Step Trials= 20
Max Error Tol= 0.3
Flow Tol Ratio= 0.001
Split Flow NTrial= 30
Split Flow Tol= 0.02
Split Flow Ratio= 0.02
Log Output Level= 0
Friction Slope Method= 1
Unsteady Friction Slope Method= 2
Unsteady Bridges Friction Slope Method= 1
Parabolic Critical Depth
Global Vel Dist=  1 , 1 , 1
Global Log Level= 0
CheckData=True
Encroach Param= -1, 0, 0, 0
BEGIN DESCRIPTION:
Multiple Run
END DESCRIPTION:

--- THOMAS CREEK.f01 (steady flow) ---

Flow Title=Multiple
Number of Profiles=7
Profile Names=10-year,25-year,50-year,1pct_min,100-year,1pct_plu,500-year
River Rch & RM= THOMAS CREEK,Reach-1,70192
     512     831    1121     734    1464    2921    2474
River Rch & RM= THOMAS CREEK,Reach-1,69720
     563     918    1242     815    1627    3246    2765
River Rch & RM= THOMAS CREEK,Reach-1,68664
     908    1520    2093    1395    2784    5555    4887
River Rch & RM= THOMAS CREEK,Reach-1,65118
    1168    1987    2764    1860    3712    7406    6643
River Rch & RM= THOMAS CREEK,Reach-1,62907
    1545    2647    3702    2501    4990    9957    9000
River Rch & RM= THOMAS CREEK,Reach-1,59019
    1667    2862    4007    2709    5406   10786    9764
River Rch & RM= THOMAS CREEK,Reach-1,56123
    1681    2887    4041    2732    5452   10878    9845
River Rch & RM= THOMAS CREEK,Reach-1,54947
    2407    4199    5943    4057    8094   16150   14904
River Rch & RM= THOMAS CREEK,Reach-1,51573
    2421    4210    5945    4048    8077   16115   14799
River Rch & RM= THOMAS CREEK,Reach-1,45332
    4081    7229   10337    7118   14201   28336   26604
River Rch & RM= THOMAS CREEK,Reach-1,36856
    4944    8778   12566    8650   17259   34437   32283
River Rch & RM= THOMAS CREEK,Reach-1,26639
    5799   10341   14848   10248   20447   40797   38438
River Rch & RM= THOMAS CREEK,Reach-1,23614
    5982   10669   15321   10574   21098   42096   39661
River Rch & RM= THOMAS CREEK,Reach-1,20132
    5891   10476   15014   10341   20633   41168   38626
River Rch & RM= THOMAS CREEK,Reach-1,14046
    5901   10490   15029   10348   20646   41195   38623
River Rch & RM= THOMAS CREEK,Reach-1,11206
    5923   10527   15080   10381   20712   41326   38735
River Rch & RM= THOMAS CREEK,Reach-1,9185
    6574   11707   16794   11574   23093   46077   43280
River Rch & RM= THOMAS CREEK,Reach-1,4732
    6864   12227   17543   12091   24124   48133   45214
Boundary for River Rch & Prof#=THOMAS CREEK,Reach-1,1
Up Type=0
Dn Type=3
Dn Slope=0.001
Boundary for River Rch & Prof#=THOMAS CREEK,Reach-1,2
Up Type=0
Dn Type=3
Dn Slope=0.001
Boundary for River Rch & Prof#=THOMAS CREEK,Reach-1,3
Up Type=0
Dn Type=3
Dn Slope=0.001
Boundary for River Rch & Prof#=THOMAS CREEK,Reach-1,4
Up Type=0
Dn Type=3
Dn Slope=0.001
Boundary for River Rch & Prof#=THOMAS CREEK,Reach-1,5
Up Type=0
Dn Type=3
Dn Slope=0.001
Boundary for River Rch & Prof#=THOMAS CREEK,Reach-1,6
Up Type=0
Dn Type=3
Dn Slope=0.001
Boundary for River Rch & Prof#=THOMAS CREEK,Reach-1,7
Up Type=0
Dn Type=3
Dn Slope=0.001

--- THOMAS CREEK.g01 (geometry) ---

Geom Title=Existing Conditions

River Reach=THOMAS CREEK,Reach-1
Reach XY= 30
      2396025.00     13573425.00      2395282.29     13571524.91
      2396182.49     13569668.31      2398758.21     13566541.44
      2400308.55     13565942.14      2401000.96     13564197.67
      2401931.38     13564117.68      2403111.81     13562788.66
      2404630.46     13559022.55      2405521.88     13558273.37
      2406124.76     13555540.22      2404925.00     13553425.00
      2406069.17     13552527.30      2405678.37     13551876.28
      2407521.39     13549173.50      2407482.33     13547218.62
      2409131.23     13547217.19      2409135.00     13546635.65
      2408375.00     13546625.00      2408885.51     13546276.22
      2414134.68     13545814.22      2414778.75     13542076.55
      2416719.89     13540627.29      2417130.45     13538222.55
      2418267.23     13538078.41      2417691.19     13537308.33
      2419527.47     13536919.55      2419880.84     13536127.05
      2421559.78     13536574.51      2422925.00     13535725.00

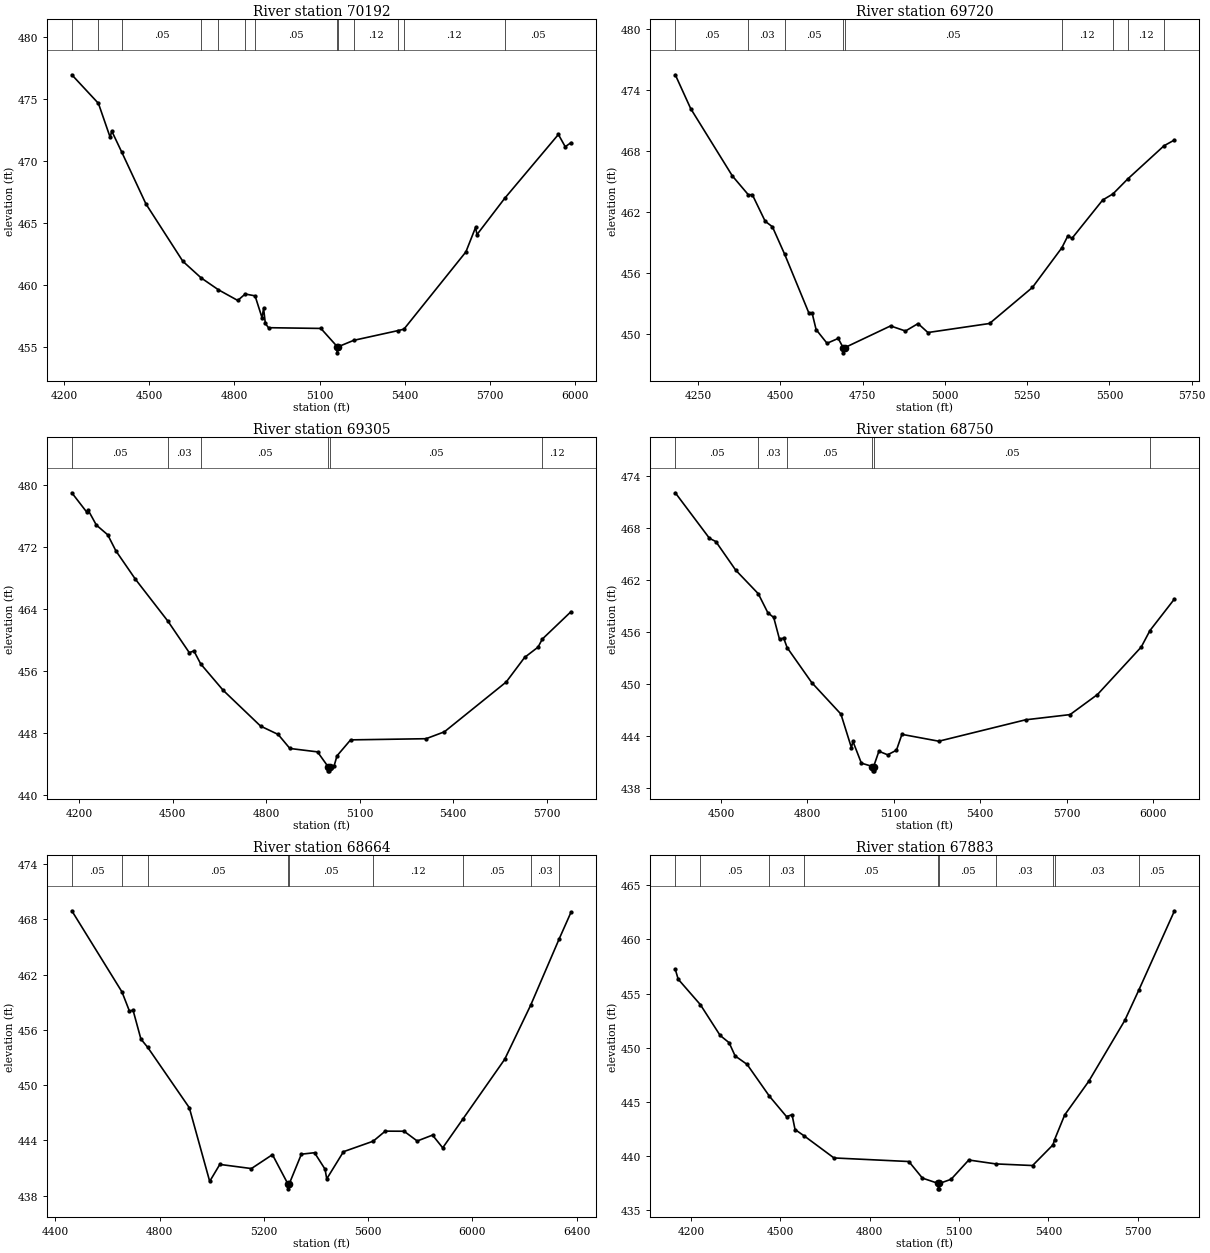
Type RM Length L Ch R = 1,70192,472,472,472
BEGIN DESCRIPTION:
LGII4671
END DESCRIPTION:
XS GIS Cut Line= 3
      2396621.01     13572901.85      2395921.23     13573232.51
      2394975.44     13573501.64
#Sta/Elev= 30
  4227.7  476.94  4321.4  474.63  4362.7  471.89  4368.2  472.40  4403.4  470.70
  4488.7  466.51  4618.6  461.88  4683.0  460.54  4743.9  459.58  4811.8  458.72
  4838.1  459.24  4872.8  459.09  4897.3  457.33  4902.8  458.08  4909.0  456.86
  4920.1  456.52  5104.5  456.46  5162.1  454.99  5162.4  454.49  5166.1  454.99
  5220.2  455.50  5375.0  456.28  5396.8  456.40  5615.0  462.64  5648.9  464.61
  5654.1  464.04  5751.4  466.96  5940.6  472.12  5964.7  471.13  5985.0  471.46
#Mann=13,-1,0
  4227.7    0.05       0  4321.4   0.013       0  4403.4    0.05       0
  4683.0   0.013       0  4743.9    0.05       0  4838.1   0.013       0
  4872.8    0.05       0  5162.1    0.05       0  5166.1    0.05       0
  5220.2    0.12       0  5375.0    0.05       0  5396.8    0.12       0
  5751.4    0.05       0
Bank Sta=5162.1,5166.1
Exp/Cntr=0.3,0.1

Type RM Length L Ch R = 1,69720,415,415,415
BEGIN DESCRIPTION:
LGII4670
END DESCRIPTION:
XS GIS Cut Line= 3
      2396451.77     13572509.72      2395544.45     13572940.32
      2395138.46     13573254.38
#Sta/Elev= 30
  4180.2  475.48  4227.0  472.15  4353.7  465.52  4402.4  463.66  4414.3  463.68
  4453.4  461.06  4475.5  460.51  4512.8  457.80  4586.2  452.03  4596.2  452.01
  4608.3  450.39  4641.5  449.04  4675.5  449.52  4690.7  448.60  4690.9  448.10
  4694.7  448.60  4834.6  450.75  4880.0  450.25  4918.2  450.98  4948.2  450.10
  5135.6  450.99  5265.9  454.54  5355.5  458.45  5373.5  459.61  5386.3  459.38
  5479.6  463.15  5510.8  463.75  5555.3  465.21  5666.0  468.49  5697.8  469.06
#Mann=9,-1,0
  4180.2    0.05       0  4402.4    0.03       0  4512.8    0.05       0
  4690.7    0.05       0  4694.7    0.05       0  5355.5    0.12       0
  5510.8    0.05       0  5555.3    0.12       0  5666.0    0.05       0
Bank Sta=4690.7,4694.7
Exp/Cntr=0.3,0.1

Type RM Length L Ch R = 1,69305,555,555,555
BEGIN DESCRIPTION:
LGII4669
END DESCRIPTION:
XS GIS Cut Line= 3
      2396451.78     13572263.65      2395506.00     13572586.60
      2395206.10     13573109.51
#Sta/Elev= 30
  4176.3  479.04  4223.7  476.57  4228.9  476.79  4255.0  474.87  4291.6  473.61
  4317.6  471.55  4380.3  467.88  4485.0  462.44  4553.3  458.39  4568.2  458.61
  4590.0  456.93  4662.2  453.52  4782.2  448.90  4838.6  447.82  4876.2  446.01
  4964.9  445.57  4999.5  443.62  4999.7  443.12  5003.2  443.12  5003.5  443.62
  5018.2  443.77  5027.5  445.06  5071.1  447.12  5313.2  447.27  5372.1  448.16
  5570.6  454.60  5629.6  457.77  5672.7  459.10  5686.4  460.14  5778.5  463.68
#Mann=6,-1,0
  4176.3    0.05       0  4485.0    0.03       0  4590.0    0.05       0
  4999.5    0.05       0  5003.5    0.05       0  5686.4    0.12       0
Bank Sta=4999.5,5003.5
Exp/Cntr=0.3,0.1

Type RM Length L Ch R = 1,68750,86,86,86
BEGIN DESCRIPTION:
LGII4668
END DESCRIPTION:
XS GIS Cut Line= 4
      2396351.80     13572086.79      2395452.17     13572240.58
      2395352.21     13572417.43      2395206.12     13573017.17
#Sta/Elev= 30
  4341.7  472.02  4460.2  466.77  4482.5  466.39  4551.5  463.09  4629.8  460.37
  4663.1  458.17  4683.4  457.63  4703.7  455.09  4717.9  455.26  4730.0  454.15
  4815.3  450.12  4916.7  446.48  4953.2  442.60  4958.3  443.34  4987.7  440.82
  5026.3  440.43  5026.6  439.93  5030.1  439.93  5030.3  440.43  5048.6  442.19
  5079.0  441.78  5109.5  442.31  5128.5  444.14  5256.6  443.35  5557.9  445.82
  5712.3  446.42  5807.5  448.74  5959.4  454.22  5989.6  456.12  6074.8  459.77
#Mann=6,-1,0
  4341.7    0.05       0  4629.8    0.03       0  4730.0    0.05       0
  5026.3    0.05       0  5030.3    0.05       0  5989.6    0.12       0
Bank Sta=5026.3,5030.3
Exp/Cntr=0.3,0.1

Type RM Length L Ch R = 1,68664,781,781,781
BEGIN DESCRIPTION:
THOMAS CREEK 97.0
END DESCRIPTION:
XS GIS Cut Line= 3
      2396257.63     13572189.48      2395025.00     13572025.00
      2394424.98     13571724.99
#Sta/Elev= 30
  4463.5  468.92  4655.8  460.12  4684.7  458.02  4698.2  458.15  4728.5  455.00
  4754.6  454.10  4914.1  447.55  4992.3  439.56  5031.1  441.40  5152.2  440.95
  5232.9  442.46  5292.8  439.25  5293.1  438.75  5296.8  439.25  5343.9  442.51
  5394.3  442.67  5434.7  440.88  5441.1  439.83  5505.3  442.78  5619.3  443.92
  5665.5  445.01  5737.8  445.00  5788.1  443.94  5846.8  444.58  5885.9  443.20
  5963.4  446.33  6123.5  452.80  6223.0  458.66  6333.0  465.90  6377.9  468.76
#Mann=9,-1,0
  4463.5    0.05       0  4655.8    0.03       0  4754.6    0.05       0
  5292.8    0.05       0  5296.8    0.05       0  5619.3    0.12       0
  5963.4    0.05       0  6223.0    0.03       0  6333.0    0.05       0
Bank Sta=5292.8,5296.8
Exp/Cntr=0.3,0.1

Type RM Length L Ch R = 1,67883,359,359,359
BEGIN DESCRIPTION:
Mapping XS d603ce26
END DESCRIPTION:
XS GIS Cut Line= 3
      2396214.67     13571770.27      2395025.38     13571640.16
      2394549.30     13571580.46
#Sta/Elev= 30
  4147.3  457.24  4157.0  456.33  4231.5  453.98  4297.9  451.14  4328.0  450.47
  4348.2  449.25  4388.4  448.47  4463.5  445.53  4520.9  443.65  4539.3  443.83
  4549.4  442.46  4579.8  441.88  4680.1  439.84  4931.6  439.51  4977.1  437.98
  5030.1  437.49  5030.4  436.99  5034.1  436.99  5034.4  437.49  5073.4  437.87
  5132.8  439.65  5223.4  439.29  5347.0  439.14  5415.6  441.05  5420.8  441.52
  5454.9  443.81  5535.6  446.91  5656.5  452.52  5704.0  455.34  5823.5  462.64
#Mann=10,-1,0
  4147.3    0.12       0  4231.5    0.05       0  4463.5    0.03       0
  4579.8    0.05       0  5030.1    0.05       0  5034.4    0.05       0
  5223.4    0.03       0  5415.6    0.12       0  5420.8    0.03       0
  5704.0    0.05       0
Bank Sta=5030.1,5034.4
Exp/Cntr=0.3,0.1

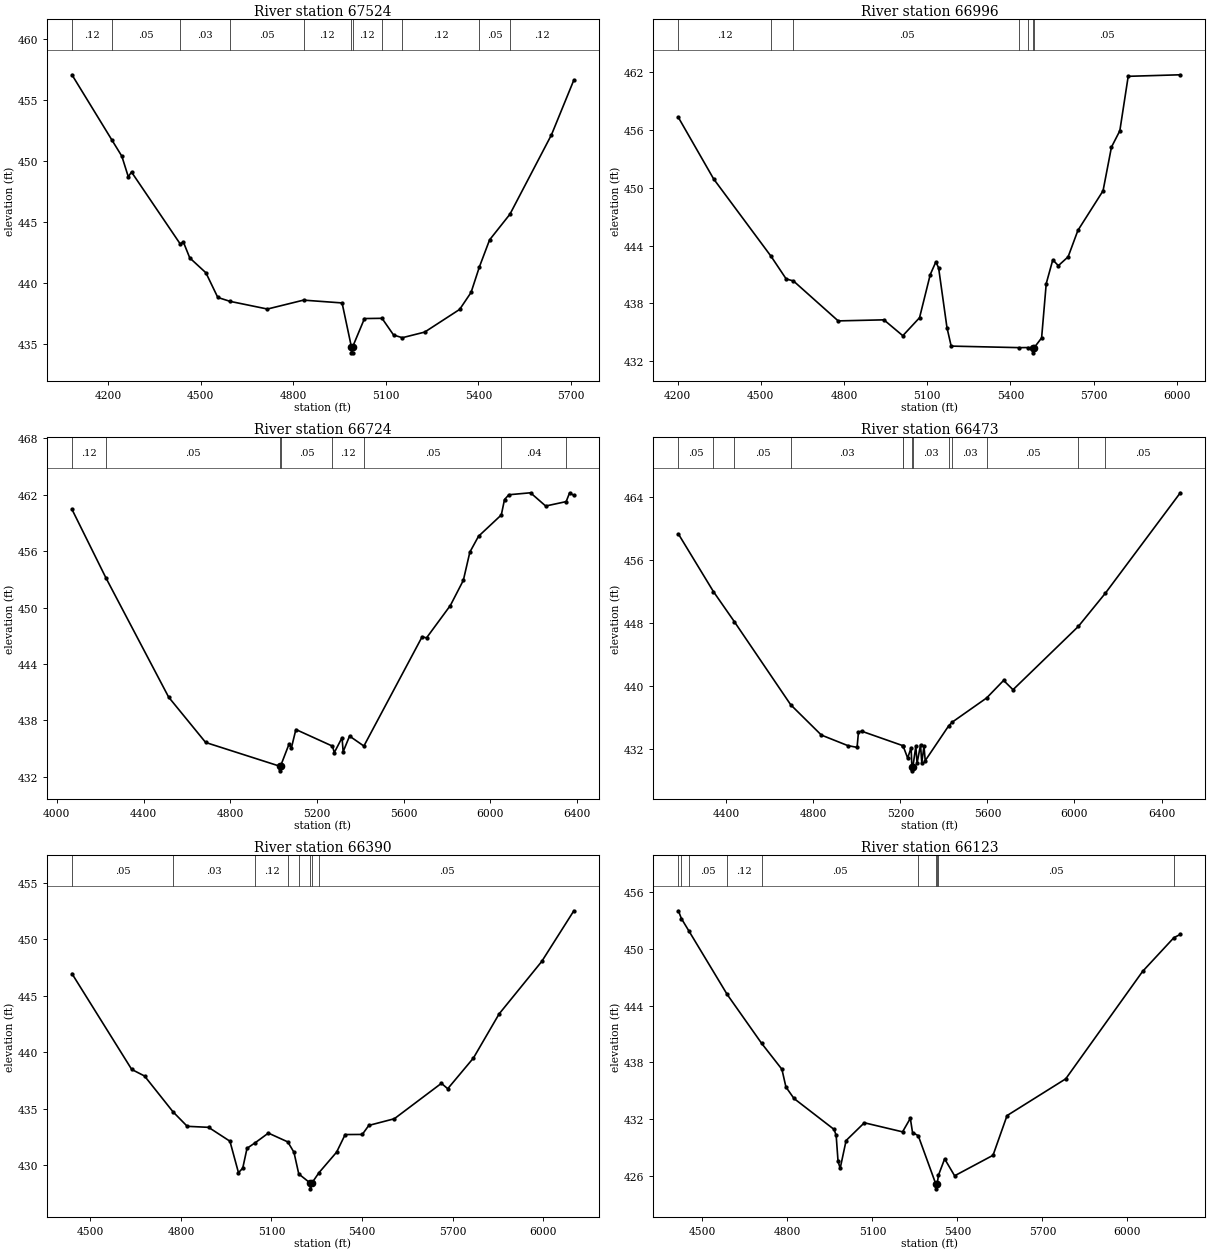
Type RM Length L Ch R = 1,67524,528,528,528
BEGIN DESCRIPTION:
Mapping XS 4bf6456f
END DESCRIPTION:
XS GIS Cut Line= 3
      2396279.11     13571673.52      2395275.04     13571355.02
      2394702.60     13571397.63
#Sta/Elev= 30
  4082.2  457.03  4211.8  451.68  4243.9  450.36  4264.9  448.67  4275.3  449.06
  4433.4  443.16  4443.2  443.34  4464.2  442.02  4516.6  440.80  4555.1  438.78
  4594.7  438.46  4716.0  437.83  4833.0  438.56  4958.1  438.33  4988.2  434.74
  4988.5  434.24  4992.2  434.24  4992.5  434.74  5030.7  437.05  5087.6  437.07
  5125.1  435.70  5153.4  435.48  5225.9  435.94  5339.3  437.80  5376.3  439.19
  5403.4  441.29  5436.4  443.50  5502.3  445.60  5637.0  452.11  5709.6  456.60
#Mann=11,-1,0
  4082.2    0.12       0  4211.8    0.05       0  4433.4    0.03       0
  4594.7    0.05       0  4833.0    0.12       0  4988.2    0.05       0
  4992.5    0.12       0  5087.6    0.05       0  5153.4    0.12       0
  5403.4    0.05       0  5502.3    0.12       0
Bank Sta=4988.2,4992.5
Exp/Cntr=0.3,0.1

Type RM Length L Ch R = 1,66996,272,272,272
BEGIN DESCRIPTION:
Mapping XS 747e0971
END DESCRIPTION:
XS GIS Cut Line= 4
      2396393.77     13571454.95      2395652.10     13571103.82
      2395146.90     13571060.83      2394668.41     13571117.96
#Sta/Elev= 30
  4203.3  457.31  4330.4  450.92  4537.6  442.87  4591.8  440.53  4618.0  440.32
  4779.3  436.17  4944.1  436.28  5012.3  434.63  5072.6  436.50  5111.3  440.99
  5131.4  442.30  5141.4  441.68  5171.5  435.47  5186.7  433.55  5432.7  433.39
  5464.0  433.40  5480.4  433.35  5480.7  432.85  5484.9  433.35  5512.7  434.40
  5529.4  440.05  5553.0  442.51  5573.1  441.91  5608.3  442.83  5643.6  445.58
  5734.2  449.69  5764.5  454.23  5794.7  455.93  5824.9  461.59  6012.8  461.75
#Mann=7,-1,0
  4203.3    0.12       0  4537.6    0.03       0  4618.0    0.05       0
  5432.7    0.12       0  5464.0    0.05       0  5480.4    0.05       0
  5484.9    0.05       0
Bank Sta=5480.4,5484.9
Exp/Cntr=0.3,0.1

Type RM Length L Ch R = 1,66724,251,251,251
BEGIN DESCRIPTION:
Mapping XS 059797c3
END DESCRIPTION:
XS GIS Cut Line= 4
      2396504.90     13571340.33      2395942.33     13570913.93
      2395225.73     13570731.19      2394355.04     13570720.44
#Sta/Elev= 30
  4069.6  460.46  4226.4  453.16  4516.0  440.46  4686.6  435.64  5027.7  433.12
  5028.0  432.62  5032.2  433.12  5070.8  435.43  5082.4  435.07  5103.0  437.02
  5271.8  435.25  5280.3  434.56  5316.0  436.15  5321.2  434.66  5350.7  436.32
  5416.8  435.26  5685.8  446.90  5705.8  446.77  5815.8  450.22  5875.8  452.90
  5905.8  455.90  5945.8  457.59  6051.0  459.86  6065.8  461.50  6085.8  462.01
  6185.8  462.22  6255.8  460.81  6350.3  461.28  6365.8  462.19  6385.8  461.95
#Mann=8,-1,0
  4069.6    0.12       0  4226.4    0.05       0  5027.7    0.05       0
  5032.2    0.05       0  5271.8    0.12       0  5416.8    0.05       0
  6051.0    0.04       0  6350.3    0.05       0
Bank Sta=5027.7,5032.2
Exp/Cntr=0.3,0.1

Type RM Length L Ch R = 1,66473,83,83,83
BEGIN DESCRIPTION:
Mapping XS 5e0206f0
END DESCRIPTION:
XS GIS Cut Line= 4
      2396529.98     13571225.68      2395859.92     13570670.28
      2395268.72     13570333.48      2394559.60     13570072.03
#Sta/Elev= 30
  4179.9  459.27  4340.7  451.98  4436.9  448.17  4696.1  437.64  4836.8  433.81
  4957.9  432.48  5000.9  432.25  5007.4  434.19  5021.7  434.30  5212.1  432.46
  5212.3  432.44  5233.4  430.90  5249.3  432.22  5252.7  429.78  5253.1  429.28
  5257.3  429.78  5270.9  432.39  5276.6  430.24  5292.5  432.56  5298.3  430.30
  5308.4  432.41  5314.1  430.57  5421.9  434.98  5438.9  435.46  5596.4  438.51
  5674.3  440.73  5717.5  439.55  6017.5  447.56  6142.4  451.79  6486.4  464.49
#Mann=13,-1,0
  4179.9    0.05       0  4340.7    0.12       0  4436.9    0.05       0
  4696.1    0.03       0  5212.1    0.05       0  5212.3    0.03       0
  5252.7    0.03       0  5257.3    0.03       0  5421.9    0.05       0
  5438.9    0.03       0  5596.4    0.05       0  6017.5    0.03       0
  6142.4    0.05       0
Bank Sta=5252.7,5257.3
Exp/Cntr=0.3,0.1

Type RM Length L Ch R = 1,66390,267,267,267
BEGIN DESCRIPTION:
THOMAS CREEK 95.0
END DESCRIPTION:
XS GIS Cut Line= 3
      2396325.02     13571025.02      2395725.00     13570425.00
      2395125.00     13569875.00
#Sta/Elev= 30
  4439.1  446.96  4637.1  438.47  4679.5  437.89  4774.0  434.71  4821.0  433.43
  4891.7  433.34  4962.4  432.11  4990.7  429.32  5004.8  429.72  5019.0  431.48
  5046.9  431.99  5089.7  432.83  5154.0  432.05  5174.5  431.13  5190.4  429.21
  5228.8  428.39  5229.1  427.89  5233.4  428.39  5257.3  429.32  5315.7  431.14
  5344.1  432.70  5400.8  432.71  5422.4  433.51  5506.9  434.10  5662.9  437.24
  5683.8  436.76  5768.9  439.48  5854.0  443.39  5995.2  448.04  6101.6  452.53
#Mann=8,-1,0
  4439.1    0.05       0  4774.0    0.03       0  5046.9    0.12       0
  5154.0    0.05       0  5190.4    0.12       0  5228.8    0.03       0
  5233.4    0.12       0  5257.3    0.05       0
Bank Sta=5228.8,5233.4
Exp/Cntr=0.3,0.1

Type RM Length L Ch R = 1,66123,349,349,349
BEGIN DESCRIPTION:
Mapping XS 5cdb1c44
END DESCRIPTION:
XS GIS Cut Line= 4
      2396522.76     13570903.16      2396046.24     13570372.89
      2395655.69     13570050.42      2395154.02     13569821.09
#Sta/Elev= 30
  4415.6  454.03  4426.0  453.21  4453.1  451.87  4587.6  445.18  4708.8  440.02
  4780.8  437.26  4795.0  435.38  4823.4  434.17  4964.7  430.90  4972.2  430.27
  4978.9  427.51  4986.4  426.78  5007.3  429.72  5071.6  431.60  5206.5  430.64
  5233.9  432.07  5241.7  430.57  5261.9  430.23  5324.0  425.11  5324.3  424.61
  5328.6  425.11  5333.3  426.06  5355.0  427.78  5390.2  425.99  5525.7  428.16
  5575.2  432.36  5782.3  436.25  6053.6  447.62  6164.1  451.19  6186.6  451.53
#Mann=10,-1,0
  4415.6    0.05       0  4426.0    0.12       0  4453.1    0.05       0
  4587.6    0.12       0  4708.8    0.05       0  5261.9    0.12       0
  5324.0    0.05       0  5328.6    0.12       0  5333.3    0.05       0
  6164.1    0.03       0
Bank Sta=5324,5328.6
Exp/Cntr=0.3,0.1

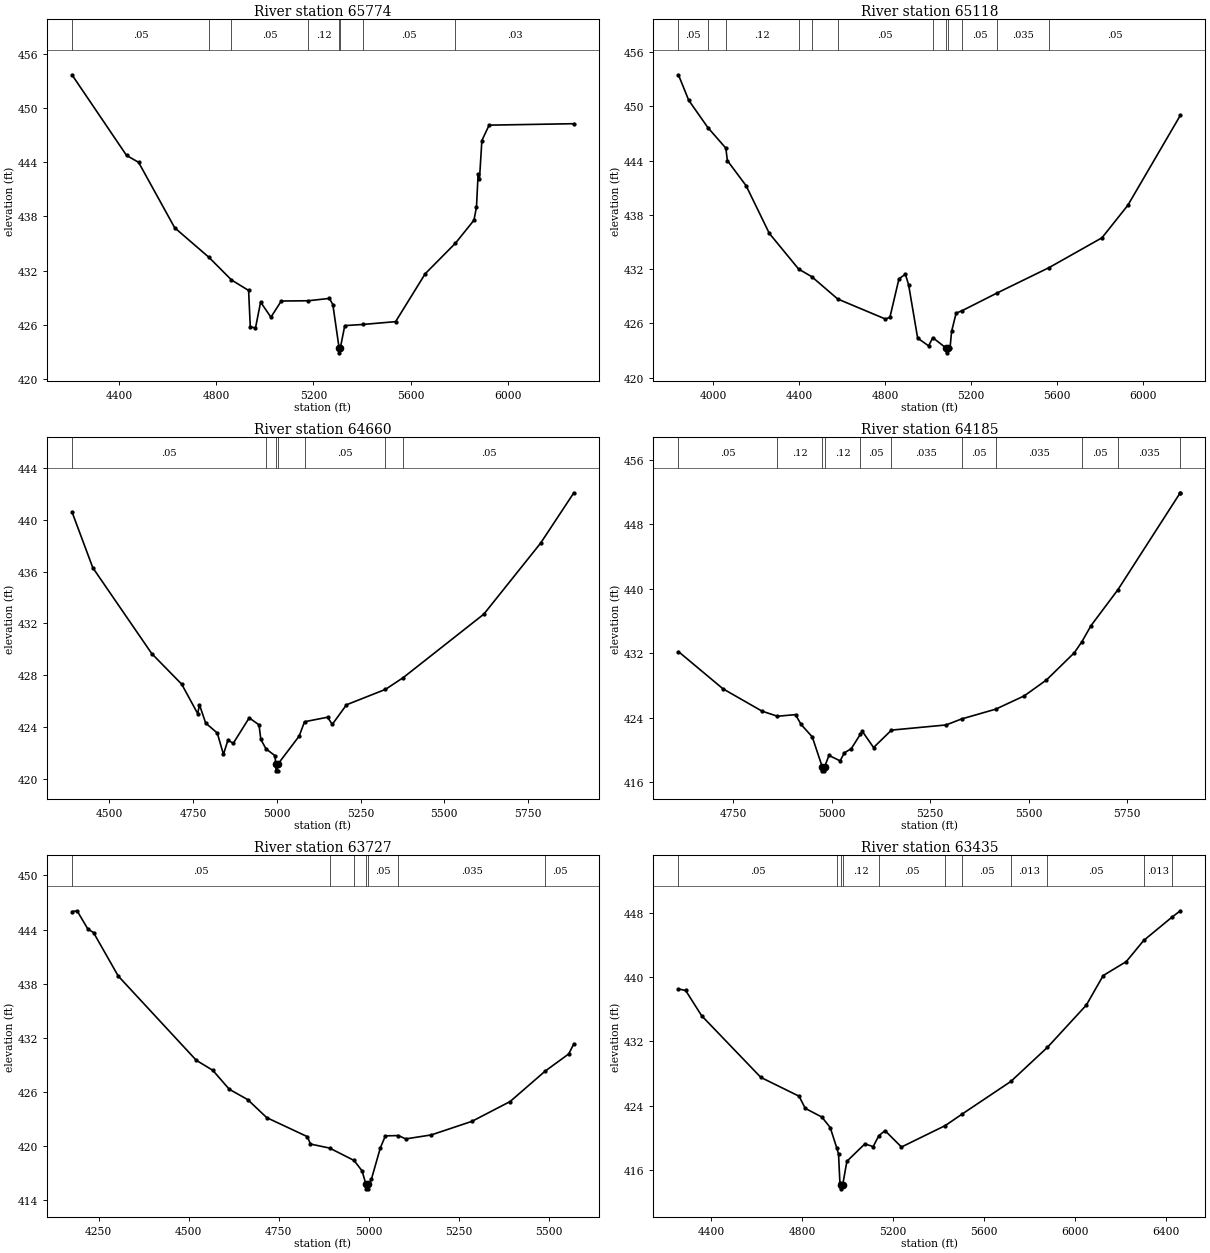
Type RM Length L Ch R = 1,65774,656,656,656
BEGIN DESCRIPTION:
Mapping XS 069e5b01
END DESCRIPTION:
XS GIS Cut Line= 3
      2396777.18     13570720.46      2396006.82     13569925.01
      2395144.00     13569509.71
#Sta/Elev= 30
  4206.6  453.66  4431.3  444.74  4480.7  443.98  4629.3  436.74  4770.7  433.46
  4862.9  430.97  4933.4  429.81  4940.3  425.79  4961.7  425.66  4982.8  428.52
  5025.2  426.85  5067.7  428.64  5179.1  428.67  5265.7  428.93  5279.9  428.25
  5305.9  423.41  5306.2  422.91  5310.5  423.41  5329.0  425.92  5404.3  426.05
  5538.2  426.36  5660.0  431.66  5783.9  435.02  5860.6  437.58  5870.9  439.04
  5877.6  442.67  5883.2  442.09  5893.1  446.39  5922.9  448.09  6271.5  448.25
#Mann=8,-1,0
  4206.6    0.05       0  4770.7    0.12       0  4862.9    0.05       0
  5179.1    0.12       0  5305.9    0.05       0  5310.5    0.12       0
  5404.3    0.05       0  5783.9    0.03       0
Bank Sta=5305.9,5310.5
Exp/Cntr=0.3,0.1

Type RM Length L Ch R = 1,65118,458,458,458
BEGIN DESCRIPTION:
Mapping XS ce9c2a4d
END DESCRIPTION:
XS GIS Cut Line= 3
      2396927.68     13570638.07      2396259.64     13569640.38
      2395451.43     13568842.92
#Sta/Elev= 30
  3838.7  453.49  3886.5  450.68  3975.5  447.66  4059.4  445.38  4066.6  444.00
  4153.7  441.23  4261.7  435.96  4398.3  432.01  4459.3  431.17  4580.3  428.70
  4802.1  426.49  4823.1  426.68  4865.3  430.94  4895.2  431.44  4910.2  430.26
  4952.2  424.38  5003.3  423.52  5022.7  424.43  5086.0  423.25  5086.5  422.75
  5091.7  423.25  5103.0  423.29  5110.1  425.11  5131.3  427.14  5160.0  427.42
  5322.3  429.37  5564.5  432.18  5810.2  435.47  5930.4  439.06  6174.8  449.00
#Mann=12,-1,0
  3838.7    0.05       0  3975.5    0.03       0  4059.4    0.12       0
  4398.3    0.05       0  4459.3    0.12       0  4580.3    0.05       0
  5022.7     0.1       0  5086.0    0.05       0  5091.7     0.1       0
  5160.0    0.05       0  5322.3   0.035       0  5564.5    0.05       0
Bank Sta=5086,5091.7
Exp/Cntr=0.3,0.1

Type RM Length L Ch R = 1,64660,475,475,475
BEGIN DESCRIPTION:
THOMAS CREEK 92.0
END DESCRIPTION:
XS GIS Cut Line= 3
      2397074.99     13569625.00      2396475.00     13569375.00
      2395875.01     13568775.01
#Sta/Elev= 30
  4388.3  440.62  4450.6  436.30  4626.6  429.67  4716.0  427.31  4763.7  425.04
  4769.1  425.72  4787.5  424.31  4822.2  423.54  4840.6  421.89  4854.1  423.00
  4869.8  422.74  4917.5  424.71  4946.8  424.17  4952.2  423.05  4967.6  422.32
  4994.4  421.79  4996.9  421.12  4997.4  420.62  5002.2  420.62  5002.7  421.12
  5066.6  423.30  5082.7  424.41  5151.4  424.76  5165.6  424.21  5208.0  425.72
  5324.3  426.91  5377.0  427.81  5618.1  432.72  5787.8  438.21  5886.8  442.09
#Mann=7,-1,0
  4388.3    0.05       0  4967.6    0.12       0  4996.9    0.05       0
  5002.7    0.12       0  5082.7    0.05       0  5324.3   0.035       0
  5377.0    0.05       0
Bank Sta=4996.9,5002.7
Exp/Cntr=0.3,0.1

Type RM Length L Ch R = 1,64185,458,458,458
BEGIN DESCRIPTION:
THOMAS CREEK 91.0
END DESCRIPTION:
XS GIS Cut Line= 3
      2397074.98     13569324.98      2396775.00     13569025.00
      2396174.98     13568424.98
#Sta/Elev= 30
  4611.5  432.21  4724.6  427.59  4823.6  424.82  4862.7  424.19  4908.5  424.39
  4922.6  423.17  4950.9  421.63  4976.2  417.92  4976.7  417.42  4981.7  417.42
  4982.2  417.92  4993.3  419.33  5021.6  418.66  5032.2  419.65  5049.9  420.17
  5073.0  421.97  5078.2  422.30  5106.4  420.31  5151.8  422.47  5290.3  423.11
  5329.4  423.85  5416.2  425.07  5488.3  426.71  5544.9  428.69  5615.6  432.07
  5634.8  433.44  5658.0  435.44  5725.9  439.87  5884.1  451.90  5884.3  451.90
#Mann=11,-1,0
  4611.5    0.05       0  4862.7    0.12       0  4976.2    0.05       0
  4982.2    0.12       0  5073.0    0.05       0  5151.8   0.035       0
  5329.4    0.05       0  5416.2   0.035       0  5634.8    0.05       0
  5725.9   0.035       0  5884.1    0.05       0
Bank Sta=4976.2,4982.2
Exp/Cntr=0.3,0.1

Type RM Length L Ch R = 1,63727,292,292,292
BEGIN DESCRIPTION:
THOMAS CREEK 90.0
END DESCRIPTION:
XS GIS Cut Line= 3
      2397374.99     13569424.99      2397025.00     13568675.00
      2396625.01     13568275.01
#Sta/Elev= 30
  4176.2  445.99  4190.4  446.08  4220.3  444.06  4236.1  443.66  4304.7  438.84
  4521.4  429.49  4567.2  428.38  4612.9  426.28  4664.1  425.13  4716.9  423.13
  4829.6  421.02  4838.3  420.20  4891.6  419.75  4959.3  418.38  4981.8  417.21
  4992.2  415.73  4992.7  415.23  4997.7  415.23  4998.2  415.73  5007.4  416.28
  5032.1  419.75  5046.3  421.11  5082.4  421.14  5102.8  420.77  5173.5  421.21
  5286.7  422.72  5392.7  424.92  5490.1  428.30  5555.4  430.20  5569.5  431.33
#Mann=7,-1,0
  4176.2    0.05       0  4891.6    0.12       0  4959.3    0.05       0
  4992.2    0.05       0  4998.2    0.05       0  5082.4   0.035       0
  5490.1    0.05       0
Bank Sta=4992.2,4998.2
Exp/Cntr=0.3,0.1

Type RM Length L Ch R = 1,63435,528,528,528
BEGIN DESCRIPTION:
Mapping XS 7c59c141
END DESCRIPTION:
XS GIS Cut Line= 4
      2397500.94     13569376.86      2397468.69     13568918.19
      2396856.00     13567929.28      2396559.30     13567425.26
#Sta/Elev= 30
  4254.7  438.52  4286.6  438.33  4356.8  435.19  4617.5  427.50  4785.5  425.16
  4812.6  423.65  4885.9  422.56  4922.5  421.26  4951.7  418.68  4959.1  417.95
  4965.3  414.30  4971.5  414.12  4972.0  413.62  4977.5  414.12  4995.8  417.05
  5074.9  419.22  5111.5  418.88  5136.3  420.24  5163.6  420.87  5235.9  418.83
  5428.6  421.50  5502.0  422.92  5717.2  427.00  5878.2  431.25  6049.2  436.51
  6123.4  440.19  6224.9  441.93  6301.5  444.56  6426.2  447.47  6462.7  448.26
#Mann=11,-1,0
  4254.7    0.05       0  4951.7    0.12       0  4971.5    0.05       0
  4977.5    0.12       0  5136.3    0.05       0  5428.6   0.035       0
  5502.0    0.05       0  5717.2   0.013       0  5878.2    0.05       0
  6301.5   0.013       0  6426.2    0.05       0
Bank Sta=4971.5,4977.5
Exp/Cntr=0.3,0.1

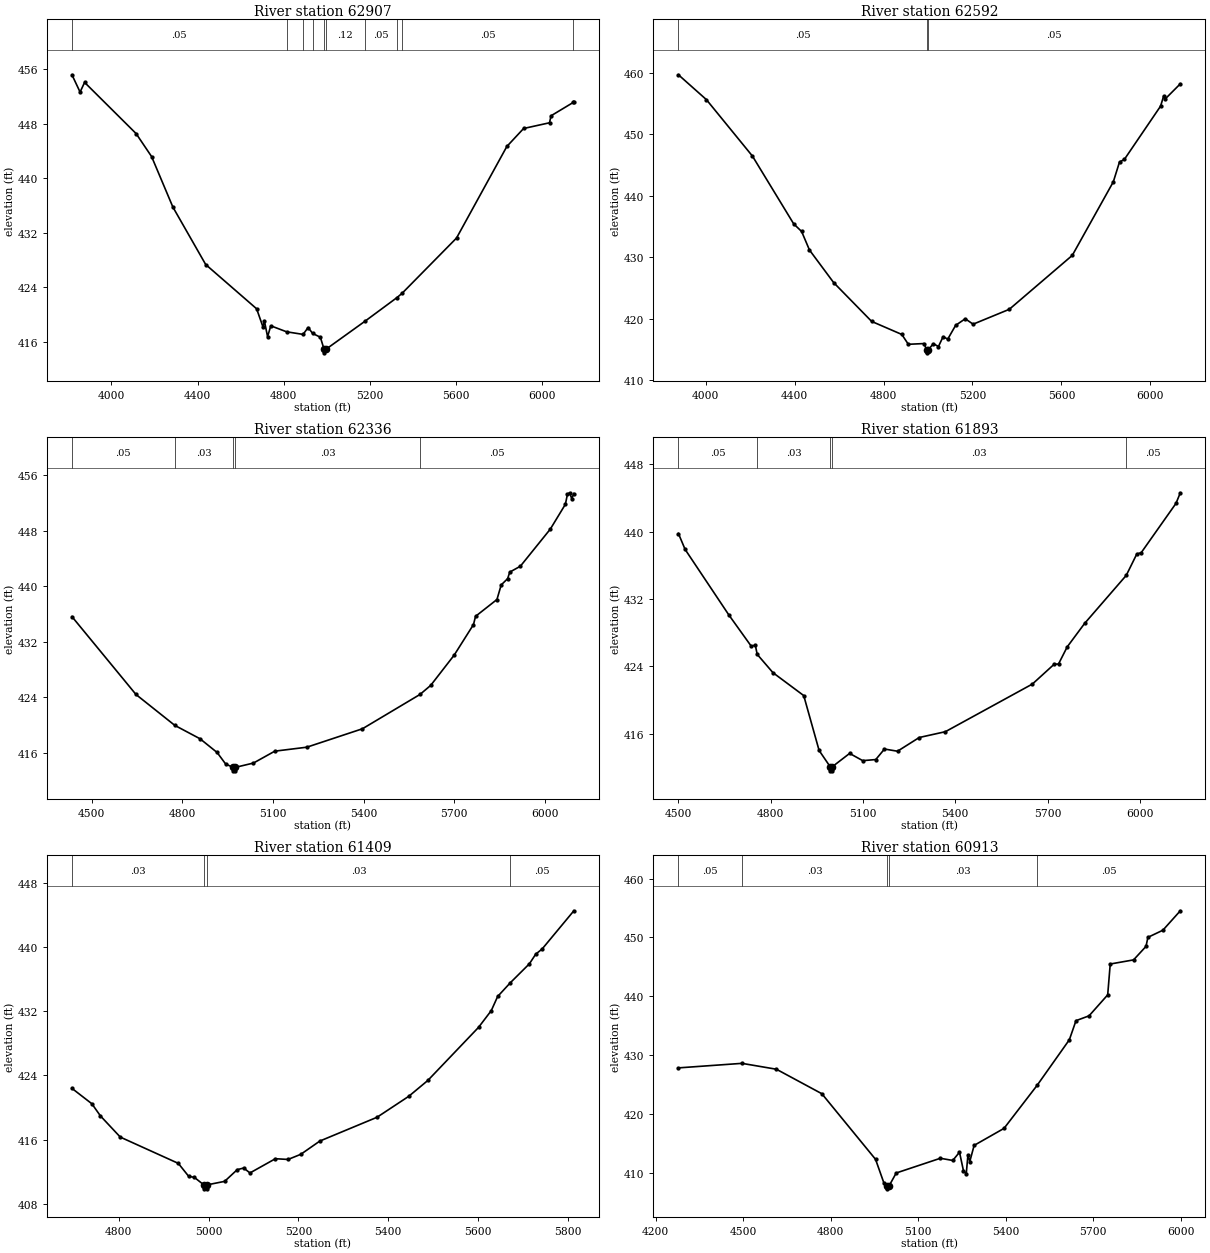
Type RM Length L Ch R = 1,62907,315,315,315
BEGIN DESCRIPTION:
Mapping XS 3d07d5c2
END DESCRIPTION:
XS GIS Cut Line= 3
      2398450.46     13568921.79      2397404.20     13568205.17
      2396681.52     13567428.83
#Sta/Elev= 30
  3817.1  455.21  3854.8  452.67  3875.8  454.09  4114.6  446.58  4186.6  443.20
  4285.4  435.78  4437.7  427.34  4674.0  420.84  4703.8  418.14  4709.8  419.09
  4724.8  416.74  4739.7  418.34  4813.0  417.46  4889.5  417.08  4913.0  418.09
  4933.9  417.22  4969.8  416.66  4987.1  414.87  4987.6  414.37  4994.6  414.87
  5176.2  419.00  5325.0  422.48  5348.8  423.11  5601.5  431.23  5835.0  444.68
  5912.7  447.32  6032.9  448.16  6040.2  449.19  6144.2  451.17  6145.9  451.28
#Mann=10,-1,0
  3817.1    0.05       0  4813.0    0.12       0  4889.5    0.05       0
  4933.9    0.12       0  4987.1    0.05       0  4994.6    0.12       0
  5176.2    0.05       0  5325.0   0.013       0  5348.8    0.05       0
  6144.2   0.013       0
Bank Sta=4987.1,4994.6
Exp/Cntr=0.3,0.1

Type RM Length L Ch R = 1,62592,256,256,256
BEGIN DESCRIPTION:
Mapping XS 89f1af2b
END DESCRIPTION:
XS GIS Cut Line= 3
      2398626.04     13568789.23      2397615.59     13568040.35
      2396870.32     13567373.90
#Sta/Elev= 30
  3877.5  459.66  4003.3  455.62  4210.4  446.44  4396.1  435.41  4431.6  434.18
  4467.0  431.16  4575.6  425.87  4746.7  419.55  4882.3  417.43  4911.6  415.83
  4982.5  415.95  4993.4  414.94  4993.9  414.44  5000.9  414.94  5024.2  415.92
  5047.2  415.47  5068.0  417.07  5088.9  416.67  5124.4  418.91  5167.6  419.98
  5203.1  419.10  5365.8  421.52  5649.1  430.29  5833.6  442.25  5861.5  445.48
  5883.2  445.89  6046.2  454.56  6060.4  456.24  6067.1  455.73  6135.0  458.19
#Mann=3,-1,0
  3877.5    0.05       0  4993.4    0.05       0  5000.9    0.05       0
Bank Sta=4993.4,5000.9
Exp/Cntr=0.3,0.1

Type RM Length L Ch R = 1,62336,443,443,443
BEGIN DESCRIPTION:
THOMAS CREEK 87.0
END DESCRIPTION:
XS GIS Cut Line= 3
      2398325.01     13568375.01      2397925.00     13567975.00
      2397124.99     13567224.99
#Sta/Elev= 30
  4434.3  435.62  4646.4  424.42  4774.9  419.98  4858.6  418.05  4915.1  416.08
  4943.4  414.42  4967.9  413.94  4968.4  413.44  4975.0  413.44  4975.5  413.94
  5035.4  414.56  5106.2  416.27  5212.2  416.84  5396.4  419.49  5586.8  424.42
  5622.5  425.73  5700.2  430.08  5764.2  434.48  5771.0  435.66  5841.9  438.08
  5856.0  440.18  5877.3  441.08  5884.3  442.02  5919.5  442.87  6018.7  448.21
  6068.5  451.77  6075.3  453.20  6082.6  453.43  6089.5  452.59  6096.6  453.32
#Mann=5,-1,0
  4434.3    0.05       0  4774.9    0.03       0  4967.9    0.03       0
  4975.5    0.03       0  5586.8    0.05       0
Bank Sta=4967.9,4975.5
Exp/Cntr=0.3,0.1

Type RM Length L Ch R = 1,61893,484,484,484
BEGIN DESCRIPTION:
THOMAS CREEK 86.0
END DESCRIPTION:
XS GIS Cut Line= 3
      2398674.97     13568024.98      2398275.00     13567725.00
      2397475.03     13566925.03
#Sta/Elev= 30
  4500.3  439.77  4522.1  437.88  4663.8  430.12  4736.7  426.40  4750.3  426.50
  4756.3  425.42  4807.6  423.24  4907.6  420.52  4957.6  414.00  4993.3  412.08
  4993.8  411.58  5000.4  411.58  5000.9  412.08  5056.8  413.65  5099.3  412.79
  5141.7  412.92  5170.0  414.17  5212.4  413.91  5283.1  415.54  5368.0  416.23
  5650.8  421.89  5721.5  424.24  5735.7  424.27  5763.9  426.30  5820.5  429.09
  5955.9  434.80  5990.2  437.34  6004.4  437.49  6117.5  443.35  6131.6  444.61
#Mann=5,-1,0
  4500.3    0.05       0  4756.3    0.03       0  4993.3    0.03       0
  5000.9    0.03       0  5955.9    0.05       0
Bank Sta=4993.3,5000.9
Exp/Cntr=0.3,0.1

Type RM Length L Ch R = 1,61409,496,496,496
BEGIN DESCRIPTION:
THOMAS CREEK 85.0
END DESCRIPTION:
XS GIS Cut Line= 3
      2398624.99     13567425.00      2398375.00     13567325.00
      2397774.98     13566724.98
#Sta/Elev= 30
  4695.5  422.39  4739.9  420.47  4758.8  418.97  4803.2  416.32  4932.4  413.05
  4955.3  411.45  4968.3  411.30  4989.1  410.38  4989.6  409.88  4996.4  409.88
  4996.9  410.38  5035.5  410.81  5063.7  412.27  5077.9  412.47  5092.0  411.86
  5148.6  413.63  5176.9  413.54  5205.2  414.18  5247.6  415.83  5374.9  418.79
  5445.6  421.40  5488.0  423.37  5601.1  429.99  5629.4  432.07  5643.6  433.83
  5672.0  435.55  5714.3  437.90  5728.4  439.10  5742.6  439.74  5813.3  444.50
#Mann=4,-1,0
  4695.5    0.03       0  4989.1    0.03       0  4996.9    0.03       0
  5672.0    0.05       0
Bank Sta=4989.1,4996.9
Exp/Cntr=0.3,0.1

Type RM Length L Ch R = 1,60913,366,366,366
BEGIN DESCRIPTION:
Mapping XS ab5a1361
END DESCRIPTION:
XS GIS Cut Line= 3
      2399149.13     13567406.16      2398583.01     13566872.29
      2397780.44     13566377.85
#Sta/Elev= 30
  4278.2  427.84  4496.0  428.61  4614.2  427.61  4770.0  423.45  4954.1  412.31
  4982.4  408.34  4992.7  407.80  4993.2  407.30  5000.5  407.80  5024.9  409.99
  5176.2  412.49  5218.8  412.12  5241.9  413.52  5255.5  410.37  5265.0  409.84
  5270.9  413.09  5277.2  411.94  5292.1  414.68  5394.6  417.57  5507.8  424.86
  5618.6  432.62  5641.3  435.86  5686.1  436.68  5750.0  440.24  5758.7  445.48
  5838.7  446.18  5881.3  448.47  5887.9  450.01  5939.2  451.22  5999.0  454.52
#Mann=5,-1,0
  4278.2    0.05       0  4496.0    0.03       0  4992.7    0.03       0
  5000.5    0.03       0  5507.8    0.05       0
Bank Sta=4992.7,5000.5
Exp/Cntr=0.3,0.1

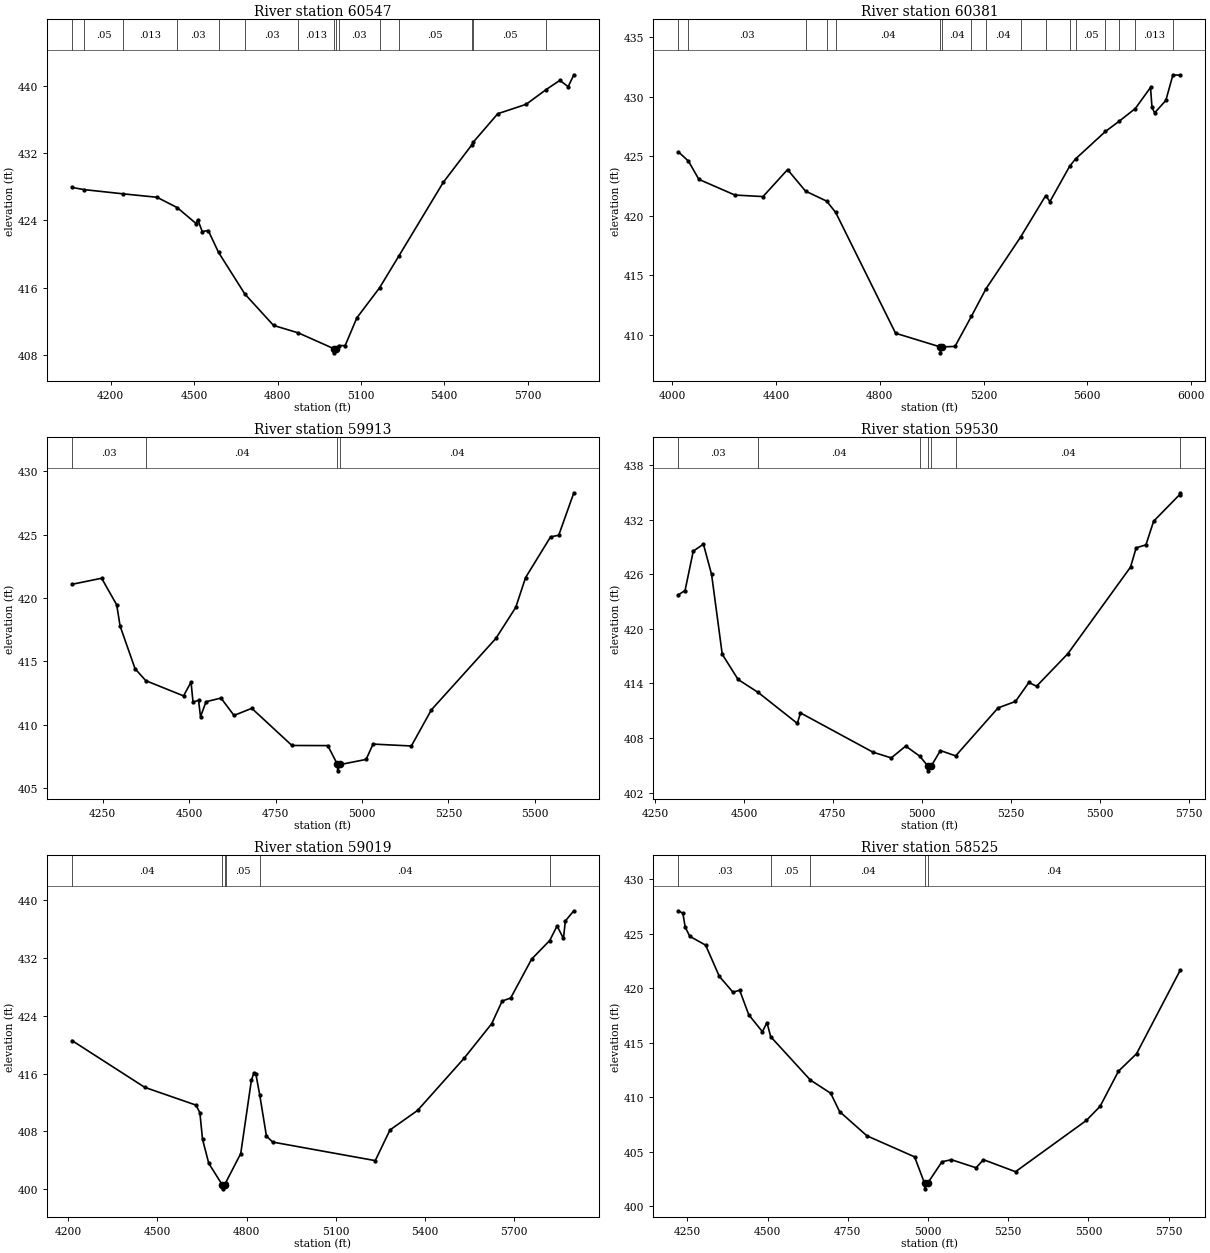
Type RM Length L Ch R = 1,60547,166,166,166
BEGIN DESCRIPTION:
Mapping XS 127e6c17
END DESCRIPTION:
XS GIS Cut Line= 3
      2399177.81     13567399.03      2398708.41     13566553.40
      2398249.91     13565851.32
#Sta/Elev= 30
  4060.4  427.92  4104.4  427.66  4244.2  427.16  4366.5  426.75  4439.2  425.52
  4507.3  423.62  4513.0  424.10  4529.0  422.68  4550.7  422.80  4587.8  420.20
  4682.3  415.26  4785.6  411.52  4874.9  410.63  5002.2  408.76  5002.7  408.26
  5010.1  408.76  5019.7  409.12  5043.3  409.12  5085.4  412.42  5166.9  415.98
  5235.6  419.72  5396.2  428.52  5500.1  433.02  5503.9  433.29  5592.3  436.68
  5694.5  437.80  5766.8  439.56  5815.5  440.64  5845.7  439.90  5866.1  441.31
#Mann=15,-1,0
  4060.4   0.013       0  4104.4    0.05       0  4244.2   0.013       0
  4439.2    0.03       0  4587.8   0.013       0  4682.3    0.03       0
  4874.9   0.013       0  5002.2    0.03       0  5010.1   0.013       0
  5019.7    0.03       0  5166.9   0.013       0  5235.6    0.05       0
  5500.1   0.013       0  5503.9    0.05       0  5766.8   0.013       0
Bank Sta=5002.2,5010.1
Exp/Cntr=0.3,0.1

Type RM Length L Ch R = 1,60381,468,468,468
BEGIN DESCRIPTION:
Mapping XS d1e433fc
END DESCRIPTION:
XS GIS Cut Line= 3
      2399360.51     13567366.72      2398826.65     13566453.07
      2398393.16     13565689.99
#Sta/Elev= 30
  4023.0  425.37  4061.5  424.60  4101.8  423.06  4240.7  421.74  4349.3  421.61
  4444.0  423.88  4513.3  422.07  4594.5  421.23  4629.4  420.28  4860.6  410.11
  5032.7  408.96  5033.2  408.46  5040.6  408.96  5089.7  409.00  5153.2  411.54
  5209.0  413.84  5342.7  418.20  5439.5  421.69  5455.9  421.19  5532.2  424.17
  5554.7  424.78  5670.0  427.09  5721.7  427.93  5785.2  429.02  5843.8  430.79
  5849.5  429.13  5859.6  428.65  5902.9  429.70  5930.4  431.86  5958.8  431.82
#Mann=17,-1,0
  4023.0    0.04       0  4061.5    0.03       0  4513.3    0.04       0
  4594.5    0.03       0  4629.4    0.04       0  5032.7    0.04       0
  5040.6    0.04       0  5153.2    0.03       0  5209.0    0.04       0
  5342.7    0.05       0  5439.5    0.04       0  5532.2   0.013       0
  5554.7    0.05       0  5670.0    0.04       0  5721.7    0.05       0
  5785.2   0.013       0  5930.4    0.04       0
Bank Sta=5032.7,5040.6
Exp/Cntr=0.3,0.1

Type RM Length L Ch R = 1,59913,383,383,383
BEGIN DESCRIPTION:
Mapping XS 3a09cc04
END DESCRIPTION:
XS GIS Cut Line= 3
      2399550.44     13566997.72      2399220.78     13566413.66
      2399135.00     13565638.06
#Sta/Elev= 30
  4161.4  421.08  4247.2  421.56  4290.8  419.46  4300.6  417.79  4343.9  414.42
  4375.0  413.48  4484.1  412.28  4505.7  413.37  4511.4  411.80  4527.4  411.93
  4533.1  410.64  4549.0  411.82  4592.3  412.11  4629.9  410.74  4681.3  411.30
  4797.4  408.37  4901.1  408.36  4929.0  406.87  4929.5  406.37  4937.5  406.87
  5011.8  407.27  5031.9  408.48  5142.6  408.33  5200.5  411.18  5387.1  416.82
  5444.4  419.26  5472.8  421.61  5545.0  424.82  5568.6  424.95  5612.4  428.30
#Mann=4,-1,0
  4161.4    0.03       0  4375.0    0.04       0  4929.0    0.04       0
  4937.5    0.04       0
Bank Sta=4929,4937.5
Exp/Cntr=0.3,0.1

Type RM Length L Ch R = 1,59530,511,511,511
BEGIN DESCRIPTION:
Mapping XS 3782bf91
END DESCRIPTION:
XS GIS Cut Line= 3
      2399847.81     13566797.03      2399536.09     13566116.27
      2399210.22     13565539.73
#Sta/Elev= 30
  4315.8  423.74  4334.5  424.21  4357.5  428.53  4386.1  429.30  4409.1  425.97
  4439.0  417.21  4483.6  414.44  4539.9  413.02  4650.1  409.62  4659.0  410.77
  4862.7  406.46  4914.2  405.83  4954.8  407.13  4994.2  406.02  5017.7  404.91
  5018.2  404.41  5026.2  404.91  5052.3  406.64  5095.2  406.05  5214.4  411.32
  5263.4  412.03  5301.0  414.11  5322.6  413.70  5410.6  417.27  5586.8  426.78
  5602.7  428.90  5630.1  429.22  5651.8  431.82  5724.9  434.74  5726.8  434.94
#Mann=7,-1,0
  4315.8    0.03       0  4539.9    0.04       0  4994.2    0.05       0
  5017.7    0.05       0  5026.2    0.05       0  5095.2    0.04       0
  5724.9    0.05       0
Bank Sta=5017.7,5026.2
Exp/Cntr=0.3,0.1

Type RM Length L Ch R = 1,59019,494,494,494
BEGIN DESCRIPTION:
Mapping XS 11dfb165
END DESCRIPTION:
XS GIS Cut Line= 3
      2400370.93     13566728.96      2399826.31     13565937.12
      2399261.15     13565479.27
#Sta/Elev= 30
  4212.7  420.59  4457.8  414.10  4630.2  411.64  4643.1  410.57  4651.9  406.92
  4672.9  403.58  4719.1  400.54  4719.6  400.04  4728.1  400.54  4729.6  400.87
  4780.5  404.93  4816.3  415.07  4824.4  416.05  4831.2  415.99  4844.6  413.00
  4867.0  407.34  4888.0  406.52  5233.0  403.95  5282.6  408.20  5375.3  410.90
  5532.0  418.14  5624.7  422.92  5659.9  426.06  5688.6  426.48  5759.0  431.87
  5819.9  434.45  5844.7  436.47  5866.1  434.73  5872.5  437.16  5901.1  438.57
#Mann=6,-1,0
  4212.7    0.04       0  4719.1    0.04       0  4728.1    0.04       0
  4729.6    0.05       0  4844.6    0.04       0  5819.9    0.05       0
Bank Sta=4719.1,4728.1
Exp/Cntr=0.3,0.1

Type RM Length L Ch R = 1,58525,516,516,516
BEGIN DESCRIPTION:
THOMAS CREEK 79.0
END DESCRIPTION:
XS GIS Cut Line= 3
      2400874.98     13566474.98      2400275.00     13565925.00
      2399675.01     13565475.01
#Sta/Elev= 30
  4222.3  427.09  4236.1  426.86  4243.5  425.59  4257.7  424.75  4307.1  423.94
  4349.6  421.09  4392.2  419.63  4413.1  419.81  4441.5  417.56  4484.0  416.01
  4498.2  416.84  4509.9  415.55  4633.4  411.58  4696.8  410.37  4724.5  408.69
  4809.6  406.47  4958.2  404.54  4989.4  402.11  4989.9  401.61  4998.5  402.11
  5043.5  404.09  5072.7  404.28  5149.8  403.54  5172.7  404.28  5272.7  403.18
  5493.5  407.88  5536.2  409.17  5593.5  412.39  5649.8  413.99  5786.2  421.66
#Mann=5,-1,0
  4222.3    0.03       0  4509.9    0.05       0  4633.4    0.04       0
  4989.4    0.04       0  4998.5    0.04       0
Bank Sta=4989.4,4998.5
Exp/Cntr=0.3,0.1