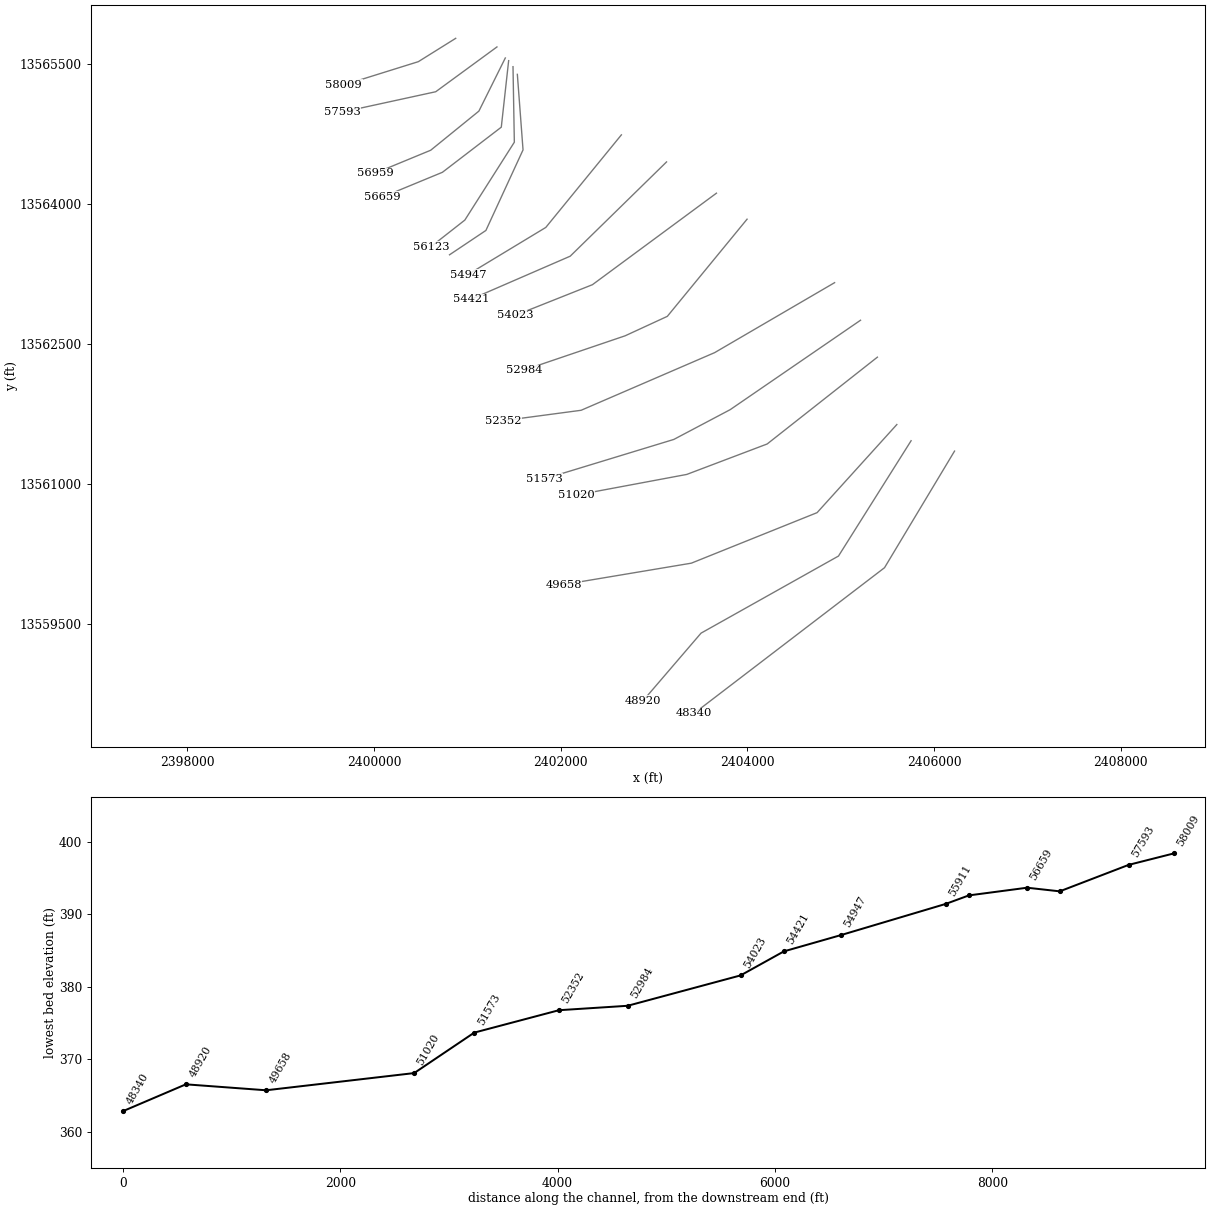
HEC-RAS study THOMAS CREEK.prj: THOMAS CREEK Base Level Engineering

--- THOMAS CREEK.g01 (geometry) --- (continued)

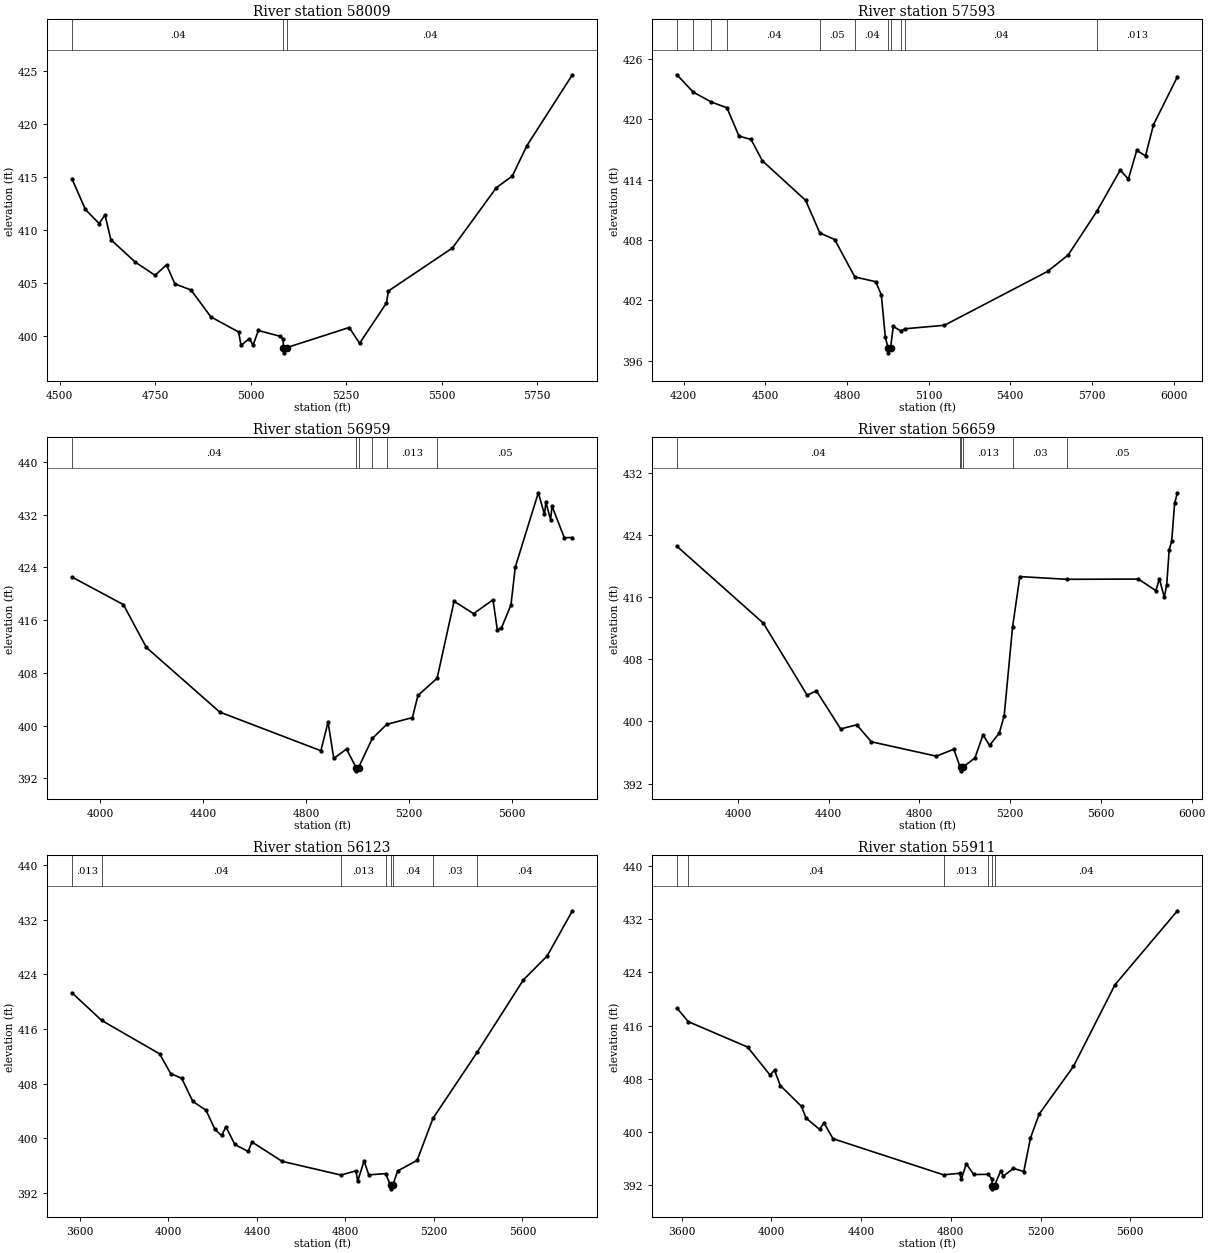
Type RM Length L Ch R = 1,58009,416,416,416
BEGIN DESCRIPTION:
THOMAS CREEK 78.0
END DESCRIPTION:
XS GIS Cut Line= 3
      2400875.02     13565775.01      2400475.00     13565525.00
      2399674.97     13565274.99
#Sta/Elev= 30
  4531.9  414.81  4567.3  411.90  4603.3  410.57  4618.6  411.39  4633.9  409.05
  4697.6  406.94  4749.5  405.69  4779.6  406.67  4801.4  404.88  4843.8  404.30
  4895.7  401.76  4968.2  400.34  4974.7  399.07  4996.0  399.71  5006.2  399.10
  5019.9  400.48  5077.0  399.93  5084.8  399.68  5085.5  398.87  5086.0  398.37
  5094.7  398.87  5257.7  400.76  5284.9  399.27  5355.1  403.07  5360.4  404.21
  5528.0  408.27  5642.7  413.95  5684.6  415.06  5722.9  417.93  5841.8  424.61
#Mann=3,-1,0
  4531.9    0.04       0  5085.5    0.04       0  5094.7    0.04       0
Bank Sta=5085.5,5094.7
Exp/Cntr=0.3,0.1

Type RM Length L Ch R = 1,57593,634,634,634
BEGIN DESCRIPTION:
Mapping XS 96a4d499
END DESCRIPTION:
XS GIS Cut Line= 3
      2401316.85     13565682.73      2400661.16     13565202.60
      2399658.95     13564984.27
#Sta/Elev= 30
  4175.6  424.42  4235.3  422.70  4301.4  421.72  4359.3  421.14  4403.7  418.32
  4447.7  418.00  4489.4  415.87  4648.4  411.94  4700.5  408.70  4755.0  408.05
  4829.0  404.33  4905.5  403.86  4926.4  402.55  4941.0  398.35  4951.0  397.29
  4951.5  396.79  4960.3  397.29  4970.3  399.41  4998.5  398.96  5012.6  399.18
  5158.3  399.53  5537.0  404.88  5612.5  406.51  5718.0  410.85  5803.7  414.95
  5833.8  414.06  5864.5  416.91  5896.7  416.36  5925.9  419.45  6014.0  424.23
#Mann=11,-1,0
  4175.6    0.05       0  4235.3    0.04       0  4301.4    0.05       0
  4359.3    0.04       0  4700.5    0.05       0  4829.0    0.04       0
  4951.0    0.05       0  4960.3    0.04       0  4998.5     0.1       0
  5012.6    0.04       0  5718.0   0.013       0
Bank Sta=4951,4960.3
Exp/Cntr=0.3,0.1

Type RM Length L Ch R = 1,56959,300,300,300
BEGIN DESCRIPTION:
Mapping XS 9cc553fe
END DESCRIPTION:
XS GIS Cut Line= 4
      2401406.44     13565564.53      2401123.36     13564994.79
      2400607.41     13564575.58      2400009.51     13564328.54
#Sta/Elev= 30
  3889.0  422.56  4089.5  418.37  4178.8  411.87  4464.4  402.06  4858.1  396.19
  4886.0  400.54  4908.3  395.02  4957.8  396.45  4995.0  393.64  4995.5  393.14
  5004.7  393.64  5058.1  398.05  5114.7  400.20  5214.2  401.22  5236.0  404.59
  5310.4  407.19  5376.5  418.88  5452.3  416.99  5528.0  419.10  5544.6  414.57
  5560.5  414.79  5597.9  418.33  5614.6  424.05  5704.3  435.34  5728.3  432.06
  5733.7  433.89  5752.2  431.27  5757.6  433.33  5805.4  428.52  5836.9  428.55
#Mann=6,-1,0
  3889.0    0.04       0  4995.0    0.04       0  5004.7    0.04       0
  5058.1    0.03       0  5114.7   0.013       0  5310.4    0.05       0
Bank Sta=4995,5004.7
Exp/Cntr=0.3,0.1

Type RM Length L Ch R = 1,56659,536,536,536
BEGIN DESCRIPTION:
Mapping XS 76f70137
END DESCRIPTION:
XS GIS Cut Line= 4
      2401442.25     13565535.80      2401363.43     13564822.80
      2400732.82     13564339.10      2400091.46     13564073.96
#Sta/Elev= 30
  3731.3  422.55  4112.6  412.64  4305.6  403.37  4345.8  403.95  4453.1  399.03
  4523.8  399.57  4588.1  397.38  4874.7  395.53  4951.6  396.42  4978.1  394.26
  4983.7  394.14  4984.2  393.64  4993.4  394.14  5045.0  395.31  5080.4  398.27
  5109.4  396.91  5152.4  398.52  5173.8  400.75  5210.6  412.14  5242.7  418.65
  5449.2  418.30  5765.2  418.33  5842.3  416.84  5857.8  418.35  5879.5  415.98
  5890.1  417.61  5901.1  422.12  5911.9  423.17  5924.9  428.07  5937.4  429.44
#Mann=6,-1,0
  3731.3    0.04       0  4978.1   0.013       0  4983.7    0.03       0
  4993.4   0.013       0  5210.6    0.03       0  5449.2    0.05       0
Bank Sta=4983.7,4993.4
Exp/Cntr=0.3,0.1

Type RM Length L Ch R = 1,56123,212,212,212
BEGIN DESCRIPTION:
Mapping XS 10cc678b
END DESCRIPTION:
XS GIS Cut Line= 4
      2401488.83     13565471.33      2401503.16     13564661.57
      2400972.88     13563826.73      2400608.73     13563541.12
#Sta/Elev= 30
  3563.8  421.33  3698.3  417.27  3960.2  412.37  4010.2  409.48  4060.2  408.77
  4110.2  405.40  4170.2  404.09  4210.2  401.30  4240.2  400.40  4260.2  401.66
  4300.2  399.08  4360.3  398.06  4377.6  399.45  4513.9  396.61  4779.9  394.60
  4847.6  395.22  4855.3  393.68  4884.1  396.69  4905.2  394.63  4981.7  394.81
  5003.7  393.08  5004.2  392.58  5013.5  393.08  5035.7  395.20  5123.8  396.75
  5195.4  402.90  5395.0  412.59  5604.1  423.21  5711.7  426.72  5825.5  433.34
#Mann=8,-1,0
  3563.8   0.013       0  3698.3    0.04       0  4779.9   0.013       0
  4981.7    0.04       0  5003.7    0.04       0  5013.5    0.04       0
  5195.4    0.03       0  5395.0    0.04       0
Bank Sta=5003.7,5013.5
Exp/Cntr=0.3,0.1

Type RM Length L Ch R = 1,55911,964,964,964
BEGIN DESCRIPTION:
Mapping XS 3faf4a24
END DESCRIPTION:
XS GIS Cut Line= 4
      2401535.41     13565388.90      2401596.32     13564579.16
      2401198.61     13563715.65      2400809.03     13563454.74
#Sta/Elev= 30
  3578.7  418.63  3629.5  416.58  3893.5  412.77  3993.8  408.55  4013.8  409.27
  4039.4  406.97  4134.2  403.82  4154.2  402.07  4214.4  400.37  4234.4  401.34
  4274.6  398.96  4767.4  393.52  4838.7  393.75  4846.7  392.84  4868.7  395.17
  4901.8  393.57  4965.4  393.59  4981.9  392.96  4984.9  391.91  4985.4  391.41
  4994.7  391.91  5022.3  394.10  5033.9  393.33  5079.3  394.49  5125.2  394.02
  5155.0  399.06  5194.1  402.69  5346.5  409.84  5531.8  422.14  5810.3  433.28
#Mann=6,-1,0
  3578.7   0.013       0  3629.5    0.04       0  4767.4   0.013       0
  4965.4    0.04       0  4984.9    0.04       0  4994.7    0.04       0
Bank Sta=4984.9,4994.7
Exp/Cntr=0.3,0.1

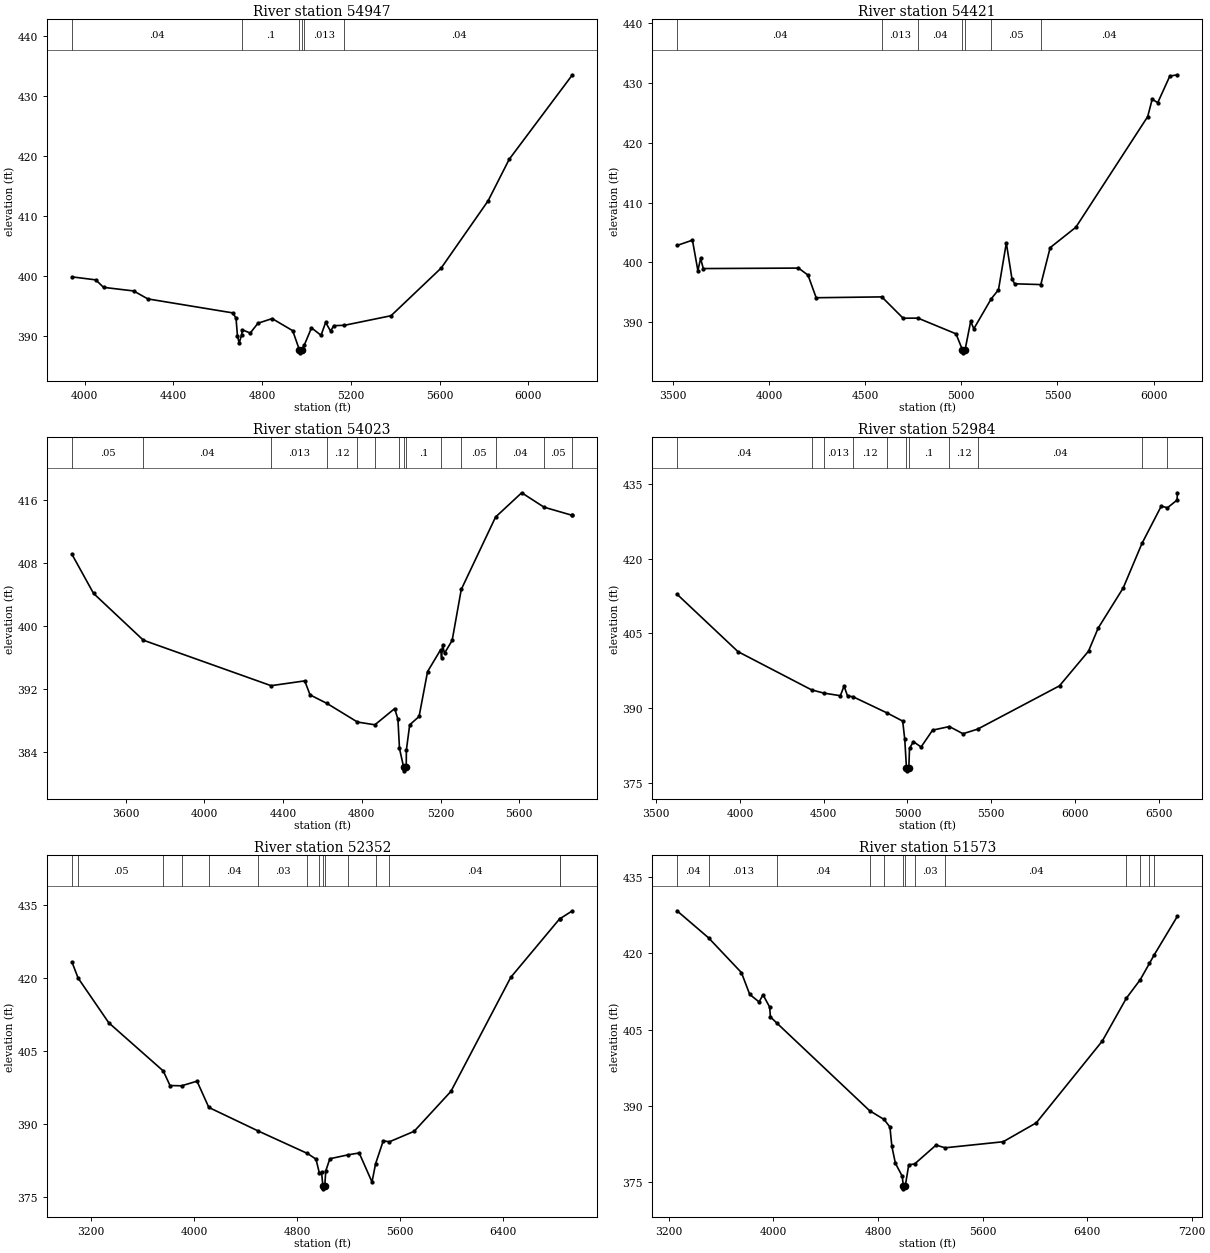
Type RM Length L Ch R = 1,54947,526,526,526
BEGIN DESCRIPTION:
Mapping XS 83c2a578
END DESCRIPTION:
XS GIS Cut Line= 3
      2402649.72     13564740.38      2401839.97     13563747.90
      2401005.13     13563242.70
#Sta/Elev= 30
  3942.8  399.80  4049.8  399.30  4085.0  398.05  4220.7  397.45  4284.6  396.12
  4668.0  393.78  4682.4  392.90  4688.8  390.00  4696.7  388.71  4707.7  390.15
  4711.1  390.96  4746.3  390.41  4781.5  392.06  4845.4  392.83  4938.0  390.81
  4968.2  387.61  4968.7  387.11  4978.1  387.61  4990.0  388.38  5022.7  391.28
  5065.8  390.04  5086.6  392.20  5108.9  390.73  5123.2  391.65  5171.2  391.71
  5381.5  393.31  5607.7  401.28  5819.1  412.50  5914.1  419.43  6199.5  433.56
#Mann=6,-1,0
  3942.8    0.04       0  4707.7     0.1       0  4968.2    0.03       0
  4978.1     0.1       0  4990.0   0.013       0  5171.2    0.04       0
Bank Sta=4968.2,4978.1
Exp/Cntr=0.3,0.1

Type RM Length L Ch R = 1,54421,398,398,398
BEGIN DESCRIPTION:
Mapping XS 884a1760
END DESCRIPTION:
XS GIS Cut Line= 3
      2403133.41     13564450.15      2402101.53     13563439.76
      2401038.64     13562978.10
#Sta/Elev= 30
  3520.9  402.82  3601.3  403.71  3629.6  398.61  3643.7  400.65  3657.8  398.96
  4152.8  399.04  4202.3  397.87  4244.8  394.08  4586.3  394.22  4697.2  390.65
  4774.2  390.67  4972.2  388.04  5005.7  385.36  5006.2  384.86  5019.3  385.36
  5048.5  390.12  5064.9  388.89  5155.0  393.88  5193.1  395.41  5233.9  403.25
  5263.4  397.21  5277.5  396.41  5413.3  396.28  5461.9  402.46  5595.6  405.87
  5969.2  424.38  5992.6  427.29  6021.5  426.71  6084.3  431.16  6123.9  431.38
#Mann=7,-1,0
  3520.9    0.04       0  4586.3   0.013       0  4774.2    0.04       0
  5005.7    0.04       0  5019.3    0.04       0  5155.0    0.05       0
  5413.3    0.04       0
Bank Sta=5005.7,5019.3
Exp/Cntr=0.3,0.1

Type RM Length L Ch R = 1,54023,1039,1039,1039
BEGIN DESCRIPTION:
Mapping XS 07b43e5a
END DESCRIPTION:
XS GIS Cut Line= 3
      2403667.95     13564115.21      2402339.81     13563134.29
      2401510.84     13562804.44
#Sta/Elev= 30
  3327.2  409.05  3436.8  404.09  3689.8  398.15  4338.8  392.37  4510.0  392.98
  4537.0  391.20  4623.4  390.11  4777.9  387.75  4866.4  387.40  4967.2  389.46
  4983.6  388.10  4991.5  384.39  5012.3  382.05  5012.8  381.55  5025.9  382.05
  5026.5  384.20  5043.4  387.39  5091.1  388.46  5134.2  394.16  5200.8  396.94
  5205.2  395.95  5210.6  397.52  5220.3  396.49  5259.2  398.12  5305.5  404.60
  5479.9  413.80  5612.6  416.88  5726.1  415.05  5868.5  414.02  5870.5  414.02
#Mann=14,-1,0
  3327.2    0.05       0  3689.8    0.04       0  4338.8   0.013       0
  4623.4    0.12       0  4777.9     0.1       0  4866.4    0.12       0
  4991.5     0.1       0  5012.3    0.05       0  5025.9     0.1       0
  5200.8   0.013       0  5305.5    0.05       0  5479.9    0.04       0
  5726.1    0.05       0  5868.5    0.04       0
Bank Sta=5012.3,5025.9
Exp/Cntr=0.3,0.1

Type RM Length L Ch R = 1,52984,632,632,632
BEGIN DESCRIPTION:
Mapping XS e0db4c0d
END DESCRIPTION:
XS GIS Cut Line= 4
      2403996.07     13563836.57      2403141.89     13562794.88
      2402690.50     13562586.55      2401608.60     13562218.98
#Sta/Elev= 30
  3624.6  412.87  3988.7  401.32  4427.5  393.64  4500.2  392.99  4599.6  392.46
  4621.8  394.40  4642.7  392.39  4674.6  392.26  4880.7  388.96  4971.7  387.36
  4984.1  383.68  4994.4  377.86  4994.9  377.36  5008.2  377.86  5012.5  381.86
  5035.5  383.23  5081.4  382.15  5150.2  385.54  5250.2  386.26  5331.7  384.82
  5418.8  385.74  5907.7  394.45  6080.9  401.42  6138.4  406.05  6287.9  414.12
  6399.7  423.06  6515.0  430.57  6552.1  430.24  6609.2  431.78  6611.5  433.25
#Mann=11,-1,0
  3624.6    0.04       0  4427.5    0.05       0  4500.2   0.013       0
  4674.6    0.12       0  4880.7     0.1       0  4994.4    0.05       0
  5008.2     0.1       0  5250.2    0.12       0  5418.8    0.04       0
  6399.7   0.013       0  6552.1    0.05       0
Bank Sta=4994.4,5008.2
Exp/Cntr=0.3,0.1

Type RM Length L Ch R = 1,52352,779,779,779
BEGIN DESCRIPTION:
Mapping XS 77b4c2f3
END DESCRIPTION:
XS GIS Cut Line= 4
      2404933.55     13563155.99      2403648.83     13562406.00
      2402218.28     13561787.94      2401384.92     13561676.83
#Sta/Elev= 30
  3050.7  423.29  3097.9  420.03  3336.5  410.83  3759.4  400.95  3811.9  397.96
  3901.5  397.90  4021.7  398.85  4113.3  393.46  4497.3  388.62  4879.3  384.01
  4945.5  382.85  4972.2  379.94  4989.1  380.14  4999.3  377.25  4999.8  376.75
  5013.5  377.25  5021.8  380.45  5053.4  382.93  5196.7  383.74  5281.2  384.11
  5380.7  378.15  5408.4  381.89  5468.4  386.64  5514.2  386.39  5707.9  388.56
  5993.7  396.76  6458.8  420.18  6837.5  432.16  6837.9  432.16  6937.4  433.83
#Mann=15,-1,0
  3050.7    0.03       0  3097.9    0.05       0  3759.4    0.04       0
  3901.5   0.013       0  4113.3    0.04       0  4497.3    0.03       0
  4879.3     0.1       0  4972.2    0.12       0  4999.3    0.05       0
  5013.5    0.12       0  5196.7     0.1       0  5408.4    0.12       0
  5514.2    0.04       0  6837.5   0.013       0  6837.9    0.05       0
Bank Sta=4999.3,5013.5
Exp/Cntr=0.3,0.1

Type RM Length L Ch R = 1,51573,553,553,553
BEGIN DESCRIPTION:
Mapping XS bd417358
END DESCRIPTION:
XS GIS Cut Line= 4
      2405211.31     13562753.20      2403815.50     13561794.88
      2403211.33     13561475.44      2401822.44     13561051.83
#Sta/Elev= 30
  3262.2  428.40  3503.4  423.08  3755.1  416.23  3818.7  411.94  3890.4  410.45
  3920.2  411.87  3971.0  409.45  3977.0  407.51  4027.6  406.26  4736.0  389.04
  4845.9  387.33  4891.3  385.83  4906.2  382.00  4933.2  378.69  4985.7  376.13
  4994.0  374.16  4994.5  373.66  5008.3  374.16  5035.3  378.39  5080.3  378.56
  5244.1  382.27  5313.4  381.74  5757.7  382.93  6011.3  386.66  6516.3  402.77
  6700.0  411.19  6805.5  414.80  6876.4  418.03  6912.9  419.71  7090.8  427.33
#Mann=13,-1,0
  3262.2    0.04       0  3503.4   0.013       0  4027.6    0.04       0
  4736.0    0.05       0  4845.9     0.1       0  4994.0    0.05       0
  5008.3     0.1       0  5080.3    0.03       0  5313.4    0.04       0
  6700.0    0.05       0  6805.5    0.04       0  6876.4    0.05       0
  6912.9    0.04       0
Bank Sta=4994,5008.3
Exp/Cntr=0.3,0.1

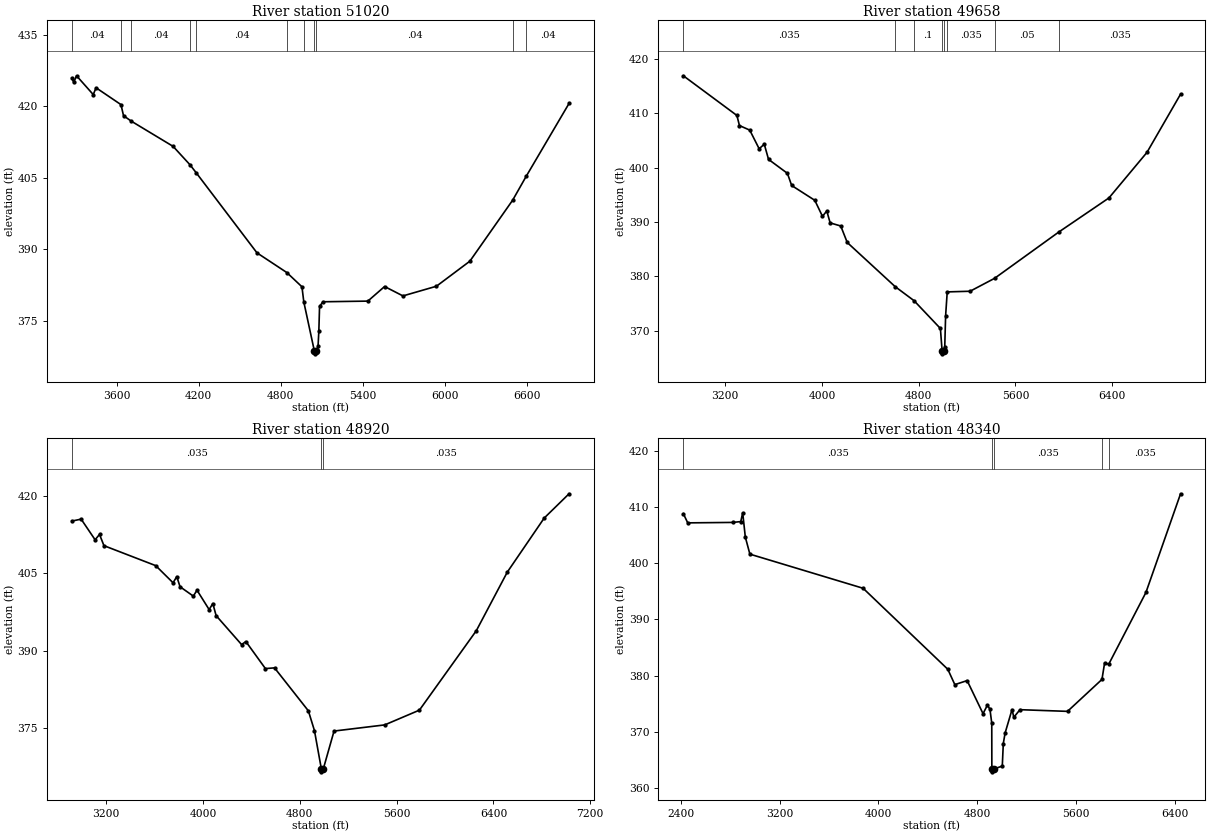
Type RM Length L Ch R = 1,51020,1362,1362,1362
BEGIN DESCRIPTION:
Mapping XS 787ae112
END DESCRIPTION:
XS GIS Cut Line= 4
      2405391.92     13562357.41      2404211.33     13561426.83
      2403350.22     13561100.44      2402162.68     13560878.21
#Sta/Elev= 30
  3273.3  425.95  3286.9  425.03  3307.7  426.40  3429.6  422.46  3450.4  423.88
  3632.2  420.35  3650.9  418.03  3707.1  416.89  4013.2  411.59  4135.9  407.75
  4180.7  406.10  4625.8  389.26  4843.8  385.13  4954.4  382.14  4967.8  378.98
  5045.7  368.58  5046.2  368.08  5060.1  368.58  5072.1  369.72  5077.7  372.82
  5083.0  378.03  5107.8  379.00  5435.7  379.14  5558.1  382.20  5692.2  380.23
  5936.8  382.26  6180.9  387.51  6493.9  400.32  6592.8  405.33  6905.6  420.60
#Mann=11,-1,0
  3273.3    0.04       0  3632.2   0.013       0  3707.1    0.04       0
  4135.9    0.03       0  4180.7    0.04       0  4843.8     0.1       0
  4967.8    0.04       0  5045.7    0.04       0  5060.1    0.04       0
  6493.9   0.035       0  6592.8    0.04       0
Bank Sta=5045.7,5060.1
Exp/Cntr=0.3,0.1

Type RM Length L Ch R = 1,49658,738,738,738
BEGIN DESCRIPTION:
Mapping XS 54f85fb7
END DESCRIPTION:
XS GIS Cut Line= 4
      2405600.25     13561635.19      2404746.06     13560690.72
      2403398.83     13560149.05      2402031.08     13559919.94
#Sta/Elev= 30
  2853.1  416.93  3296.1  409.62  3317.1  407.76  3402.3  406.92  3480.0  403.49
  3522.6  404.32  3557.7  401.53  3713.8  398.96  3749.0  396.72  3940.3  393.99
  4003.8  391.04  4039.6  392.03  4067.3  389.83  4155.0  389.26  4208.7  386.22
  4604.5  378.10  4761.3  375.50  4979.2  370.38  4993.3  366.21  4993.8  365.71
  5008.1  366.21  5015.0  366.91  5022.3  372.72  5035.6  377.12  5224.6  377.24
  5427.3  379.62  5958.5  388.15  6373.3  394.43  6687.7  402.82  6965.4  413.54
#Mann=8,-1,0
  2853.1   0.035       0  4604.5    0.04       0  4761.3     0.1       0
  4993.3    0.05       0  5008.1     0.1       0  5035.6   0.035       0
  5427.3    0.05       0  5958.5   0.035       0
Bank Sta=4993.3,5008.1
Exp/Cntr=0.3,0.1

Type RM Length L Ch R = 1,48920,580,580,580
BEGIN DESCRIPTION:
Mapping XS 700a37d7
END DESCRIPTION:
XS GIS Cut Line= 4
      2405753.02     13561461.58      2404975.22     13560225.44
      2403503.00     13559399.05      2402879.08     13558671.14
#Sta/Elev= 30
  2917.0  415.10  2993.8  415.48  3109.2  411.48  3145.7  412.52  3182.2  410.34
  3610.0  406.47  3753.3  403.15  3783.9  404.35  3811.0  402.38  3920.5  400.57
  3951.1  401.71  4051.2  397.96  4081.8  399.13  4108.9  396.79  4318.9  391.19
  4355.0  391.76  4516.1  386.53  4591.4  386.67  4870.9  378.35  4921.1  374.53
  4978.8  367.03  4979.3  366.53  4993.6  367.03  5083.1  374.43  5501.6  375.62
  5788.3  378.48  6258.4  393.87  6514.2  405.21  6819.3  415.69  7024.5  420.39
#Mann=3,-1,0
  2917.0   0.035       0  4978.8   0.035       0  4993.6   0.035       0
Bank Sta=4978.8,4993.6
Exp/Cntr=0.3,0.1

Type RM Length L Ch R = 1,48340,907,907,907
BEGIN DESCRIPTION:
Mapping XS 7beab9f9
END DESCRIPTION:
XS GIS Cut Line= 3
      2406218.30     13561350.48      2405468.28     13560100.44
      2403427.99     13558538.99
#Sta/Elev= 30
  2419.9  408.88  2455.5  407.24  2820.9  407.32  2885.0  407.47  2900.6  409.04
  2921.9  404.70  2958.9  401.66  3876.0  395.57  4561.8  381.12  4618.7  378.38
  4718.4  379.10  4847.2  373.20  4882.5  374.72  4903.3  373.98  4917.8  371.50
  4918.6  363.32  4919.1  362.82  4933.6  363.32  5003.1  363.85  5011.3  367.87
  5025.8  369.74  5082.0  373.93  5096.5  372.56  5146.4  373.91  5531.4  373.61
  5810.3  379.31  5831.9  382.26  5865.3  382.03  6166.4  394.82  6446.9  412.43
#Mann=5,-1,0
  2419.9   0.035       0  4918.6   0.035       0  4933.6   0.035       0
  5810.3    0.04       0  5865.3   0.035       0
Bank Sta=4918.6,4933.6
Exp/Cntr=0.3,0.1