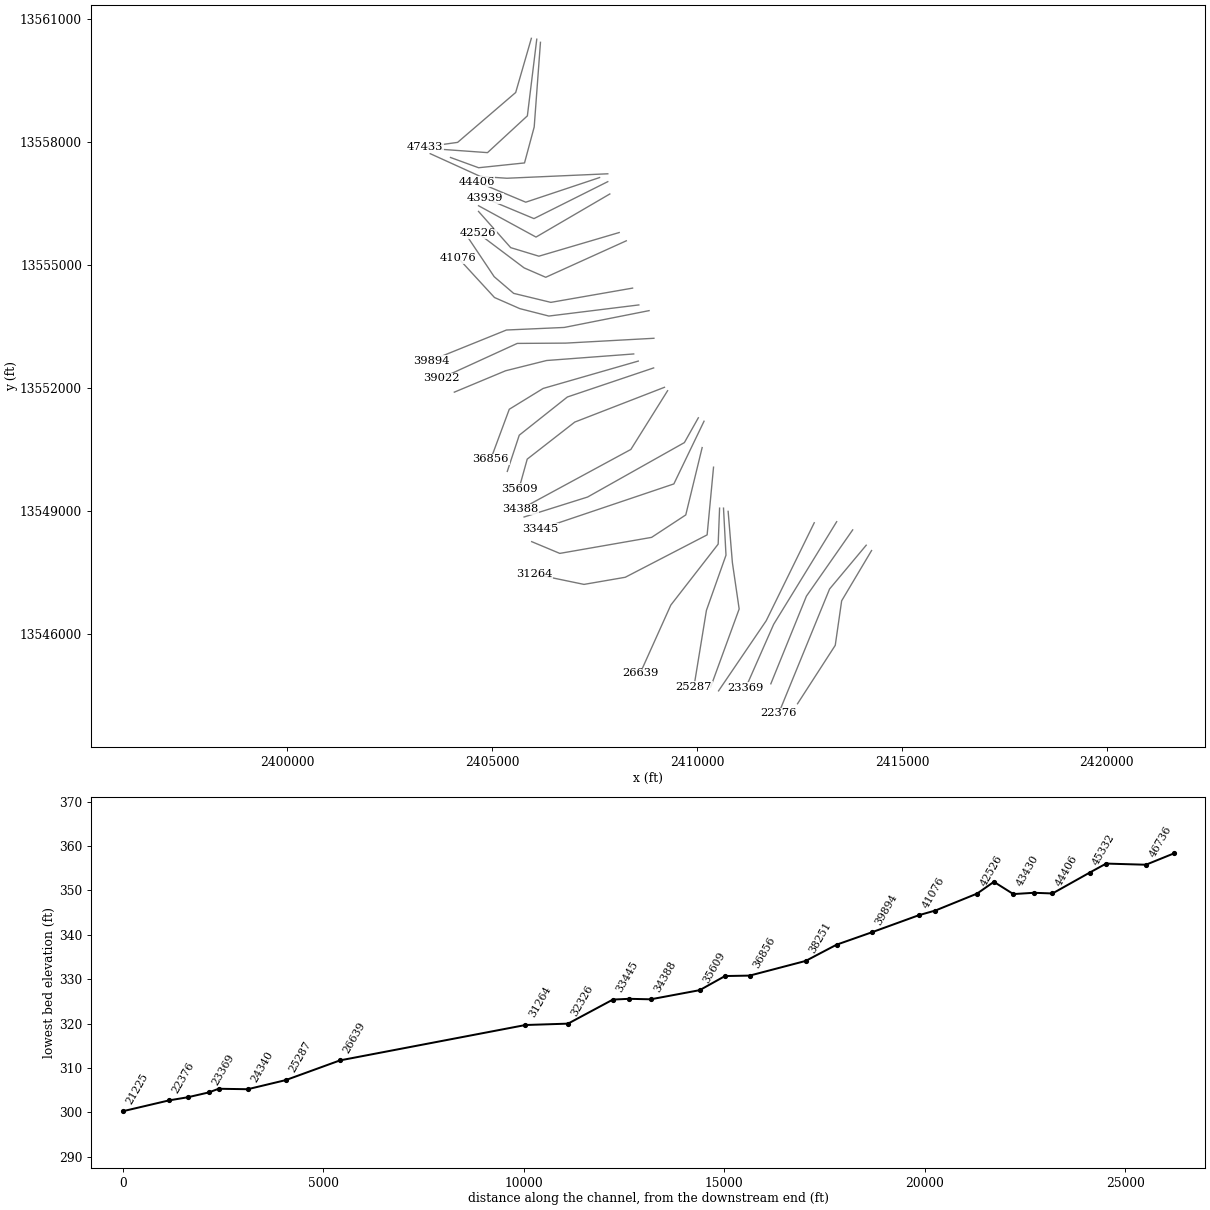
HEC-RAS study THOMAS CREEK.prj: THOMAS CREEK Base Level Engineering

--- THOMAS CREEK.g01 (geometry) --- (continued)

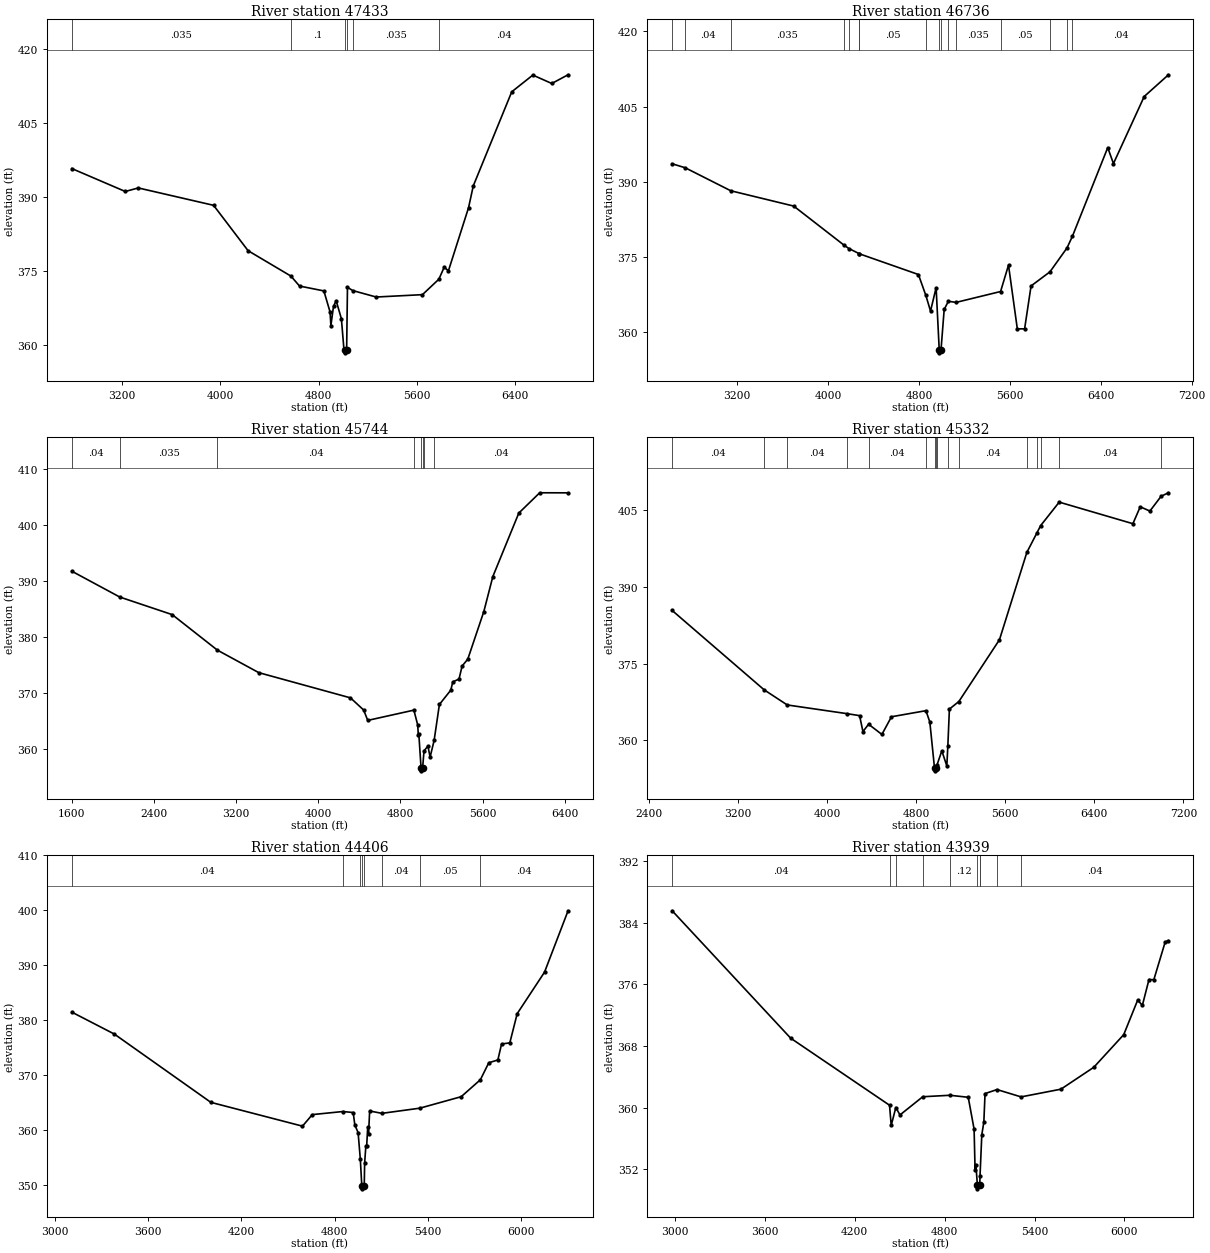
Type RM Length L Ch R = 1,47433,697,697,697
BEGIN DESCRIPTION:
Mapping XS be577984
END DESCRIPTION:
XS GIS Cut Line= 4
      2405961.34     13560517.14      2405579.39     13559197.66
      2404162.72     13557982.38      2403371.04     13557871.27
#Sta/Elev= 30
  2790.9  395.79  3226.2  391.13  3332.2  391.85  3945.0  388.32  4226.0  379.10
  4574.8  373.94  4644.6  371.92  4842.8  370.93  4893.3  366.64  4899.9  363.88
  4921.3  367.79  4942.7  368.95  4985.5  365.27  5006.3  359.00  5013.0  358.85
  5013.5  358.35  5028.1  358.85  5034.9  371.66  5078.1  371.00  5268.6  369.69
  5645.1  370.17  5779.0  373.31  5821.8  375.73  5856.9  375.03  6020.4  387.83
  6059.0  392.27  6372.1  411.38  6543.8  414.78  6698.0  413.07  6830.5  414.84
#Mann=6,-1,0
  2790.9   0.035       0  4574.8     0.1       0  5013.0    0.05       0
  5028.1     0.1       0  5078.1   0.035       0  5779.0    0.04       0
Bank Sta=5013,5028.1
Exp/Cntr=0.3,0.1

Type RM Length L Ch R = 1,46736,992,992,992
BEGIN DESCRIPTION:
Mapping XS 87adc5cd
END DESCRIPTION:
XS GIS Cut Line= 4
      2406093.27     13560496.23      2405864.11     13558628.22
      2404891.89     13557732.38      2403732.22     13557815.71
#Sta/Elev= 30
  2628.5  393.57  2743.5  392.77  3143.8  388.18  3697.7  385.12  4139.0  377.34
  4183.3  376.64  4274.3  375.61  4276.2  375.58  4795.0  371.45  4860.6  367.27
  4901.6  364.14  4950.9  368.82  4978.5  356.30  4979.0  355.80  4993.6  356.30
  5021.8  364.46  5058.5  366.10  5126.8  365.88  5518.1  368.05  5587.8  373.32
  5665.4  360.59  5729.5  360.59  5786.2  369.16  5952.9  371.99  6103.0  376.77
  6150.9  379.13  6461.0  396.80  6511.2  393.61  6781.9  407.01  6995.2  411.35
#Mann=16,-1,0
  2628.5   0.035       0  2743.5    0.04       0  3143.8   0.035       0
  4139.0    0.04       0  4183.3    0.05       0  4274.3    0.04       0
  4276.2    0.05       0  4860.6    0.12       0  4978.5    0.05       0
  4993.6    0.12       0  5058.5    0.12       0  5126.8   0.035       0
  5518.1    0.05       0  5952.9    0.04       0  6103.0    0.05       0
  6150.9    0.04       0
Bank Sta=4978.5,4993.6
Exp/Cntr=0.3,0.1

Type RM Length L Ch R = 1,45744,412,412,412
BEGIN DESCRIPTION:
Mapping XS 5c872c6d
END DESCRIPTION:
XS GIS Cut Line= 5
      2406183.56     13560419.91      2406030.78     13558357.38
      2405794.67     13557481.52      2404674.88     13557364.33
      2403989.52     13557614.18
#Sta/Elev= 30
  1601.8  391.68  2068.6  387.07  2579.4  383.93  3018.7  377.60  3421.7  373.58
  4314.6  369.08  4442.7  366.91  4482.6  365.06  4931.7  366.89  4968.9  364.25
  4975.0  362.44  4980.0  362.59  5001.6  356.56  5002.1  356.06  5016.7  356.56
  5030.3  359.61  5068.3  360.48  5089.6  358.51  5128.8  361.49  5180.1  367.90
  5290.7  370.45  5310.8  371.93  5371.1  372.44  5401.3  374.76  5456.5  375.99
  5612.4  384.47  5700.4  390.73  5953.1  402.05  6156.4  405.67  6432.5  405.66
#Mann=8,-1,0
  1601.8    0.04       0  2068.6   0.035       0  3018.7    0.04       0
  4931.7     0.1       0  5001.6    0.05       0  5016.7     0.1       0
  5030.3    0.05       0  5128.8    0.04       0
Bank Sta=5001.6,5016.7
Exp/Cntr=0.3,0.1

Type RM Length L Ch R = 1,45332,926,926,926
BEGIN DESCRIPTION:
Mapping XS b9790cb8
END DESCRIPTION:
XS GIS Cut Line= 4
      2407825.94     13557216.76      2405364.98     13557108.25
      2404718.28     13557151.66      2403494.36     13557707.19
#Sta/Elev= 30
  2610.3  385.39  3435.9  369.87  3643.2  366.91  4175.8  365.22  4292.9  364.82
  4322.9  361.69  4373.6  363.14  4493.1  361.14  4579.1  364.60  4888.6  365.79
  4923.5  363.57  4965.7  354.52  4966.2  354.02  4981.3  354.52  4986.9  355.11
  5031.3  357.93  5076.1  354.98  5085.3  358.93  5099.2  366.10  5184.1  367.58
  5548.7  379.67  5794.6  396.76  5883.5  400.51  5918.1  401.99  6085.1  406.59
  6746.7  402.37  6812.6  405.68  6899.2  404.84  7000.2  407.74  7065.9  408.42
#Mann=16,-1,0
  2610.3    0.04       0  3435.9    0.05       0  3643.2    0.04       0
  4175.8     0.1       0  4373.6    0.04       0  4888.6     0.1       0
  4965.7    0.04       0  4981.3     0.1       0  4986.9    0.04       0
  5085.3    0.05       0  5184.1    0.04       0  5794.6    0.03       0
  5883.5    0.04       0  5918.1    0.03       0  6085.1    0.04       0
  7000.2    0.05       0
Bank Sta=4965.7,4981.3
Exp/Cntr=0.3,0.1

Type RM Length L Ch R = 1,44406,467,467,467
BEGIN DESCRIPTION:
THOMAS CREEK 53.0
END DESCRIPTION:
XS GIS Cut Line= 3
      2407624.97     13557124.99      2405825.00     13556525.00
      2404625.03     13557024.99
#Sta/Elev= 30
  3106.7  381.47  3380.7  377.48  4002.6  365.06  4592.9  360.73  4656.2  362.83
  4852.9  363.39  4919.7  363.21  4930.2  360.95  4951.3  359.56  4965.5  354.77
  4975.2  349.83  4975.7  349.33  4990.8  349.83  4993.5  354.06  5001.4  357.17
  5006.7  357.17  5013.2  360.55  5018.7  359.27  5025.7  363.49  5104.7  363.06
  5349.0  364.00  5615.6  366.09  5739.1  369.17  5793.2  372.26  5851.7  372.77
  5875.6  375.67  5928.7  375.88  5976.3  381.19  6152.4  388.74  6304.0  399.90
#Mann=8,-1,0
  3106.7    0.04       0  4852.9     0.1       0  4965.5    0.05       0
  4975.2    0.05       0  4990.8    0.05       0  5104.7    0.04       0
  5349.0    0.05       0  5739.1    0.04       0
Bank Sta=4975.2,4990.8
Exp/Cntr=0.3,0.1

Type RM Length L Ch R = 1,43939,509,509,509
BEGIN DESCRIPTION:
THOMAS CREEK 52.0
END DESCRIPTION:
XS GIS Cut Line= 3
      2407825.02     13557025.01      2406025.00     13556125.00
      2404824.99     13556625.01
#Sta/Elev= 30
  2981.3  385.53  3772.3  369.01  4432.1  360.32  4443.2  357.70  4474.0  360.02
  4501.8  359.06  4653.8  361.42  4835.6  361.61  4957.4  361.35  4996.5  357.22
  5003.0  351.97  5008.4  352.62  5018.5  349.98  5019.0  349.48  5034.1  349.98
  5036.1  351.17  5048.0  356.50  5061.5  358.13  5069.6  361.83  5149.6  362.35
  5310.2  361.40  5576.1  362.40  5795.5  365.24  5995.3  369.47  6088.0  373.93
  6119.9  373.28  6163.8  376.61  6196.3  376.60  6272.1  381.49  6293.8  381.66
#Mann=10,-1,0
  2981.3    0.04       0  4432.1    0.05       0  4474.0    0.04       0
  4653.8    0.03       0  4835.6    0.12       0  5018.5    0.05       0
  5034.1    0.12       0  5036.1     0.1       0  5149.6    0.05       0
  5310.2    0.04       0
Bank Sta=5018.5,5034.1
Exp/Cntr=0.3,0.1

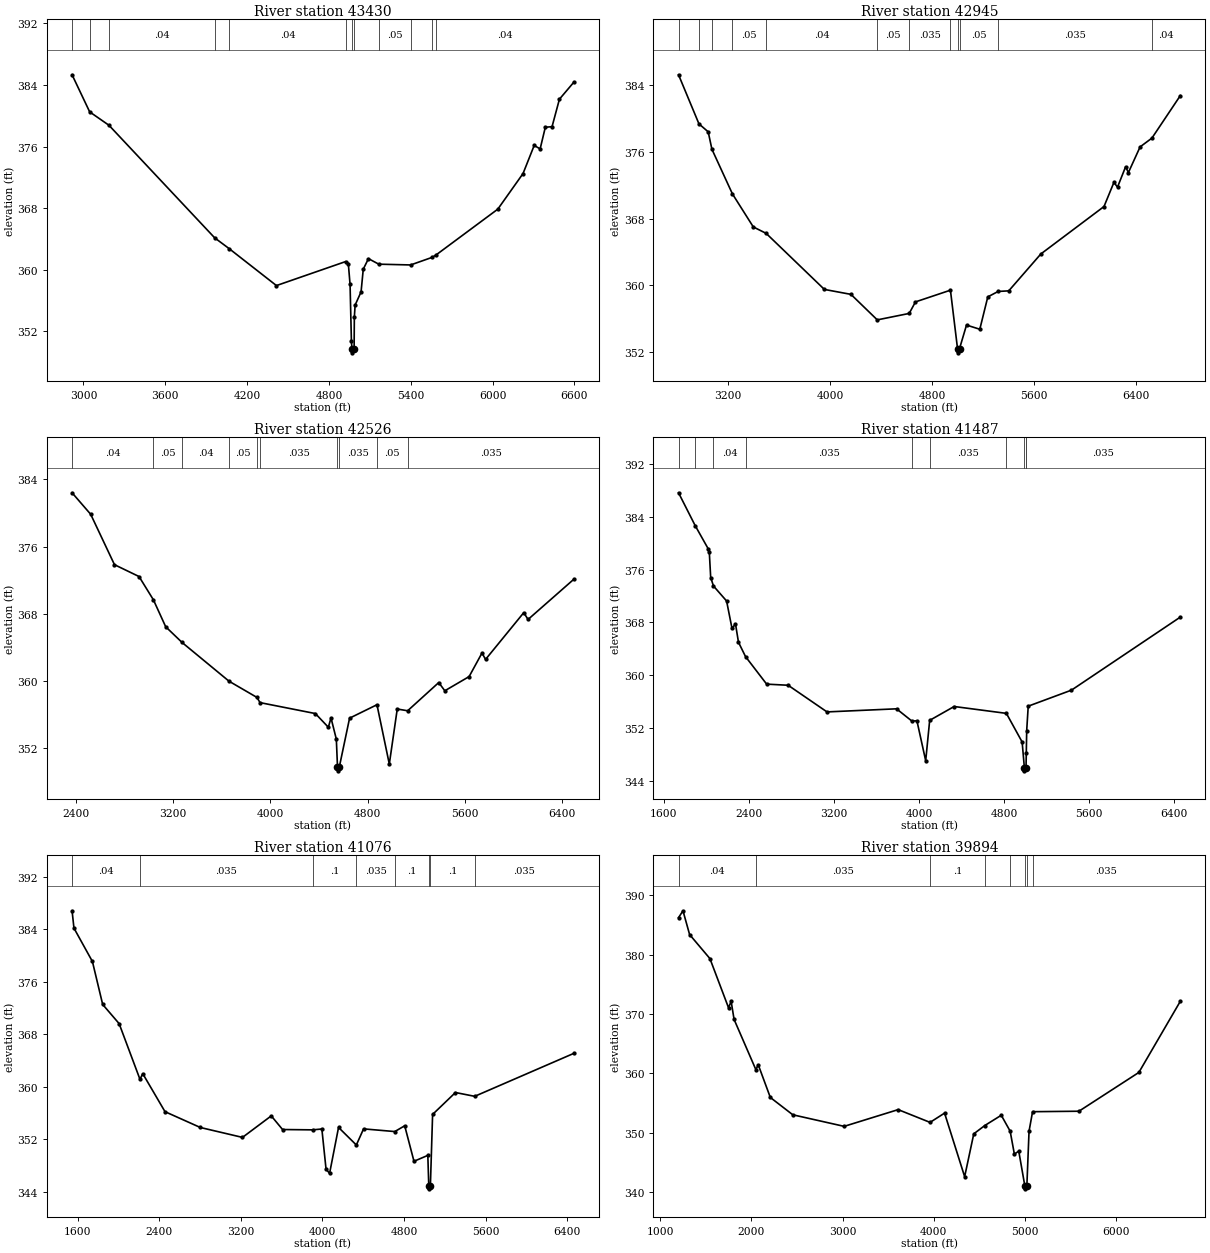
Type RM Length L Ch R = 1,43430,485,485,485
BEGIN DESCRIPTION:
THOMAS CREEK 51.0
END DESCRIPTION:
XS GIS Cut Line= 3
      2407874.99     13556724.99      2406075.00     13555675.00
      2404673.14     13556438.41
#Sta/Elev= 30
  2916.4  385.32  3045.5  380.50  3186.9  378.76  3962.4  364.13  4068.5  362.73
  4415.2  357.93  4922.8  361.05  4942.4  360.79  4955.2  358.07  4965.1  350.68
  4969.3  349.69  4969.8  349.19  4984.9  349.69  4986.6  353.83  4992.4  355.40
  5035.9  357.11  5052.0  360.06  5090.0  361.43  5165.8  360.71  5399.4  360.61
  5556.1  361.59  5583.6  361.88  6038.7  367.86  6223.9  372.49  6305.6  376.14
  6349.2  375.69  6387.2  378.50  6436.6  378.58  6490.7  382.15  6596.5  384.36
#Mann=12,-1,0
  2916.4    0.04       0  3045.5    0.05       0  3186.9    0.04       0
  3962.4    0.05       0  4068.5    0.04       0  4922.8     0.1       0
  4969.3    0.05       0  4984.9     0.1       0  5165.8    0.05       0
  5399.4    0.04       0  5556.1    0.05       0  5583.6    0.04       0
Bank Sta=4969.3,4984.9
Exp/Cntr=0.3,0.1

Type RM Length L Ch R = 1,42945,419,419,419
BEGIN DESCRIPTION:
Mapping XS 3ad422c2
END DESCRIPTION:
XS GIS Cut Line= 4
      2408103.74     13555785.64      2406145.36     13555209.24
      2405457.86     13555417.57      2404673.16     13556299.49
#Sta/Elev= 30
  2809.8  385.19  2970.2  379.32  3042.7  378.37  3071.9  376.29  3233.0  370.95
  3396.9  367.00  3498.0  366.23  3955.1  359.53  4163.6  358.94  4370.4  355.89
  4621.0  356.66  4670.3  358.04  4944.9  359.44  5000.6  352.45  5001.1  351.95
  5016.2  352.45  5071.1  355.27  5175.5  354.77  5238.3  358.64  5319.7  359.29
  5402.9  359.36  5654.9  363.77  6150.8  369.44  6228.5  372.32  6257.0  371.76
  6320.5  374.20  6342.3  373.50  6434.2  376.57  6527.0  377.62  6750.1  382.70
#Mann=12,-1,0
  2809.8    0.04       0  2970.2    0.05       0  3071.9    0.03       0
  3233.0    0.05       0  3498.0    0.04       0  4370.4    0.05       0
  4621.0   0.035       0  4944.9    0.05       0  5000.6    0.05       0
  5016.2    0.05       0  5319.7   0.035       0  6527.0    0.04       0
Bank Sta=5000.6,5016.2
Exp/Cntr=0.3,0.1

Type RM Length L Ch R = 1,42526,1039,1039,1039
BEGIN DESCRIPTION:
Mapping XS 18d69374
END DESCRIPTION:
XS GIS Cut Line= 4
      2408277.30     13555584.24      2406312.03     13554695.35
      2405784.25     13554924.51      2404666.23     13555764.77
#Sta/Elev= 30
  2367.0  382.40  2520.3  379.84  2716.1  373.84  2918.3  372.43  3036.5  369.66
  3137.8  366.45  3272.6  364.58  3659.1  359.97  3888.9  358.04  3914.6  357.42
  4369.8  356.12  4476.8  354.49  4498.7  355.60  4542.5  353.07  4552.0  349.80
  4552.5  349.30  4567.7  349.80  4651.5  355.57  4877.0  357.17  4978.6  350.11
  5044.0  356.66  5129.5  356.45  5385.6  359.81  5435.6  358.83  5635.6  360.52
  5741.8  363.33  5770.9  362.56  6085.4  368.13  6120.8  367.32  6497.9  372.11
#Mann=10,-1,0
  2367.0    0.04       0  3036.5    0.05       0  3272.6    0.04       0
  3659.1    0.05       0  3888.9    0.04       0  3914.6   0.035       0
  4552.0    0.05       0  4567.7   0.035       0  4877.0    0.05       0
  5129.5   0.035       0
Bank Sta=4552,4567.7
Exp/Cntr=0.3,0.1

Type RM Length L Ch R = 1,41487,411,411,411
BEGIN DESCRIPTION:
Mapping XS 80af5ae5
END DESCRIPTION:
XS GIS Cut Line= 5
      2408430.12     13554431.47      2406437.03     13554084.24
      2405529.98     13554303.35      2405055.08     13554709.24
      2404423.16     13555653.65
#Sta/Elev= 30
  1740.0  387.63  1895.9  382.67  2019.3  379.13  2029.4  378.59  2042.3  374.79
  2068.6  373.50  2191.8  371.23  2242.6  367.08  2275.5  367.75  2303.5  364.98
  2369.9  362.80  2568.4  358.63  2770.4  358.46  3135.8  354.42  3789.3  354.89
  3933.2  353.04  3981.2  353.07  4063.5  347.02  4101.0  353.14  4331.0  355.24
  4822.1  354.20  4970.3  349.86  4991.0  345.99  4991.5  345.49  5006.8  345.99
  5009.2  348.13  5013.1  351.60  5027.4  355.29  5434.1  357.72  6457.3  368.79
#Mann=10,-1,0
  1740.0    0.04       0  1895.9    0.05       0  2068.6    0.04       0
  2369.9   0.035       0  3933.2     0.1       0  4101.0   0.035       0
  4822.1     0.1       0  4991.0    0.05       0  5006.8     0.1       0
  5009.2   0.035       0
Bank Sta=4991,5006.8
Exp/Cntr=0.3,0.1

Type RM Length L Ch R = 1,41076,1182,1182,1182
BEGIN DESCRIPTION:
Mapping XS 73315718
END DESCRIPTION:
XS GIS Cut Line= 5
      2408582.87     13554021.74      2406388.42     13553750.90
      2405680.08     13553931.46      2405062.03     13554202.29
      2404180.40     13555160.28
#Sta/Elev= 30
  1546.6  386.82  1565.2  384.17  1746.0  379.09  1846.7  372.54  2007.9  369.62
  2212.0  361.14  2239.7  361.99  2457.6  356.20  2803.9  353.79  3217.0  352.28
  3499.2  355.56  3610.0  353.48  3904.1  353.43  3995.2  353.56  4036.1  347.46
  4070.8  346.79  4158.7  353.80  4333.2  351.12  4404.0  353.58  4710.0  353.17
  4807.2  354.05  4898.2  348.64  5033.9  349.54  5043.1  344.94  5043.6  344.44
  5059.1  344.94  5080.7  355.78  5304.6  359.12  5493.4  358.54  6465.4  365.09
#Mann=8,-1,0
  1546.6    0.04       0  2212.0   0.035       0  3904.1     0.1       0
  4333.2   0.035       0  4710.0     0.1       0  5043.1    0.05       0
  5059.1     0.1       0  5493.4   0.035       0
Bank Sta=5043.1,5059.1
Exp/Cntr=0.3,0.1

Type RM Length L Ch R = 1,39894,872,872,872
BEGIN DESCRIPTION:
Mapping XS e6f99be5
END DESCRIPTION:
XS GIS Cut Line= 4
      2408832.88     13553882.85      2406763.42     13553473.13
      2405353.70     13553410.63      2403513.39     13552667.56
#Sta/Elev= 30
  1199.6  386.26  1248.4  387.42  1321.1  383.41  1544.0  379.36  1747.9  371.09
  1777.0  372.14  1809.1  369.11  2047.9  360.65  2074.1  361.47  2206.7  355.96
  2453.2  353.04  3016.7  351.09  3609.3  353.91  3959.1  351.76  4118.4  353.32
  4338.7  342.61  4438.8  349.83  4559.8  351.23  4740.5  352.96  4837.9  350.28
  4884.2  346.42  4932.5  346.91  4998.9  341.06  4999.4  340.56  5021.3  341.06
  5045.2  350.27  5083.9  353.56  5592.5  353.64  6250.3  360.18  6705.0  372.17
#Mann=8,-1,0
  1199.6    0.04       0  2047.9   0.035       0  3959.1     0.1       0
  4559.8    0.05       0  4837.9     0.1       0  4998.9    0.05       0
  5021.3     0.1       0  5083.9   0.035       0
Bank Sta=4998.9,5021.3
Exp/Cntr=0.3,0.1

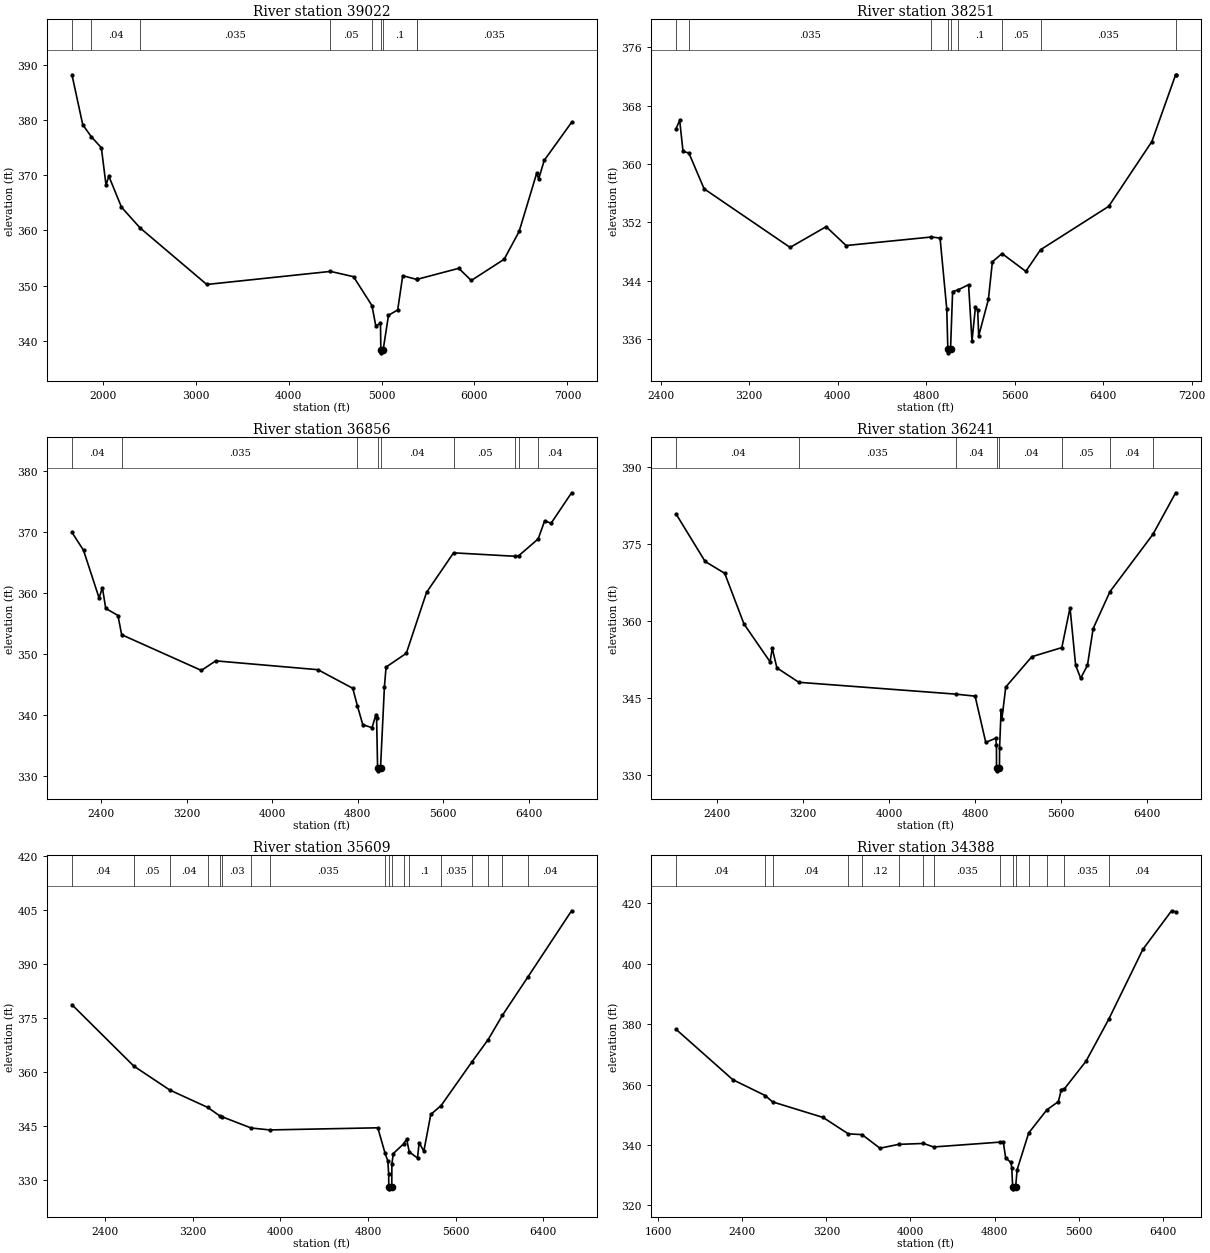
Type RM Length L Ch R = 1,39022,771,771,771
BEGIN DESCRIPTION:
Mapping XS f3da7c21
END DESCRIPTION:
XS GIS Cut Line= 4
      2408950.93     13553209.24      2406798.14     13553091.18
      2405617.58     13553084.24      2403763.38     13552237.00
#Sta/Elev= 30
  1669.5  388.22  1785.6  379.16  1877.6  376.99  1985.9  374.98  2036.0  368.21
  2066.0  369.84  2202.3  364.21  2401.5  360.46  3119.6  350.19  4450.9  352.56
  4698.7  351.60  4896.7  346.37  4938.7  342.66  4988.7  343.14  4992.7  338.29
  4993.2  337.79  5017.1  338.29  5074.9  344.60  5173.9  345.57  5228.1  351.78
  5379.5  351.10  5380.1  351.11  5831.2  353.12  5965.5  350.91  6319.2  354.76
  6480.4  359.80  6669.1  370.35  6691.1  369.34  6750.1  372.69  7044.7  379.59
#Mann=9,-1,0
  1669.5    0.05       0  1877.6    0.04       0  2401.5   0.035       0
  4450.9    0.05       0  4896.7     0.1       0  4992.7    0.05       0
  5017.1     0.1       0  5379.5    0.05       0  5380.1   0.035       0
Bank Sta=4992.7,5017.1
Exp/Cntr=0.3,0.1

Type RM Length L Ch R = 1,38251,1395,1395,1395
BEGIN DESCRIPTION:
Mapping XS 255cda75
END DESCRIPTION:
XS GIS Cut Line= 4
      2408457.91     13552827.30      2406332.86     13552667.57
      2405332.86     13552417.57      2404082.85     13551896.73
#Sta/Elev= 30
  2538.9  364.85  2571.9  365.97  2602.0  361.72  2654.7  361.51  2792.5  356.60
  3569.9  348.57  3895.6  351.41  4076.1  348.83  4847.8  350.00  4925.4  349.85
  4985.9  340.14  4995.7  334.63  4996.2  334.13  5020.1  334.63  5038.8  342.52
  5085.8  342.74  5183.1  343.46  5214.0  335.76  5245.0  340.37  5265.6  339.97
  5274.6  336.45  5362.2  341.44  5398.3  346.60  5485.4  347.73  5700.7  345.29
  5833.3  348.25  6449.9  354.20  6839.9  363.07  7054.5  372.22  7054.9  372.22
#Mann=9,-1,0
  2538.9    0.04       0  2654.7   0.035       0  4847.8    0.05       0
  4995.7    0.05       0  5020.1    0.05       0  5085.8     0.1       0
  5485.4    0.05       0  5833.3   0.035       0  7054.5    0.04       0
Bank Sta=4995.7,5020.1
Exp/Cntr=0.3,0.1

Type RM Length L Ch R = 1,36856,615,615,615
BEGIN DESCRIPTION:
Mapping XS 6f0dc433
END DESCRIPTION:
XS GIS Cut Line= 4
      2408568.99     13552653.69      2406249.53     13551987.01
      2405423.14     13551480.07      2404971.74     13550264.76
#Sta/Elev= 30
  2124.0  369.94  2232.2  367.01  2377.9  359.19  2409.1  360.86  2440.3  357.47
  2554.8  356.31  2589.3  353.16  3336.1  347.30  3470.4  348.87  4427.6  347.42
  4753.9  344.37  4797.4  341.49  4847.7  338.40  4934.5  337.91  4971.2  340.07
  4977.1  339.52  4986.5  331.33  4987.0  330.83  5014.0  331.33  5050.5  344.65
  5065.9  347.85  5255.4  350.11  5444.9  360.10  5698.1  366.59  6277.9  366.02
  6308.5  366.12  6490.5  368.87  6551.1  371.83  6611.8  371.45  6803.3  376.44
#Mann=9,-1,0
  2124.0    0.04       0  2589.3   0.035       0  4797.4    0.04       0
  4986.5    0.04       0  5014.0    0.04       0  5698.1    0.05       0
  6277.9    0.04       0  6308.5    0.05       0  6490.5    0.04       0
Bank Sta=4986.5,5014
Exp/Cntr=0.3,0.1

Type RM Length L Ch R = 1,36241,632,632,632
BEGIN DESCRIPTION:
Mapping XS e9002b63
END DESCRIPTION:
XS GIS Cut Line= 4
      2408944.00     13552487.02      2406839.81     13551778.68
      2405666.20     13550848.13      2405374.53     13549966.19
#Sta/Elev= 30
  2019.1  380.78  2289.5  371.52  2471.8  369.21  2651.1  359.34  2893.8  351.97
  2914.2  354.58  2957.1  350.79  3161.1  347.98  4623.4  345.67  4800.6  345.28
  4899.9  336.26  4992.9  337.10  4999.2  335.77  4999.9  331.23  5000.4  330.73
  5027.4  331.23  5028.1  335.10  5042.5  342.61  5049.5  340.78  5085.8  347.06
  5327.8  352.96  5607.4  354.74  5683.5  362.51  5735.6  351.31  5782.5  348.76
  5845.7  351.30  5898.4  358.43  6054.7  365.63  6454.1  376.79  6666.0  384.90
#Mann=8,-1,0
  2019.1    0.04       0  3161.1   0.035       0  4623.4    0.04       0
  4999.9    0.04       0  5027.4    0.04       0  5607.4    0.05       0
  6054.7    0.04       0  6454.1    0.03       0
Bank Sta=4999.9,5027.4
Exp/Cntr=0.3,0.1

Type RM Length L Ch R = 1,35609,1221,1221,1221
BEGIN DESCRIPTION:
Mapping XS f7d007cc
END DESCRIPTION:
XS GIS Cut Line= 4
      2409207.86     13552014.79      2407020.36     13551167.57
      2405860.64     13550264.79      2405659.62     13549543.91
#Sta/Elev= 30
  2095.9  378.62  2661.8  361.58  2989.9  354.95  3335.6  350.14  3450.5  347.70
  3469.8  347.51  3733.4  344.42  3904.7  343.89  4889.7  344.48  4956.6  337.36
  4981.1  335.30  4989.2  331.63  4989.9  328.05  4990.4  327.55  5017.4  328.05
  5018.2  334.45  5031.5  337.34  5125.0  340.02  5153.0  341.34  5177.1  337.79
  5252.5  336.08  5267.0  340.34  5310.3  338.02  5373.6  348.19  5468.1  350.65
  5748.6  362.73  5898.2  368.97  6027.7  375.67  6262.1  386.38  6659.8  404.68
#Mann=18,-1,0
  2095.9    0.04       0  2661.8    0.05       0  2989.9    0.04       0
  3335.6    0.03       0  3450.5    0.04       0  3469.8    0.03       0
  3733.4    0.05       0  3904.7   0.035       0  4956.6    0.04       0
  4989.9    0.04       0  5017.4    0.04       0  5125.0    0.05       0
  5177.1     0.1       0  5468.1   0.035       0  5748.6    0.05       0
  5898.2    0.04       0  6027.7    0.05       0  6262.1    0.04       0
Bank Sta=4989.9,5017.4
Exp/Cntr=0.3,0.1

Type RM Length L Ch R = 1,34388,537,537,537
BEGIN DESCRIPTION:
Mapping XS 38b3efb2
END DESCRIPTION:
XS GIS Cut Line= 3
      2409284.28     13551931.50      2408388.42     13550500.90
      2405694.00     13549042.59
#Sta/Elev= 30
  1770.6  378.29  2310.7  361.61  2618.7  356.37  2688.8  354.27  3168.8  349.12
  3409.0  343.69  3539.8  343.44  3709.7  338.94  3888.5  340.21  4123.5  340.51
  4220.2  339.35  4851.1  340.95  4883.6  340.90  4905.4  335.72  4954.9  334.24
  4963.4  332.51  4972.3  325.99  4972.8  325.49  4999.9  325.99  5014.8  331.85
  5124.4  343.97  5297.2  351.63  5406.8  354.36  5435.3  358.35  5464.1  358.59
  5670.2  367.76  5885.9  381.63  6210.5  404.75  6483.5  417.52  6522.3  417.20
#Mann=15,-1,0
  1770.6    0.04       0  2618.7    0.05       0  2688.8    0.04       0
  3409.0    0.05       0  3539.8    0.12       0  3888.5    0.04       0
  4123.5    0.05       0  4220.2   0.035       0  4851.1     0.1       0
  4972.3    0.05       0  4999.9     0.1       0  5124.4    0.05       0
  5297.2    0.04       0  5464.1   0.035       0  5885.9    0.04       0
Bank Sta=4972.3,4999.9
Exp/Cntr=0.3,0.1

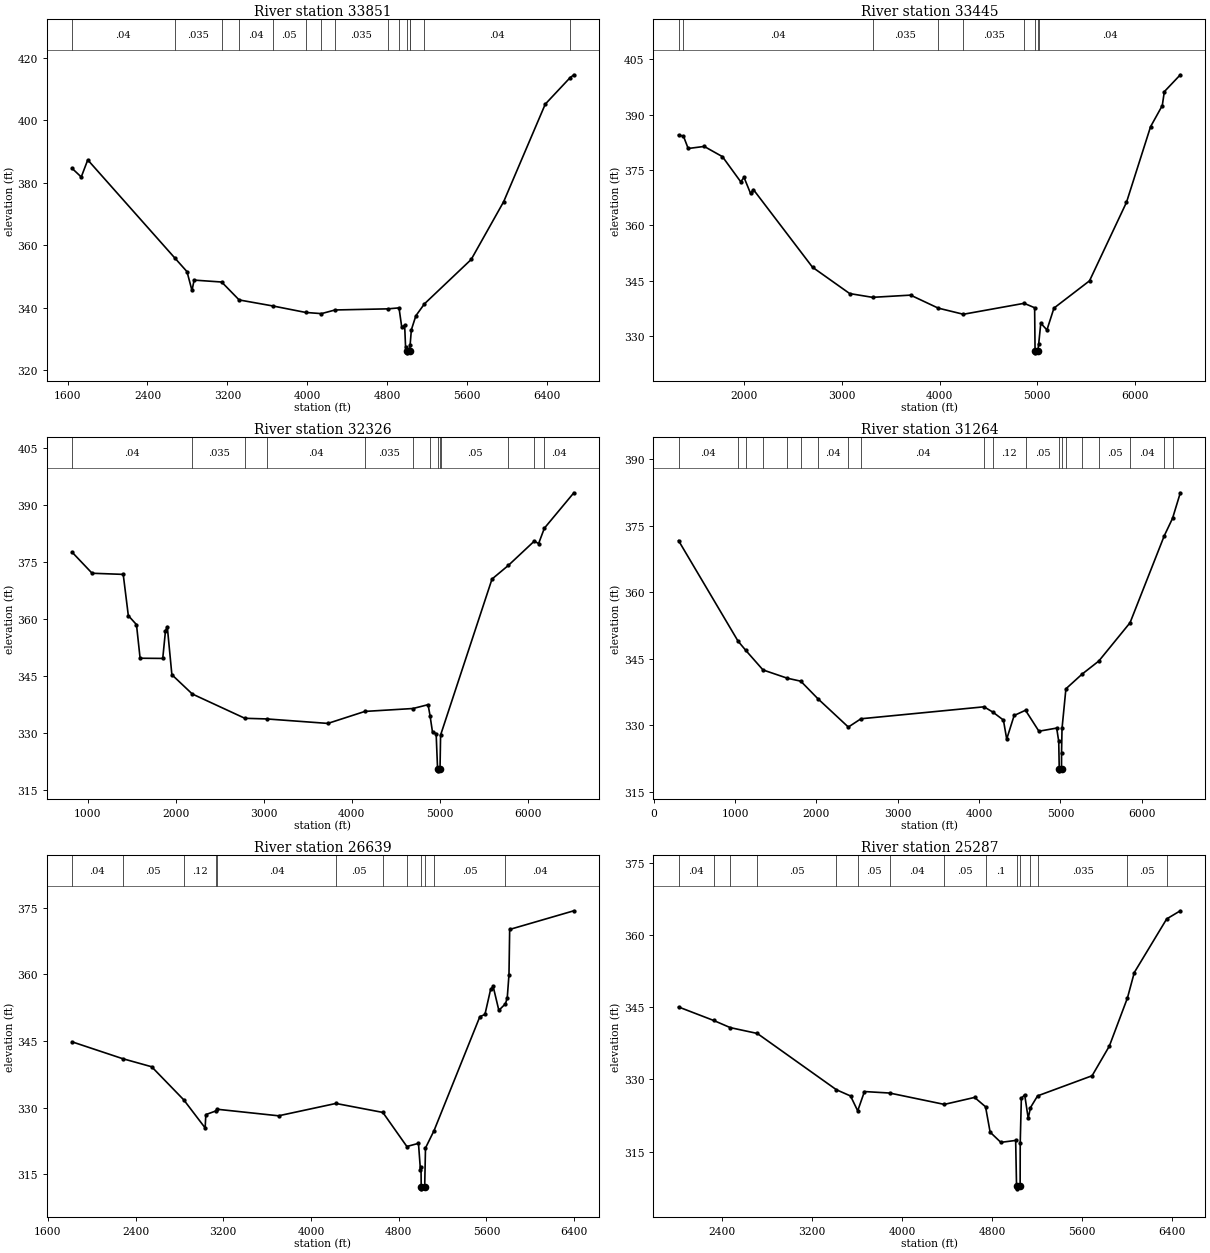
Type RM Length L Ch R = 1,33851,406,406,406
BEGIN DESCRIPTION:
Mapping XS bcfaddf1
END DESCRIPTION:
XS GIS Cut Line= 4
      2410034.24     13551271.72      2409693.97     13550667.57
      2407332.86     13549341.18      2405784.21     13548855.06
#Sta/Elev= 30
  1644.9  384.60  1736.9  381.84  1801.9  387.31  2672.1  355.99  2795.9  351.56
  2845.6  345.54  2867.3  348.86  3142.8  348.25  3317.8  342.52  3653.9  340.60
  3984.3  338.52  4141.9  338.14  4278.3  339.31  4807.9  339.67  4918.9  339.98
  4946.6  333.71  4975.2  334.47  4984.3  327.52  4997.8  326.10  4998.3  325.60
  5025.5  326.10  5029.9  328.06  5042.4  332.97  5087.6  337.46  5173.8  341.28
  5641.6  355.46  5966.5  373.93  6383.3  405.14  6632.0  413.61  6669.6  414.53
#Mann=15,-1,0
  1644.9    0.04       0  2672.1   0.035       0  3142.8    0.05       0
  3317.8    0.04       0  3653.9    0.05       0  3984.3    0.03       0
  4141.9    0.05       0  4278.3   0.035       0  4807.9    0.05       0
  4918.9     0.1       0  4997.8    0.05       0  5025.5     0.1       0
  5029.9    0.05       0  5173.8    0.04       0  6632.0    0.05       0
Bank Sta=4997.8,5025.5
Exp/Cntr=0.3,0.1

Type RM Length L Ch R = 1,33445,1119,1119,1119
BEGIN DESCRIPTION:
Mapping XS c91b8c17
END DESCRIPTION:
XS GIS Cut Line= 3
      2410173.13     13551188.39      2409437.03     13549660.63
      2406180.04     13548563.39
#Sta/Elev= 30
  1330.6  384.52  1381.3  384.16  1429.3  380.84  1593.2  381.40  1779.7  378.63
  1967.1  371.80  2000.4  373.01  2067.0  368.67  2096.4  369.70  2701.2  348.64
  3081.4  341.50  3314.8  340.48  3703.9  341.08  3986.4  337.56  4243.9  335.89
  4865.5  338.86  4973.0  337.66  4977.5  325.93  4978.0  325.43  5005.2  325.93
  5014.2  327.72  5035.9  333.47  5098.9  331.64  5170.7  337.56  5534.5  344.96
  5912.4  366.23  6159.0  386.76  6278.7  392.48  6299.8  396.26  6463.3  400.83
#Mann=9,-1,0
  1330.6    0.05       0  1381.3    0.04       0  3314.8   0.035       0
  3986.4     0.1       0  4243.9   0.035       0  4865.5    0.05       0
  4977.5    0.05       0  5005.2    0.05       0  5014.2    0.04       0
Bank Sta=4977.5,5005.2
Exp/Cntr=0.3,0.1

Type RM Length L Ch R = 1,32326,1062,1062,1062
BEGIN DESCRIPTION:
Mapping XS bc757058
END DESCRIPTION:
XS GIS Cut Line= 5
      2410127.14     13550546.06      2409727.83     13548905.42
      2408894.49     13548358.54      2406654.91     13547967.92
      2405969.58     13548254.19
#Sta/Elev= 30
   823.0  377.65  1050.5  372.09  1404.2  371.79  1462.2  360.92  1554.8  358.55
  1596.0  349.69  1853.3  349.64  1884.2  356.89  1904.7  358.04  1957.0  345.35
  2188.6  340.27  2786.3  333.86  3035.4  333.69  3729.3  332.51  4150.0  335.67
  4696.8  336.44  4868.0  337.45  4890.0  334.59  4918.8  330.13  4959.6  329.83
  4975.9  320.51  4976.4  320.01  5003.7  320.51  5010.2  329.44  5594.4  370.56
  5779.8  374.15  6074.8  380.56  6123.7  379.90  6189.2  383.96  6524.4  393.30
#Mann=13,-1,0
   823.0    0.04       0  2188.6   0.035       0  2786.3    0.03       0
  3035.4    0.04       0  4150.0   0.035       0  4696.8    0.05       0
  4890.0     0.1       0  4975.9    0.05       0  5003.7     0.1       0
  5010.2    0.05       0  5779.8    0.04       0  6074.8   0.013       0
  6189.2    0.04       0
Bank Sta=4975.9,5003.7
Exp/Cntr=0.3,0.1

Type RM Length L Ch R = 1,31264,4625,4625,4625
BEGIN DESCRIPTION:
Mapping XS 5cbb0b2c
END DESCRIPTION:
XS GIS Cut Line= 5
      2410404.91     13550068.62      2410248.66     13548419.31
      2408252.13     13547386.32      2407245.19     13547212.71
      2406029.91     13547464.44
#Sta/Elev= 30
   306.2  371.66  1038.3  348.95  1132.1  346.90  1344.3  342.47  1643.8  340.60
  1808.7  339.93  2018.2  335.99  2393.2  329.58  2548.5  331.45  4060.8  334.15
  4169.9  332.95  4299.2  331.16  4339.8  326.87  4431.2  332.19  4570.8  333.37
  4735.6  328.64  4954.0  329.35  4979.1  326.36  4985.5  320.20  4986.0  319.70
  5013.4  320.20  5013.9  323.80  5019.7  329.26  5067.3  338.21  5266.5  341.53
  5471.9  344.48  5855.7  353.12  6276.8  372.77  6377.8  376.67  6473.7  382.45
#Mann=20,-1,0
   306.2    0.04       0  1038.3    0.05       0  1132.1    0.04       0
  1344.3    0.04       0  1643.8    0.05       0  1808.7    0.05       0
  2018.2    0.04       0  2393.2     0.1       0  2548.5    0.04       0
  4060.8    0.05       0  4169.9    0.12       0  4570.8    0.05       0
  4985.5    0.05       0  5013.4    0.12       0  5067.3    0.05       0
  5266.5    0.04       0  5471.9    0.05       0  5855.7    0.04       0
  6276.8   0.013       0  6377.8    0.04       0
Bank Sta=4985.5,5013.4
Exp/Cntr=0.3,0.1

Type RM Length L Ch R = 1,26639,1352,1352,1352
BEGIN DESCRIPTION:
Mapping XS 4dfa3435
END DESCRIPTION:
XS GIS Cut Line= 4
      2410552.48     13549070.38      2410517.76     13548193.61
      2409363.24     13546709.24      2408616.70     13545051.21
#Sta/Elev= 30
  1821.4  344.82  2281.4  341.04  2547.3  339.21  2840.0  331.76  3035.0  325.44
  3041.4  328.44  3135.4  329.29  3146.8  329.64  3704.7  328.17  4227.6  330.95
  4655.6  328.93  4874.7  321.26  4980.6  321.97  4998.3  316.04  5003.8  316.59
  5005.6  312.23  5006.1  311.73  5037.3  312.23  5044.6  320.92  5122.5  324.83
  5540.4  350.49  5586.7  350.98  5638.5  356.62  5661.6  357.30  5713.6  351.91
  5774.1  353.39  5790.4  354.78  5806.0  359.95  5812.3  370.12  6397.7  374.32
#Mann=12,-1,0
  1821.4    0.04       0  2281.4    0.05       0  2840.0    0.12       0
  3135.4     0.1       0  3146.8    0.04       0  4227.6    0.05       0
  4655.6    0.03       0  4874.7     0.1       0  5005.6    0.05       0
  5037.3     0.1       0  5122.5    0.05       0  5774.1    0.04       0
Bank Sta=5005.6,5037.3
Exp/Cntr=0.3,0.1

Type RM Length L Ch R = 1,25287,947,947,947
BEGIN DESCRIPTION:
Mapping XS ff772e72
END DESCRIPTION:
XS GIS Cut Line= 4
      2410647.97     13549070.35      2410708.73     13547924.51
      2410231.30     13546579.03      2409927.49     13544721.44
#Sta/Elev= 30
  2015.0  345.05  2326.7  342.25  2474.9  340.76  2714.6  339.55  3417.6  327.86
  3543.0  326.57  3606.6  323.48  3666.5  327.49  3890.2  327.18  4375.9  324.82
  4644.9  326.27  4742.1  324.33  4782.9  319.06  4877.9  316.94  5009.7  317.34
  5017.5  307.79  5018.0  307.29  5049.4  307.79  5050.2  316.89  5060.3  326.07
  5089.7  326.83  5121.1  321.94  5141.4  324.16  5204.4  326.59  5688.6  330.77
  5841.5  336.91  6002.6  346.92  6063.5  352.20  6351.3  363.33  6472.4  365.02
#Mann=15,-1,0
  2015.0    0.04       0  2326.7    0.05       0  2474.9    0.04       0
  2714.6    0.05       0  3417.6    0.12       0  3606.6    0.05       0
  3890.2    0.04       0  4375.9    0.05       0  4742.1     0.1       0
  5017.5    0.05       0  5049.4     0.1       0  5141.4    0.12       0
  5204.4   0.035       0  6002.6    0.05       0  6351.3    0.04       0
Bank Sta=5017.5,5049.4
Exp/Cntr=0.3,0.1

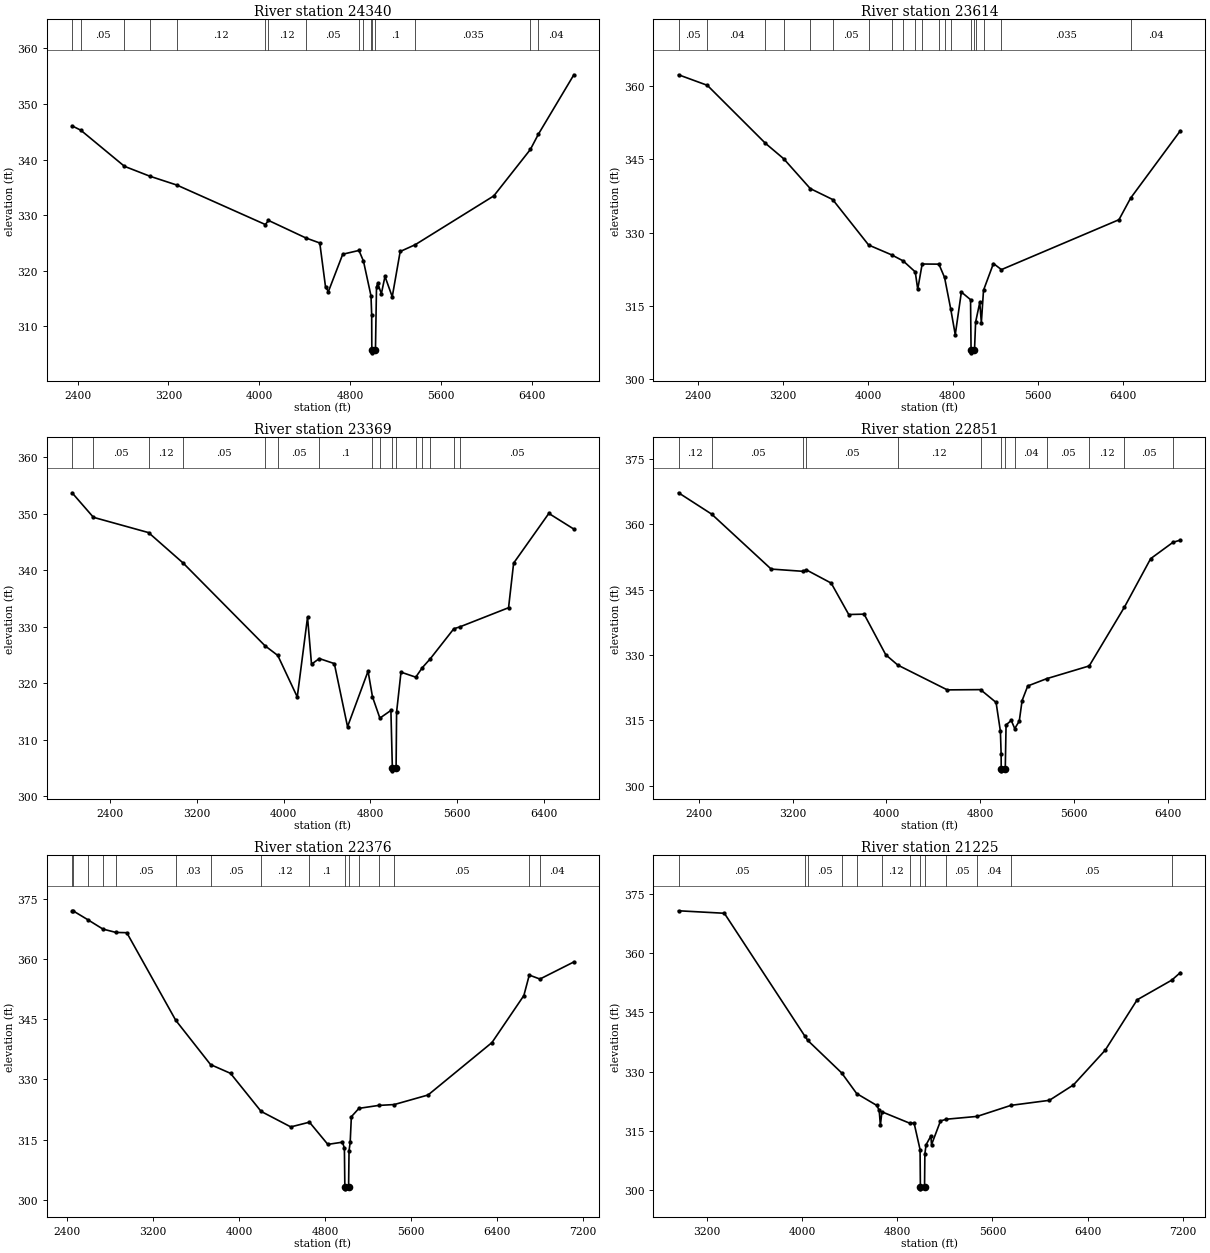
Type RM Length L Ch R = 1,24340,726,726,726
BEGIN DESCRIPTION:
Mapping XS 77ca6a62
END DESCRIPTION:
XS GIS Cut Line= 4
      2410760.81     13548992.26      2410864.98     13547742.22
      2411029.91     13546613.75      2410335.48     13544712.75
#Sta/Elev= 30
  2350.9  346.07  2427.6  345.29  2812.5  338.79  3036.4  337.01  3273.8  335.42
  4052.9  328.32  4080.6  329.06  4410.5  325.90  4532.2  325.00  4582.8  317.10
  4608.0  316.26  4734.4  322.98  4877.2  323.66  4917.1  321.73  4983.2  315.49
  4989.3  312.06  4990.5  305.74  4991.0  305.24  5022.5  305.74  5031.7  317.08
  5042.5  317.73  5074.4  315.87  5106.4  318.99  5170.3  315.32  5240.2  323.47
  5372.5  324.69  6064.5  333.47  6386.5  341.82  6457.5  344.58  6769.6  355.26
#Mann=16,-1,0
  2350.9    0.04       0  2427.6    0.05       0  2812.5    0.04       0
  3036.4    0.05       0  3273.8    0.12       0  4052.9    0.05       0
  4080.6    0.12       0  4410.5    0.05       0  4877.2    0.12       0
  4917.1    0.05       0  4983.2     0.1       0  4990.5    0.05       0
  5022.5     0.1       0  5372.5   0.035       0  6386.5    0.05       0
  6457.5    0.04       0
Bank Sta=4990.5,5022.5
Exp/Cntr=0.3,0.1

Type RM Length L Ch R = 1,23614,245,245,245
BEGIN DESCRIPTION:
Mapping XS 3528826b
END DESCRIPTION:
XS GIS Cut Line= 3
      2412861.49     13548714.40      2411689.63     13546327.29
      2410527.40     13544618.64
#Sta/Elev= 30
  2216.5  362.34  2487.6  360.18  3035.5  348.28  3206.3  345.14  3457.1  339.01
  3667.9  336.77  4006.9  327.44  4223.0  325.43  4332.3  324.18  4445.8  321.93
  4469.1  318.38  4511.0  323.55  4668.5  323.52  4721.8  320.79  4779.9  314.33
  4822.6  309.06  4880.1  317.80  4966.6  316.24  4971.5  305.84  4972.0  305.34
  5003.7  305.84  5014.3  311.64  5053.4  315.67  5068.3  311.52  5088.7  318.17
  5182.1  323.65  5257.3  322.40  6364.3  332.63  6473.5  337.04  6942.2  350.86
#Mann=20,-1,0
  2216.5    0.05       0  2487.6    0.04       0  3035.5    0.04       0
  3206.3    0.05       0  3457.1    0.05       0  3667.9    0.05       0
  4006.9    0.05       0  4223.0   0.013       0  4332.3    0.12       0
  4445.8   0.013       0  4511.0    0.12       0  4668.5   0.013       0
  4721.8     0.1       0  4779.9   0.013       0  4971.5    0.05       0
  5003.7    0.12       0  5014.3   0.013       0  5088.7     0.1       0
  5257.3   0.035       0  6473.5    0.04       0
Bank Sta=4971.5,5003.7
Exp/Cntr=0.3,0.1

Type RM Length L Ch R = 1,23369,518,518,518
BEGIN DESCRIPTION:
Mapping XS a2491a8d
END DESCRIPTION:
XS GIS Cut Line= 3
      2413408.37     13548740.47      2411871.92     13546240.49
      2411186.89     13544688.31
#Sta/Elev= 30
  2048.7  353.68  2245.9  349.34  2754.5  346.64  3073.7  341.26  3829.5  326.63
  3947.2  324.92  4127.1  317.58  4221.8  331.68  4258.5  323.38  4330.7  324.37
  4469.1  323.48  4591.0  312.32  4780.4  322.14  4821.3  317.60  4889.5  313.84
  4991.2  315.20  5004.6  305.02  5005.3  304.52  5039.1  305.02  5043.7  314.91
  5084.4  321.97  5220.6  321.08  5280.6  322.75  5355.3  324.35  5571.9  329.64
  5627.2  329.97  6077.1  333.36  6123.8  341.24  6448.7  350.03  6679.7  347.26
#Mann=16,-1,0
  2048.7    0.04       0  2245.9    0.05       0  2754.5    0.12       0
  3073.7    0.05       0  3829.5    0.12       0  3947.2    0.05       0
  4330.7     0.1       0  4821.3    0.12       0  4889.5     0.1       0
  5004.6    0.05       0  5039.1    0.12       0  5220.6    0.05       0
  5280.6     0.1       0  5355.3    0.05       0  5571.9    0.12       0
  5627.2    0.05       0
Bank Sta=5004.6,5039.1
Exp/Cntr=0.3,0.1

Type RM Length L Ch R = 1,22851,475,475,475
BEGIN DESCRIPTION:
Mapping XS 643f998b
END DESCRIPTION:
XS GIS Cut Line= 3
      2413799.03     13548540.87      2412670.54     13546926.25
      2411802.48     13544790.84
#Sta/Elev= 30
  2228.3  367.26  2510.5  362.36  3017.3  349.75  3289.9  349.23  3316.0  349.58
  3528.7  346.53  3678.3  339.32  3809.2  339.40  3994.0  330.07  4096.6  327.71
  4518.1  322.02  4801.1  322.08  4933.6  319.14  4970.5  312.52  4976.8  307.21
  4977.3  303.94  4978.1  303.44  5011.9  303.94  5018.7  313.98  5063.1  315.01
  5092.4  313.14  5131.2  314.85  5155.2  319.56  5203.4  322.92  5364.5  324.59
  5727.1  327.52  6027.4  341.03  6250.5  352.14  6441.3  355.90  6503.3  356.39
#Mann=13,-1,0
  2228.3    0.12       0  2510.5    0.05       0  3289.9    0.12       0
  3316.0    0.05       0  4096.6    0.12       0  4801.1     0.1       0
  4977.3    0.05       0  5011.9     0.1       0  5092.4    0.04       0
  5364.5    0.05       0  5727.1    0.12       0  6027.4    0.05       0
  6441.3    0.12       0
Bank Sta=4977.3,5011.9
Exp/Cntr=0.3,0.1

Type RM Length L Ch R = 1,22376,1151,1151,1151
BEGIN DESCRIPTION:
Mapping XS 95d2cce8
END DESCRIPTION:
XS GIS Cut Line= 3
      2414128.86     13548167.56      2413234.77     13547099.86
      2411993.44     13544070.32
#Sta/Elev= 30
  2446.4  371.96  2459.0  371.89  2590.7  369.77  2733.5  367.40  2854.0  366.57
  2955.3  366.50  3410.5  344.69  3734.3  333.66  3919.9  331.48  4204.6  322.00
  4480.5  318.14  4654.0  319.32  4824.9  313.79  4961.1  314.34  4979.0  312.85
  4983.2  303.22  4983.9  302.72  5018.1  303.22  5022.2  312.15  5033.0  314.38
  5043.8  320.68  5114.1  322.76  5297.0  323.49  5443.1  323.71  5757.1  326.09
  6351.5  339.15  6648.0  350.85  6698.3  355.95  6797.5  354.96  7113.0  359.22
#Mann=16,-1,0
  2446.4    0.05       0  2459.0    0.12       0  2590.7    0.05       0
  2733.5    0.12       0  2854.0    0.05       0  3410.5    0.03       0
  3734.3    0.05       0  4204.6    0.12       0  4654.0     0.1       0
  4983.2    0.05       0  5018.1     0.1       0  5114.1    0.05       0
  5297.0    0.04       0  5443.1    0.05       0  6698.3   0.013       0
  6797.5    0.04       0
Bank Sta=4983.2,5018.1
Exp/Cntr=0.3,0.1

Type RM Length L Ch R = 1,21225,508,508,508
BEGIN DESCRIPTION:
Mapping XS ea4b49c3
END DESCRIPTION:
XS GIS Cut Line= 4
      2414259.08     13548037.36      2413529.91     13546813.40
      2413373.66     13545728.33      2412453.54     13544304.76
#Sta/Elev= 30
  2963.0  370.71  3348.0  370.08  4026.1  338.88  4048.9  337.87  4333.1  329.66
  4459.8  324.41  4628.6  321.41  4648.8  320.19  4658.9  316.38  4671.7  319.79
  4911.6  316.83  4941.8  316.98  4992.3  310.23  4995.0  300.78  4995.7  300.28
  5030.0  300.78  5032.7  309.13  5042.8  311.44  5083.2  313.66  5088.5  311.46
  5164.0  317.47  5212.0  317.91  5472.0  318.63  5756.7  321.43  6078.8  322.70
  6281.3  326.61  6547.6  335.39  6816.3  348.16  7106.9  353.14  7179.0  355.05
#Mann=13,-1,0
  2963.0    0.05       0  4026.1    0.03       0  4048.9    0.05       0
  4333.1    0.12       0  4459.8    0.05       0  4671.7    0.12       0
  4911.6     0.1       0  4995.0    0.05       0  5030.0     0.1       0
  5212.0    0.05       0  5472.0    0.04       0  5756.7    0.05       0
  7106.9   0.013       0
Bank Sta=4995,5030
Exp/Cntr=0.3,0.1