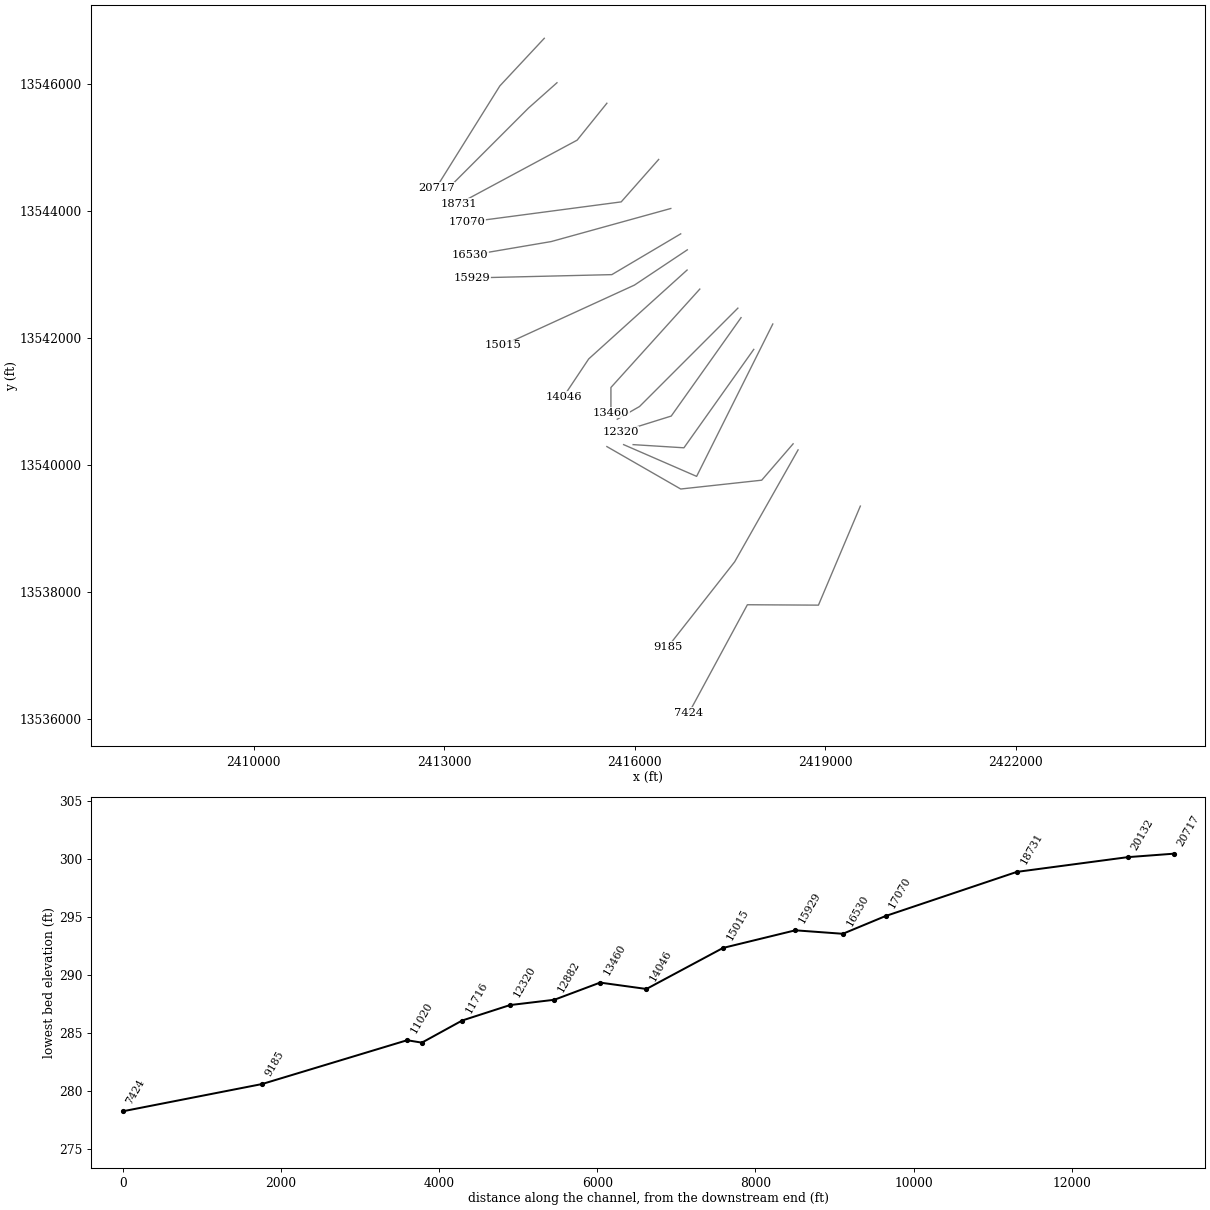
HEC-RAS study THOMAS CREEK.prj: THOMAS CREEK Base Level Engineering

--- THOMAS CREEK.g01 (geometry) --- (continued)

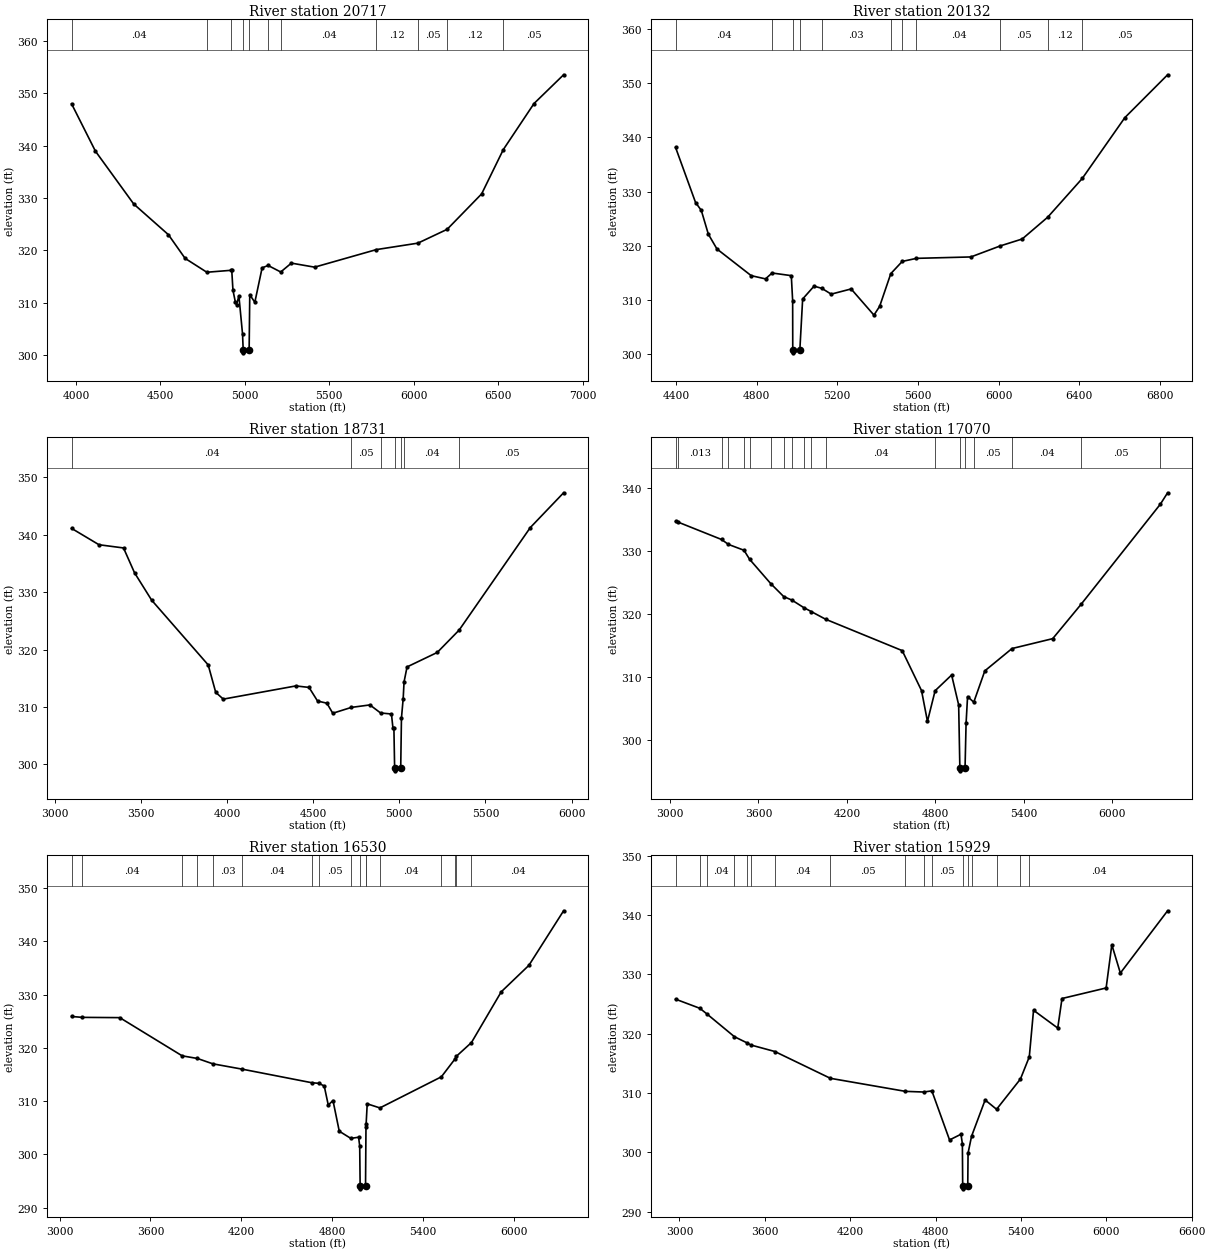
Type RM Length L Ch R = 1,20717,585,585,585
BEGIN DESCRIPTION:
THOMAS CREEK 25.0
END DESCRIPTION:
XS GIS Cut Line= 3
      2414574.98     13546724.98      2413875.00     13545975.00
      2412874.99     13544374.99
#Sta/Elev= 30
  3974.1  347.95  4115.5  338.91  4342.2  328.84  4547.4  322.99  4646.0  318.48
  4774.8  315.83  4917.9  316.20  4922.1  316.30  4929.4  312.40  4943.6  310.15
  4950.4  309.63  4964.6  311.31  4986.1  304.07  4990.1  300.96  4990.9  300.46
  5025.2  300.96  5028.9  311.54  5058.9  310.10  5102.0  316.67  5137.5  317.12
  5212.2  315.88  5275.3  317.57  5412.7  316.80  5778.5  320.15  6024.2  321.38
  6197.1  324.01  6401.5  330.77  6530.0  339.23  6711.7  348.01  6886.8  353.49
#Mann=11,-1,0
  3974.1    0.04       0  4774.8    0.05       0  4917.9     0.1       0
  4990.1    0.05       0  5025.2     0.1       0  5137.5    0.05       0
  5212.2    0.04       0  5778.5    0.12       0  6024.2    0.05       0
  6197.1    0.12       0  6530.0    0.05       0
Bank Sta=4990.1,5025.2
Exp/Cntr=0.3,0.1

Type RM Length L Ch R = 1,20132,1401,1401,1401
BEGIN DESCRIPTION:
THOMAS CREEK 24.0
END DESCRIPTION:
XS GIS Cut Line= 3
      2414774.99     13546024.99      2414325.00     13545625.00
      2413025.03     13544325.03
#Sta/Elev= 30
  4398.2  338.15  4497.3  327.97  4525.7  326.52  4560.8  322.10  4603.5  319.37
  4773.2  314.44  4844.3  313.84  4876.8  314.93  4972.2  314.44  4978.9  309.79
  4979.4  300.66  4980.1  300.16  5014.5  300.66  5028.5  310.12  5085.1  312.50
  5123.7  312.09  5170.0  311.02  5269.0  311.98  5382.1  307.14  5410.4  308.76
  5465.7  314.81  5522.4  317.07  5593.1  317.64  5862.9  317.90  6008.7  319.94
  6117.5  321.22  6244.2  325.26  6415.4  332.42  6626.6  343.67  6838.7  351.60
#Mann=11,-1,0
  4398.2    0.04       0  4876.8     0.1       0  4979.4    0.05       0
  5014.5     0.1       0  5123.7    0.03       0  5465.7    0.04       0
  5522.4    0.03       0  5593.1    0.04       0  6008.7    0.05       0
  6244.2    0.12       0  6415.4    0.05       0
Bank Sta=4979.4,5014.5
Exp/Cntr=0.3,0.1

Type RM Length L Ch R = 1,18731,1661,1661,1661
BEGIN DESCRIPTION:
Mapping XS 61bc49c5
END DESCRIPTION:
XS GIS Cut Line= 3
      2415561.16     13545702.29      2415092.41     13545120.70
      2413234.74     13544122.41
#Sta/Elev= 30
  3097.9  341.12  3257.0  338.27  3399.4  337.71  3463.4  333.38  3562.6  328.62
  3890.8  317.34  3934.6  312.56  3978.5  311.38  4399.8  313.68  4476.1  313.42
  4525.6  311.05  4579.9  310.67  4613.9  308.92  4722.1  309.94  4829.6  310.37
  4891.4  308.97  4954.5  308.79  4963.1  306.39  4968.8  306.31  4973.0  299.39
  4973.8  298.89  5008.3  299.39  5012.6  308.09  5022.6  311.44  5027.7  314.38
  5045.1  316.99  5220.4  319.51  5347.6  323.41  5760.5  341.26  5953.8  347.32
#Mann=7,-1,0
  3097.9    0.04       0  4722.1    0.05       0  4891.4     0.1       0
  4973.0    0.05       0  5008.3     0.1       0  5027.7    0.04       0
  5347.6    0.05       0
Bank Sta=4973,5008.3
Exp/Cntr=0.3,0.1

Type RM Length L Ch R = 1,17070,540,540,540
BEGIN DESCRIPTION:
Mapping XS 0aacb381
END DESCRIPTION:
XS GIS Cut Line= 3
      2416377.13     13544816.87      2415786.86     13544148.47
      2413358.20     13543827.54
#Sta/Elev= 30
  3036.9  334.65  3052.3  334.55  3349.0  331.78  3395.7  331.00  3501.6  330.07
  3539.6  328.64  3683.5  324.77  3771.5  322.72  3827.3  322.16  3906.4  320.99
  3957.9  320.35  4056.7  319.12  4576.1  314.15  4707.2  307.81  4747.5  302.93
  4799.5  307.79  4911.6  310.28  4959.4  305.54  4967.5  295.58  4968.2  295.08
  5002.8  295.58  5009.8  302.63  5019.9  306.86  5062.0  305.97  5137.1  310.94
  5321.7  314.48  5598.1  316.05  5790.6  321.49  6329.5  337.39  6378.4  339.19
#Mann=19,-1,0
  3036.9    0.04       0  3052.3   0.013       0  3349.0    0.04       0
  3395.7   0.013       0  3501.6    0.04       0  3539.6   0.013       0
  3683.5    0.04       0  3771.5   0.013       0  3827.3    0.05       0
  3906.4   0.013       0  3957.9    0.05       0  4056.7    0.04       0
  4799.5    0.12       0  4967.5    0.04       0  5002.8    0.12       0
  5062.0    0.05       0  5321.7    0.04       0  5790.6    0.05       0
  6329.5   0.013       0
Bank Sta=4967.5,5002.8
Exp/Cntr=0.3,0.1

Type RM Length L Ch R = 1,16530,601,601,601
BEGIN DESCRIPTION:
Mapping XS 04d97e97
END DESCRIPTION:
XS GIS Cut Line= 3
      2416568.14     13544044.31      2414684.42     13543523.47
      2413409.23     13543306.60
#Sta/Elev= 30
  3079.6  325.91  3149.6  325.74  3397.6  325.69  3809.4  318.52  3910.7  318.02
  4011.9  317.02  4205.3  316.02  4663.4  313.48  4713.7  313.35  4747.5  312.84
  4774.0  309.28  4805.1  310.13  4846.6  304.37  4922.9  303.02  4974.2  303.24
  4981.5  301.60  4984.5  294.05  4985.3  293.55  5020.0  294.05  5023.0  305.21
  5024.1  305.79  5031.1  309.51  5114.8  308.74  5520.6  314.58  5612.7  318.01
  5619.9  318.44  5719.2  321.01  5915.9  330.54  6098.5  335.51  6327.5  345.75
#Mann=17,-1,0
  3079.6    0.05       0  3149.6    0.04       0  3809.4    0.05       0
  3910.7   0.013       0  4011.9    0.03       0  4205.3    0.04       0
  4663.4    0.03       0  4713.7    0.05       0  4922.9    0.12       0
  4984.5    0.05       0  5020.0    0.12       0  5024.1    0.05       0
  5114.8    0.04       0  5520.6    0.05       0  5612.7   0.013       0
  5619.9    0.05       0  5719.2    0.04       0
Bank Sta=4984.5,5020
Exp/Cntr=0.3,0.1

Type RM Length L Ch R = 1,15929,914,914,914
BEGIN DESCRIPTION:
Mapping XS 43751ac5
END DESCRIPTION:
XS GIS Cut Line= 3
      2416724.37     13543645.01      2415639.29     13543002.64
      2413443.07     13542950.56
#Sta/Elev= 30
  2973.1  325.82  3143.7  324.28  3193.3  323.33  3386.8  319.49  3472.1  318.49
  3501.6  318.10  3670.4  317.00  4061.0  312.48  4588.6  310.28  4715.9  310.17
  4774.2  310.36  4898.5  302.09  4978.6  303.05  4988.6  301.48  4990.8  294.35
  4991.6  293.85  5026.4  294.35  5028.6  299.88  5053.2  302.72  5148.6  308.83
  5228.9  307.26  5396.7  312.36  5458.9  316.10  5488.7  323.95  5658.8  320.95
  5688.8  325.93  5998.9  327.71  6038.9  334.99  6098.9  330.22  6430.9  340.72
#Mann=17,-1,0
  2973.1    0.04       0  3143.7    0.05       0  3193.3    0.04       0
  3386.8    0.05       0  3472.1    0.04       0  3501.6    0.05       0
  3670.4    0.04       0  4061.0    0.05       0  4588.6   0.013       0
  4715.9    0.03       0  4774.2    0.05       0  4990.8    0.05       0
  5026.4    0.05       0  5053.2   0.013       0  5228.9    0.05       0
  5396.7   0.013       0  5458.9    0.04       0
Bank Sta=4990.8,5026.4
Exp/Cntr=0.3,0.1

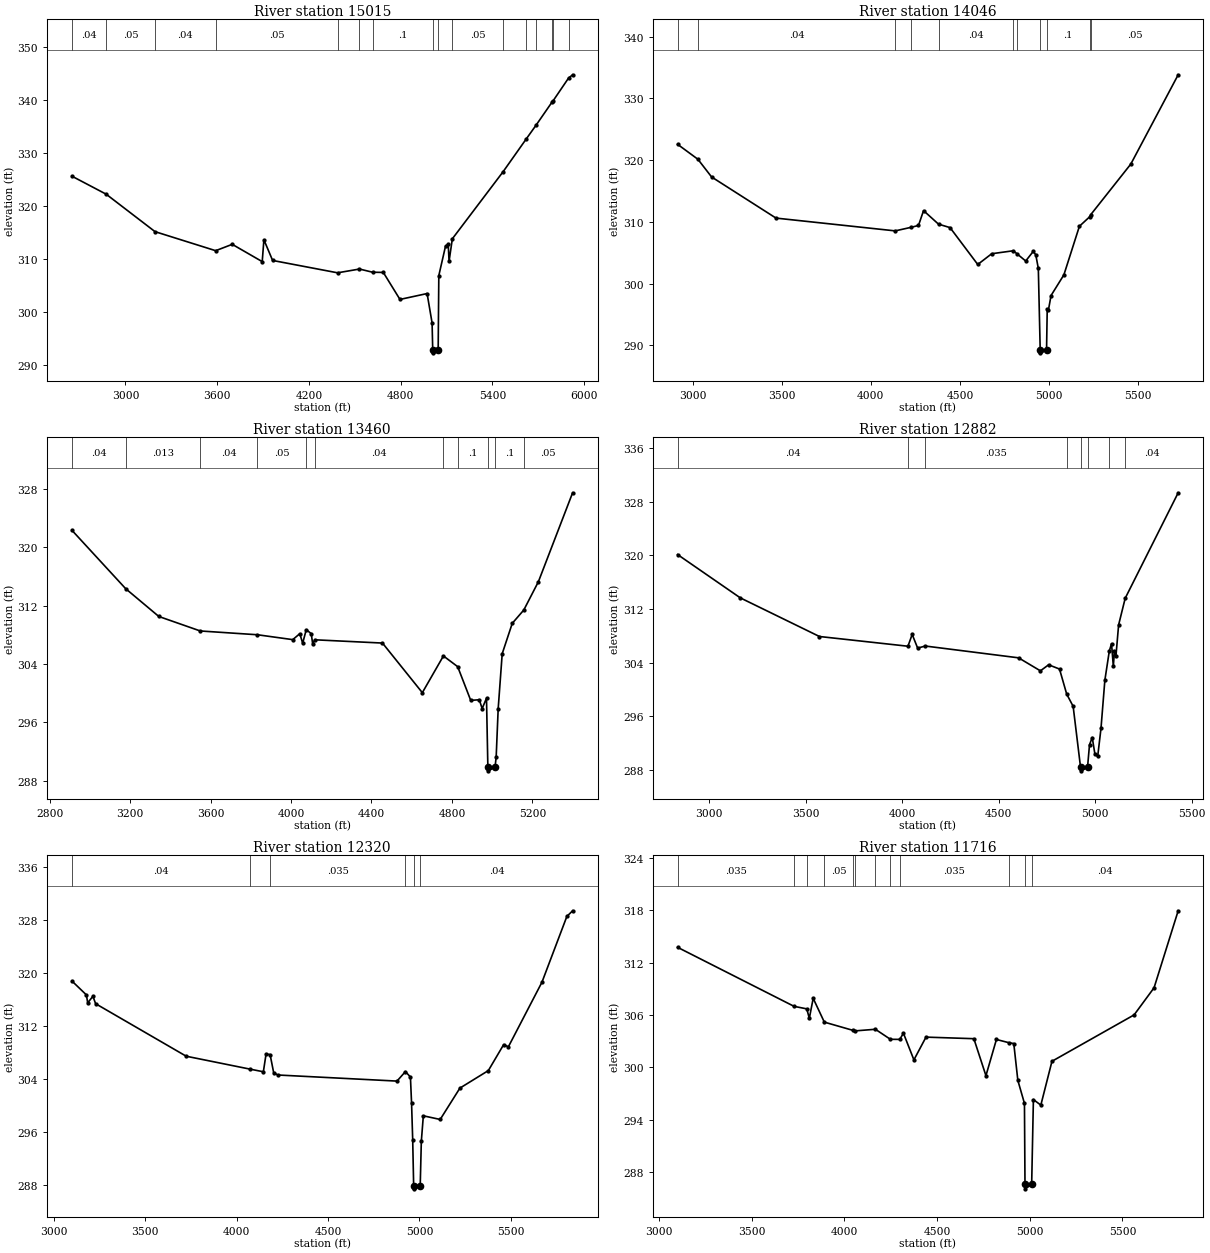
Type RM Length L Ch R = 1,15015,969,969,969
BEGIN DESCRIPTION:
Mapping XS bec8ecb1
END DESCRIPTION:
XS GIS Cut Line= 3
      2416828.55     13543393.28      2415995.19     13542837.71
      2413929.59     13541891.70
#Sta/Elev= 30
  2650.5  325.63  2873.6  322.25  3193.4  315.18  3589.9  311.59  3698.2  312.79
  3894.3  309.53  3905.3  313.65  3962.3  309.75  4387.1  307.42  4530.4  308.13
  4616.2  307.53  4686.2  307.49  4795.0  302.40  4972.5  303.51  5005.1  297.97
  5009.3  292.83  5010.1  292.33  5044.9  292.83  5049.1  306.90  5093.1  312.47
  5110.6  312.81  5116.1  309.59  5137.6  313.84  5470.2  326.51  5618.3  332.56
  5683.7  335.20  5790.4  339.65  5793.6  339.73  5897.2  344.13  5924.0  344.76
#Mann=16,-1,0
  2650.5    0.04       0  2873.6    0.05       0  3193.4    0.04       0
  3589.9    0.05       0  4387.1   0.013       0  4530.4    0.05       0
  4616.2     0.1       0  5009.3    0.05       0  5044.9     0.1       0
  5137.6    0.05       0  5470.2    0.03       0  5618.3    0.05       0
  5683.7   0.013       0  5790.4    0.04       0  5793.6   0.013       0
  5897.2    0.04       0
Bank Sta=5009.3,5044.9
Exp/Cntr=0.3,0.1

Type RM Length L Ch R = 1,14046,586,586,586
BEGIN DESCRIPTION:
THOMAS CREEK 16.0
END DESCRIPTION:
XS GIS Cut Line= 3
      2416825.02     13543075.02      2415275.00     13541675.00
      2414875.00     13541075.00
#Sta/Elev= 30
  2915.5  322.56  3029.6  320.14  3106.5  317.27  3468.0  310.61  4137.1  308.54
  4228.2  309.13  4267.7  309.42  4296.1  311.82  4380.1  309.63  4444.8  309.07
  4600.3  303.10  4678.7  304.84  4799.5  305.32  4819.9  304.85  4869.4  303.66
  4911.9  305.22  4926.1  304.66  4940.3  302.46  4950.8  289.29  4951.6  288.79
  4986.5  289.29  4990.3  295.89  4997.1  295.73  5011.7  298.07  5083.8  301.42
  5170.9  309.29  5229.2  310.84  5234.9  311.18  5459.4  319.36  5725.3  333.82
#Mann=11,-1,0
  2915.5    0.05       0  3029.6    0.04       0  4137.1    0.05       0
  4228.2   0.013       0  4380.1    0.04       0  4799.5    0.05       0
  4819.9     0.1       0  4950.8    0.05       0  4986.5     0.1       0
  5229.2    0.12       0  5234.9    0.05       0
Bank Sta=4950.8,4986.5
Exp/Cntr=0.3,0.1

Type RM Length L Ch R = 1,13460,578,578,578
BEGIN DESCRIPTION:
THOMAS CREEK 15.0
END DESCRIPTION:
XS GIS Cut Line= 3
      2417025.01     13542775.01      2415625.00     13541225.00
      2415625.00     13540824.97
#Sta/Elev= 30
  2911.3  322.35  3178.3  314.34  3342.9  310.53  3548.9  308.54  3833.3  308.02
  4008.7  307.35  4043.8  308.17  4058.0  306.85  4075.8  308.72  4100.6  308.17
  4108.1  306.70  4117.7  307.33  4454.8  306.88  4652.9  300.07  4757.7  305.11
  4828.6  303.64  4893.5  299.01  4936.1  299.10  4950.3  297.89  4971.9  299.31
  4978.7  289.84  4979.5  289.34  5014.4  289.84  5020.0  291.24  5030.0  297.88
  5050.0  305.42  5100.0  309.59  5157.4  311.42  5230.0  315.31  5400.0  327.51
#Mann=11,-1,0
  2911.3    0.04       0  3178.3   0.013       0  3548.9    0.04       0
  3833.3    0.05       0  4075.8   0.013       0  4117.7    0.04       0
  4757.7    0.05       0  4828.6     0.1       0  4978.7    0.05       0
  5014.4     0.1       0  5157.4    0.05       0
Bank Sta=4978.7,5014.4
Exp/Cntr=0.3,0.1

Type RM Length L Ch R = 1,12882,562,562,562
BEGIN DESCRIPTION:
THOMAS CREEK 14.0
END DESCRIPTION:
XS GIS Cut Line= 3
      2417624.98     13542474.98      2416075.00     13540925.00
      2415725.01     13540725.00
#Sta/Elev= 30
  2835.3  320.11  3160.5  313.65  3570.7  307.89  4029.5  306.44  4051.5  308.20
  4079.8  306.16  4119.3  306.47  4603.0  304.71  4716.2  302.77  4758.6  303.67
  4815.2  303.04  4852.5  299.30  4885.9  297.48  4924.4  288.36  4925.3  287.86
  4960.4  288.36  4970.7  291.75  4984.9  292.83  4999.0  290.31  5013.2  290.02
  5030.2  294.18  5050.3  301.37  5073.4  305.73  5084.9  306.82  5094.2  303.44
  5100.0  305.70  5107.9  305.02  5121.6  309.62  5155.7  313.59  5430.4  329.32
#Mann=8,-1,0
  2835.3    0.04       0  4029.5   0.013       0  4119.3   0.035       0
  4852.5    0.05       0  4924.4    0.05       0  4960.4    0.05       0
  5073.4     0.1       0  5155.7    0.04       0
Bank Sta=4924.4,4960.4
Exp/Cntr=0.3,0.1

Type RM Length L Ch R = 1,12320,604,604,604
BEGIN DESCRIPTION:
THOMAS CREEK 13.0
END DESCRIPTION:
XS GIS Cut Line= 3
      2417674.99     13542324.99      2416575.00     13540775.00
      2415775.00     13540525.00
#Sta/Elev= 30
  3099.4  318.81  3178.1  316.72  3185.2  315.52  3213.8  316.51  3228.6  315.39
  3724.3  307.45  4073.1  305.50  4146.3  305.10  4161.1  307.79  4183.2  307.69
  4203.0  304.92  4226.3  304.61  4877.4  303.69  4923.6  305.13  4950.9  304.30
  4957.0  300.43  4963.3  294.84  4968.5  287.90  4969.4  287.40  5004.5  287.90
  5010.5  294.58  5021.5  298.44  5113.7  297.89  5221.6  302.63  5377.2  305.28
  5461.0  309.21  5486.7  308.87  5670.6  318.65  5806.8  328.59  5838.2  329.44
#Mann=6,-1,0
  3099.4    0.04       0  4073.1   0.013       0  4183.2   0.035       0
  4923.6    0.05       0  4968.5    0.05       0  5004.5    0.04       0
Bank Sta=4968.5,5004.5
Exp/Cntr=0.3,0.1

Type RM Length L Ch R = 1,11716,510,510,510
BEGIN DESCRIPTION:
THOMAS CREEK 12.0
END DESCRIPTION:
XS GIS Cut Line= 3
      2417875.01     13541825.01      2416775.00     13540275.00
      2415975.03     13540325.00
#Sta/Elev= 30
  3099.0  313.77  3727.8  307.00  3796.5  306.71  3810.1  305.62  3831.0  307.92
  3891.1  305.19  4043.3  304.26  4054.3  304.18  4166.7  304.37  4247.8  303.22
  4298.4  303.21  4318.1  303.92  4374.7  300.86  4439.9  303.47  4698.3  303.29
  4763.5  299.05  4820.1  303.20  4885.6  302.84  4913.8  302.73  4935.7  298.51
  4971.4  295.87  4974.3  286.57  4975.1  286.07  5010.3  286.57  5019.7  296.31
  5059.8  295.67  5119.9  300.70  5563.3  306.02  5671.0  309.13  5801.2  317.96
#Mann=12,-1,0
  3099.0   0.035       0  3727.8    0.05       0  3796.5   0.013       0
  3891.1    0.05       0  4043.3   0.035       0  4054.3    0.05       0
  4166.7   0.035       0  4247.8    0.05       0  4298.4   0.035       0
  4885.6    0.04       0  4974.3    0.04       0  5010.3    0.04       0
Bank Sta=4974.3,5010.3
Exp/Cntr=0.3,0.1

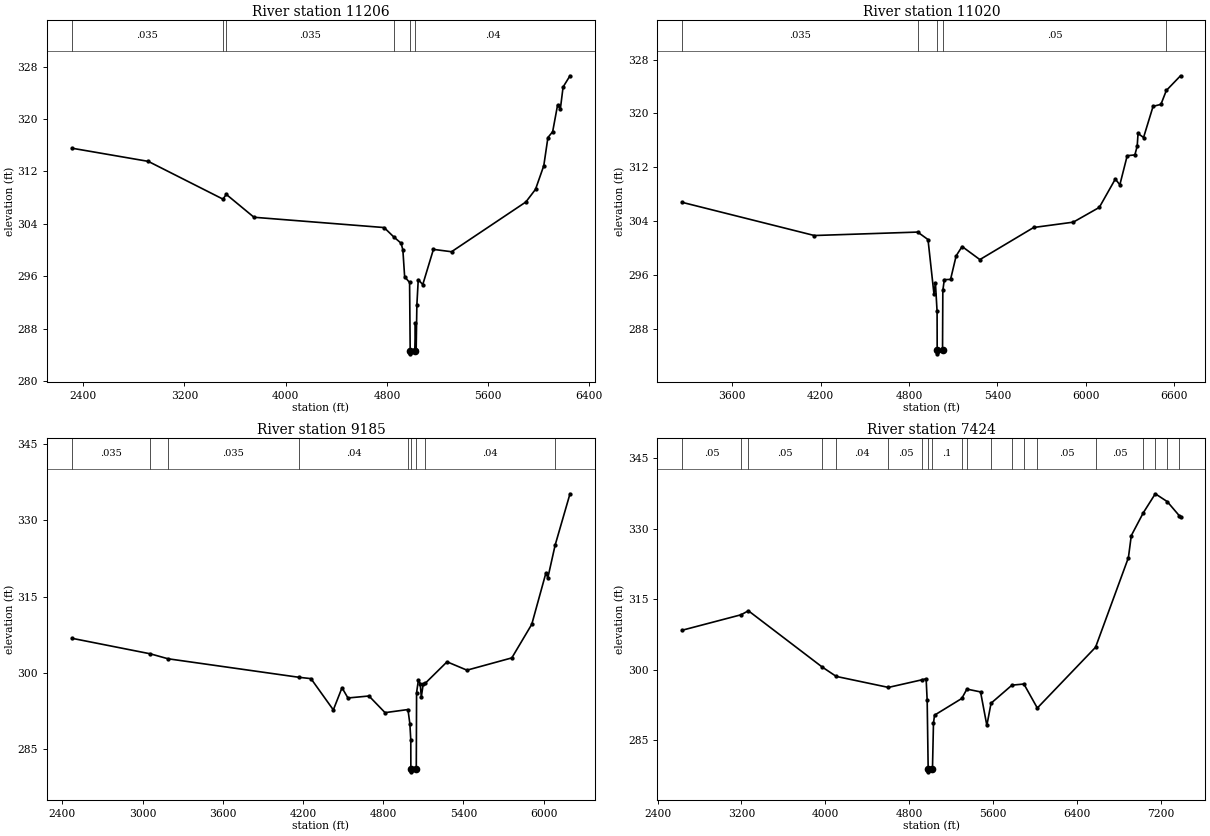
Type RM Length L Ch R = 1,11206,186,186,186
BEGIN DESCRIPTION:
THOMAS CREEK 11.0
END DESCRIPTION:
XS GIS Cut Line= 3
      2418174.99     13542224.98      2416975.00     13539825.00
      2415824.96     13540325.02
#Sta/Elev= 30
  2310.2  315.54  2913.9  313.53  3504.2  307.77  3530.7  308.49  3749.6  305.00
  4778.2  303.43  4853.5  302.02  4912.4  301.04  4926.4  300.02  4940.4  295.93
  4979.5  295.05  4984.3  284.66  4985.2  284.16  5020.6  284.66  5025.9  288.80
  5031.4  284.67  5037.1  291.64  5048.0  295.48  5083.7  294.73  5167.9  300.10
  5311.1  299.74  5898.5  307.33  5974.8  309.26  6040.3  312.87  6073.0  317.17
  6110.3  318.05  6149.3  322.12  6171.1  321.51  6192.9  324.88  6247.5  326.59
#Mann=6,-1,0
  2310.2   0.035       0  3504.2   0.013       0  3530.7   0.035       0
  4853.5    0.04       0  4984.3    0.04       0  5020.6    0.04       0
Bank Sta=4984.3,5020.6
Exp/Cntr=0.3,0.1

Type RM Length L Ch R = 1,11020,1835,1835,1835
BEGIN DESCRIPTION:
Mapping XS ac3590ef
END DESCRIPTION:
XS GIS Cut Line= 4
      2418495.17     13540337.69      2418000.40     13539764.79
      2416724.36     13539625.90      2415561.18     13540294.30
#Sta/Elev= 30
  3261.3  306.82  4157.2  301.91  4858.7  302.42  4929.0  301.31  4969.3  293.26
  4979.3  294.89  4990.6  290.65  4991.3  284.87  4992.2  284.37  5027.6  284.87
  5029.6  293.76  5039.7  295.37  5082.1  295.40  5120.1  298.90  5160.4  300.28
  5281.1  298.34  5646.3  303.10  5915.2  303.89  6092.0  306.08  6200.7  310.28
  6231.5  309.43  6281.5  313.74  6333.5  313.86  6349.3  315.16  6355.1  317.04
  6392.5  316.44  6457.2  321.06  6510.4  321.35  6547.1  323.41  6643.4  325.59
#Mann=5,-1,0
  3261.3   0.035       0  4858.7    0.05       0  4991.3    0.05       0
  5027.6    0.05       0  6547.1    0.05       0
Bank Sta=4991.3,5027.6
Exp/Cntr=0.3,0.1

Type RM Length L Ch R = 1,9185,1761,1761,1761
BEGIN DESCRIPTION:
Mapping XS 09052f62
END DESCRIPTION:
XS GIS Cut Line= 3
      2418573.29     13540242.18      2417575.05     13538480.07
      2416524.70     13537143.27
#Sta/Elev= 30
  2471.8  306.81  3058.3  303.76  3190.5  302.79  4170.4  299.15  4259.8  298.89
  4427.1  292.75  4492.0  297.10  4536.4  295.09  4693.6  295.48  4813.9  292.21
  4985.2  292.82  4999.4  290.04  5006.4  286.85  5006.9  281.09  5007.9  280.59
  5047.4  281.09  5049.7  296.12  5063.0  298.57  5076.9  297.91  5085.0  295.27
  5099.5  297.88  5113.5  297.95  5277.5  302.19  5426.6  300.55  5761.9  302.96
  5911.1  309.55  6016.9  319.63  6031.3  318.67  6085.7  325.08  6197.1  335.18
#Mann=9,-1,0
  2471.8   0.035       0  3058.3    0.12       0  3190.5   0.035       0
  4170.4    0.04       0  4985.2     0.1       0  5006.9    0.05       0
  5047.4     0.1       0  5113.5    0.04       0  6085.7    0.05       0
Bank Sta=5006.9,5047.4
Exp/Cntr=0.3,0.1

Type RM Length L Ch R = 1,7424,1384,1384,1384
BEGIN DESCRIPTION:
Mapping XS 9479be2a
END DESCRIPTION:
XS GIS Cut Line= 4
      2419554.20     13539356.77      2418894.22     13537796.76
      2417774.70     13537802.99      2416854.55     13536101.57
#Sta/Elev= 30
  2637.1  308.39  3196.5  311.67  3266.1  312.52  3967.6  300.58  4103.4  298.55
  4600.9  296.21  4924.7  297.85  4960.2  298.05  4970.2  293.44  4979.8  278.74
  4980.8  278.24  5020.6  278.74  5030.2  288.58  5040.2  290.30  5299.7  293.85
  5348.9  295.85  5479.0  295.25  5539.0  288.12  5578.9  292.84  5778.3  296.69
  5892.1  296.93  6020.0  291.82  6575.2  304.76  6888.1  323.82  6915.7  328.52
  7030.5  333.39  7144.4  337.42  7258.2  335.76  7372.1  332.78  7384.8  332.52
#Mann=20,-1,0
  2637.1    0.05       0  3196.5   0.013       0  3266.1    0.05       0
  3967.6   0.013       0  4103.4    0.04       0  4600.9    0.05       0
  4924.7     0.1       0  4979.8    0.05       0  5020.6     0.1       0
  5299.7    0.05       0  5348.9    0.12       0  5578.9    0.12       0
  5778.3    0.12       0  5892.1     0.1       0  6020.0    0.05       0
  6575.2    0.05       0  7030.5    0.04       0  7144.4    0.05       0
  7258.2    0.04       0  7372.1    0.04       0
Bank Sta=4979.8,5020.6
Exp/Cntr=0.3,0.1