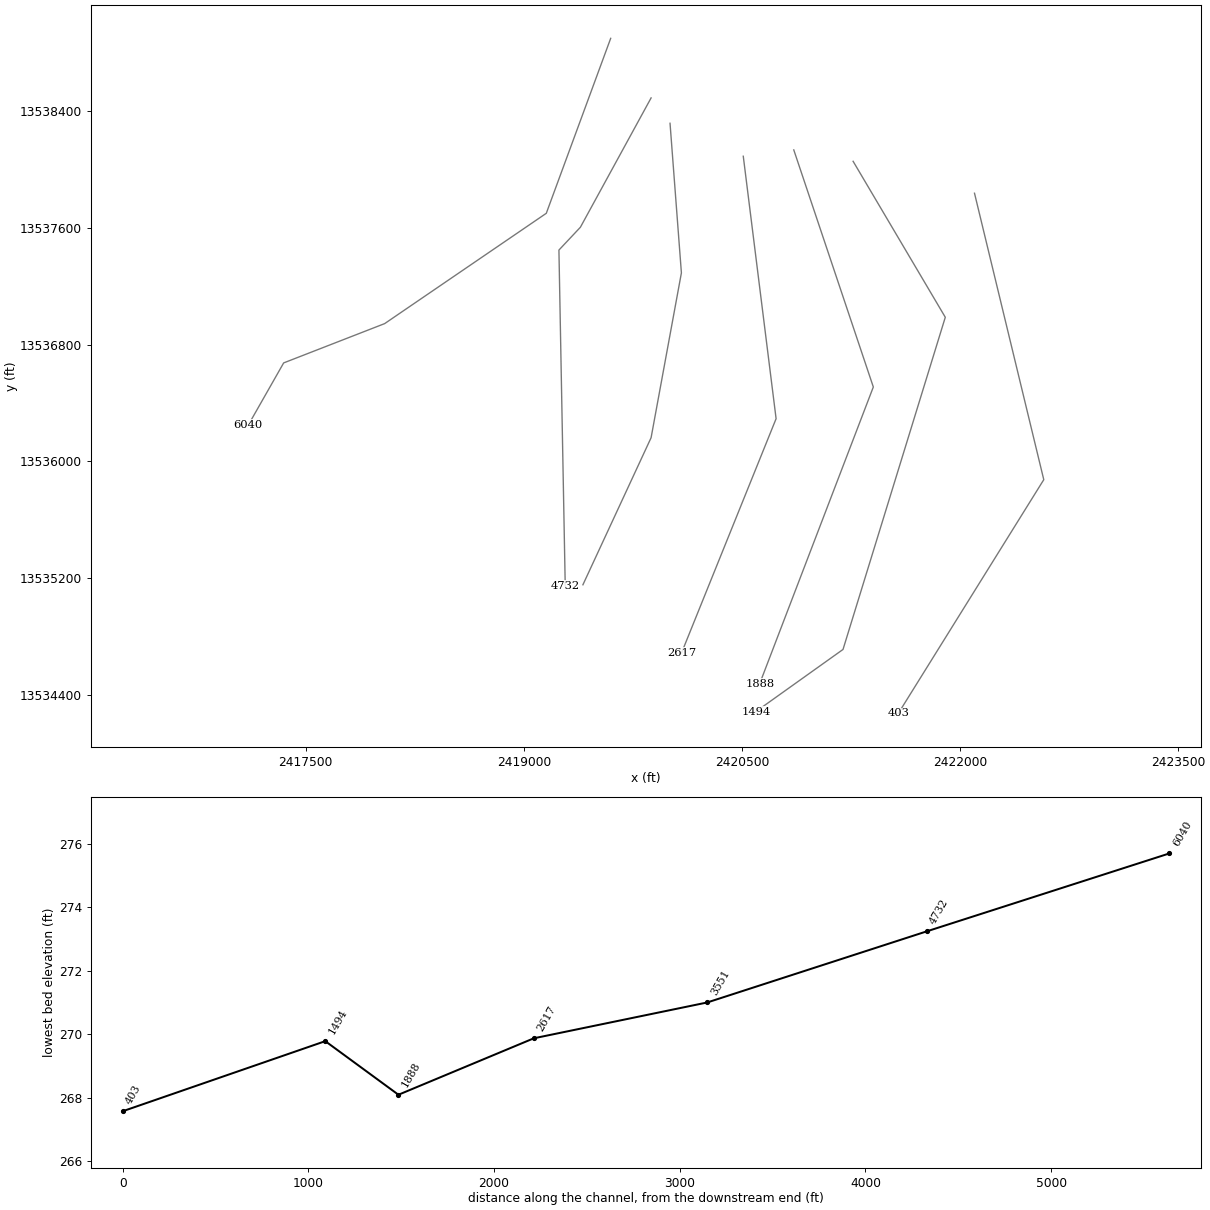
HEC-RAS study THOMAS CREEK.prj: THOMAS CREEK Base Level Engineering

--- THOMAS CREEK.g01 (geometry) --- (continued)

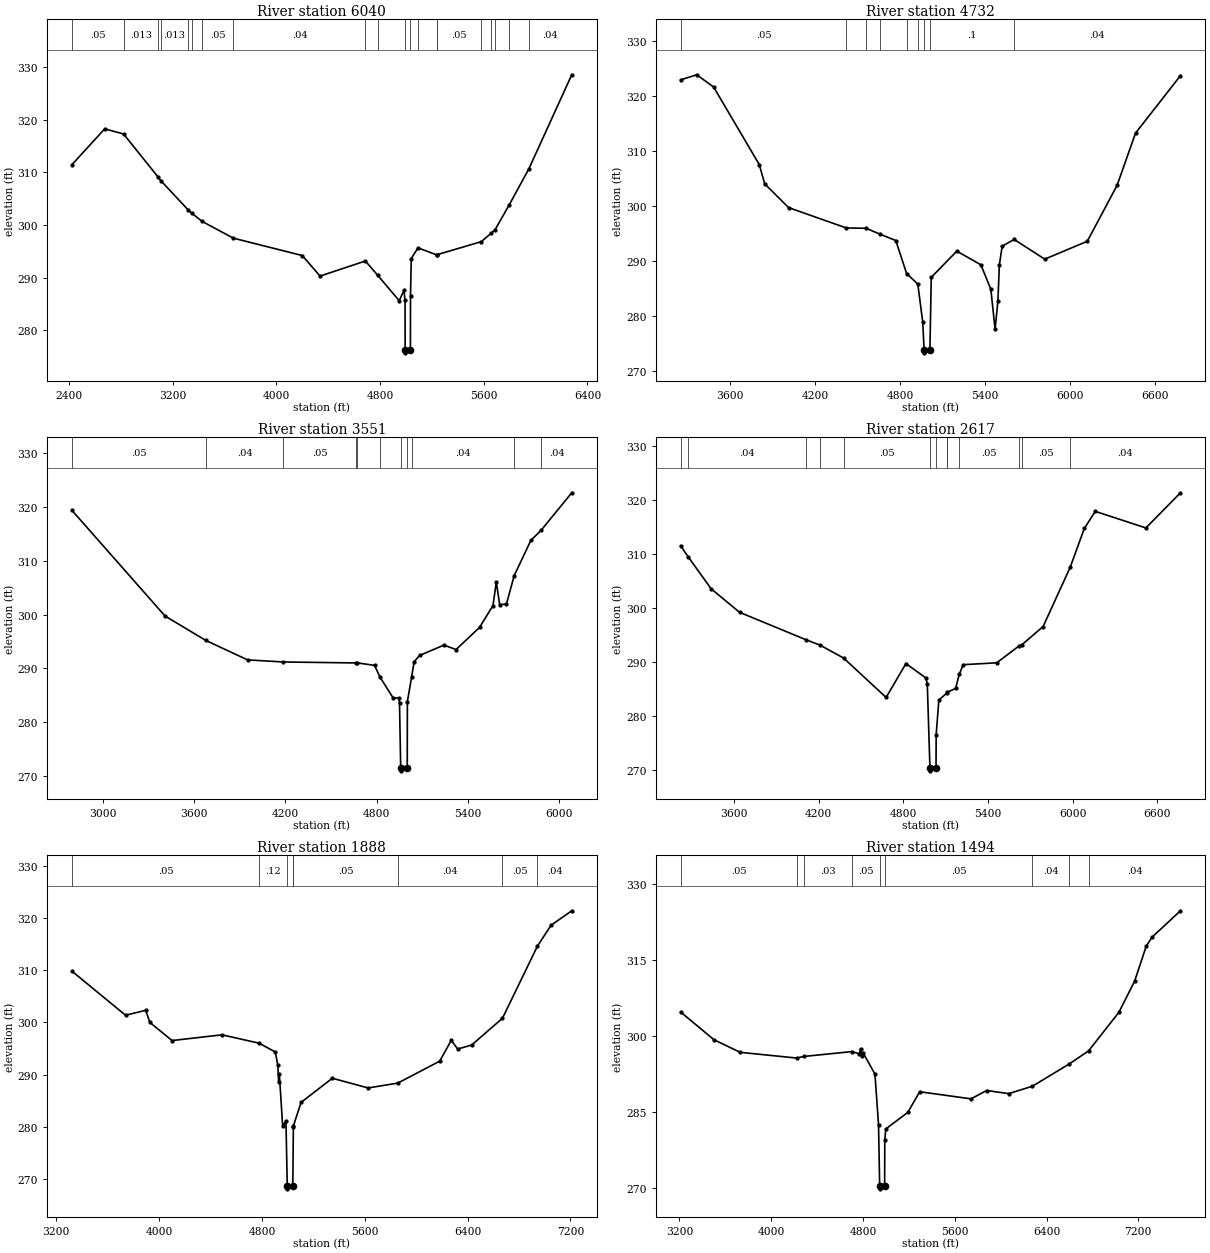
Type RM Length L Ch R = 1,6040,1308,1308,1308
BEGIN DESCRIPTION:
Mapping XS aabc7f34
END DESCRIPTION:
XS GIS Cut Line= 5
      2419597.60     13538896.70      2419154.91     13537698.82
      2418043.80     13536943.61      2417349.36     13536674.51
      2417106.54     13536249.59
#Sta/Elev= 30
  2424.2  311.48  2676.7  318.28  2822.0  317.31  3085.2  309.22  3108.4  308.46
  3320.8  302.86  3348.4  302.25  3427.0  300.70  3669.1  297.50  4200.1  294.20
  4337.8  290.29  4687.4  293.16  4782.4  290.43  4948.5  285.60  4984.4  287.59
  4993.3  285.70  4993.9  276.20  4994.9  275.70  5034.7  276.20  5035.3  286.57
  5041.0  293.61  5092.4  295.66  5237.3  294.32  5237.8  294.34  5580.7  296.83
  5658.5  298.46  5687.9  299.11  5797.8  303.88  5948.5  310.70  6278.9  328.56
#Mann=20,-1,0
  2424.2    0.05       0  2822.0   0.013       0  3085.2    0.05       0
  3108.4   0.013       0  3320.8    0.05       0  3348.4   0.013       0
  3427.0    0.05       0  3669.1    0.04       0  4687.4    0.05       0
  4782.4     0.1       0  4993.9    0.05       0  5034.7     0.1       0
  5092.4    0.05       0  5237.3    0.12       0  5237.8    0.05       0
  5580.7    0.12       0  5658.5    0.05       0  5687.9    0.12       0
  5797.8    0.05       0  5948.5    0.04       0
Bank Sta=4993.9,5034.7
Exp/Cntr=0.3,0.1

Type RM Length L Ch R = 1,4732,1181,1181,1181
BEGIN DESCRIPTION:
Mapping XS 15e2fcad
END DESCRIPTION:
XS GIS Cut Line= 4
      2419875.42     13538488.79      2419389.29     13537603.33
      2419241.72     13537447.08      2419285.09     13535148.34
#Sta/Elev= 30
  3252.8  322.96  3366.7  323.88  3485.3  321.65  3807.4  307.52  3845.2  304.03
  4013.9  299.69  4420.1  295.99  4560.5  295.92  4659.1  294.85  4770.0  293.69
  4846.2  287.68  4925.2  285.77  4960.0  278.82  4969.5  273.74  4970.5  273.24
  5010.5  273.74  5020.0  286.99  5200.1  291.76  5370.1  289.27  5440.1  284.83
  5470.1  277.53  5490.1  282.71  5500.1  289.21  5520.1  292.67  5604.6  293.89
  5820.2  290.30  6120.2  293.56  6330.3  303.74  6460.3  313.25  6777.0  323.71
#Mann=9,-1,0
  3252.8    0.05       0  4420.1    0.04       0  4560.5    0.05       0
  4659.1     0.1       0  4846.2    0.05       0  4925.2     0.1       0
  4969.5    0.05       0  5010.5     0.1       0  5604.6    0.04       0
Bank Sta=4969.5,5010.5
Exp/Cntr=0.3,0.1

Type RM Length L Ch R = 1,3551,934,934,934
BEGIN DESCRIPTION:
Mapping XS 13a566ab
END DESCRIPTION:
XS GIS Cut Line= 4
      2420005.60     13538315.16      2420083.73     13537290.83
      2419875.40     13536162.36      2419406.67     13535155.46
#Sta/Elev= 30
  2797.0  319.35  3408.9  299.74  3676.0  295.22  3951.1  291.60  4185.3  291.21
  4663.6  291.03  4670.6  291.05  4786.2  290.58  4821.4  288.43  4908.1  284.54
  4945.1  284.53  4950.2  283.57  4958.0  271.50  4959.0  271.00  5001.0  271.50
  5002.0  283.87  5029.5  288.37  5046.1  291.25  5082.1  292.42  5242.2  294.34
  5321.9  293.52  5476.3  297.62  5564.6  301.68  5586.6  306.05  5608.7  301.85
  5653.2  301.96  5703.7  307.21  5813.4  313.77  5880.8  315.65  6082.5  322.62
#Mann=11,-1,0
  2797.0    0.05       0  3676.0    0.04       0  4185.3    0.05       0
  4663.6    0.12       0  4670.6    0.05       0  4821.4     0.1       0
  4958.0    0.05       0  5001.0     0.1       0  5029.5    0.04       0
  5703.7    0.05       0  5880.8    0.04       0
Bank Sta=4958,5001
Exp/Cntr=0.3,0.1

Type RM Length L Ch R = 1,2617,729,729,729
BEGIN DESCRIPTION:
Mapping XS 0cabbeef
END DESCRIPTION:
XS GIS Cut Line= 3
      2420509.07     13538089.47      2420734.77     13536292.57
      2420084.40     13534688.31
#Sta/Elev= 30
  3221.7  311.54  3273.6  309.53  3437.9  303.56  3639.4  299.21  4111.2  294.12
  4210.1  293.13  4376.8  290.74  4678.0  283.45  4818.6  289.73  4959.7  287.05
  4969.8  285.93  4988.6  270.37  4989.6  269.87  5031.7  270.37  5032.7  276.58
  5051.7  282.98  5107.0  284.23  5109.5  284.41  5170.4  285.11  5195.7  287.70
  5224.3  289.52  5461.7  289.86  5616.6  292.92  5640.0  293.20  5790.8  296.58
  5982.7  307.55  6082.8  314.74  6160.5  317.89  6519.2  314.82  6763.8  321.33
#Mann=13,-1,0
  3221.7    0.05       0  3273.6    0.04       0  4111.2    0.05       0
  4210.1    0.12       0  4376.8    0.05       0  4988.6    0.05       0
  5031.7    0.05       0  5107.0    0.05       0  5109.5    0.12       0
  5195.7    0.05       0  5616.6    0.04       0  5640.0    0.05       0
  5982.7    0.04       0
Bank Sta=4988.6,5031.7
Exp/Cntr=0.3,0.1

Type RM Length L Ch R = 1,1888,394,394,394
BEGIN DESCRIPTION:
Mapping XS ea618668
END DESCRIPTION:
XS GIS Cut Line= 3
      2420856.31     13538132.81      2421403.17     13536509.58
      2420622.24     13534479.15
#Sta/Elev= 30
  3322.0  309.83  3738.6  301.39  3896.1  302.33  3927.6  300.02  4100.6  296.53
  4489.1  297.63  4778.6  296.02  4903.7  294.34  4923.6  291.82  4929.9  288.62
  4935.2  290.12  4961.4  280.12  4986.9  281.06  4997.0  268.59  4998.0  268.09
  5040.2  268.59  5044.4  279.86  5045.5  280.22  5104.4  284.67  5347.6  289.30
  5626.2  287.44  5856.8  288.37  6183.3  292.58  6273.3  296.59  6322.6  294.90
  6431.9  295.68  6671.1  300.80  6942.9  314.62  7049.0  318.64  7210.3  321.42
#Mann=8,-1,0
  3322.0    0.05       0  4778.6    0.12       0  4997.0    0.05       0
  5040.2    0.12       0  5045.5    0.05       0  5856.8    0.04       0
  6671.1    0.05       0  6942.9    0.04       0
Bank Sta=4997,5040.2
Exp/Cntr=0.3,0.1

Type RM Length L Ch R = 1,1494,1091,1091,1091
BEGIN DESCRIPTION:
Mapping XS 08ee54b5
END DESCRIPTION:
XS GIS Cut Line= 4
      2421264.27     13538054.75      2421897.97     13536987.01
      2421194.84     13534712.71      2420595.86     13534287.34
#Sta/Elev= 30
  3210.5  304.67  3501.4  299.20  3729.4  296.72  4220.5  295.59  4287.0  295.91
  4701.5  296.86  4768.2  296.43  4778.6  297.43  4789.2  295.99  4799.6  296.68
  4904.3  292.43  4935.7  282.41  4945.5  270.28  4946.5  269.78  4988.7  270.28
  4990.1  279.44  4998.5  281.60  5191.1  284.87  5294.2  288.94  5741.7  287.54
  5877.7  289.18  6070.9  288.57  6277.2  290.03  6597.2  294.41  6766.8  297.01
  7031.1  304.62  7167.6  310.74  7268.5  317.62  7318.9  319.42  7567.3  324.65
#Mann=9,-1,0
  3210.5    0.05       0  4220.5    0.04       0  4287.0    0.03       0
  4701.5    0.05       0  4945.5    0.05       0  4988.7    0.05       0
  6277.2    0.04       0  6597.2    0.05       0  6766.8    0.04       0
Bank Sta=4945.5,4988.7
Exp/Cntr=0.3,0.1

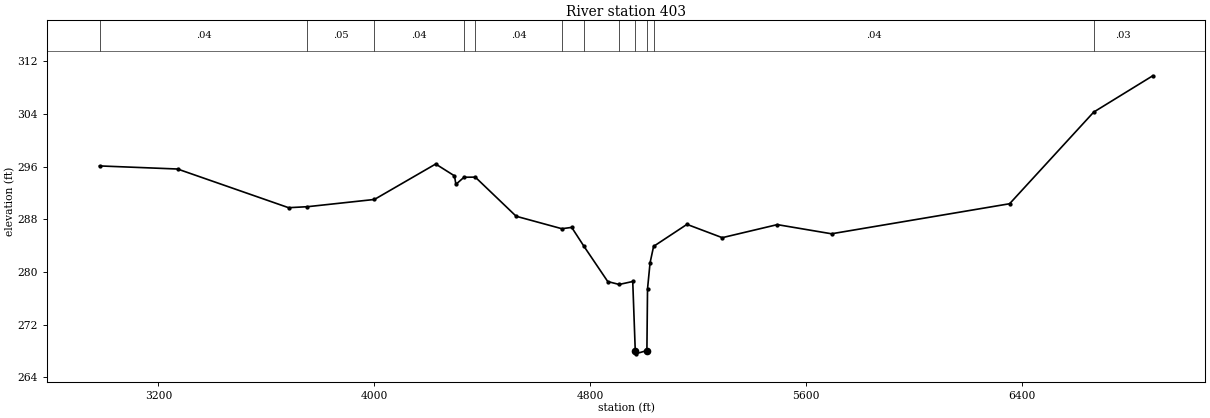
Type RM Length L Ch R = 1,403,0,0,0
BEGIN DESCRIPTION:
THOMAS CREEK 1.0
END DESCRIPTION:
XS GIS Cut Line= 3
      2422098.75     13537836.21      2422575.00     13535875.00
      2421575.00     13534275.00
#Sta/Elev= 30
  2981.4  296.09  3270.8  295.62  3682.4  289.75  3752.3  289.90  4000.6  291.00
  4227.8  296.38  4297.5  294.58  4302.7  293.29  4332.8  294.37  4374.6  294.39
  4526.2  288.45  4695.5  286.56  4732.1  286.76  4777.4  283.90  4865.8  278.54
  4908.1  278.10  4958.4  278.55  4967.7  268.07  4968.7  267.57  5010.9  268.07
  5013.2  277.42  5022.6  281.38  5035.7  283.88  5159.4  287.22  5290.3  285.20
  5494.3  287.18  5695.4  285.79  6355.7  290.35  6667.5  304.26  6886.4  309.77
#Mann=12,-1,0
  2981.4    0.04       0  3752.3    0.05       0  4000.6    0.04       0
  4332.8    0.03       0  4374.6    0.04       0  4695.5    0.05       0
  4777.4    0.04       0  4908.1    0.05       0  4967.7    0.05       0
  5010.9    0.05       0  5035.7    0.04       0  6667.5    0.03       0
Bank Sta=4967.7,5010.9
Exp/Cntr=0.3,0.1

Chan Stop Cuts=-1