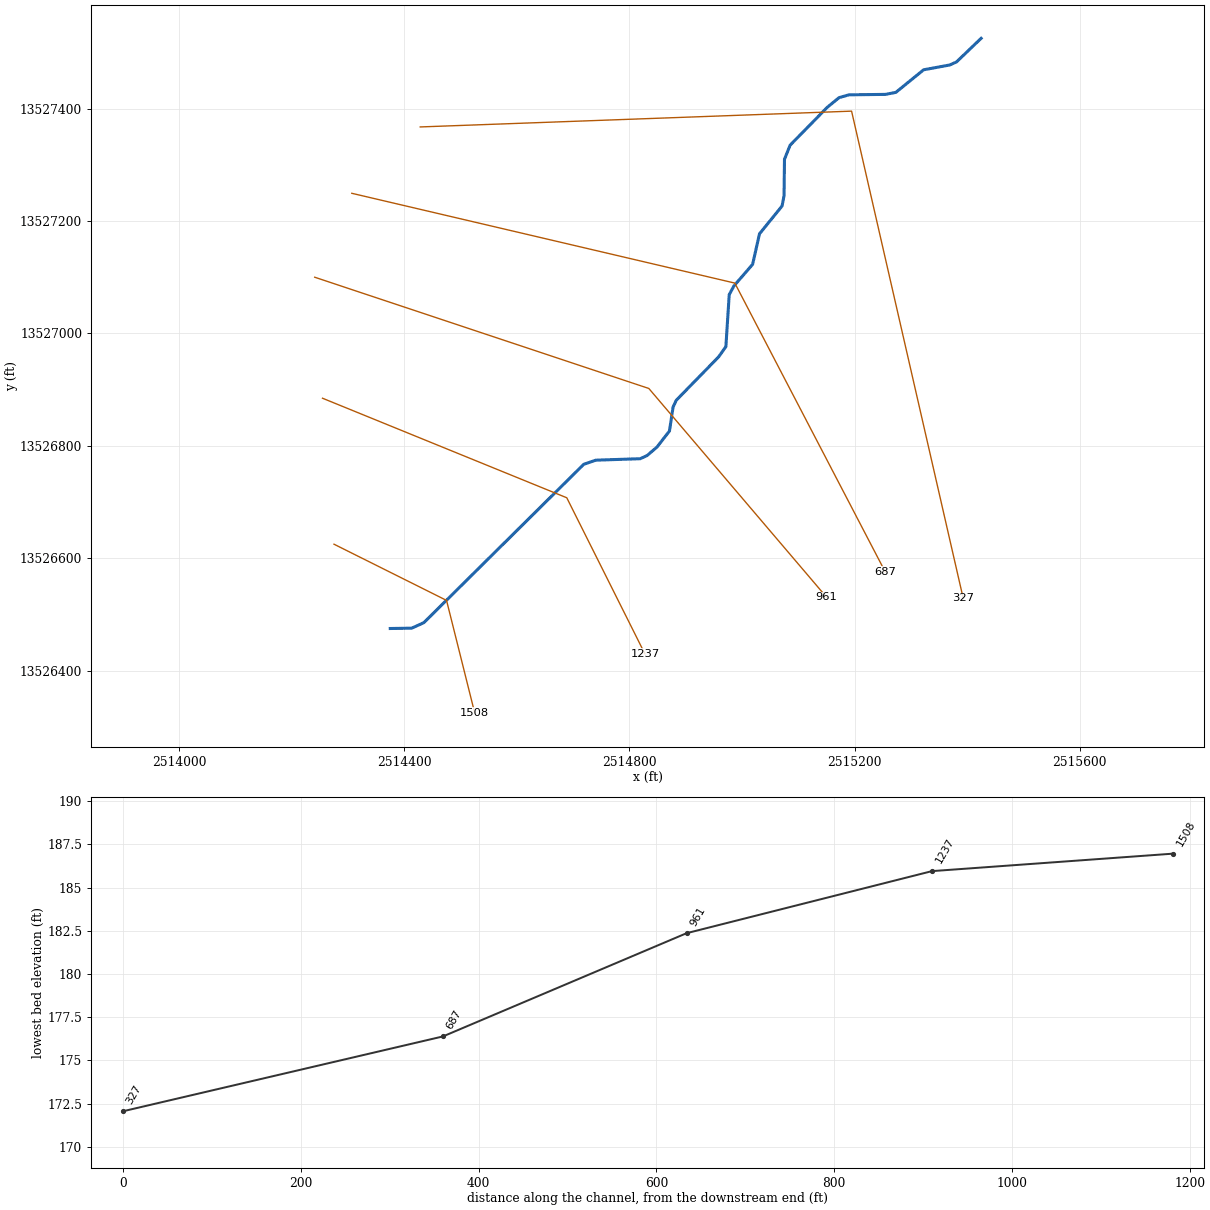
--- TRIB 1 TO BOGGY BRANCH.prj (project) ---

Proj Title=TRIB 1 TO BOGGY BRANCH Base Level Engineering
Current Plan=p01
Default Exp/Contr=0.3,0.1
English Units
Geom File=g01
Flow File=f01
Plan File=p01
BEGIN DESCRIPTION:
TRIB 1 TO BOGGY BRANCH
END DESCRIPTION:

--- TRIB 1 TO BOGGY BRANCH.p01 (plan) ---

Plan Title=Multiple Run
Short Identifier=Multiple
Geom File=g01
Flow File=f01
Subcritical Flow
K Sum by GR= 0
Std Step Tol= 0.01
Critical Tol= 0.01
Num of Std Step Trials= 20
Max Error Tol= 0.3
Flow Tol Ratio= 0.001
Split Flow NTrial= 30
Split Flow Tol= 0.02
Split Flow Ratio= 0.02
Log Output Level= 0
Friction Slope Method= 1
Unsteady Friction Slope Method= 2
Unsteady Bridges Friction Slope Method= 1
Parabolic Critical Depth
Global Vel Dist=  1 , 1 , 1
Global Log Level= 0
CheckData=True
Encroach Param= -1, 0, 0, 0
BEGIN DESCRIPTION:
Multiple Run
END DESCRIPTION:

--- TRIB 1 TO BOGGY BRANCH.f01 (steady flow) ---

Flow Title=Multiple
Number of Profiles=7
Profile Names=10-year,25-year,50-year,1pct_min,100-year,1pct_plu,500-year
River Rch & RM= TRIB 1 TO BOGGY ,Reach-1,1508
     271     413     535     337     673    1343    1049
Boundary for River Rch & Prof#=TRIB 1 TO BOGGY ,Reach-1,1
Up Type=0
Dn Type=3
Dn Slope=0.005
Boundary for River Rch & Prof#=TRIB 1 TO BOGGY ,Reach-1,2
Up Type=0
Dn Type=3
Dn Slope=0.005
Boundary for River Rch & Prof#=TRIB 1 TO BOGGY ,Reach-1,3
Up Type=0
Dn Type=3
Dn Slope=0.005
Boundary for River Rch & Prof#=TRIB 1 TO BOGGY ,Reach-1,4
Up Type=0
Dn Type=3
Dn Slope=0.005
Boundary for River Rch & Prof#=TRIB 1 TO BOGGY ,Reach-1,5
Up Type=0
Dn Type=3
Dn Slope=0.005
Boundary for River Rch & Prof#=TRIB 1 TO BOGGY ,Reach-1,6
Up Type=0
Dn Type=3
Dn Slope=0.005
Boundary for River Rch & Prof#=TRIB 1 TO BOGGY ,Reach-1,7
Up Type=0
Dn Type=3
Dn Slope=0.005

--- TRIB 1 TO BOGGY BRANCH.g01 (geometry) ---

Geom Title=Existing Conditions

River Reach=TRIB 1 TO BOGGY ,Reach-1
Reach XY= 30
      2514375.00     13526475.00      2514413.16     13526475.59
      2514434.79     13526485.51      2514718.83     13526767.14
      2514740.22     13526774.47      2514819.29     13526777.08
      2514831.45     13526782.75      2514848.89     13526797.72
      2514871.13     13526826.40      2514877.56     13526868.91
      2514883.19     13526881.02      2514958.51     13526958.26
      2514971.38     13526976.50      2514977.33     13527069.03
      2514985.84     13527084.65      2515018.89     13527122.82
      2515031.11     13527177.18      2515071.17     13527226.59
      2515074.76     13527245.10      2515075.52     13527309.79
      2515085.51     13527334.81      2515151.42     13527402.15
      2515172.56     13527419.48      2515190.21     13527424.48
      2515254.90     13527425.23      2515273.42     13527428.82
      2515322.78     13527468.97      2515368.96     13527477.51
      2515381.15     13527482.91      2515425.00     13527525.00

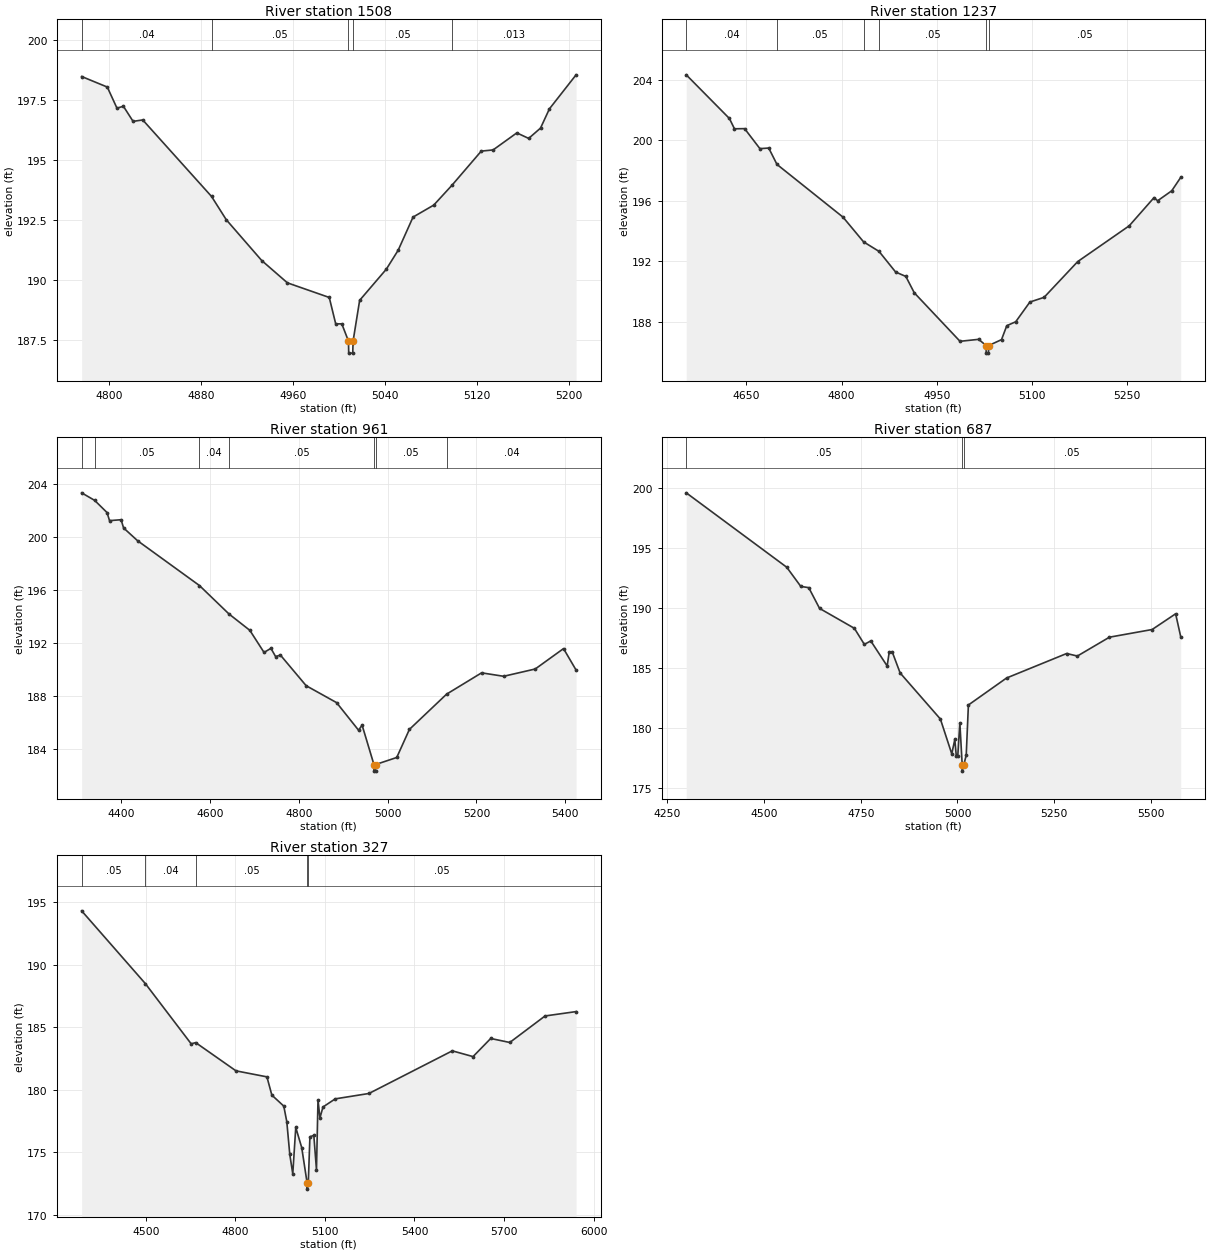
Type RM Length L Ch R = 1,1508,271,271,271
BEGIN DESCRIPTION:
TRIB 1 TO BOGGY BRANCH 3.0
END DESCRIPTION:
XS GIS Cut Line= 3
      2514275.04     13526624.98      2514475.00     13526525.00
      2514525.00     13526325.02
#Sta/Elev= 30
  4776.2  198.49  4798.5  198.05  4806.9  197.17  4812.5  197.25  4820.9  196.62
  4829.3  196.68  4889.1  193.49  4901.9  192.52  4932.7  190.82  4955.0  189.89
  4991.4  189.28  4997.0  188.18  5002.3  188.18  5008.1  187.46  5008.3  186.96
  5011.8  186.96  5012.1  187.46  5017.8  189.16  5041.0  190.46  5051.3  191.25
  5064.2  192.63  5082.2  193.13  5097.9  193.95  5123.5  195.38  5133.8  195.43
  5154.4  196.14  5164.7  195.91  5175.0  196.34  5182.7  197.14  5205.9  198.56
#Mann=5,-1,0
  4776.2    0.04       0  4889.1    0.05       0  5008.1    0.05       0
  5012.1    0.05       0  5097.9   0.013       0
Bank Sta=5008.1,5012.1
Exp/Cntr=0.3,0.1

Type RM Length L Ch R = 1,1237,276,276,276
BEGIN DESCRIPTION:
Mapping XS de328829
END DESCRIPTION:
XS GIS Cut Line= 3
      2514254.59     13526884.69      2514688.64     13526707.60
      2514827.51     13526429.87
#Sta/Elev= 30
  4555.2  204.31  4623.2  201.43  4631.2  200.75  4647.2  200.76  4671.3  199.44
  4685.2  199.48  4698.2  198.40  4802.3  194.92  4834.7  193.29  4859.1  192.66
  4885.2  191.30  4901.3  191.01  4914.6  189.93  4986.7  186.73  5016.1  186.86
  5027.8  186.45  5028.0  185.95  5031.5  185.95  5031.8  186.45  5052.1  186.84
  5060.4  187.76  5074.5  188.02  5096.8  189.32  5119.2  189.63  5172.2  191.99
  5253.4  194.35  5292.5  196.21  5298.1  196.00  5320.4  196.66  5334.5  197.54
#Mann=6,-1,0
  4555.2    0.04       0  4698.2    0.05       0  4834.7    0.04       0
  4859.1    0.05       0  5027.8    0.05       0  5031.8    0.05       0
Bank Sta=5027.8,5031.8
Exp/Cntr=0.3,0.1

Type RM Length L Ch R = 1,961,274,274,274
BEGIN DESCRIPTION:
Mapping XS ec6602c1
END DESCRIPTION:
XS GIS Cut Line= 3
      2514240.71     13527099.96      2514834.47     13526902.04
      2515150.25     13526530.75
#Sta/Elev= 30
  4311.0  203.37  4340.3  202.80  4368.2  201.88  4373.8  201.27  4399.9  201.34
  4405.4  200.72  4437.1  199.75  4576.3  196.37  4642.9  194.22  4689.7  192.99
  4721.7  191.32  4737.2  191.63  4747.7  191.01  4758.6  191.12  4816.5  188.81
  4885.1  187.53  4934.5  185.45  4942.5  185.83  4969.1  182.86  4969.3  182.36
  4972.8  182.36  4973.1  182.86  5020.5  183.39  5049.0  185.51  5132.7  188.17
  5211.5  189.78  5261.2  189.52  5332.3  190.07  5396.0  191.61  5424.3  189.99
#Mann=7,-1,0
  4311.0    0.03       0  4340.3    0.05       0  4576.3    0.04       0
  4642.9    0.05       0  4969.1    0.05       0  4973.1    0.05       0
  5132.7    0.04       0
Bank Sta=4969.1,4973.1
Exp/Cntr=0.3,0.1

Type RM Length L Ch R = 1,687,360,360,360
BEGIN DESCRIPTION:
Mapping XS ce8c0dea
END DESCRIPTION:
XS GIS Cut Line= 3
      2514306.66     13527249.27      2514987.25     13527089.54
      2515254.63     13526575.62
#Sta/Elev= 30
  4298.7  199.58  4558.5  193.38  4594.9  191.78  4615.4  191.68  4643.4  189.95
  4733.4  188.29  4759.2  186.95  4775.8  187.24  4818.2  185.15  4823.4  186.29
  4831.1  186.34  4851.7  184.57  4955.8  180.73  4985.2  177.83  4993.1  179.03
  4996.8  177.69  5000.8  177.69  5006.1  180.42  5012.2  176.89  5012.4  176.39
  5016.2  176.89  5022.6  177.73  5028.2  181.90  5126.9  184.15  5282.2  186.19
  5310.0  185.98  5392.8  187.55  5503.3  188.19  5564.0  189.50  5577.1  187.60
#Mann=3,-1,0
  4298.7    0.05       0  5012.2    0.05       0  5016.2    0.05       0
Bank Sta=5012.2,5016.2
Exp/Cntr=0.3,0.1

Type RM Length L Ch R = 1,327,0,0,0
BEGIN DESCRIPTION:
TRIB 1 TO BOGGY BRANCH 1.0
END DESCRIPTION:
XS GIS Cut Line= 3
      2514428.21     13527367.32      2515194.76     13527395.42
      2515393.17     13526528.51
#Sta/Elev= 30
  4285.0  194.32  4498.4  188.50  4652.0  183.68  4667.0  183.78  4802.1  181.52
  4905.7  181.04  4922.2  179.58  4962.2  178.70  4972.3  177.45  4982.3  174.83
  4992.3  173.28  5002.3  176.99  5022.3  175.38  5040.3  172.56  5040.6  172.06
  5044.3  172.56  5049.7  176.24  5062.8  176.36  5071.7  173.61  5076.8  179.20
  5083.3  177.75  5093.5  178.63  5134.6  179.28  5247.4  179.71  5526.7  183.12
  5596.2  182.66  5655.4  184.11  5719.3  183.79  5837.4  185.91  5941.4  186.26
#Mann=5,-1,0
  4285.0    0.05       0  4498.4    0.04       0  4667.0    0.05       0
  5040.3    0.05       0  5044.3    0.05       0
Bank Sta=5040.3,5044.3
Exp/Cntr=0.3,0.1

Chan Stop Cuts=-1