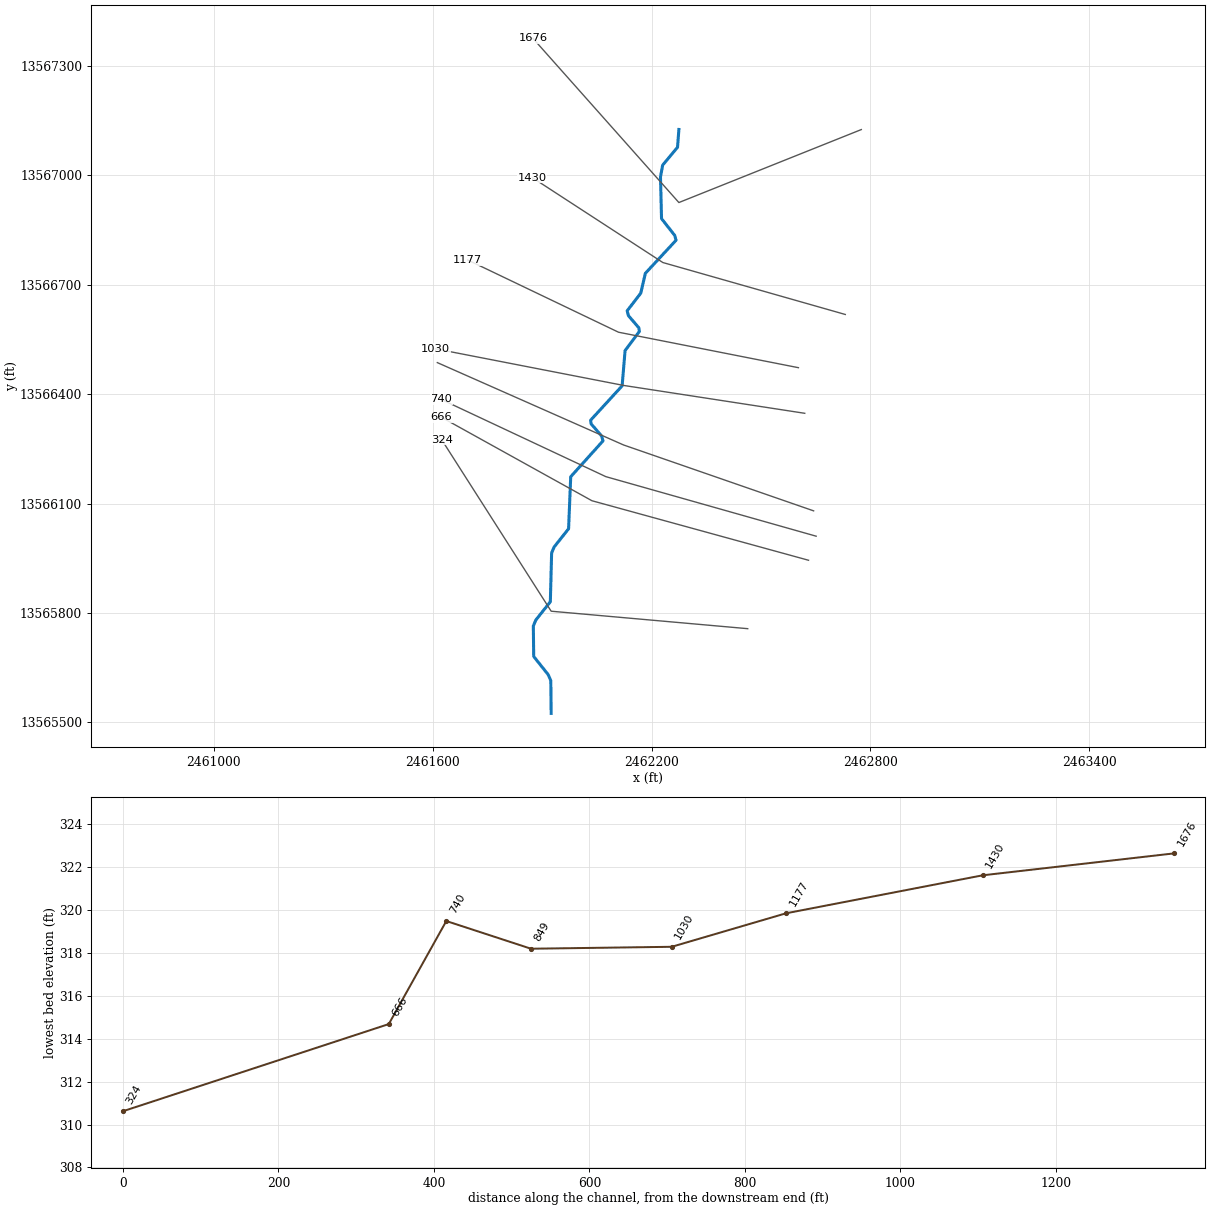
--- TRIB 1 TO COTTONWOOD CREEK.prj (project) ---

Proj Title=TRIB 1 TO COTTONWOOD CREEK Base Level Engineering
Current Plan=p01
Default Exp/Contr=0.3,0.1
English Units
Geom File=g01
Flow File=f01
Plan File=p01
BEGIN DESCRIPTION:
TRIB 1 TO COTTONWOOD CREEK
END DESCRIPTION:

--- TRIB 1 TO COTTONWOOD CREEK.p01 (plan) ---

Plan Title=Multiple Run
Short Identifier=Multiple
Geom File=g01
Flow File=f01
Subcritical Flow
K Sum by GR= 0
Std Step Tol= 0.01
Critical Tol= 0.01
Num of Std Step Trials= 20
Max Error Tol= 0.3
Flow Tol Ratio= 0.001
Split Flow NTrial= 30
Split Flow Tol= 0.02
Split Flow Ratio= 0.02
Log Output Level= 0
Friction Slope Method= 1
Unsteady Friction Slope Method= 2
Unsteady Bridges Friction Slope Method= 1
Parabolic Critical Depth
Global Vel Dist=  1 , 1 , 1
Global Log Level= 0
CheckData=True
Encroach Param= -1, 0, 0, 0
BEGIN DESCRIPTION:
Multiple Run
END DESCRIPTION:

--- TRIB 1 TO COTTONWOOD CREEK.f01 (steady flow) ---

Flow Title=Multiple
Number of Profiles=7
Profile Names=10-year,25-year,50-year,1pct_min,100-year,1pct_plu,500-year
River Rch & RM= TRIB 1 TO COTTON,Reach-1,1676
     590     950    1275     828    1653    3298    2753
Boundary for River Rch & Prof#=TRIB 1 TO COTTON,Reach-1,1
Up Type=0
Dn Type=3
Dn Slope=0.005
Boundary for River Rch & Prof#=TRIB 1 TO COTTON,Reach-1,2
Up Type=0
Dn Type=3
Dn Slope=0.005
Boundary for River Rch & Prof#=TRIB 1 TO COTTON,Reach-1,3
Up Type=0
Dn Type=3
Dn Slope=0.005
Boundary for River Rch & Prof#=TRIB 1 TO COTTON,Reach-1,4
Up Type=0
Dn Type=3
Dn Slope=0.005
Boundary for River Rch & Prof#=TRIB 1 TO COTTON,Reach-1,5
Up Type=0
Dn Type=3
Dn Slope=0.005
Boundary for River Rch & Prof#=TRIB 1 TO COTTON,Reach-1,6
Up Type=0
Dn Type=3
Dn Slope=0.005
Boundary for River Rch & Prof#=TRIB 1 TO COTTON,Reach-1,7
Up Type=0
Dn Type=3
Dn Slope=0.005

--- TRIB 1 TO COTTONWOOD CREEK.g01 (geometry) ---

Geom Title=Existing Conditions

River Reach=TRIB 1 TO COTTON,Reach-1
Reach XY= 30
      2462275.00     13567125.27      2462271.35     13567076.51
      2462230.53     13567027.42      2462224.59     13566995.14
      2462227.46     13566880.86      2462263.66     13566834.85
      2462267.19     13566821.59      2462183.16     13566731.05
      2462170.56     13566676.65      2462133.24     13566628.23
      2462136.81     13566614.96      2462165.23     13566581.73
      2462166.72     13566571.78      2462127.55     13566519.11
      2462119.45     13566422.57      2462033.02     13566328.33
      2462034.62     13566318.33      2462063.29     13566285.00
      2462066.98     13566271.67      2461978.57     13566173.53
      2461972.73     13566030.94      2461933.15     13565981.05
      2461926.23     13565964.49      2461922.73     13565830.94
      2461883.09     13565781.03      2461876.10     13565764.45
      2461877.14     13565680.97      2461916.88     13565631.07
      2461923.98     13565614.58      2461925.00     13565525.00

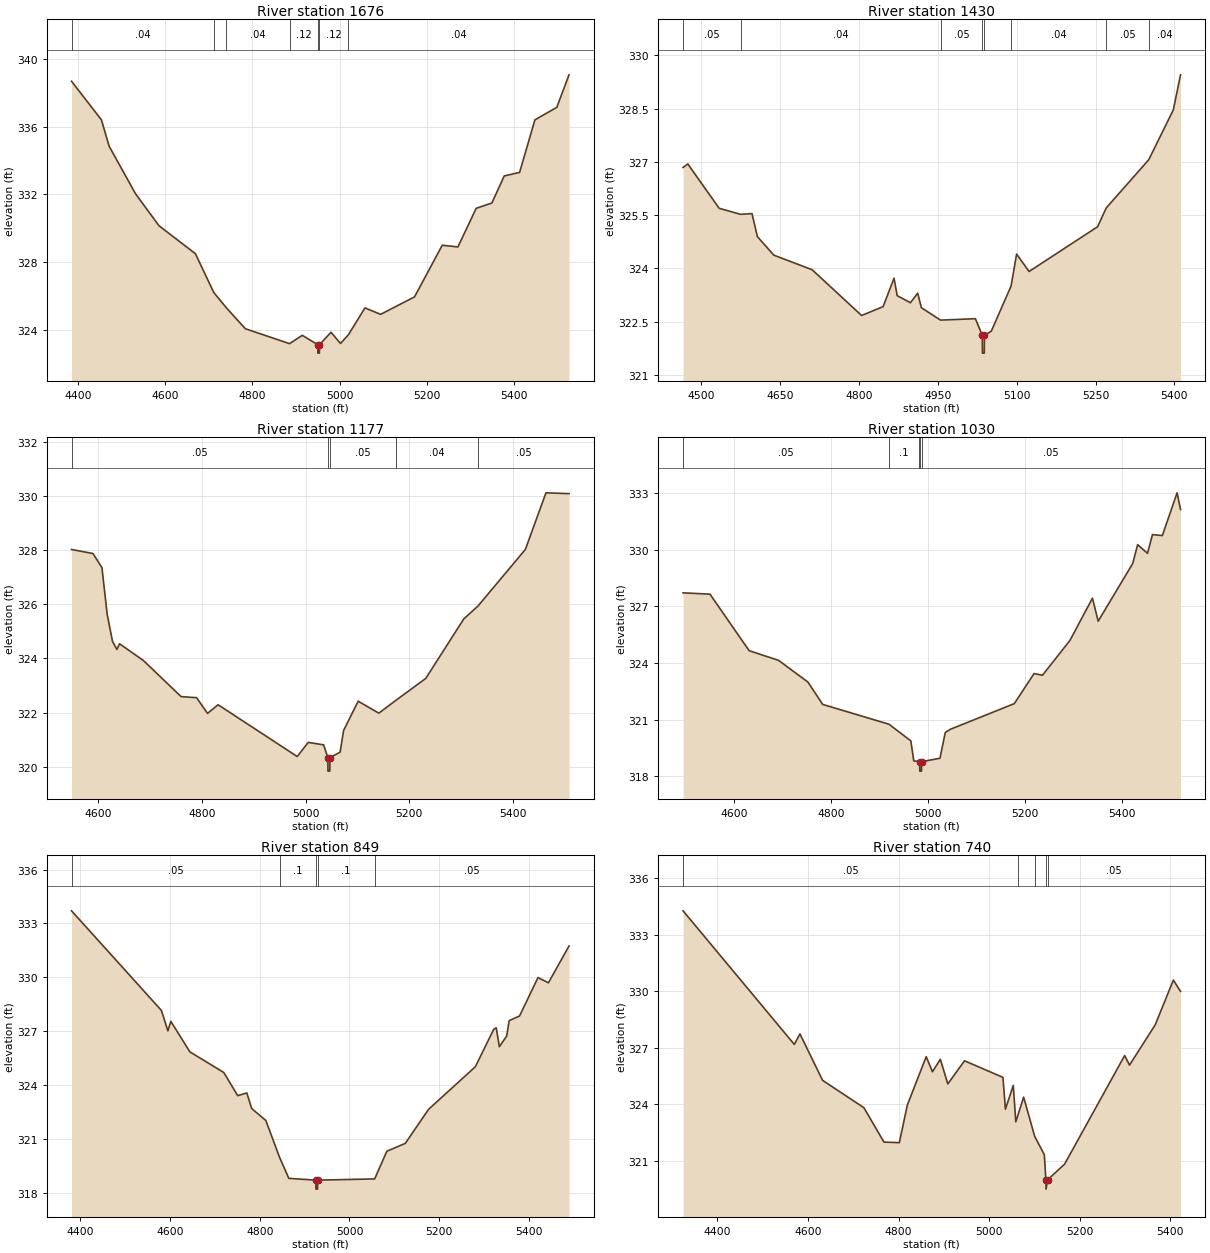
Type RM Length L Ch R = 1,1676,246,246,246
BEGIN DESCRIPTION:
TRIB 1 TO COTTONWOOD CREEK 3.0
END DESCRIPTION:
XS GIS Cut Line= 3
      2462774.98     13567124.99      2462275.00     13566925.00
      2461874.98     13567375.02
#Sta/Elev= 30
  4385.5  338.68  4454.1  336.40  4471.6  334.85  4532.2  332.04  4586.1  330.15
  4669.5  328.50  4711.6  326.21  4740.7  325.30  4784.0  324.07  4885.3  323.19
  4914.6  323.68  4950.0  323.13  4950.3  322.63  4953.8  322.63  4954.0  323.13
  4980.4  323.86  5002.2  323.20  5020.5  323.72  5058.2  325.30  5094.2  324.92
  5171.9  325.95  5235.5  329.00  5271.4  328.90  5313.3  331.18  5349.2  331.49
  5377.6  333.09  5412.8  333.30  5447.9  336.40  5498.1  337.14  5526.1  339.06
#Mann=7,-1,0
  4385.5    0.04       0  4711.6    0.12       0  4740.7    0.04       0
  4885.3    0.12       0  4950.0    0.05       0  4954.0    0.12       0
  5020.5    0.04       0
Bank Sta=4950,4954
Exp/Cntr=0.3,0.1

Type RM Length L Ch R = 1,1430,253,253,253
BEGIN DESCRIPTION:
Mapping XS f5614ceb
END DESCRIPTION:
XS GIS Cut Line= 3
      2462731.08     13566618.23      2462231.07     13566760.59
      2461873.45     13566993.22
#Sta/Elev= 30
  4465.3  326.84  4474.3  326.94  4534.0  325.69  4574.9  325.52  4596.4  325.54
  4606.8  324.89  4638.0  324.37  4710.8  323.96  4805.0  322.67  4845.9  322.92
  4866.7  323.72  4872.7  323.23  4897.9  323.03  4911.7  323.30  4918.7  322.89
  4955.2  322.54  5021.5  322.58  5034.6  322.11  5034.9  321.61  5038.4  321.61
  5038.6  322.11  5051.8  322.23  5089.4  323.50  5099.9  324.40  5123.6  323.91
  5254.0  325.17  5270.4  325.70  5351.4  327.06  5398.0  328.46  5411.8  329.45
#Mann=8,-1,0
  4465.3    0.05       0  4574.9    0.04       0  4955.2    0.05       0
  5034.6    0.05       0  5038.6    0.05       0  5089.4    0.04       0
  5270.4    0.05       0  5351.4    0.04       0
Bank Sta=5034.6,5038.6
Exp/Cntr=0.3,0.1

Type RM Length L Ch R = 1,1177,147,147,147
BEGIN DESCRIPTION:
Mapping XS a852f611
END DESCRIPTION:
XS GIS Cut Line= 3
      2462602.61     13566472.40      2462109.55     13566569.62
      2461696.36     13566767.53
#Sta/Elev= 30
  4548.1  328.02  4589.5  327.87  4606.8  327.35  4617.0  325.62  4627.2  324.63
  4635.7  324.33  4640.8  324.54  4687.0  323.92  4759.7  322.59  4789.7  322.55
  4810.7  321.97  4831.1  322.29  4983.9  320.38  5005.2  320.90  5034.9  320.81
  5043.1  320.34  5043.3  319.84  5046.8  319.84  5047.1  320.34  5066.8  320.54
  5073.5  321.34  5101.7  322.42  5141.5  321.98  5175.0  322.46  5232.1  323.26
  5305.7  325.46  5332.9  325.93  5424.5  328.02  5464.3  330.11  5508.8  330.08
#Mann=5,-1,0
  4548.1    0.05       0  5043.1    0.05       0  5047.1    0.05       0
  5175.0    0.04       0  5332.9    0.05       0
Bank Sta=5043.1,5047.1
Exp/Cntr=0.3,0.1

Type RM Length L Ch R = 1,1030,181,181,181
BEGIN DESCRIPTION:
Mapping XS 327f8ed1
END DESCRIPTION:
XS GIS Cut Line= 3
      2462619.94     13566347.40      2462123.44     13566423.79
      2461608.05     13566524.10
#Sta/Elev= 30
  4494.5  327.71  4550.1  327.64  4631.0  324.65  4691.7  324.14  4752.4  322.99
  4782.8  321.81  4919.8  320.76  4964.9  319.88  4971.0  318.82  4982.5  318.79
  4983.1  318.78  4983.4  318.28  4986.9  318.28  4987.1  318.78  5025.0  318.96
  5036.0  320.32  5046.2  320.49  5178.6  321.85  5219.4  323.44  5236.7  323.35
  5293.4  325.19  5340.0  327.43  5351.8  326.21  5423.1  329.26  5433.3  330.26
  5453.7  329.80  5463.9  330.79  5484.3  330.74  5514.8  333.00  5521.9  332.12
#Mann=5,-1,0
  4494.5    0.05       0  4919.8     0.1       0  4982.5    0.05       0
  4983.1    0.05       0  4987.1    0.05       0
Bank Sta=4983.1,4987.1
Exp/Cntr=0.3,0.1

Type RM Length L Ch R = 1,849,109,109,109
BEGIN DESCRIPTION:
Mapping XS c0d30977
END DESCRIPTION:
XS GIS Cut Line= 3
      2462644.30     13566080.03      2462123.44     13566260.59
      2461612.99     13566486.30
#Sta/Elev= 30
  4380.2  333.70  4580.6  328.15  4595.1  327.01  4601.7  327.54  4644.1  325.84
  4719.7  324.69  4750.8  323.40  4771.1  323.55  4782.0  322.68  4813.4  322.02
  4844.0  319.97  4864.8  318.79  4925.1  318.69  4925.3  318.19  4928.8  318.19
  4929.1  318.69  5056.2  318.76  5083.3  320.30  5124.5  320.74  5176.5  322.64
  5280.7  325.01  5321.8  327.10  5327.3  327.18  5334.3  326.13  5350.6  326.72
  5356.2  327.58  5379.3  327.84  5420.4  329.98  5443.7  329.69  5489.6  331.74
#Mann=5,-1,0
  4380.2    0.05       0  4844.0     0.1       0  4925.1    0.05       0
  4929.1     0.1       0  5056.2    0.05       0
Bank Sta=4925.1,4929.1
Exp/Cntr=0.3,0.1

Type RM Length L Ch R = 1,740,74,74,74
BEGIN DESCRIPTION:
Mapping XS 39148694
END DESCRIPTION:
XS GIS Cut Line= 3
      2462651.23     13566010.59      2462074.82     13566173.79
      2461623.41     13566385.61
#Sta/Elev= 30
  4324.6  334.27  4570.1  327.17  4582.5  327.73  4632.5  325.26  4723.5  323.81
  4767.9  321.98  4801.8  321.95  4819.5  323.95  4861.1  326.52  4874.9  325.72
  4892.3  326.38  4908.8  325.07  4945.6  326.30  5030.4  325.42  5035.9  323.73
  5053.2  324.99  5058.8  323.06  5063.5  323.41  5076.1  324.37  5100.4  322.29
  5121.7  321.31  5125.2  319.98  5125.5  319.48  5129.2  319.98  5166.5  320.81
  5299.0  326.58  5309.7  326.07  5366.4  328.21  5406.5  330.59  5422.3  329.99
#Mann=5,-1,0
  4324.6    0.05       0  5063.5     0.1       0  5100.4    0.05       0
  5125.2    0.05       0  5129.2    0.05       0
Bank Sta=5125.2,5129.2
Exp/Cntr=0.3,0.1

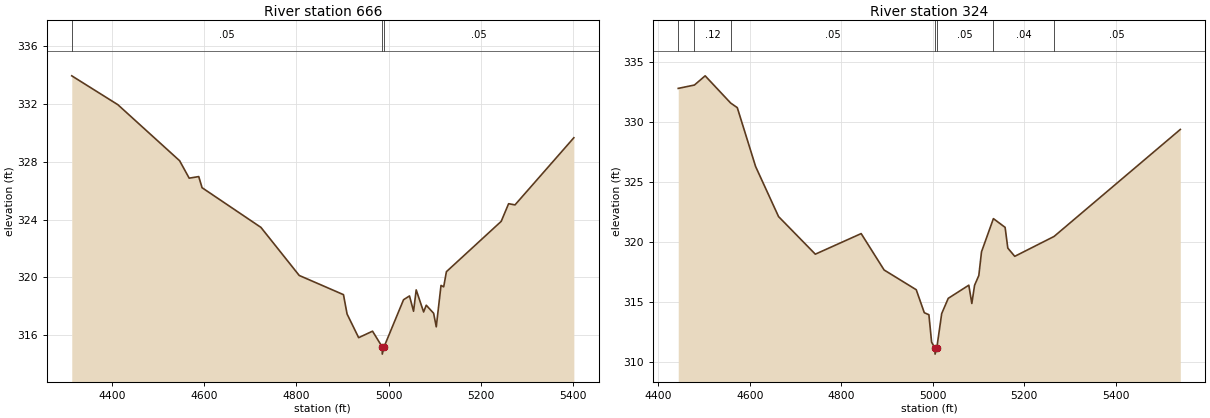
Type RM Length L Ch R = 1,666,342,342,342
BEGIN DESCRIPTION:
Mapping XS 821fb18c
END DESCRIPTION:
XS GIS Cut Line= 3
      2462630.37     13565944.62      2462036.63     13566107.81
      2461623.48     13566336.96
#Sta/Elev= 30
  4313.3  333.96  4413.2  331.96  4547.0  328.08  4567.8  326.87  4588.5  326.98
  4595.7  326.21  4723.3  323.46  4806.3  320.13  4902.2  318.80  4910.0  317.46
  4935.1  315.82  4965.2  316.27  4986.1  315.18  4986.3  314.68  4990.1  315.18
  5032.4  318.45  5045.3  318.71  5054.1  317.65  5059.8  319.13  5075.9  317.60
  5081.6  318.07  5097.6  317.51  5103.3  316.57  5113.6  319.44  5119.4  319.34
  5125.3  320.39  5244.1  323.88  5260.1  325.10  5274.0  325.02  5401.5  329.67
#Mann=3,-1,0
  4313.3    0.05       0  4986.1    0.05       0  4990.1    0.05       0
Bank Sta=4986.1,4990.1
Exp/Cntr=0.3,0.1

Type RM Length L Ch R = 1,324,0,0,0
BEGIN DESCRIPTION:
TRIB 1 TO COTTONWOOD CREEK 1.0
END DESCRIPTION:
XS GIS Cut Line= 3
      2462463.67     13565757.12      2461924.97     13565805.01
      2461624.99     13566275.01
#Sta/Elev= 30
  4443.3  332.82  4478.7  333.10  4502.2  333.87  4557.9  331.60  4572.5  331.21
  4612.6  326.29  4662.8  322.11  4743.2  318.97  4843.5  320.69  4893.7  317.65
  4964.0  316.00  4981.6  314.08  4991.7  313.91  4997.6  311.62  5004.9  311.12
  5005.2  310.62  5008.9  311.12  5019.7  314.01  5034.0  315.28  5079.0  316.38
  5085.6  314.85  5091.6  316.37  5100.9  317.19  5106.8  319.17  5132.8  321.94
  5158.4  321.21  5164.3  319.48  5179.5  318.79  5265.5  320.45  5541.7  329.39
#Mann=7,-1,0
  4443.3    0.05       0  4478.7    0.12       0  4557.9    0.05       0
  5004.9    0.05       0  5008.9    0.05       0  5132.8    0.04       0
  5265.5    0.05       0
Bank Sta=5004.9,5008.9
Exp/Cntr=0.3,0.1

Chan Stop Cuts=-1