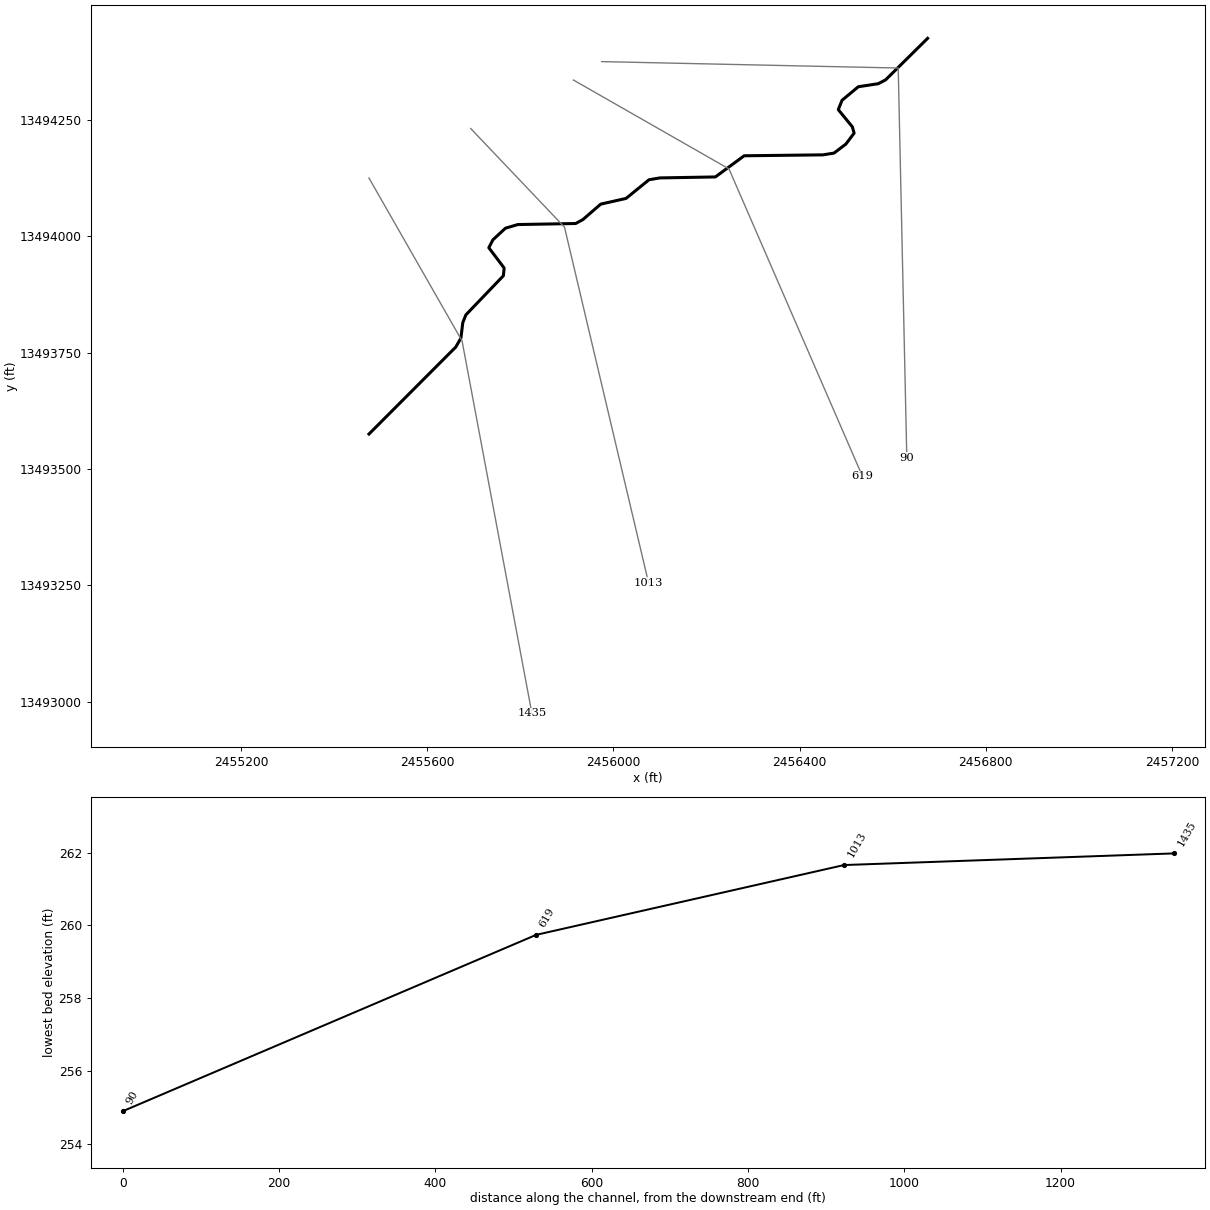
--- TRIB 1 TO COW CREEK.prj (project) ---

Proj Title=TRIB 1 TO COW CREEK Base Level Engineering
Current Plan=p01
Default Exp/Contr=0.3,0.1
English Units
Geom File=g01
Flow File=f01
Plan File=p01
Y Axis Title=Elevation
X Axis Title(PF)=Main Channel Distance
X Axis Title(XS)=Station
BEGIN DESCRIPTION:
TRIB 1 TO COW CREEK
END DESCRIPTION:
DSS Export Rating Curves= 0
DSS Export Rating Curve Sorted= 0
DSS Export Volume Flow Curves= 0
DXF OffsetX= 0
DXF OffsetY= 0
DXF ScaleX= 1
DXF ScaleY= 10

--- TRIB 1 TO COW CREEK.p01 (plan) ---

Plan Title=Multiple Run
Program Version=4.10
Short Identifier=Multiple
Geom File=g01
Flow File=f01
Subcritical Flow
K Sum by GR= 0
Std Step Tol= 0.01
Critical Tol= 0.01
Num of Std Step Trials= 20
Max Error Tol= 0.3
Flow Tol Ratio= 0.001
Split Flow NTrial= 30
Split Flow Tol= 0.02
Split Flow Ratio= 0.02
Log Output Level= 0
Friction Slope Method= 1
Unsteady Friction Slope Method= 2
Unsteady Bridges Friction Slope Method= 1
Parabolic Critical Depth
Global Vel Dist= 1 , 1 , 1
Global Log Level= 0
CheckData=True
Encroach Param=-1 ,0,0, 0
BEGIN DESCRIPTION:
Multiple Run
END DESCRIPTION:
Computation Interval=1HOUR
Output Interval=1HOUR
Run HTab= 0
Run UNet= 0
Run PostProcess= 0
Run WQNet= 0
UNET Theta= 1
UNET Theta Warmup= 1
UNET ZTol= 0.02
UNET ZSATol= 0.05
UNET MxIter= 20
UNET MaxInSteps= 0
UNET DtIC= 0
UNET DtMin= 0
UNET MaxCRTS= 20
UNET WFStab= 2
UNET SFStab= 1
UNET WFX= 1
UNET SFX= 1
UNET DSS MLevel= 4
UNET DZMax Abort= 100
UNET Convert EG Bridges= 0
UNET Use Existing IB Tables=-1
UNET Froude Reduction=False
UNET Froude Limit= 1
UNET Froude Power= 10
UNET Time Slicing=0,0, 5
UNET Junction Losses=0
Instantaneous Interval=1HOUR
Write IC File= 0
Write IC File at Sim End=0
Echo Input=False
Echo Parameters=False
Echo Output=False
Write Detailed= 0
WQ AD Non Conservative
WQ ULTIMATE=-1
WQ Max Comp Step=1HOUR
WQ Output Interval=15MIN
WQ Output Selected Increments= 0
WQ Output face flow=0
WQ Output face velocity=0
WQ Output face area=0
WQ Output face dispersion=0
WQ Output cell volume=0
WQ Output cell surface area=0
WQ Output cell continuity=0
WQ Output cumulative cell continuity=0
WQ Output face conc=0
WQ Output face dconc_dx=0
WQ Output face courant=0
WQ Output face peclet=0
WQ Output face adv mass=0
WQ Output face disp mass=0
WQ Output cell mass=0
WQ Output cell source sink temp=0
WQ Output cell source sink nsm=0
WQ Output MaxMinRange=-1
WQ Daily Max Min Mean=-1
WQ Daily Range=0
WQ Daily Time=0
WQ Create Restart=0
WQ Fixed Restart=0
WQ System Summary=0
WQ Use Fixed Temperature=0
Sorting and Armoring Iterations= 10
XS Update Threshold= 0.02
Hydraulics Update Threshold= 0.02
Energy Slope Method= 1
Volume Change Method= 0
XS Weighting Method= 0
Number of US Weighted Cross Sections= 1
Number of DS Weighted Cross Sections= 1
Upstream XS Weight=0.25
Main XS Weight=0.5
Downstream XS Weight=0.25
Number of DS XS's Weighted with US Boundary= 1
Upstream Boundary Weight= 1
Weight of XSs Associated with US Boundary= 0
Number of US XS's Weighted with DS Boundary= 1
Downstream Boundary Weight= 0.5
Weight of XSs Associated with DS Boundary= 0.5
Sediment Output Level= 4
Mass or Volume Output= 0
Output Increment Type= 1
Profile and TS Output Increment= 10
XS Output Flag= 0
XS Output Increment= 10
Disregard all LS=0
Disregard all Conn=0
Disregard all Breaches=0
Disregard all Pumps=0

--- TRIB 1 TO COW CREEK.f01 (steady flow) ---

Flow Title=Multiple
Number of Profiles=7
Profile Names=10-year,25-year,50-year,1pct_min,100-year,1pct_plu,500-year
River Rch & RM= TRIB 1 TO COW CR,Reach-1,1435
     752    1228    1662    1089    2172    4335    3674
River Rch & RM= TRIB 1 TO COW CR,Reach-1,1013
     821    1347    1829    1201    2397    4783    4076
Boundary for River Rch & Prof#=TRIB 1 TO COW CR,Reach-1,1
Up Type=0
Dn Type=3
Dn Slope=0.005
Boundary for River Rch & Prof#=TRIB 1 TO COW CR,Reach-1,2
Up Type=0
Dn Type=3
Dn Slope=0.005
Boundary for River Rch & Prof#=TRIB 1 TO COW CR,Reach-1,3
Up Type=0
Dn Type=3
Dn Slope=0.005
Boundary for River Rch & Prof#=TRIB 1 TO COW CR,Reach-1,4
Up Type=0
Dn Type=3
Dn Slope=0.005
Boundary for River Rch & Prof#=TRIB 1 TO COW CR,Reach-1,5
Up Type=0
Dn Type=3
Dn Slope=0.005
Boundary for River Rch & Prof#=TRIB 1 TO COW CR,Reach-1,6
Up Type=0
Dn Type=3
Dn Slope=0.005
Boundary for River Rch & Prof#=TRIB 1 TO COW CR,Reach-1,7
Up Type=0
Dn Type=3
Dn Slope=0.005

--- TRIB 1 TO COW CREEK.g01 (geometry) ---

Geom Title=Existing Conditions
Program Version=4.10

River Reach=TRIB 1 TO COW CR,Reach-1
Reach XY= 30
        2455475.       13493575.      2455661.37     13493761.79
      2455672.47     13493781.05      2455676.56     13493814.36
       2455683.2     13493831.05      2455763.73     13493915.02
      2455765.37     13493931.69      2455732.46     13493975.25
       2455741.2     13493992.13      2455768.18     13494017.18
      2455794.77     13494025.02      2455919.07     13494027.25
      2455934.67      13494035.8      2455972.82     13494068.88
      2456027.18     13494081.12      2456076.56     13494121.24
      2456099.92     13494125.19      2456219.06     13494127.27
      2456280.94     13494172.74       2456450.3     13494174.71
        2456474.     13494178.54      2456499.42     13494197.86
      2456517.11     13494221.39      2456513.34     13494234.88
      2456483.09     13494271.83      2456491.24     13494292.04
      2456526.17     13494321.04      2456568.88     13494327.52
      2456584.67     13494335.72        2456675.       13494425.

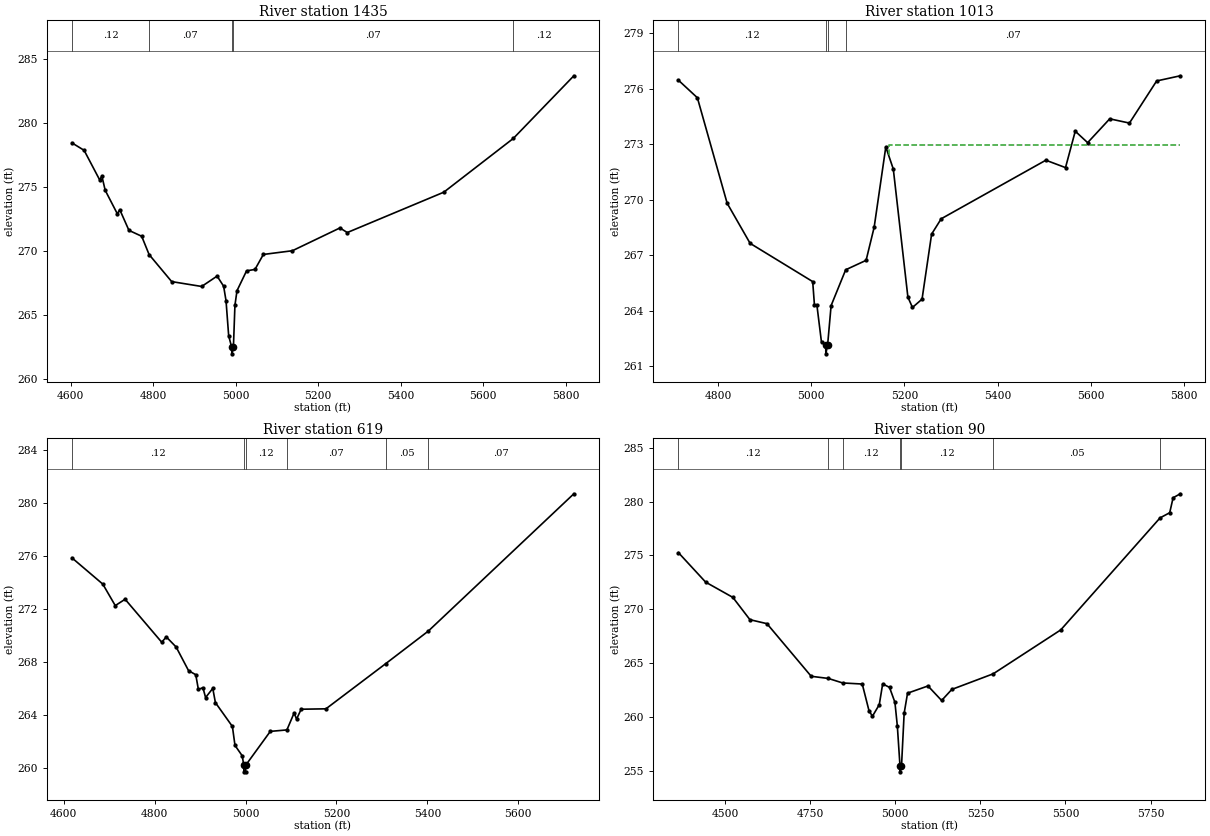
Type RM Length L Ch R = 1 ,1435    ,422,422,422
BEGIN DESCRIPTION:
TRIB 1 TO COW CREEK 3.0
END DESCRIPTION:
XS GIS Cut Line= 3
      2455475.01     13494124.97        2455675.       13493775.
        2455825.     13492975.02
#Sta/Elev= 30
  4602.7  278.45  4632.2  277.87  4669.6  275.58  4675.4  275.84  4683.3  274.75
  4712.8  272.91  4718.6  273.24  4740.9  271.62  4771.8  271.16  4789.8  269.73
  4844.5  267.62  4917.2  267.24  4954.7  268.05  4970.5  267.26  4976.3  266.13
  4982.7   263.4  4990.1  262.48  4990.4  261.98  4994.2  262.48  4997.9  265.77
  5002.9  266.91  5026.1  268.46  5046.5  268.57  5066.8  269.74  5137.2  270.03
  5252.5  271.81  5270.3  271.45  5504.3   274.6    5673   278.8  5819.7  283.69
#Mann= 5 ,-1 , 0
  4602.7     .12       0  4789.8     .07       0  4990.1     .05       0
  4994.2     .07       0    5673     .12       0
Bank Sta=4990.1,4994.2
XS Rating Curve= 0 ,0
Exp/Cntr=0.3,0.1

Type RM Length L Ch R = 1 ,1013    ,394,394,394
BEGIN DESCRIPTION:
Mapping XS 3f49cd5a
END DESCRIPTION:
XS GIS Cut Line= 3
      2455693.61     13494231.24      2455895.01     13494019.43
      2456075.56     13493255.56
#Sta/Elev= 30
  4714.9  276.47  4755.6  275.52  4819.5  269.81  4868.8  267.64  5003.1  265.57
  5006.8  264.32    5012  264.32    5022  262.28  5031.1  262.16  5031.3  261.66
  5035.2  262.16  5042.6  264.27  5073.9  266.21  5117.7  266.72    5135  268.51
    5160  272.86  5176.1  271.66  5207.4  264.73  5217.2  264.17  5237.8  264.62
  5258.3  268.14  5278.9  268.97  5503.5  272.14  5545.7  271.74  5566.6  273.71
  5593.2  273.09  5640.6  274.38  5682.9  274.15  5741.3  276.43  5792.1  276.71
#Mann= 4 ,-1 , 0
  4714.9     .12       0  5031.1     .05       0  5035.2     .12       0
  5073.9     .07       0
#XS Ineff= 2 , 0
       0                  5165.9       0  272.94
Permanent Ineff=
       F       F
Bank Sta=5031.1,5035.2
XS Rating Curve= 0 ,0
Exp/Cntr=0.3,0.1

Type RM Length L Ch R = 1 ,619     ,529,529,529
BEGIN DESCRIPTION:
Mapping XS 696b93cf
END DESCRIPTION:
XS GIS Cut Line= 3
      2455914.12     13494335.47      2456248.34     13494144.49
      2456534.81     13493484.74
#Sta/Elev= 30
    4618  275.87  4685.9  273.89  4713.3  272.27  4734.9  272.75  4815.5  269.51
  4825.6  269.91  4847.2  269.15  4874.5  267.37  4890.4  267.06  4896.1  265.96
  4906.2  266.08    4912  265.34  4927.8  266.03  4933.6  264.96    4971  263.16
  4976.7  261.73  4992.6  260.95    4996  260.24  4996.3  259.74    5000  259.74
  5000.3  260.24  5054.4  262.79  5090.9   262.9  5106.7  264.17  5112.2  263.72
  5122.3  264.46  5176.8  264.49  5308.1  267.89    5402  270.35  5722.2   280.7
#Mann= 6 ,-1 , 0
    4618     .12       0    4996     .05       0  5000.3     .12       0
  5090.9     .07       0  5308.1     .05       0    5402     .07       0
Bank Sta=4996,5000.3
XS Rating Curve= 0 ,0
Exp/Cntr=0.3,0.1

Type RM Length L Ch R = 1 ,90      ,0,0,0
BEGIN DESCRIPTION:
TRIB 1 TO COW CREEK 1.0
END DESCRIPTION:
XS GIS Cut Line= 3
      2455974.99       13494375.      2456611.84     13494361.22
      2456630.29     13493523.83
#Sta/Elev= 30
    4363  275.26    4443  272.52    4523   271.1  4573.1  269.03  4623.1  268.66
  4753.1  263.77  4803.3  263.57  4845.6  263.15  4903.1  263.05  4923.1  260.55
  4933.1  260.06  4953.1  261.13  4963.1  263.06  4983.2  262.74  4999.1  261.35
  5006.2  259.15  5014.1  255.39  5014.3  254.89  5018.4  255.39  5026.2  260.33
  5036.2   262.2  5096.2  262.87  5136.3  261.52  5166.3  262.55  5287.9     264
  5486.3  268.08  5778.1  278.49  5806.4  278.97  5816.4  280.36  5837.6  280.73
#Mann= 7 ,-1 , 0
    4363     .12       0  4803.3     .07       0  4845.6     .12       0
  5014.1     .05       0  5018.4     .12       0  5287.9     .05       0
  5778.1     .07       0
Bank Sta=5014.1,5018.4
XS Rating Curve= 0 ,0
Exp/Cntr=0.3,0.1

Chan Stop Cuts=-1
Use User Specified Reach Order=0
Composite Channel Slope=5