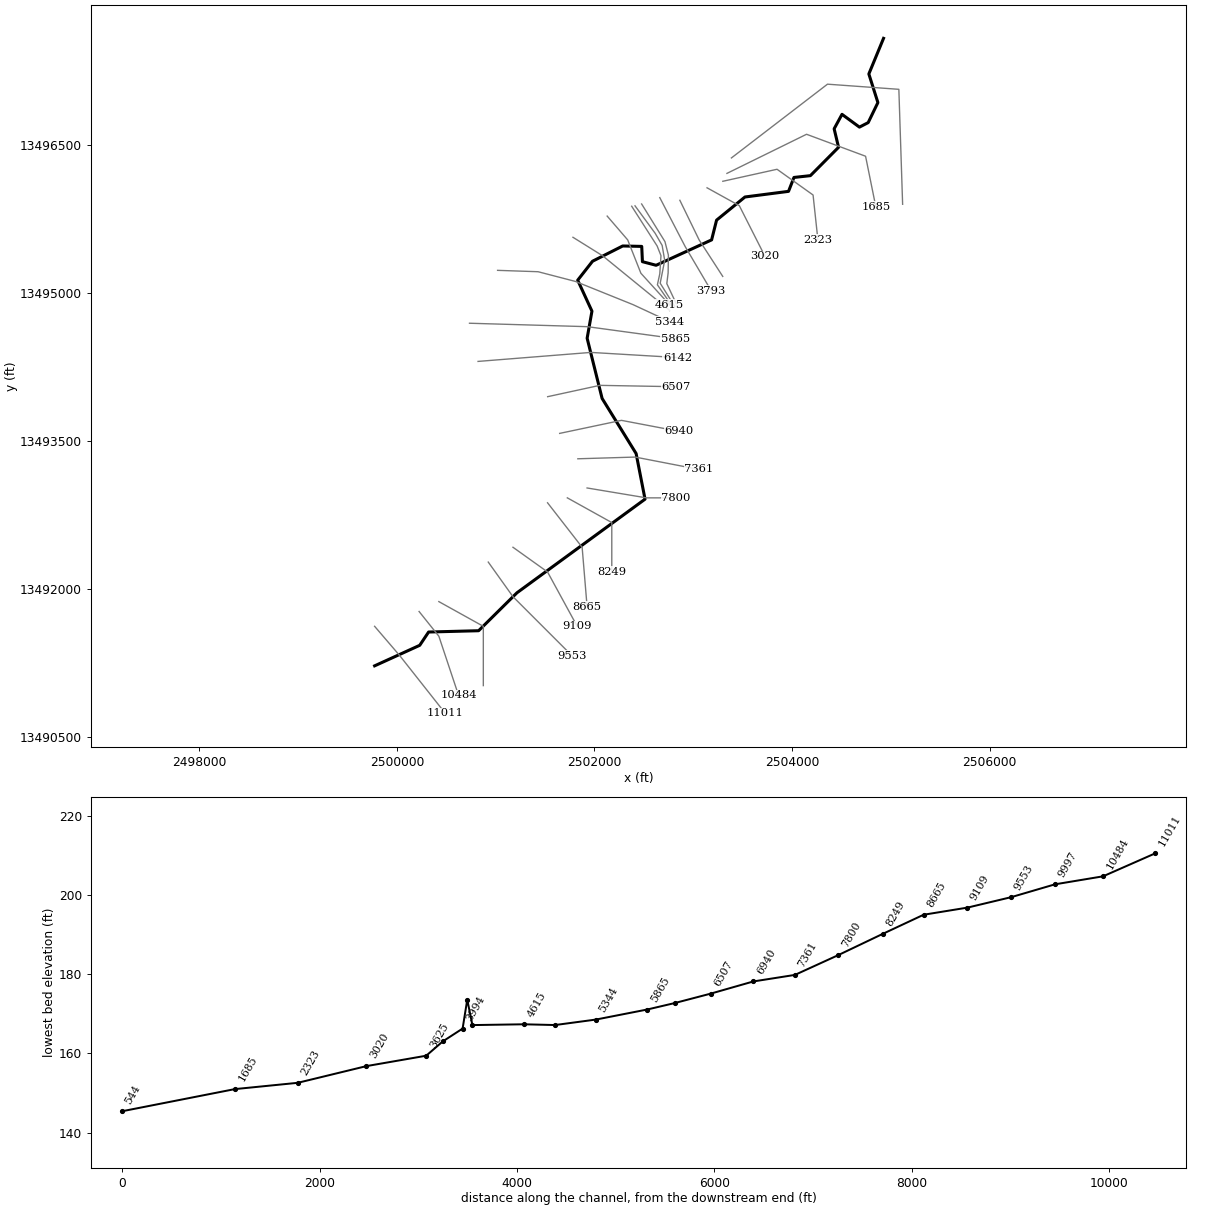
--- TRIB 1 TO EIGHTEENMILE CREEK.prj (project) ---

Proj Title=TRIB 1 TO EIGHTEENMILE CREEK Base Level Engineering
Current Plan=p01
Default Exp/Contr=0.3,0.1
English Units
Geom File=g01
Flow File=f01
Plan File=p01
Y Axis Title=Elevation
X Axis Title(PF)=Main Channel Distance
X Axis Title(XS)=Station
BEGIN DESCRIPTION:
TRIB 1 TO EIGHTEENMILE CREEK
END DESCRIPTION:
DSS Export Rating Curves= 0
DSS Export Rating Curve Sorted= 0
DSS Export Volume Flow Curves= 0
DXF OffsetX= 0
DXF OffsetY= 0
DXF ScaleX= 1
DXF ScaleY= 10

--- TRIB 1 TO EIGHTEENMILE CREEK.p01 (plan) ---

Plan Title=Multiple Run
Program Version=4.10
Short Identifier=Multiple
Geom File=g01
Flow File=f01
Subcritical Flow
K Sum by GR= 0
Std Step Tol= 0.01
Critical Tol= 0.01
Num of Std Step Trials= 20
Max Error Tol= 0.3
Flow Tol Ratio= 0.001
Split Flow NTrial= 30
Split Flow Tol= 0.02
Split Flow Ratio= 0.02
Log Output Level= 0
Friction Slope Method= 1
Unsteady Friction Slope Method= 2
Unsteady Bridges Friction Slope Method= 1
Parabolic Critical Depth
Global Vel Dist= 1 , 1 , 1
Global Log Level= 0
CheckData=True
Encroach Param=-1 ,0,0, 0
BEGIN DESCRIPTION:
Multiple Run
END DESCRIPTION:
Computation Interval=1HOUR
Output Interval=1HOUR
Run HTab= 0
Run UNet= 0
Run PostProcess= 0
Run WQNet= 0
UNET Theta= 1
UNET Theta Warmup= 1
UNET ZTol= 0.02
UNET ZSATol= 0.05
UNET MxIter= 20
UNET MaxInSteps= 0
UNET DtIC= 0
UNET DtMin= 0
UNET MaxCRTS= 20
UNET WFStab= 2
UNET SFStab= 1
UNET WFX= 1
UNET SFX= 1
UNET DSS MLevel= 4
UNET DZMax Abort= 100
UNET Convert EG Bridges= 0
UNET Use Existing IB Tables=-1
UNET Froude Reduction=False
UNET Froude Limit= 1
UNET Froude Power= 10
UNET Time Slicing=0,0, 5
UNET Junction Losses=0
Instantaneous Interval=1HOUR
Write IC File= 0
Write IC File at Sim End=0
Echo Input=False
Echo Parameters=False
Echo Output=False
Write Detailed= 0
WQ AD Non Conservative
WQ ULTIMATE=-1
WQ Max Comp Step=1HOUR
WQ Output Interval=15MIN
WQ Output Selected Increments= 0
WQ Output face flow=0
WQ Output face velocity=0
WQ Output face area=0
WQ Output face dispersion=0
WQ Output cell volume=0
WQ Output cell surface area=0
WQ Output cell continuity=0
WQ Output cumulative cell continuity=0
WQ Output face conc=0
WQ Output face dconc_dx=0
WQ Output face courant=0
WQ Output face peclet=0
WQ Output face adv mass=0
WQ Output face disp mass=0
WQ Output cell mass=0
WQ Output cell source sink temp=0
WQ Output cell source sink nsm=0
WQ Output MaxMinRange=-1
WQ Daily Max Min Mean=-1
WQ Daily Range=0
WQ Daily Time=0
WQ Create Restart=0
WQ Fixed Restart=0
WQ System Summary=0
WQ Use Fixed Temperature=0
Sorting and Armoring Iterations= 10
XS Update Threshold= 0.02
Hydraulics Update Threshold= 0.02
Energy Slope Method= 1
Volume Change Method= 0
XS Weighting Method= 0
Number of US Weighted Cross Sections= 1
Number of DS Weighted Cross Sections= 1
Upstream XS Weight=0.25
Main XS Weight=0.5
Downstream XS Weight=0.25
Number of DS XS's Weighted with US Boundary= 1
Upstream Boundary Weight= 1
Weight of XSs Associated with US Boundary= 0
Number of US XS's Weighted with DS Boundary= 1
Downstream Boundary Weight= 0.5
Weight of XSs Associated with DS Boundary= 0.5
Sediment Output Level= 4
Mass or Volume Output= 0
Output Increment Type= 1
Profile and TS Output Increment= 10
XS Output Flag= 0
XS Output Increment= 10
Disregard all LS=0
Disregard all Conn=0
Disregard all Breaches=0
Disregard all Pumps=0

--- TRIB 1 TO EIGHTEENMILE CREEK.f01 (steady flow) ---

Flow Title=Multiple
Number of Profiles=7
Profile Names=10-year,25-year,50-year,1pct_min,100-year,1pct_plu,500-year
River Rch & RM= TRIB 1 TO EIGHTE,Reach-1,11011
     464     733     973     626    1249    2492    2035
River Rch & RM= TRIB 1 TO EIGHTE,Reach-1,7361
     771    1253    1692    1106    2206    4402    3709
Boundary for River Rch & Prof#=TRIB 1 TO EIGHTE,Reach-1,1
Up Type=0
Dn Type=3
Dn Slope=0.005
Boundary for River Rch & Prof#=TRIB 1 TO EIGHTE,Reach-1,2
Up Type=0
Dn Type=3
Dn Slope=0.005
Boundary for River Rch & Prof#=TRIB 1 TO EIGHTE,Reach-1,3
Up Type=0
Dn Type=3
Dn Slope=0.005
Boundary for River Rch & Prof#=TRIB 1 TO EIGHTE,Reach-1,4
Up Type=0
Dn Type=3
Dn Slope=0.005
Boundary for River Rch & Prof#=TRIB 1 TO EIGHTE,Reach-1,5
Up Type=0
Dn Type=3
Dn Slope=0.005
Boundary for River Rch & Prof#=TRIB 1 TO EIGHTE,Reach-1,6
Up Type=0
Dn Type=3
Dn Slope=0.005
Boundary for River Rch & Prof#=TRIB 1 TO EIGHTE,Reach-1,7
Up Type=0
Dn Type=3
Dn Slope=0.005

--- TRIB 1 TO EIGHTEENMILE CREEK.g01 (geometry) ---

Geom Title=Existing Conditions
Program Version=4.10

River Reach=TRIB 1 TO EIGHTE,Reach-1
Reach XY= 30
        2499775.       13491225.      2500231.45     13491432.75
      2500321.34     13491567.28      2500827.45     13491580.47
       2501215.3     13491964.23      2502511.47     13492911.62
      2502421.17     13493373.42      2502077.06     13493930.85
      2501925.52     13494540.22      2501974.23     13494814.31
      2501829.96     13495127.54      2501980.26     13495319.53
       2502285.5     13495473.78      2502478.01     13495469.55
      2502485.05     13495314.94       2502623.5     13495278.47
      2503185.16     13495535.36      2503235.35     13495735.12
      2503522.55     13495969.53      2503963.47      13496026.5
      2504018.48     13496167.32      2504184.82     13496185.47
       2504469.7     13496472.33      2504425.08     13496659.61
      2504504.61     13496805.95      2504681.09     13496676.56
      2504769.58     13496722.25       2504867.9       13496925.
      2504776.22     13497214.49        2504925.       13497575.

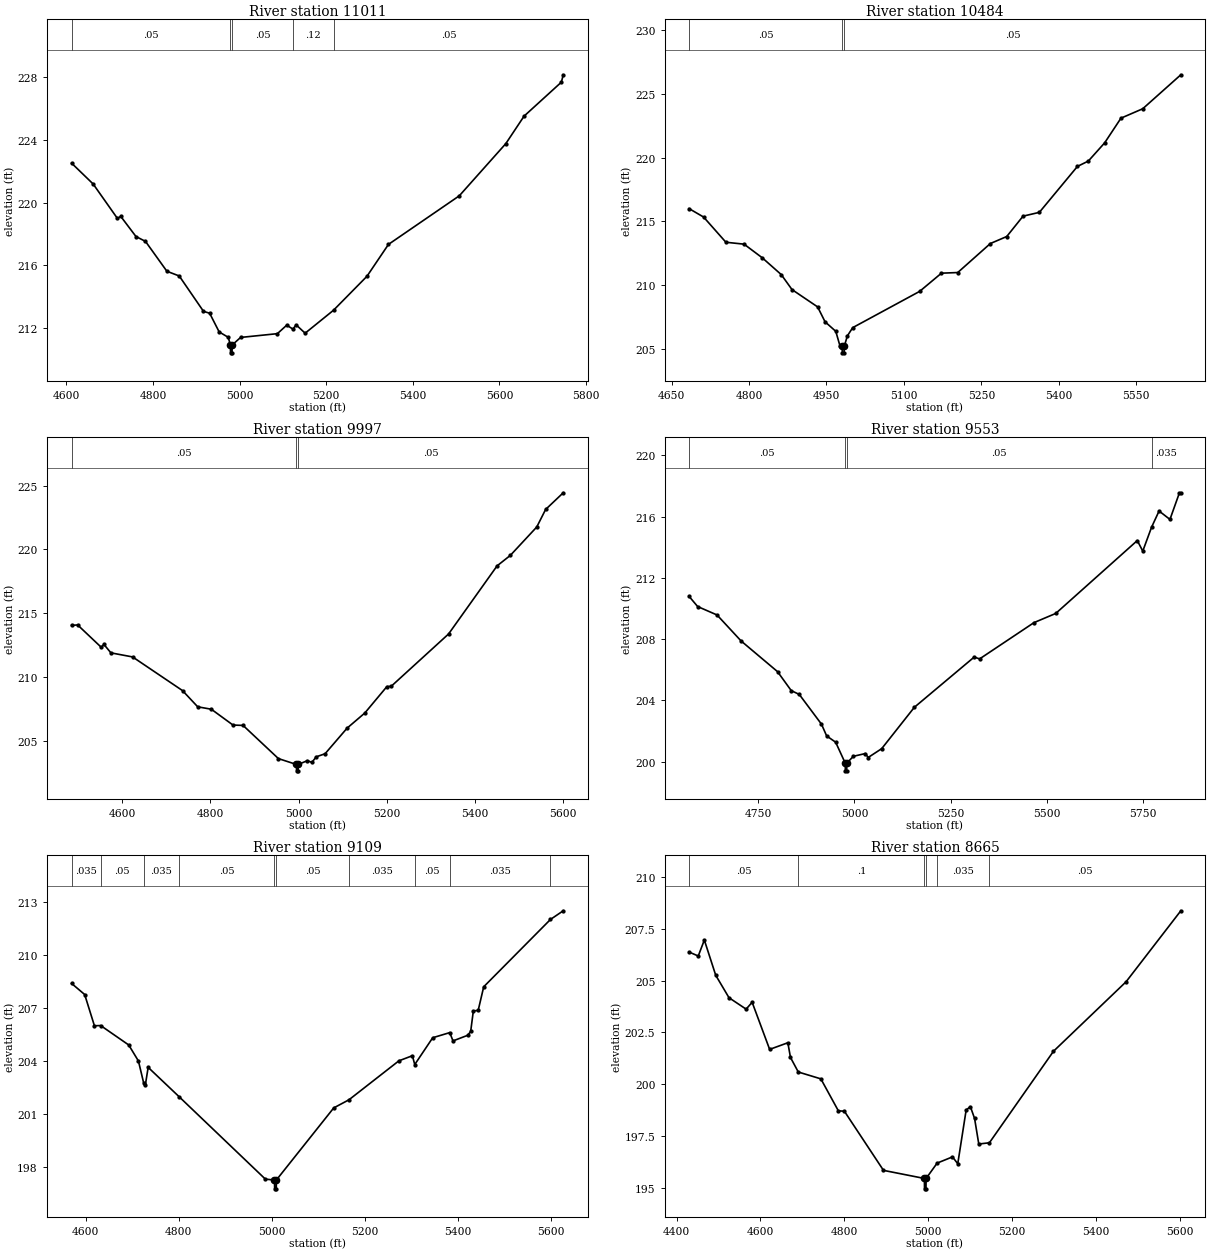
Type RM Length L Ch R = 1 ,11011   ,527,527,527
BEGIN DESCRIPTION:
TRIB 1 TO EIGHTEENMILE CREEK 21.0
END DESCRIPTION:
XS GIS Cut Line= 3
        2499775.       13491625.      2500027.44     13491330.48
      2500490.62     13490744.03
#Sta/Elev= 30
  4612.1  222.51    4662  221.18    4718  218.99  4725.7  219.12  4760.8  217.84
  4782.8  217.53  4832.2  215.63  4860.7  215.33  4916.7  213.08  4930.9  212.96
  4952.9  211.77  4973.7  211.43  4978.9  210.94  4979.1  210.44  4982.6  210.44
  4982.9  210.94  5002.4  211.42  5087.3  211.66  5108.9   212.2  5123.2  211.95
  5130.6  212.22  5151.4  211.69  5216.9  213.15  5294.1  215.31  5343.8  217.34
  5507.3  220.43  5614.7  223.75  5656.9   225.5    5743  227.66  5747.3  228.13
#Mann= 5 ,-1 , 0
  4612.1     .05       0  4978.9     .05       0  4982.9     .05       0
  5123.2     .12       0  5216.9     .05       0
Bank Sta=4978.9,4982.9
XS Rating Curve= 0 ,0
Exp/Cntr=0.3,0.1

Type RM Length L Ch R = 1 ,10484   ,487,487,487
BEGIN DESCRIPTION:
TRIB 1 TO EIGHTEENMILE CREEK 20.0
END DESCRIPTION:
XS GIS Cut Line= 3
      2500225.02     13491774.97        2500425.       13491525.
      2500625.01     13490924.97
#Sta/Elev= 30
  4683.9  215.99  4711.9  215.33  4755.1  213.35  4790.3   213.2  4825.5  212.13
  4862.3  210.81  4883.2  209.63  4932.8  208.27  4947.2   207.1    4968  206.35
    4976  205.22  4980.4  205.16  4980.7  204.66  4984.2  204.66  4984.4  205.16
  4990.4  205.99  5000.8  206.64  5130.5  209.49  5172.7  210.92  5204.3  210.97
  5267.5  213.25  5299.2   213.8  5330.8   215.4  5362.4   215.7  5436.2  219.31
  5457.3  219.73  5488.9  221.16  5520.5   223.1  5562.7  223.84  5636.5  226.51
#Mann= 3 ,-1 , 0
  4683.9     .05       0  4980.4     .05       0  4984.4     .05       0
Bank Sta=4980.4,4984.4
XS Rating Curve= 0 ,0
Exp/Cntr=0.3,0.1

Type RM Length L Ch R = 1 ,9997    ,444,444,444
BEGIN DESCRIPTION:
TRIB 1 TO EIGHTEENMILE CREEK 19.0
END DESCRIPTION:
XS GIS Cut Line= 3
      2500425.02     13491874.99        2500875.       13491625.
        2500875.     13491024.96
#Sta/Elev= 30
  4485.2  214.04  4498.9  214.08  4552.7  212.32  4558.4  212.56  4574.4  211.89
  4623.6  211.57  4736.8  208.93  4771.2  207.66  4802.1  207.47  4851.2  206.23
  4874.1   206.2  4954.2   203.6  4995.1  203.14  4995.3  202.64  4998.8  202.64
  4999.1  203.14    5020  203.44    5030   203.3    5040  203.74    5060  203.98
    5110  205.99    5150  207.17    5200  209.24    5210  209.27    5340  213.37
    5450  218.71    5480  219.53    5540  221.76    5560  223.13    5600  224.44
#Mann= 3 ,-1 , 0
  4485.2     .05       0  4995.1     .05       0  4999.1     .05       0
Bank Sta=4995.1,4999.1
XS Rating Curve= 0 ,0
Exp/Cntr=0.3,0.1

Type RM Length L Ch R = 1 ,9553    ,444,444,444
BEGIN DESCRIPTION:
TRIB 1 TO EIGHTEENMILE CREEK 18.0
END DESCRIPTION:
XS GIS Cut Line= 3
      2500924.99     13492275.02        2501175.       13491925.
      2501775.02     13491324.98
#Sta/Elev= 30
  4570.3  210.79  4592.4  210.13  4642.8  209.58  4705.5  207.88  4800.1  205.88
  4835.8  204.64  4856.7  204.39  4914.4  202.45  4927.9  201.68  4951.3  201.27
  4976.3   199.9  4976.6   199.4  4980.1   199.4  4980.3   199.9  4997.4  200.35
  5028.7  200.53  5035.8  200.27  5071.1  200.85    5156  203.55  5311.6  206.83
  5325.7  206.71  5467.1  209.08  5523.7  209.68  5735.8  214.44    5750  213.75
  5772.9  215.31  5792.4  216.37  5820.7  215.82  5845.4  217.56    5849  217.56
#Mann= 4 ,-1 , 0
  4570.3     .05       0  4976.3     .05       0  4980.3     .05       0
  5772.9    .035       0
Bank Sta=4976.3,4980.3
XS Rating Curve= 0 ,0
Exp/Cntr=0.3,0.1

Type RM Length L Ch R = 1 ,9109    ,444,444,444
BEGIN DESCRIPTION:
TRIB 1 TO EIGHTEENMILE CREEK 17.0
END DESCRIPTION:
XS GIS Cut Line= 3
      2501175.04     13492424.97        2501525.       13492175.
      2501825.02     13491624.97
#Sta/Elev= 30
  4569.9  208.41  4598.1  207.78    4619  206.01  4632.5  206.02  4692.7  204.92
  4713.6  204.01  4724.7  202.78  4728.4  202.64  4734.5  203.65  4800.8  201.99
  4986.4  197.31    5006  197.26  5006.3  196.76  5009.8  196.76    5010  197.26
  5133.3  201.35    5166  201.81  5273.3  204.02  5302.3  204.31  5307.4  203.81
    5346  205.33  5382.6  205.62  5389.6  205.15  5421.4  205.47  5427.6  205.69
  5433.3  206.85  5443.7  206.88  5455.6  208.22  5599.1  212.04  5626.5  212.53
#Mann= 10 ,-1 , 0
  4569.9    .035       0  4632.5     .05       0  4724.7    .035       0
  4800.8     .05       0    5006     .05       0    5010     .05       0
    5166    .035       0  5307.4     .05       0  5382.6    .035       0
  5599.1     .05       0
Bank Sta=5006,5010
XS Rating Curve= 0 ,0
Exp/Cntr=0.3,0.1

Type RM Length L Ch R = 1 ,8665    ,416,416,416
BEGIN DESCRIPTION:
TRIB 1 TO EIGHTEENMILE CREEK 16.0
END DESCRIPTION:
XS GIS Cut Line= 3
      2501524.98     13492875.02        2501875.       13492425.
        2501925.     13491824.99
#Sta/Elev= 30
  4429.9  206.37  4451.6  206.18  4466.1  206.95  4493.3  205.25  4524.9  204.17
  4565.7  203.62  4580.1  203.95  4621.8  201.68  4665.2     202  4671.5  201.29
  4690.1  200.59  4743.9  200.26  4785.6  198.72    4800   198.7  4893.2  195.85
  4990.8  195.46    4991  194.96  4994.5  194.96  4994.8  195.46  5021.1   196.2
  5057.7   196.5  5070.3  196.17  5090.3  198.76  5100.4  198.92  5110.4  198.35
  5120.4  197.12  5145.7  197.18  5298.5  201.59  5471.6  204.94  5602.1  208.36
#Mann= 6 ,-1 , 0
  4429.9     .05       0  4690.1      .1       0  4990.8     .05       0
  4994.8      .1       0  5021.1    .035       0  5145.7     .05       0
Bank Sta=4990.8,4994.8
XS Rating Curve= 0 ,0
Exp/Cntr=0.3,0.1

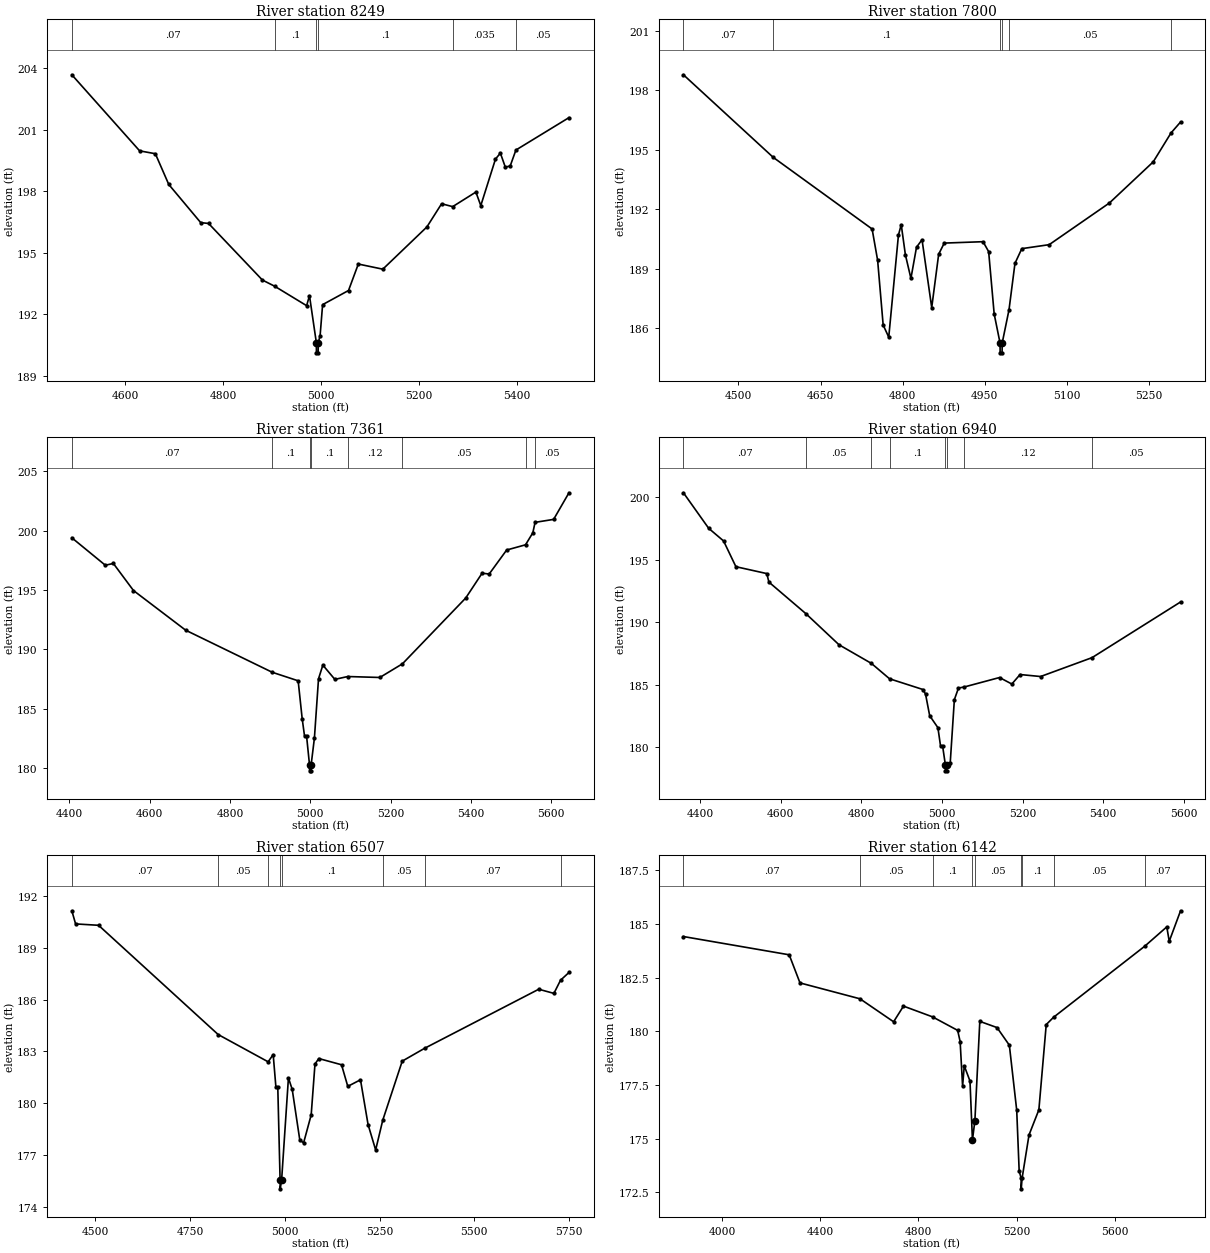
Type RM Length L Ch R = 1 ,8249    ,449,449,449
BEGIN DESCRIPTION:
TRIB 1 TO EIGHTEENMILE CREEK 15.0
END DESCRIPTION:
XS GIS Cut Line= 3
      2501724.99     13492925.01        2502175.       13492675.
        2502175.       13492175.
#Sta/Elev= 30
  4491.1  203.67  4629.5  199.96  4661.6  199.82    4689  198.32  4754.2  196.46
  4770.2  196.42  4880.1  193.66    4905  193.36  4970.4  192.41  4976.2   192.9
  4990.2  190.61  4990.4  190.11  4993.9  190.11  4994.2  190.61  4997.9  190.95
    5003  192.46  5055.9  193.15  5075.9  194.44  5125.9  194.19  5215.9  196.25
  5245.9  197.38  5268.5  197.24  5315.9  197.95  5325.9  197.29  5355.9  199.56
  5365.9  199.85  5375.9  199.17  5385.9  199.22  5397.6     200  5505.9  201.58
#Mann= 6 ,-1 , 0
  4491.1     .07       0    4905      .1       0  4990.2     .05       0
  4994.2      .1       0  5268.5    .035       0  5397.6     .05       0
Bank Sta=4990.2,4994.2
XS Rating Curve= 0 ,0
Exp/Cntr=0.3,0.1

Type RM Length L Ch R = 1 ,7800    ,439,439,439
BEGIN DESCRIPTION:
TRIB 1 TO EIGHTEENMILE CREEK 14.0
END DESCRIPTION:
XS GIS Cut Line= 3
      2501925.03       13493025.        2502525.       13492925.
      2502824.95       13492925.
#Sta/Elev= 30
  4399.4  198.78  4563.4  194.62  4744.1  191.01  4754.2  189.43  4764.3  186.17
  4774.5  185.56  4792.2   190.7  4797.3  191.23  4804.9  189.71    4815  188.52
  4825.2  190.09  4835.3  190.47    4853  187.05  4865.7  189.74  4875.9   190.3
  4946.8  190.37    4957  189.87  4967.1  186.73  4977.8  185.27    4978  184.77
  4981.5  184.77  4981.8  185.27  4994.2  186.94  5005.1  189.28  5017.6  190.02
  5067.6  190.22  5177.6  192.32  5257.6  194.39  5290.2  195.85  5307.6   196.4
#Mann= 6 ,-1 , 0
  4399.4     .07       0  4563.4      .1       0  4977.8     .05       0
  4981.8      .1       0  4994.2     .05       0  5290.2     .07       0
Bank Sta=4977.8,4981.8
XS Rating Curve= 0 ,0
Exp/Cntr=0.3,0.1

Type RM Length L Ch R = 1 ,7361    ,421,421,421
BEGIN DESCRIPTION:
Mapping XS 4333fa45
END DESCRIPTION:
XS GIS Cut Line= 3
      2501831.62     13493320.35      2502411.51     13493337.71
      2503057.37      13493212.7
#Sta/Elev= 30
    4406   199.4  4489.4  197.09  4509.4  197.24  4559.5  194.96  4689.5  191.62
  4904.9  188.08  4969.6  187.36  4979.6  184.18  4985.4  182.73  4990.5  182.73
  4997.9  180.28  4998.1  179.78  5001.6  179.78  5001.9  180.28  5010.1  182.54
  5020.3  187.53  5031.1  188.68    5061  187.48  5093.1  187.72    5173  187.64
  5229.3  188.79  5386.9  194.33  5427.7  196.42  5445.3  196.35  5488.8  198.37
  5535.8  198.81    5554  199.82  5559.6   200.7  5605.8  200.95    5644  203.19
#Mann= 8 ,-1 , 0
    4406     .07       0  4904.9      .1       0  4997.9     .05       0
  5001.9      .1       0  5093.1     .12       0  5229.3     .05       0
  5535.8     .07       0  5559.6     .05       0
Bank Sta=4997.9,5001.9
XS Rating Curve= 0 ,0
Exp/Cntr=0.3,0.1

Type RM Length L Ch R = 1 ,6940    ,433,433,433
BEGIN DESCRIPTION:
Mapping XS 708d7ad3
END DESCRIPTION:
XS GIS Cut Line= 3
      2501647.66      13493577.3      2502272.62     13493709.24
       2502855.9     13493598.14
#Sta/Elev= 30
  4359.3  200.36  4421.9  197.52  4458.8  196.51  4489.4  194.45    4566   193.9
  4571.2  193.22  4663.1  190.69    4745  188.21  4825.3  186.72  4870.3  185.49
  4953.3  184.63  4959.6  184.26  4969.8  182.54  4990.2  181.58  4996.7  180.13
  5001.8  180.13  5008.6  178.63  5008.9  178.13  5012.4  178.13  5012.6  178.63
  5020.8  178.79    5031  183.82  5041.2  184.75    5055  184.83    5143  185.59
  5173.5  185.07  5193.9  185.83  5244.8  185.67  5372.4  187.18  5591.8  191.63
#Mann= 8 ,-1 , 0
  4359.3     .07       0  4663.1     .05       0  4825.3     .07       0
  4870.3      .1       0  5008.6     .05       0  5012.6      .1       0
    5055     .12       0  5372.4     .05       0
Bank Sta=5008.6,5012.6
XS Rating Curve= 0 ,0
Exp/Cntr=0.3,0.1

Type RM Length L Ch R = 1 ,6507    ,365,365,365
BEGIN DESCRIPTION:
Mapping XS 874a6f44
END DESCRIPTION:
XS GIS Cut Line= 3
      2501526.09     13493948.82      2502053.87      13494063.4
      2502824.67     13494049.52
#Sta/Elev= 30
  4438.5  191.14  4448.4  190.38    4509   190.3  4824.3  183.98  4956.2   182.4
  4969.5  182.82  4976.6  180.95  4981.6  180.95  4987.7  175.55    4988  175.05
  4991.7  175.55  5009.7  181.47  5019.7   180.8  5039.7  177.87  5049.7  177.71
  5069.7  179.33  5079.7  182.27  5089.7  182.59  5149.7  182.23  5166.2  180.98
  5199.7  181.36  5219.7  178.77  5239.7   177.3  5258.4  179.02  5309.8  182.44
  5368.6  183.18  5669.8   186.6  5709.8  186.36  5727.2  187.12  5749.5  187.57
#Mann= 8 ,-1 , 0
  4438.5     .07       0  4824.3     .05       0  4956.2      .1       0
  4987.7     .05       0  4991.7      .1       0  5258.4     .05       0
  5368.6     .07       0  5727.2     .05       0
Bank Sta=4987.7,4991.7
XS Rating Curve= 0 ,0
Exp/Cntr=0.3,0.1

Type RM Length L Ch R = 1 ,6142    ,277,277,277
BEGIN DESCRIPTION:
Mapping XS 2148db55
END DESCRIPTION:
XS GIS Cut Line= 3
      2500821.79     13494305.66      2501963.59     13494396.74
      2502841.02     13494344.72
#Sta/Elev= 30
  3843.2  184.42  4273.9  183.57  4317.9  182.26  4562.3  181.52  4699.1  180.45
  4739.3  181.18  4857.5  180.68  4959.9  180.05    4970  179.53    4980  177.45
  4986.8   178.4  5010.1  177.69  5020.1  174.94  5030.1  175.85  5050.1  180.47
  5120.3  180.18  5170.4  179.36  5200.4  176.33  5210.4   173.5  5218.4  173.17
  5218.7  172.67  5222.4  173.17  5250.5  175.18  5290.6  176.35  5320.6  180.32
  5350.4  180.66  5721.8  183.97  5811.5  184.87  5821.5   184.2  5867.6  185.62
#Mann= 9 ,-1 , 0
  3843.2     .07       0  4562.3     .05       0  4857.5      .1       0
  5020.1     .05       0  5030.1     .05       0  5218.4     .07       0
  5222.4      .1       0  5350.4     .05       0  5721.8     .07       0
Bank Sta=5020.1,5030.1
XS Rating Curve= 0 ,0
Exp/Cntr=0.3,0.1

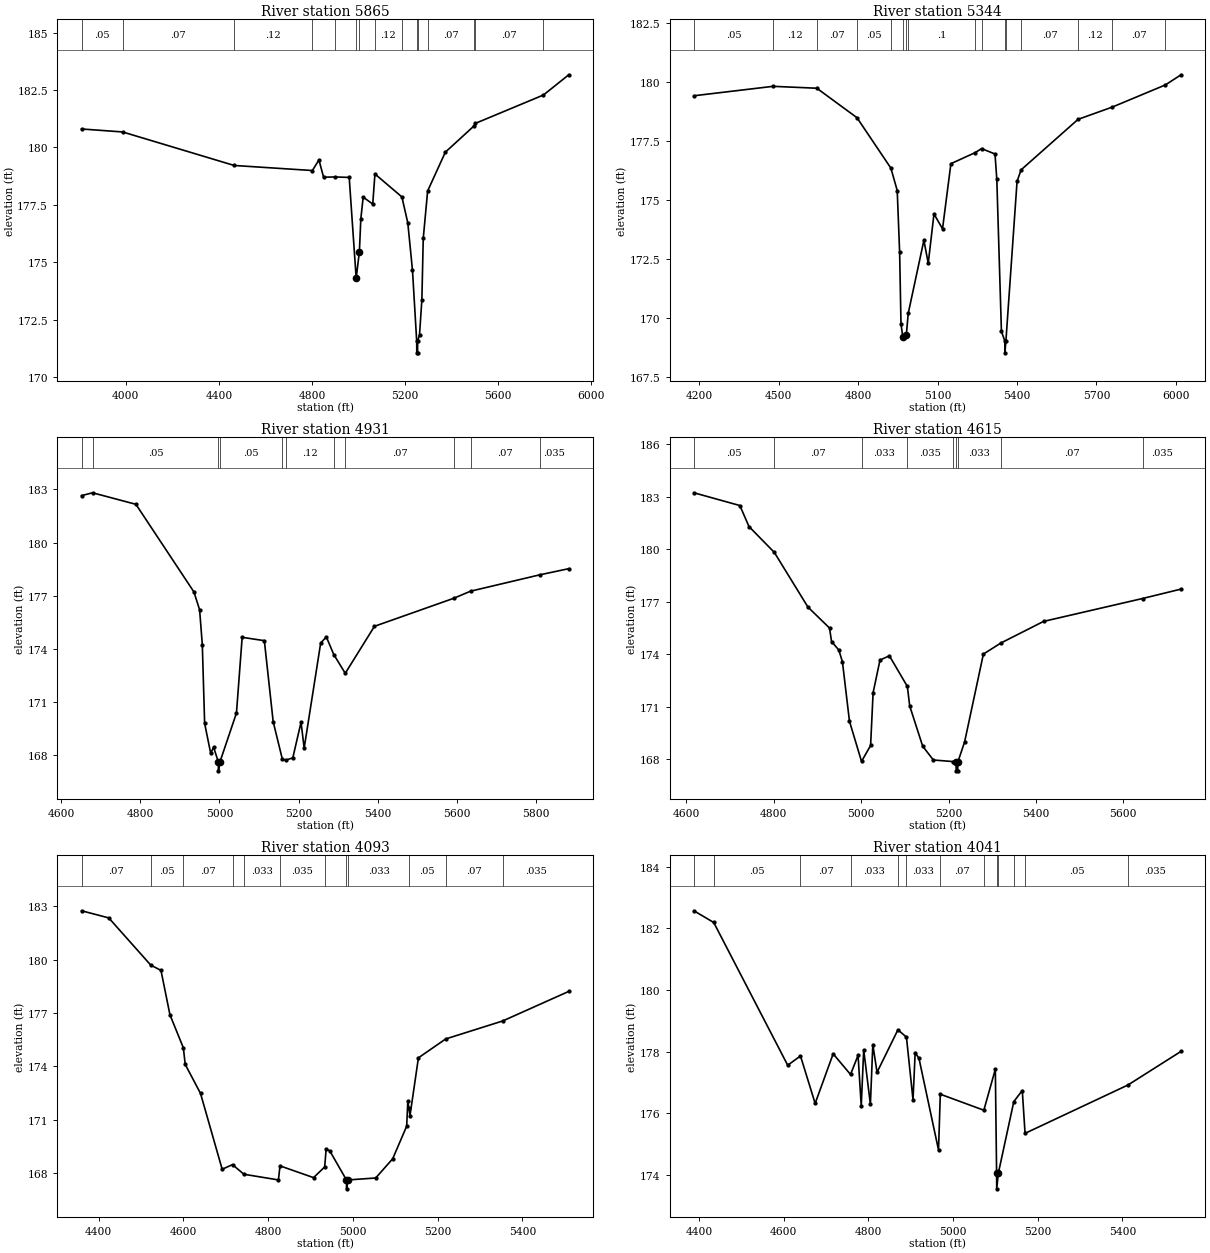
Type RM Length L Ch R = 1 ,5865    ,521,521,521
BEGIN DESCRIPTION:
Mapping XS 3d7df3fa
END DESCRIPTION:
XS GIS Cut Line= 3
      2500735.03     13494691.95      2501928.87     13494657.15
      2502820.59     13494535.71
#Sta/Elev= 30
  3809.8   180.8  3986.1  180.67    4466  179.21  4801.9  178.99  4830.2  179.45
  4850.2   178.7  4900.4  178.71  4960.3  178.69  4990.3   174.3  5004.1  175.46
  5010.3  176.89  5020.4  177.83  5061.5  177.53  5070.9  178.84  5186.8  177.84
  5212.2  176.71  5232.4  174.64  5250.5  171.55  5250.8  171.05  5254.3  171.05
  5254.5  171.55  5262.6  171.84  5272.7  173.36  5278.6  176.03  5297.5   178.1
  5373.7  179.79  5496.7  180.93  5501.9  181.04  5795.5  182.28  5904.1  183.16
#Mann= 15 ,-1 , 0
  3809.8     .05       0  3986.1     .07       0    4466     .12       0
  4801.9     .07       0  4900.4      .1       0  4990.3     .05       0
  5004.1      .1       0  5070.9     .12       0  5186.8      .1       0
  5250.5     .07       0  5254.5      .1       0  5297.5     .07       0
  5496.7     .12       0  5501.9     .07       0  5795.5     .05       0
Bank Sta=4990.3,5004.1
XS Rating Curve= 0 ,0
Exp/Cntr=0.3,0.1

Type RM Length L Ch R = 1 ,5344    ,413,413,413
BEGIN DESCRIPTION:
Mapping XS 7e7cf6c6
END DESCRIPTION:
XS GIS Cut Line= 5
      2501019.36     13495227.18      2501429.07     13495213.29
      2501808.21     13495114.62       2502389.8     13494880.25
      2502761.51     13494707.36
#Sta/Elev= 30
  4180.5  179.41  4479.2  179.81  4644.4  179.73    4796  178.48  4924.1  176.34
  4947.9  175.39    4957  172.77  4962.1  169.75  4968.6   169.2  4982.2  169.26
  4989.4  170.18  5048.5  173.28    5065  172.31  5086.6   174.4  5118.9  173.77
  5150.5  176.53  5242.3     177  5266.3  177.17    5317  176.94  5323.8  175.86
  5341.2  169.42  5354.1  169.01  5354.4  168.51  5358.1  169.01  5400.2  175.78
  5415.5  176.27  5630.4  178.41  5759.6  178.93    5960  179.87  6019.2   180.3
#Mann= 16 ,-1 , 0
  4180.5     .05       0  4479.2     .12       0  4644.4     .07       0
    4796     .05       0  4924.1      .1       0  4968.6     .05       0
  4982.2     .07       0  4989.4      .1       0  5242.3     .12       0
  5266.3      .1       0  5354.1     .07       0  5358.1      .1       0
  5415.5     .07       0  5630.4     .12       0  5759.6     .07       0
    5960    .035       0
Bank Sta=4968.6,4982.2
XS Rating Curve= 0 ,0
Exp/Cntr=0.3,0.1

Type RM Length L Ch R = 1 ,4931    ,316,316,316
BEGIN DESCRIPTION:
Mapping XS f40ff897
END DESCRIPTION:
XS GIS Cut Line= 3
       2501782.2     13495561.65      2502081.64     13495375.04
      2502761.19     13494821.01
#Sta/Elev= 30
  4652.1  182.65  4679.7  182.81  4789.2  182.16  4935.6  177.22    4950  176.21
  4956.8  174.25  4962.7   169.8    4978  168.12  4985.3  168.46  4997.3  167.63
  4997.5  167.13  5001.3  167.63    5043  170.39  5057.4  174.66  5113.4  174.47
  5135.7   169.9  5158.8  167.79  5166.8  167.73  5185.2  167.86    5206  169.87
  5213.9  168.41  5255.6  174.34  5269.9  174.68  5288.6  173.69  5317.6  172.63
  5391.3  175.28  5591.4  176.86  5633.8  177.26    5808  178.18  5881.7  178.53
#Mann= 11 ,-1 , 0
  4652.1     .07       0  4679.7     .05       0  4997.3     .05       0
  5001.3     .05       0  5158.8    .035       0  5166.8     .12       0
  5288.6    .033       0  5317.6     .07       0  5591.4     .12       0
  5633.8     .07       0    5808    .035       0
Bank Sta=4997.3,5001.3
XS Rating Curve= 0 ,0
Exp/Cntr=0.3,0.1

Type RM Length L Ch R = 1 ,4615    ,522,522,522
BEGIN DESCRIPTION:
Mapping XS 8b7eecd9
END DESCRIPTION:
XS GIS Cut Line= 4
       2502128.4     13495776.25      2502336.04     13495535.24
      2502469.51     13495197.85      2502761.23     13494876.59
#Sta/Elev= 30
  4617.3  183.23  4722.5   182.5  4743.3   181.3  4801.3  179.82  4878.3  176.69
  4927.7  175.49  4932.3  174.72    4949  174.23  4957.2  173.56  4973.3  170.16
  5000.9  167.86  5021.7  168.77  5027.4  171.79  5043.2  173.66  5064.7   173.9
  5105.8  172.15  5111.2  171.03  5140.9  168.73  5165.3  167.94  5210.7  167.85
  5217.3  167.82  5217.6  167.32  5221.1  167.32  5221.3  167.82  5236.8  168.97
  5279.8     174  5319.6  174.63  5417.5  175.87    5644  177.18  5732.2  177.72
#Mann= 9 ,-1 , 0
  4617.3     .05       0  4801.3     .07       0  5000.9    .033       0
  5105.8    .035       0  5210.7    .033       0  5217.3     .05       0
  5221.3    .033       0  5319.6     .07       0    5644    .035       0
Bank Sta=5217.3,5221.3
XS Rating Curve= 0 ,0
Exp/Cntr=0.3,0.1

Type RM Length L Ch R = 1 ,4093    ,52,52,52
BEGIN DESCRIPTION:
Mapping XS 7f8bc250
END DESCRIPTION:
XS GIS Cut Line= 6
      2502376.38     13495876.03      2502633.86     13495473.71
      2502672.75     13495375.81      2502660.68     13495192.09
      2502636.55     13495080.79      2502789.24     13494859.78
#Sta/Elev= 30
  4359.7  182.74  4423.8  182.34  4522.9  179.69  4547.1  179.39  4568.2   176.9
  4599.9  175.04  4604.3  174.11  4640.4  172.48  4691.5  168.22  4715.9  168.48
  4742.7  167.94  4824.3  167.62    4828  168.41  4907.2  167.75  4933.5  168.35
  4936.9  169.36  4945.8  169.24  4984.8  167.62  4985.1  167.12  4988.8  167.62
  5053.9  167.73    5094  168.81    5127  170.64  5129.7  172.06  5132.2  171.65
  5134.8  171.23  5154.7  174.48  5219.1  175.54  5353.6  176.55  5509.5  178.21
#Mann= 12 ,-1 , 0
  4359.7     .07       0  4522.9     .05       0  4599.9     .07       0
  4715.9    .035       0  4742.7    .033       0    4828    .035       0
  4933.5    .033       0  4984.8    .033       0  4988.8    .033       0
  5132.2     .05       0  5219.1     .07       0  5353.6    .035       0
Bank Sta=4984.8,4988.8
XS Rating Curve= 0 ,0
Exp/Cntr=0.3,0.1

Type RM Length L Ch R = 1 ,4041    ,47,47,47
BEGIN DESCRIPTION:
Mapping XS 1a322c1b
END DESCRIPTION:
XS GIS Cut Line= 6
      2502410.18     13495880.04       2502614.1     13495601.97
      2502684.55     13495479.62       2502710.5     13495327.62
      2502664.73     13495097.09      2502810.29     13494864.68
#Sta/Elev= 30
  4388.4  182.57  4435.2  182.19  4609.8  177.56    4640  177.86  4674.6  176.32
  4717.1  177.93  4758.1  177.26  4775.9  177.88  4783.4  176.24  4789.2  178.06
    4805  176.29  4810.7  178.23  4820.7  177.33    4870  178.71  4890.1  178.47
  4905.6  176.44  4910.7  177.97  4919.7  177.78  4965.8  174.81    4970  176.62
  5072.8   176.1  5099.9  177.43  5102.9  174.05  5103.2  173.55  5106.9  174.05
  5143.5  176.38  5163.5  176.74  5170.1  175.35  5413.2  176.92  5538.3  178.01
#Mann= 13 ,-1 , 0
  4388.4     .07       0  4435.2     .05       0    4640     .07       0
  4758.1    .033       0    4870    .035       0  4890.1    .033       0
    4970     .07       0  5072.8     .05       0  5102.9     .05       0
  5106.9     .05       0  5143.5    .033       0  5170.1     .05       0
  5413.2    .035       0
Bank Sta=5102.9,5106.9
XS Rating Curve= 0 ,0
Exp/Cntr=0.3,0.1

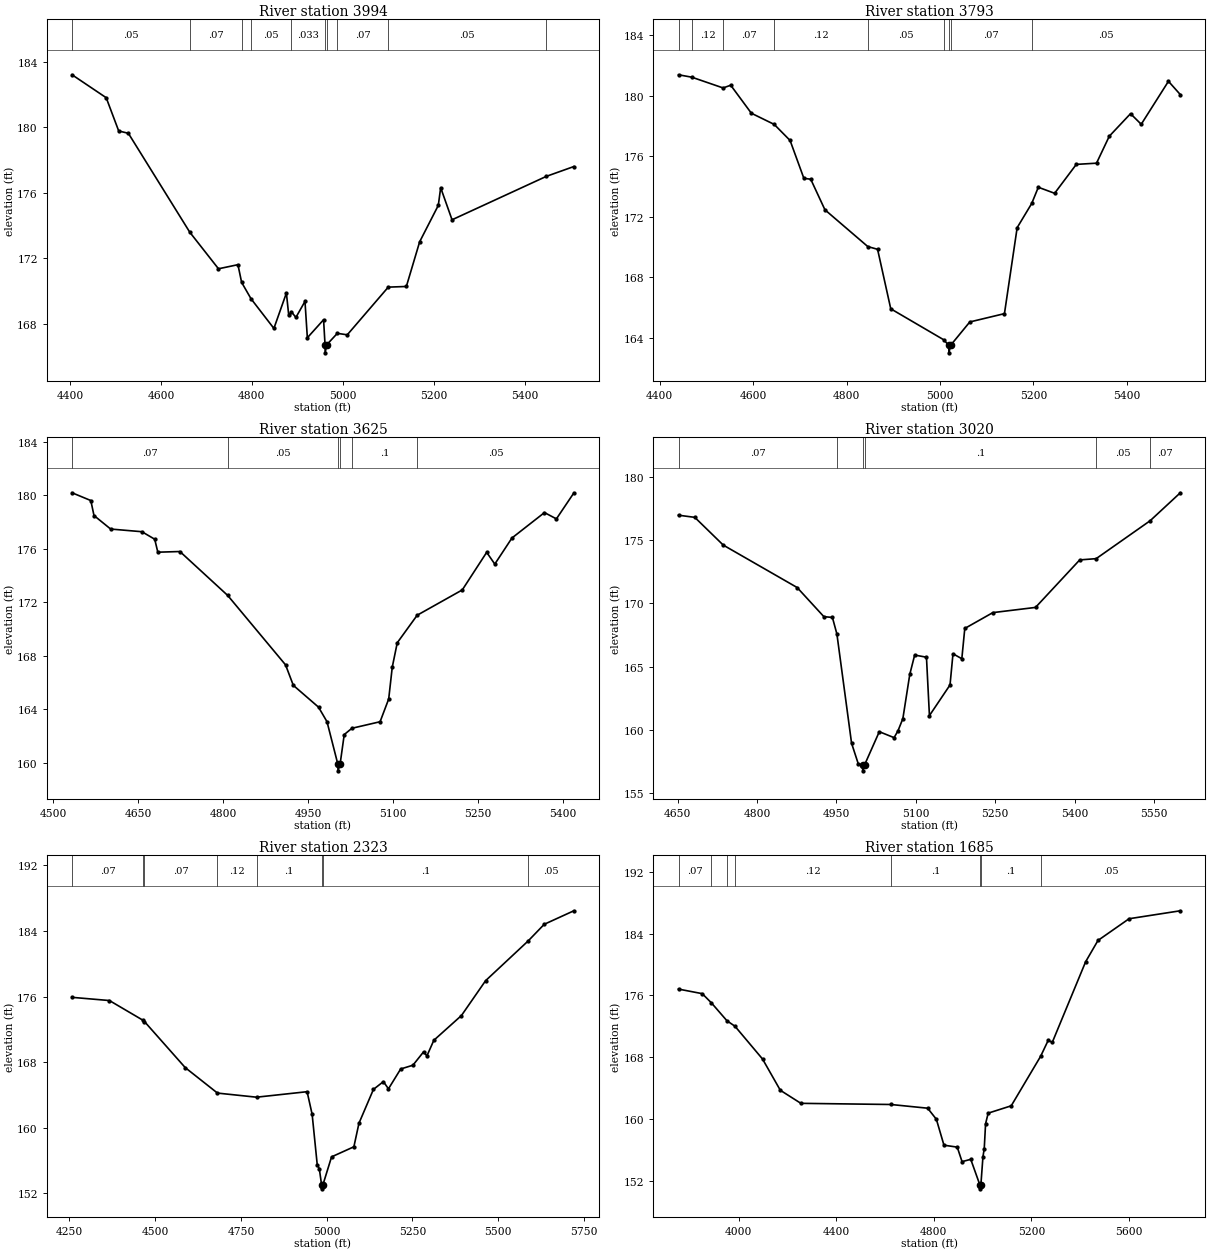
Type RM Length L Ch R = 1 ,3994    ,201,201,201
BEGIN DESCRIPTION:
Mapping XS d169ff8d
END DESCRIPTION:
XS GIS Cut Line= 6
      2502476.96     13495898.82      2502712.98     13495517.96
      2502747.85     13495381.18      2502745.17     13495201.48
      2502731.76     13495092.86      2502827.78      13494888.8
#Sta/Elev= 30
  4404.5  183.21  4479.6  181.81  4507.1  179.78  4528.3  179.64  4663.5   173.6
  4726.6  171.37  4769.4  171.62  4777.5  170.54  4798.2  169.54  4848.5  167.73
    4876  169.89  4881.2  168.52    4887  168.75  4896.9   168.4  4916.9  169.38
  4922.1  167.16  4957.8  168.26    4961  166.74  4961.2  166.24    4965  166.74
  4988.1  167.43  5009.9  167.34  5100.1  170.25  5139.9  170.29  5169.2  173.02
  5210.2  175.24  5215.4  176.32  5240.4  174.36  5447.8  177.01  5508.4  177.61
#Mann= 10 ,-1 , 0
  4404.5     .05       0  4663.5     .07       0  4777.5    .033       0
  4798.2     .05       0    4887    .033       0    4961     .05       0
    4965    .033       0  4988.1     .07       0  5100.1     .05       0
  5447.8    .035       0
Bank Sta=4961,4965
XS Rating Curve= 0 ,0
Exp/Cntr=0.3,0.1

Type RM Length L Ch R = 1 ,3793    ,168,168,168
BEGIN DESCRIPTION:
Mapping XS 0a569959
END DESCRIPTION:
XS GIS Cut Line= 3
      2502660.68     13495963.18      2502918.16       13495467.
      2503179.67     13495023.11
#Sta/Elev= 30
  4440.4  181.37  4468.9  181.21  4535.8   180.5  4552.1  180.68  4596.3  178.83
  4645.3  178.09  4679.2  177.03  4708.7  174.53  4723.4  174.47  4753.8  172.45
  4845.6  170.02  4866.5  169.84  4894.7  165.91  5007.7  163.87  5018.9   163.5
  5019.2     163  5022.9   163.5  5063.9  165.04  5138.1  165.59  5165.3  171.27
  5196.5  172.87  5210.6  173.94  5245.5  173.54  5291.9  175.45  5335.2  175.53
  5362.5  177.31    5408   178.8  5430.9   178.1  5489.2  180.94  5514.6  180.06
#Mann= 9 ,-1 , 0
  4440.4     .07       0  4468.9     .12       0  4535.8     .07       0
  4645.3     .12       0  4845.6     .05       0  5007.7     .07       0
  5018.9     .05       0  5022.9     .07       0  5196.5     .05       0
Bank Sta=5018.9,5022.9
XS Rating Curve= 0 ,0
Exp/Cntr=0.3,0.1

Type RM Length L Ch R = 1 ,3625    ,605,605,605
BEGIN DESCRIPTION:
Mapping XS 5212d562
END DESCRIPTION:
XS GIS Cut Line= 3
      2502863.78     13495936.23       2503059.1     13495534.72
      2503297.81     13495165.81
#Sta/Elev= 30
  4533.1  180.17  4566.2  179.59  4571.8  178.47  4601.2  177.46  4656.4  177.26
    4679   176.7  4684.5  175.73  4723.5  175.78  4807.8   172.5    4910  167.31
  4923.7  165.78  4968.2  164.15  4983.2  163.06  5002.3  159.89  5002.6  159.39
  5006.3  159.89  5013.6   162.1  5027.1  162.57  5076.9  163.06  5092.1  164.76
  5098.4  167.14  5107.2  168.96  5142.4  171.02    5222  172.91  5265.1  175.72
  5279.4  174.84  5309.7  176.79  5367.1  178.69  5388.2  178.22    5419  180.16
#Mann= 6 ,-1 , 0
  4533.1     .07       0  4807.8     .05       0  5002.3     .05       0
  5006.3     .05       0  5027.1      .1       0  5142.4     .05       0
Bank Sta=5002.3,5006.3
XS Rating Curve= 0 ,0
Exp/Cntr=0.3,0.1

Type RM Length L Ch R = 1 ,3020    ,697,697,697
BEGIN DESCRIPTION:
Mapping XS 772cbc05
END DESCRIPTION:
XS GIS Cut Line= 3
      2503138.94     13496062.53      2503465.33     13495881.98
      2503725.24     13495369.08
#Sta/Elev= 30
  4651.6  176.95  4682.3  176.78  4736.1  174.59  4875.7  171.24  4926.2  168.94
  4942.3  168.88  4950.8  167.57  4978.5  158.95  4991.5  157.28  4999.4  157.27
  4999.6  156.77  5003.4  157.27  5030.9  159.86  5058.8  159.39  5066.1  159.92
  5075.4  160.89  5088.5  164.39  5097.7  165.91    5120  165.74  5125.6  161.13
  5164.5  163.55  5170.1  166.01  5186.8  165.62  5192.4  168.01  5245.4  169.26
    5326  169.67  5409.5  173.42  5440.6  173.52  5542.5  176.51  5599.6  178.72
#Mann= 6 ,-1 , 0
  4651.6     .07       0  4950.8      .1       0  4999.4     .05       0
  5003.4      .1       0  5440.6     .05       0  5542.5     .07       0
Bank Sta=4999.4,5003.4
XS Rating Curve= 0 ,0
Exp/Cntr=0.3,0.1

Type RM Length L Ch R = 1 ,2323    ,638,638,638
BEGIN DESCRIPTION:
Mapping XS 2ae3e25c
END DESCRIPTION:
XS GIS Cut Line= 4
      2503298.64      13496128.5      2503847.27     13496250.04
      2504211.85     13495989.62      2504260.37     13495539.09
#Sta/Elev= 30
  4257.7  175.91  4366.6  175.52  4465.1   173.1  4468.7  172.96  4587.6  167.34
  4681.7  164.23  4795.6  163.73    4943   164.4  4957.7  161.64  4972.5  155.51
  4978.6     155  4985.2  153.05  4985.5  152.55  4989.2  153.05  5014.3  156.45
  5079.4  157.68  5094.2  160.55  5136.4  164.68  5165.4  165.63  5180.2  164.75
  5215.8  167.17  5251.5  167.63  5282.4  169.25  5292.4  168.77  5312.5  170.67
    5393  173.69  5463.4  177.94  5587.8   182.8  5634.4  184.82  5720.8  186.47
#Mann= 8 ,-1 , 0
  4257.7     .07       0  4465.1     .12       0  4468.7     .07       0
  4681.7     .12       0  4795.6      .1       0  4985.2     .05       0
  4989.2      .1       0  5587.8     .05       0
Bank Sta=4985.2,4989.2
XS Rating Curve= 0 ,0
Exp/Cntr=0.3,0.1

Type RM Length L Ch R = 1 ,1685    ,1141,1141,1141
BEGIN DESCRIPTION:
Mapping XS 6dc7e328
END DESCRIPTION:
XS GIS Cut Line= 4
      2503340.31     13496208.36      2504145.88      13496604.2
       2504743.1     13496381.98      2504847.08     13495869.01
#Sta/Elev= 30
  3752.9  176.82  3850.1  176.23  3887.7  175.04  3951.5  172.72  3984.4  172.01
  4097.4  167.77  4170.4  163.72  4254.7  162.03  4623.8  161.88  4774.7   161.4
  4810.4  159.97  4841.6  156.61  4896.1  156.36  4915.8  154.48  4951.5  154.78
    4989  151.46  4989.2  150.96    4993  151.46  5001.5  155.11  5006.8  156.15
  5012.3  159.39    5023  160.76  5117.5  161.71  5238.3  168.13  5269.2  170.19
    5286  169.93  5422.7  180.36  5473.4  183.12  5600.9  185.93  5811.1  186.96
#Mann= 8 ,-1 , 0
  3752.9     .07       0  3887.7     .12       0  3951.5     .07       0
  3984.4     .12       0  4623.8      .1       0    4989     .05       0
    4993      .1       0  5238.3     .05       0
Bank Sta=4989,4993
XS Rating Curve= 0 ,0
Exp/Cntr=0.3,0.1

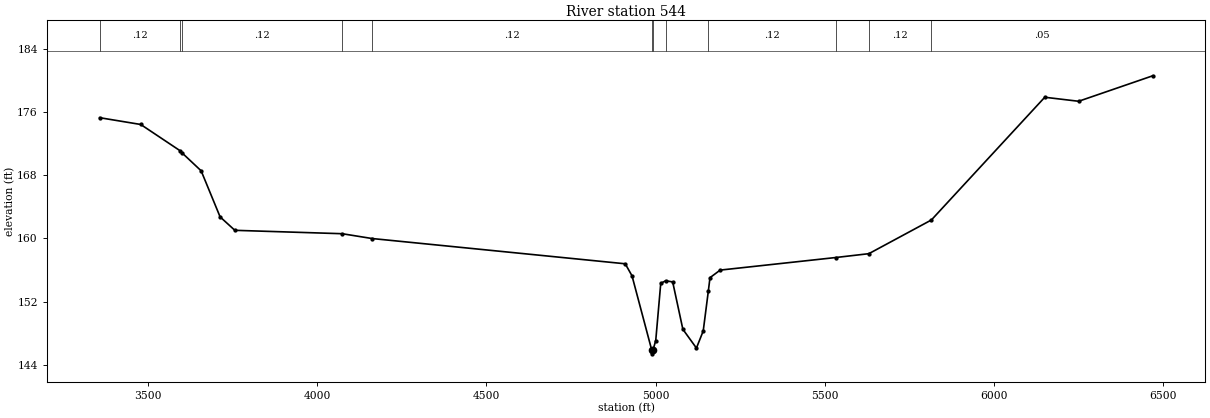
Type RM Length L Ch R = 1 ,544     ,0,0,0
BEGIN DESCRIPTION:
TRIB 1 TO EIGHTEENMILE CREEK 6.0
END DESCRIPTION:
XS GIS Cut Line= 4
      2503385.44     13496364.61      2504357.69     13497111.15
      2505079.91     13497059.06       2505118.1     13495895.89
#Sta/Elev= 30
  3356.2   175.3  3477.7  174.44  3594.2  171.11  3600.4  170.82  3656.3  168.57
  3712.4  162.73    3756  161.03  4073.2   160.6  4161.6  159.99  4910.2  156.79
  4930.2  155.27  4988.4  145.88  4988.6  145.38  4992.4  145.88  5000.4  147.06
  5015.2  154.31  5029.8  154.64  5050.5  154.49  5080.6  148.49  5120.7  146.11
  5140.8  148.28  5155.9  153.33  5160.8  155.03  5190.9  155.99  5531.9  157.58
  5630.5  158.07  5815.4  162.34  6150.6  177.89  6250.7  177.38  6469.9  180.61
#Mann= 12 ,-1 , 0
  3356.2     .12       0  3594.2     .07       0  3600.4     .12       0
  4073.2     .07       0  4161.6     .12       0  4988.4     .05       0
  4992.4     .12       0  5029.8     .07       0  5155.9     .12       0
  5531.9     .07       0  5630.5     .12       0  5815.4     .05       0
Bank Sta=4988.4,4992.4
XS Rating Curve= 0 ,0
Exp/Cntr=0.3,0.1

Chan Stop Cuts=-1
Use User Specified Reach Order=0
Composite Channel Slope=5