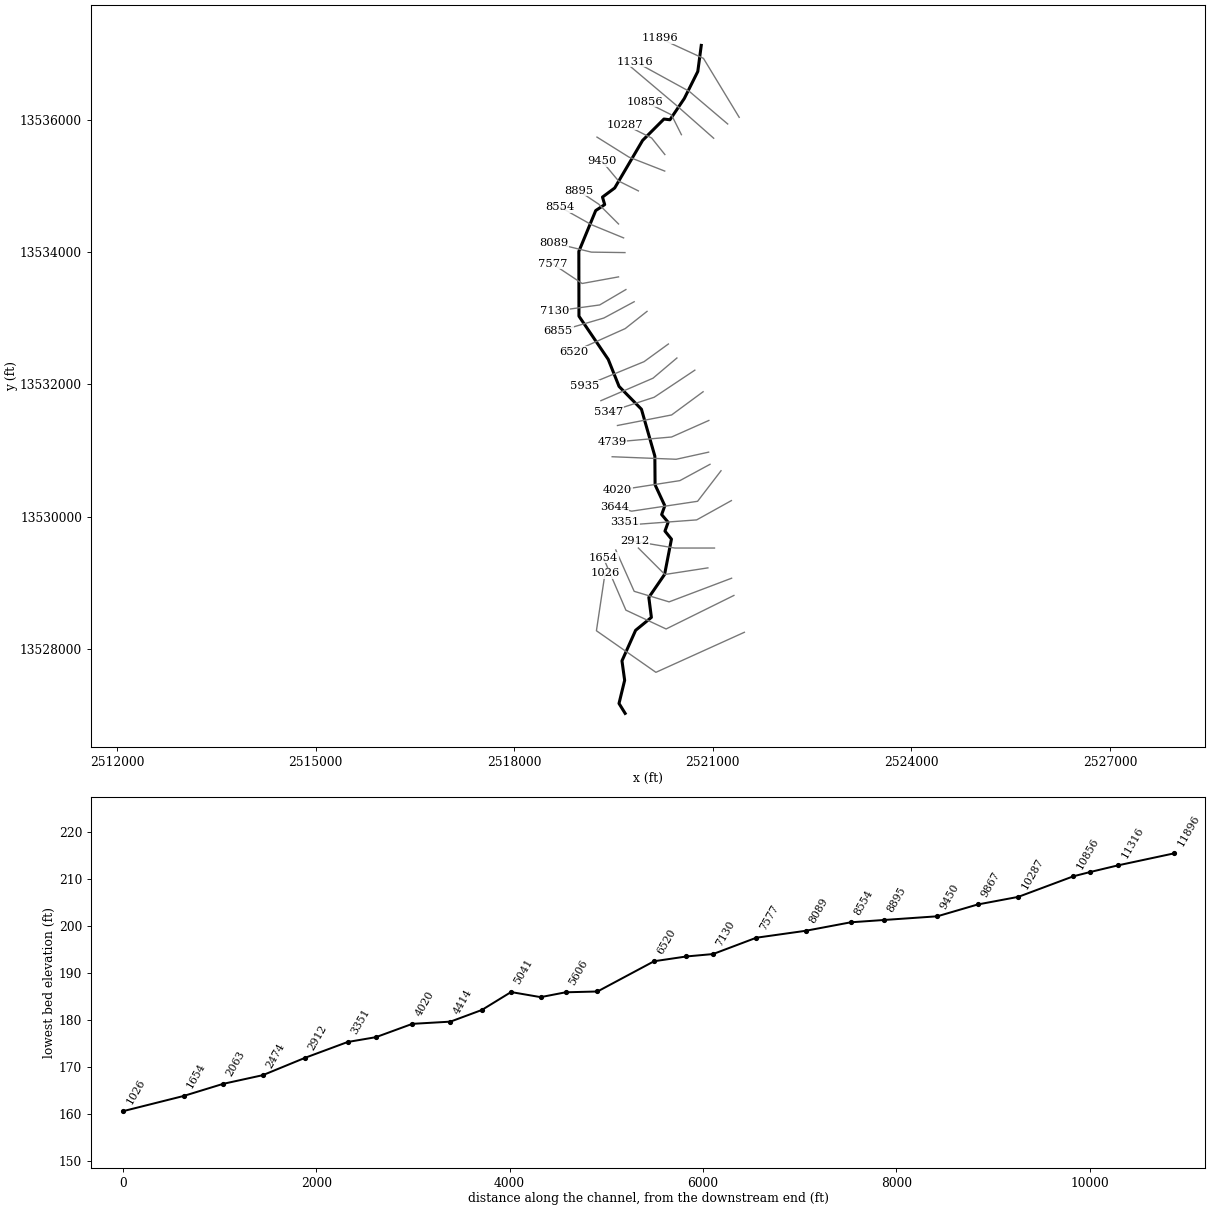
--- TRIB 1 TO FIVEMILE CREEK.prj (project) ---

Proj Title=TRIB 1 TO FIVEMILE CREEK Base Level Engineering
Current Plan=p01
Default Exp/Contr=0.3,0.1
English Units
Geom File=g01
Flow File=f01
Plan File=p01
BEGIN DESCRIPTION:
TRIB 1 TO FIVEMILE CREEK
END DESCRIPTION:

--- TRIB 1 TO FIVEMILE CREEK.p01 (plan) ---

Plan Title=Multiple Run
Short Identifier=Multiple
Geom File=g01
Flow File=f01
Subcritical Flow
K Sum by GR= 0
Std Step Tol= 0.01
Critical Tol= 0.01
Num of Std Step Trials= 20
Max Error Tol= 0.3
Flow Tol Ratio= 0.001
Split Flow NTrial= 30
Split Flow Tol= 0.02
Split Flow Ratio= 0.02
Log Output Level= 0
Friction Slope Method= 1
Unsteady Friction Slope Method= 2
Unsteady Bridges Friction Slope Method= 1
Parabolic Critical Depth
Global Vel Dist=  1 , 1 , 1
Global Log Level= 0
CheckData=True
Encroach Param= -1, 0, 0, 0
BEGIN DESCRIPTION:
Multiple Run
END DESCRIPTION:

--- TRIB 1 TO FIVEMILE CREEK.f01 (steady flow) ---

Flow Title=Multiple
Number of Profiles=7
Profile Names=10-year,25-year,50-year,1pct_min,100-year,1pct_plu,500-year
River Rch & RM= TRIB 1 TO FIVEMI,Reach-1,11896
     387     596     775     489     976    1947    1527
River Rch & RM= TRIB 1 TO FIVEMI,Reach-1,11024
     620     983    1305     837    1671    3334    2710
River Rch & RM= TRIB 1 TO FIVEMI,Reach-1,5041
     775    1246    1668    1079    2154    4297    3553
Boundary for River Rch & Prof#=TRIB 1 TO FIVEMI,Reach-1,1
Up Type=0
Dn Type=3
Dn Slope=0.005
Boundary for River Rch & Prof#=TRIB 1 TO FIVEMI,Reach-1,2
Up Type=0
Dn Type=3
Dn Slope=0.005
Boundary for River Rch & Prof#=TRIB 1 TO FIVEMI,Reach-1,3
Up Type=0
Dn Type=3
Dn Slope=0.005
Boundary for River Rch & Prof#=TRIB 1 TO FIVEMI,Reach-1,4
Up Type=0
Dn Type=3
Dn Slope=0.005
Boundary for River Rch & Prof#=TRIB 1 TO FIVEMI,Reach-1,5
Up Type=0
Dn Type=3
Dn Slope=0.005
Boundary for River Rch & Prof#=TRIB 1 TO FIVEMI,Reach-1,6
Up Type=0
Dn Type=3
Dn Slope=0.005
Boundary for River Rch & Prof#=TRIB 1 TO FIVEMI,Reach-1,7
Up Type=0
Dn Type=3
Dn Slope=0.005

--- TRIB 1 TO FIVEMILE CREEK.g01 (geometry) ---

Geom Title=Existing Conditions

River Reach=TRIB 1 TO FIVEMI,Reach-1
Reach XY= 30
      2520825.00     13537125.00      2520772.76     13536730.93
      2520569.17     13536322.70      2520352.12     13536000.59
      2520261.32     13536011.49      2519938.61     13535688.24
      2519516.87     13534968.93      2519332.39     13534831.33
      2519365.97     13534717.99      2519230.42     13534627.67
      2518975.38     13534009.84      2518977.06     13533030.85
      2519419.48     13532377.43      2519583.02     13531968.66
      2519921.39     13531623.50      2520123.80     13530914.50
      2520127.24     13530480.93      2520274.23     13530164.31
      2520226.63     13530031.04      2520324.39     13529914.37
      2520276.63     13529781.04      2520374.61     13529659.84
      2520271.24     13529126.56      2520032.81     13528778.41
      2520071.47     13528476.45      2519833.13     13528281.07
      2519627.06     13527819.14      2519667.44     13527525.00
      2519582.31     13527174.90      2519675.00     13527025.00

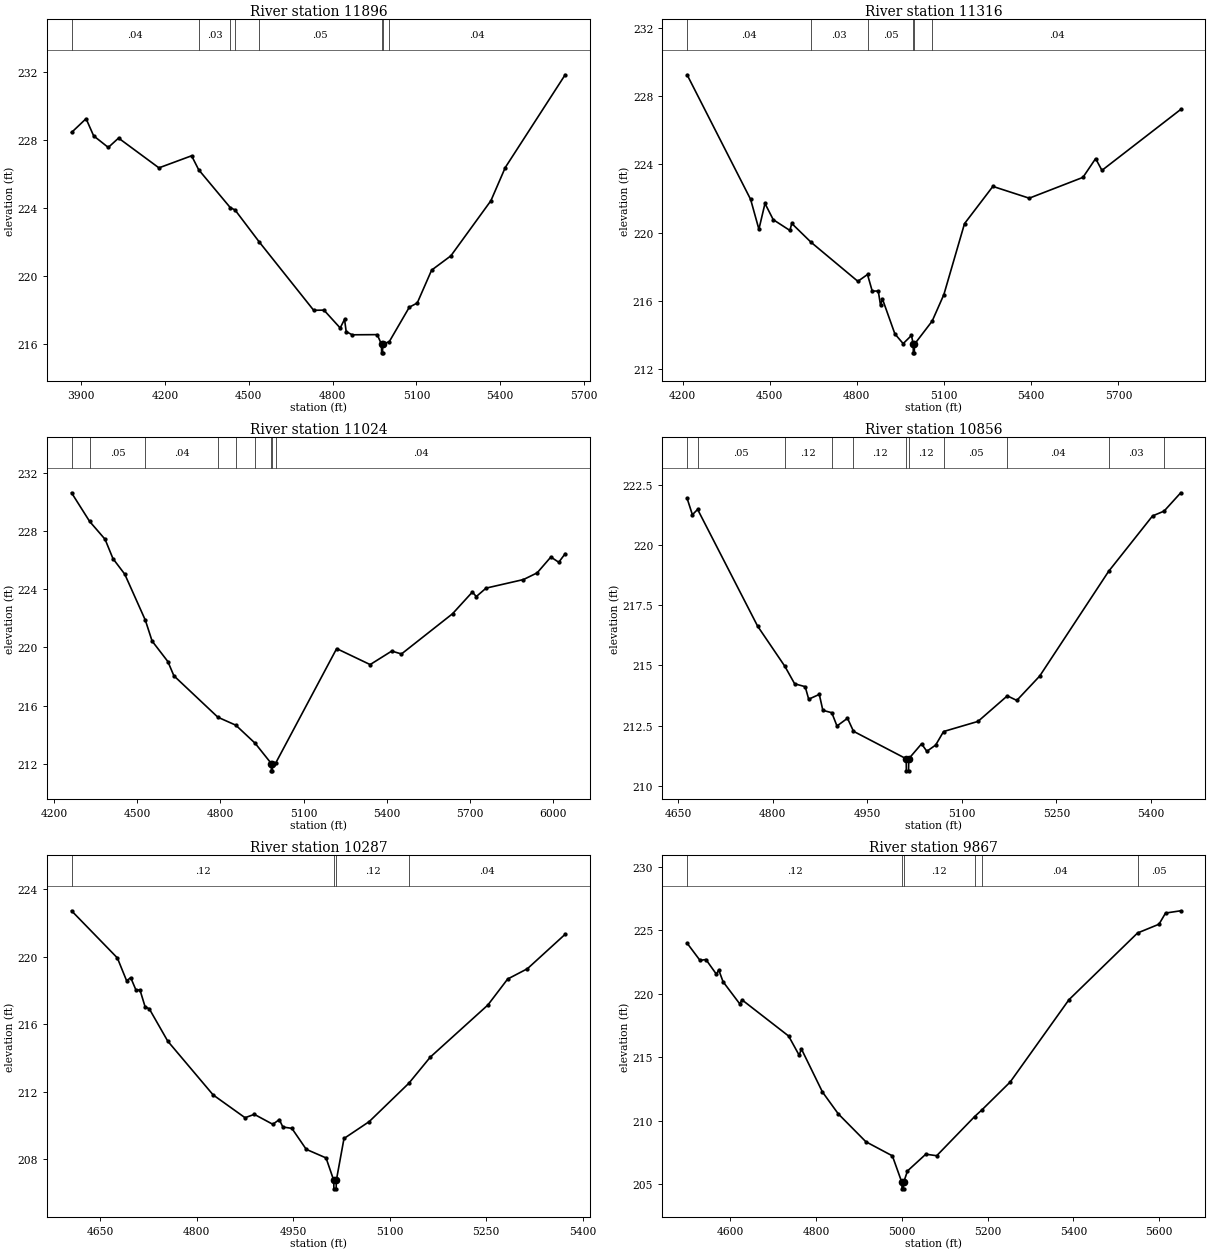
Type RM Length L Ch R = 1,11896,580,580,580
BEGIN DESCRIPTION:
Mapping XS f779290d
END DESCRIPTION:
XS GIS Cut Line= 3
      2521398.04     13536037.41      2520858.20     13536928.94
      2520200.10     13537231.85
#Sta/Elev= 30
  3865.8  228.45  3917.8  229.26  3945.0  228.25  3997.3  227.57  4034.1  228.12
  4178.6  226.37  4295.5  227.08  4320.8  226.26  4434.1  224.03  4450.8  223.90
  4537.4  222.02  4732.4  218.00  4769.2  218.01  4827.3  216.96  4842.9  217.47
  4848.7  216.75  4870.1  216.56  4959.8  216.57  4975.2  216.00  4975.5  215.50
  4979.0  215.50  4979.2  216.00  5003.1  216.16  5074.6  218.18  5103.1  218.43
  5154.5  220.36  5223.4  221.20  5366.7  224.44  5418.1  226.39  5632.5  231.84
#Mann=8,-1,0
  3865.8    0.04       0  4320.8    0.03       0  4434.1    0.05       0
  4450.8    0.03       0  4537.4    0.05       0  4975.2    0.05       0
  4979.2    0.05       0  5003.1    0.04       0
Bank Sta=4975.2,4979.2
Exp/Cntr=0.3,0.1

Type RM Length L Ch R = 1,11316,292,292,292
BEGIN DESCRIPTION:
Mapping XS fba86e41
END DESCRIPTION:
XS GIS Cut Line= 3
      2521224.47     13535936.67      2520644.58     13536429.74
      2519822.68     13536880.57
#Sta/Elev= 30
  4215.8  229.24  4434.4  221.94  4462.9  220.19  4483.8  221.70  4512.3  220.75
  4569.5  220.12  4576.0  220.53  4642.2  219.43  4803.4  217.14  4836.6  217.54
  4852.8  216.57  4873.6  216.57  4881.4  215.74  4887.9  216.11  4930.8  214.06
  4959.3  213.49  4987.9  213.97  4994.0  213.45  4994.2  212.95  4997.7  212.95
  4998.0  213.45  5059.1  214.81  5099.3  216.36  5170.4  220.52  5268.0  222.70
  5393.1  222.01  5577.9  223.23  5621.5  224.33  5643.3  223.64  5914.4  227.21
#Mann=6,-1,0
  4215.8    0.04       0  4642.2    0.03       0  4836.6    0.05       0
  4994.0    0.05       0  4998.0    0.05       0  5059.1    0.04       0
Bank Sta=4994,4998
Exp/Cntr=0.3,0.1

Type RM Length L Ch R = 1,11024,168,168,168
BEGIN DESCRIPTION:
Mapping XS 1b69736f
END DESCRIPTION:
XS GIS Cut Line= 3
      2521012.61     13535721.44      2520450.14     13536217.94
      2519661.93     13536884.61
#Sta/Elev= 30
  4262.3  230.64  4327.6  228.67  4383.4  227.44  4411.9  226.11  4454.5  225.04
  4528.9  221.87  4553.2  220.44  4610.1  219.03  4631.9  218.05  4790.7  215.20
  4855.6  214.65  4925.2  213.41  4983.8  212.01  4984.0  211.51  4987.5  211.51
  4987.8  212.01  5000.0  212.06  5219.7  219.92  5340.6  218.82  5418.6  219.75
  5453.7  219.55  5638.3  222.32  5709.7  223.81  5724.0  223.50  5759.2  224.08
  5894.3  224.67  5943.7  225.13  5993.2  226.22  6021.8  225.86  6044.9  226.45
#Mann=9,-1,0
  4262.3    0.04       0  4327.6    0.05       0  4528.9    0.04       0
  4790.7    0.12       0  4855.6    0.04       0  4925.2    0.05       0
  4983.8    0.04       0  4987.8    0.05       0  5000.0    0.04       0
Bank Sta=4983.8,4987.8
Exp/Cntr=0.3,0.1

Type RM Length L Ch R = 1,10856,569,569,569
BEGIN DESCRIPTION:
TRIB 1 TO FIVEMILE CREEK 23.0
END DESCRIPTION:
XS GIS Cut Line= 3
      2520524.99     13535775.03      2520375.00     13536075.00
      2519975.00     13536275.00
#Sta/Elev= 30
  4664.6  221.93  4673.0  221.25  4681.3  221.47  4776.4  216.63  4819.7  214.96
  4835.1  214.24  4851.8  214.12  4857.4  213.60  4874.2  213.80  4879.8  213.14
  4894.0  213.04  4902.2  212.49  4918.9  212.81  4928.4  212.27  5012.0  211.13
  5012.2  210.63  5015.7  210.63  5016.0  211.13  5036.3  211.75  5044.7  211.44
  5058.7  211.70  5071.2  212.26  5125.8  212.68  5172.3  213.74  5187.3  213.55
  5223.6  214.56  5332.8  218.90  5402.5  221.20  5420.8  221.40  5447.2  222.16
#Mann=11,-1,0
  4664.6    0.12       0  4681.3    0.05       0  4819.7    0.12       0
  4894.0    0.05       0  4928.4    0.12       0  5012.0    0.05       0
  5016.0    0.12       0  5071.2    0.05       0  5172.3    0.04       0
  5332.8    0.03       0  5420.8    0.04       0
Bank Sta=5012,5016
Exp/Cntr=0.3,0.1

Type RM Length L Ch R = 1,10287,420,420,420
BEGIN DESCRIPTION:
TRIB 1 TO FIVEMILE CREEK 22.0
END DESCRIPTION:
XS GIS Cut Line= 3
      2520274.97     13535475.03      2520075.00     13535725.00
      2519675.02     13535924.99
#Sta/Elev= 30
  4605.3  222.72  4676.5  219.93  4690.9  218.58  4697.3  218.76  4705.3  218.04
  4711.7  218.03  4719.7  217.03  4726.1  216.92  4754.9  215.00  4825.4  211.82
  4875.0  210.47  4889.4  210.67  4918.2  210.08  4928.2  210.36  4933.8  209.92
  4947.8  209.84  4970.1  208.60  5000.9  208.09  5012.9  206.76  5013.1  206.26
  5016.6  206.26  5016.9  206.76  5028.8  209.24  5068.0  210.24  5129.6  212.51
  5163.0  214.06  5252.4  217.14  5283.2  218.68  5313.9  219.29  5372.6  221.33
#Mann=4,-1,0
  4605.3    0.12       0  5012.9    0.05       0  5016.9    0.12       0
  5129.6    0.04       0
Bank Sta=5012.9,5016.9
Exp/Cntr=0.3,0.1

Type RM Length L Ch R = 1,9867,417,417,417
BEGIN DESCRIPTION:
Mapping XS e35f4ad4
END DESCRIPTION:
XS GIS Cut Line= 3
      2520273.04     13535224.89      2519731.39     13535436.69
      2519249.40     13535738.37
#Sta/Elev= 30
  4499.8  224.00  4529.9  222.64  4543.7  222.71  4568.1  221.55  4573.5  221.89
  4583.6  220.96  4622.4  219.22  4627.8  219.53  4736.4  216.68  4760.9  215.17
  4766.2  215.66  4815.2  212.27  4852.0  210.55  4916.4  208.35  4978.1  207.24
  5000.3  205.14  5000.6  204.64  5004.1  204.64  5004.3  205.14  5013.3  206.05
  5056.0  207.37  5081.4  207.25  5169.9  210.34  5187.0  210.87  5252.7  213.06
  5389.5  219.54  5549.4  224.80  5599.3  225.49  5614.6  226.37  5650.0  226.55
#Mann=6,-1,0
  4499.8    0.12       0  5000.3    0.05       0  5004.3    0.12       0
  5169.9    0.05       0  5187.0    0.04       0  5549.4    0.05       0
Bank Sta=5000.3,5004.3
Exp/Cntr=0.3,0.1

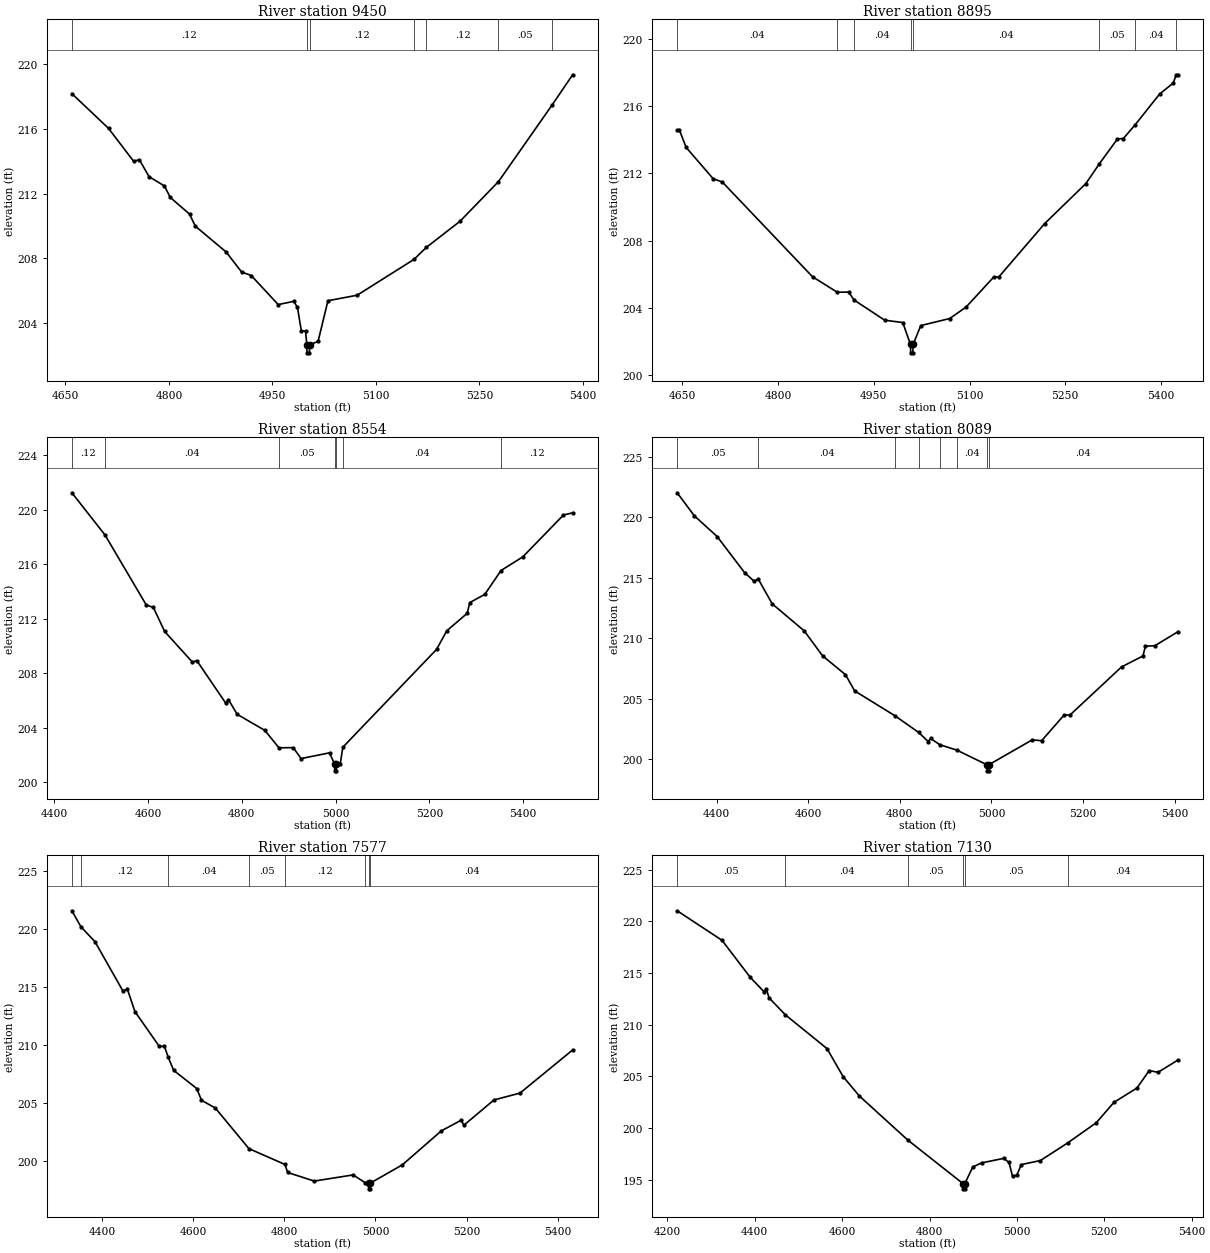
Type RM Length L Ch R = 1,9450,555,555,555
BEGIN DESCRIPTION:
TRIB 1 TO FIVEMILE CREEK 20.0
END DESCRIPTION:
XS GIS Cut Line= 3
      2519875.02     13534924.99      2519575.00     13535075.00
      2519325.03     13535374.97
#Sta/Elev= 30
  4659.3  218.19  4712.4  216.04  4748.8  214.00  4757.1  214.10  4771.1  213.05
  4793.5  212.47  4801.9  211.76  4829.8  210.73  4838.2  209.98  4882.9  208.38
  4905.3  207.14  4919.3  206.92  4958.4  205.12  4980.8  205.32  4986.3  204.95
  4991.9  203.49  4998.0  203.49  4999.9  202.63  5000.1  202.13  5003.6  202.13
  5003.9  202.63  5016.2  202.84  5030.5  205.36  5072.8  205.70  5155.2  207.92
  5173.3  208.67  5221.9  210.28  5277.7  212.74  5355.5  217.49  5385.2  219.36
#Mann=7,-1,0
  4659.3    0.12       0  4999.9    0.05       0  5003.9    0.12       0
  5155.2    0.05       0  5173.3    0.12       0  5277.7    0.05       0
  5355.5    0.12       0
Bank Sta=4999.9,5003.9
Exp/Cntr=0.3,0.1

Type RM Length L Ch R = 1,8895,341,341,341
BEGIN DESCRIPTION:
TRIB 1 TO FIVEMILE CREEK 19.0
END DESCRIPTION:
XS GIS Cut Line= 3
      2519574.98     13534425.02      2519275.00     13534725.00
      2518974.99     13534925.01
#Sta/Elev= 30
  4641.8  214.57  4645.3  214.57  4655.9  213.54  4698.3  211.68  4712.5  211.49
  4853.9  205.86  4892.7  204.94  4910.5  204.95  4919.0  204.48  4967.0  203.28
  4995.3  203.14  5007.5  201.84  5007.7  201.34  5011.2  201.34  5011.5  201.84
  5023.6  202.96  5069.0  203.38  5094.6  204.06  5138.1  205.85  5145.7  205.84
  5217.8  209.02  5282.4  211.40  5303.6  212.58  5331.9  214.05  5341.0  214.07
  5359.6  214.89  5398.0  216.72  5419.1  217.36  5424.0  217.86  5426.6  217.86
#Mann=8,-1,0
  4641.8    0.04       0  4892.7    0.05       0  4919.0    0.04       0
  5007.5    0.04       0  5011.5    0.04       0  5303.6    0.05       0
  5359.6    0.04       0  5424.0    0.05       0
Bank Sta=5007.5,5011.5
Exp/Cntr=0.3,0.1

Type RM Length L Ch R = 1,8554,465,465,465
BEGIN DESCRIPTION:
Mapping XS 983ba8be
END DESCRIPTION:
XS GIS Cut Line= 3
      2519651.55     13534214.46      2519168.89     13534412.38
      2518693.23     13534679.72
#Sta/Elev= 30
  4437.9  221.24  4508.4  218.15  4596.3  213.02  4611.6  212.83  4635.6  211.07
  4694.3  208.84  4704.4  208.92  4766.3  205.79  4771.7  206.07  4790.3  204.99
  4849.1  203.82  4879.2  202.54  4909.7  202.55  4926.4  201.75  4987.0  202.17
  4997.8  201.35  4998.1  200.85  5001.6  200.85  5001.8  201.35  5009.9  201.36
  5015.4  202.58  5215.3  209.76  5237.0  211.12  5280.4  212.40  5286.1  213.19
  5318.0  213.79  5352.6  215.54  5399.0  216.54  5485.7  219.61  5505.2  219.77
#Mann=7,-1,0
  4437.9    0.12       0  4508.4    0.04       0  4879.2    0.05       0
  4997.8    0.05       0  5001.8    0.05       0  5015.4    0.04       0
  5352.6    0.12       0
Bank Sta=4997.8,5001.8
Exp/Cntr=0.3,0.1

Type RM Length L Ch R = 1,8089,512,512,512
BEGIN DESCRIPTION:
Mapping XS 3768307d
END DESCRIPTION:
XS GIS Cut Line= 3
      2519672.33     13533992.24      2519165.42     13533999.19
      2518595.97     13534138.08
#Sta/Elev= 30
  4313.9  222.04  4351.2  220.14  4401.2  218.42  4461.2  215.43  4481.2  214.75
  4491.3  214.88  4521.3  212.86  4591.3  210.62  4631.3  208.56  4681.3  207.00
  4701.3  205.66  4789.0  203.61  4840.8  202.23  4861.9  201.47  4867.1  201.73
  4887.1  201.21  4924.0  200.77  4990.1  199.55  4990.4  199.05  4993.9  199.05
  4994.1  199.55  5088.9  201.61  5109.5  201.54  5158.9  203.68  5171.3  203.66
  5283.9  207.64  5330.8  208.55  5336.0  209.36  5356.5  209.39  5407.0  210.55
#Mann=8,-1,0
  4313.9    0.05       0  4491.3    0.04       0  4789.0   0.013       0
  4840.8    0.04       0  4887.1    0.05       0  4924.0    0.04       0
  4990.1    0.04       0  4994.1    0.04       0
Bank Sta=4990.1,4994.1
Exp/Cntr=0.3,0.1

Type RM Length L Ch R = 1,7577,447,447,447
BEGIN DESCRIPTION:
TRIB 1 TO FIVEMILE CREEK 16.0
END DESCRIPTION:
XS GIS Cut Line= 3
      2519574.99     13533625.00      2519025.00     13533525.00
      2518575.03     13533824.98
#Sta/Elev= 30
  4333.2  221.56  4353.2  220.17  4384.0  218.89  4445.0  214.66  4455.2  214.78
  4471.7  212.86  4525.0  209.87  4536.5  209.87  4544.8  208.91  4556.8  207.79
  4607.6  206.22  4617.8  205.21  4648.3  204.54  4722.0  201.04  4801.3  199.67
  4807.1  198.98  4865.5  198.24  4950.8  198.77  4978.0  198.09  4984.9  198.07
  4985.1  197.57  4988.6  197.57  4988.9  198.07  5059.0  199.64  5144.6  202.57
  5188.2  203.49  5194.2  203.06  5260.3  205.24  5317.4  205.83  5433.0  209.55
#Mann=8,-1,0
  4333.2    0.05       0  4353.2    0.12       0  4544.8    0.04       0
  4722.0    0.05       0  4801.3    0.12       0  4978.0    0.04       0
  4984.9    0.04       0  4988.9    0.04       0
Bank Sta=4984.9,4988.9
Exp/Cntr=0.3,0.1

Type RM Length L Ch R = 1,7130,275,275,275
BEGIN DESCRIPTION:
Mapping XS 596b6d1e
END DESCRIPTION:
XS GIS Cut Line= 3
      2519686.27     13533433.22      2519290.42     13533200.58
      2518609.90     13533106.83
#Sta/Elev= 30
  4222.4  221.02  4325.0  218.16  4389.4  214.59  4420.7  213.20  4426.5  213.44
  4432.7  212.59  4469.9  210.95  4565.2  207.68  4602.3  204.96  4639.4  203.09
  4750.0  198.83  4876.8  194.60  4877.1  194.10  4880.6  194.10  4880.8  194.60
  4899.0  196.22  4919.2  196.61  4969.7  197.05  4981.8  196.66  4989.9  195.32
  4999.9  195.44  5010.0  196.45  5053.8  196.84  5116.0  198.54  5181.6  200.50
  5222.0  202.47  5274.8  203.86  5302.8  205.55  5323.0  205.38  5368.5  206.57
#Mann=6,-1,0
  4222.4    0.05       0  4469.9    0.04       0  4750.0    0.05       0
  4876.8    0.05       0  4880.8    0.05       0  5116.0    0.04       0
Bank Sta=4876.8,4880.8
Exp/Cntr=0.3,0.1

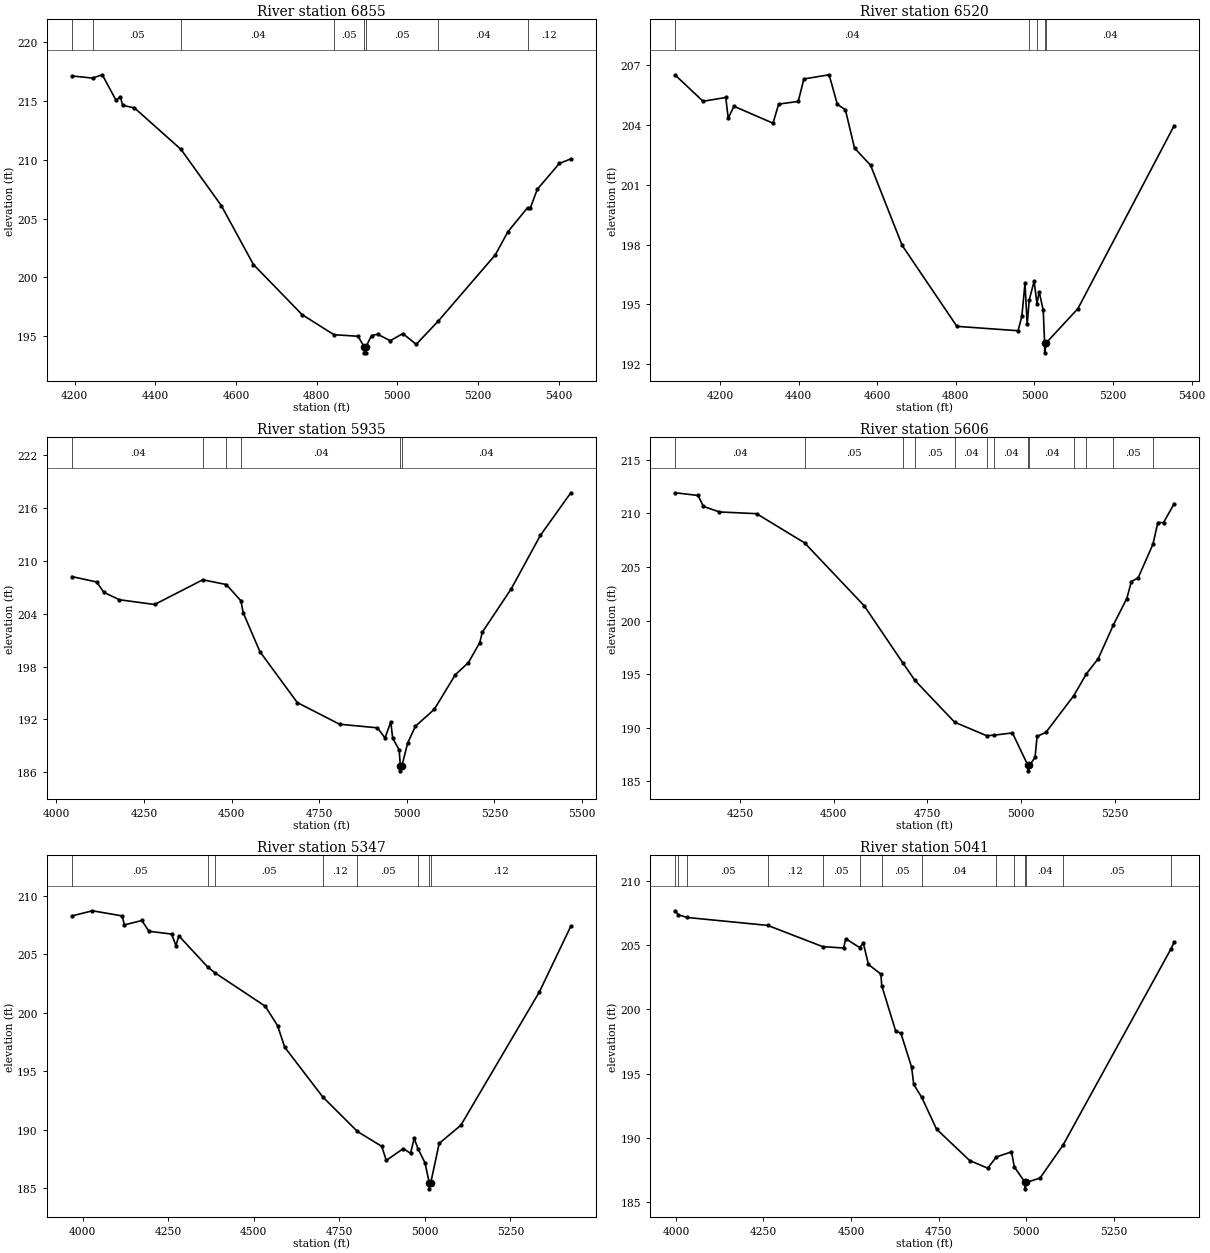
Type RM Length L Ch R = 1,6855,335,335,335
BEGIN DESCRIPTION:
Mapping XS e903d0ca
END DESCRIPTION:
XS GIS Cut Line= 3
      2519811.29     13533249.21      2519352.92     13533002.66
      2518665.38     13532801.26
#Sta/Elev= 30
  4193.3  217.13  4244.4  216.95  4268.6  217.23  4302.7  215.06  4313.3  215.36
  4319.0  214.63  4348.1  214.42  4463.9  210.88  4563.8  206.10  4643.3  201.10
  4763.9  196.84  4843.0  195.13  4902.7  195.00  4918.0  194.09  4918.3  193.59
  4921.8  193.59  4922.0  194.09  4936.2  195.06  4951.3  195.17  4982.5  194.62
  5013.8  195.23  5046.8  194.31  5101.3  196.28  5243.0  201.92  5274.3  203.89
  5323.0  205.93  5329.8  205.91  5347.2  207.50  5401.8  209.69  5430.2  210.08
#Mann=8,-1,0
  4193.3    0.04       0  4244.4    0.05       0  4463.9    0.04       0
  4843.0    0.05       0  4918.0    0.05       0  4922.0    0.05       0
  5101.3    0.04       0  5323.0    0.12       0
Bank Sta=4918,4922
Exp/Cntr=0.3,0.1

Type RM Length L Ch R = 1,6520,585,585,585
BEGIN DESCRIPTION:
Mapping XS bb8be3ca
END DESCRIPTION:
XS GIS Cut Line= 3
      2520005.73     13533103.38      2519675.83     13532842.94
      2518901.54     13532495.72
#Sta/Elev= 30
  4086.6  206.51  4157.1  205.20  4214.9  205.39  4221.2  204.35  4235.7  204.95
  4335.1  204.10  4349.5  205.06  4399.2  205.19  4413.6  206.32  4477.8  206.53
  4498.6  205.05  4519.2  204.77  4542.4  202.85  4583.2  201.99  4663.7  197.96
  4802.8  193.90  4958.3  193.68  4968.1  194.41  4976.0  196.08  4981.5  194.00
  4986.9  195.23  4999.2  196.17  5006.5  195.04  5012.0  195.64  5022.4  194.71
  5025.9  193.07  5026.1  192.57  5029.9  193.07  5110.6  194.79  5355.5  203.98
#Mann=5,-1,0
  4086.6    0.04       0  4986.9    0.05       0  5006.5    0.04       0
  5025.9    0.05       0  5029.9    0.04       0
Bank Sta=5025.9,5029.9
Exp/Cntr=0.3,0.1

Type RM Length L Ch R = 1,5935,329,329,329
BEGIN DESCRIPTION:
Mapping XS 3364b49e
END DESCRIPTION:
XS GIS Cut Line= 3
      2520328.58     13532610.28      2519960.56     13532342.94
      2519064.70     13531974.87
#Sta/Elev= 30
  4044.5  208.22  4115.0  207.61  4135.8  206.43  4179.9  205.59  4280.4  205.05
  4418.0  207.86  4484.9  207.32  4526.9  205.46  4532.9  204.14  4580.9  199.69
  4687.5  193.90  4808.1  191.44  4916.2  191.03  4937.8  189.88  4954.2  191.70
  4959.7  189.86  4978.2  188.51  4981.6  186.64  4981.9  186.14  4985.6  186.64
  5002.2  189.27  5024.3  191.20  5078.4  193.13  5138.2  197.06  5175.7  198.44
  5208.1  200.72  5215.5  201.91  5298.3  206.86  5381.1  212.91  5467.9  217.75
#Mann=6,-1,0
  4044.5    0.04       0  4418.0    0.12       0  4484.9    0.05       0
  4526.9    0.04       0  4981.6    0.04       0  4985.6    0.04       0
Bank Sta=4981.6,4985.6
Exp/Cntr=0.3,0.1

Type RM Length L Ch R = 1,5606,259,259,259
BEGIN DESCRIPTION:
Mapping XS 3f875ede
END DESCRIPTION:
XS GIS Cut Line= 3
      2520457.08     13532398.49      2520095.97     13532092.94
      2519308.91     13531753.15
#Sta/Elev= 30
  4077.9  211.92  4138.5  211.67  4152.8  210.65  4195.7  210.13  4294.5  209.97
  4422.5  207.25  4581.4  201.38  4683.9  196.08  4716.8  194.41  4822.7  190.51
  4908.1  189.25  4928.5  189.30  4976.8  189.51  5018.3  186.47  5018.6  185.97
  5022.3  186.47  5037.2  187.23  5042.6  189.19  5066.1  189.56  5140.1  192.97
  5174.2  195.03  5205.5  196.43  5245.9  199.58  5281.8  202.05  5294.0  203.64
  5312.1  203.98  5351.7  207.14  5364.6  209.14  5379.8  209.14  5408.2  210.91
#Mann=13,-1,0
  4077.9    0.04       0  4422.5    0.05       0  4683.9    0.12       0
  4716.8    0.05       0  4822.7    0.04       0  4908.1    0.05       0
  4928.5    0.04       0  5018.3    0.04       0  5022.3    0.04       0
  5140.1    0.05       0  5174.2    0.12       0  5245.9    0.05       0
  5351.7    0.04       0
Bank Sta=5018.3,5022.3
Exp/Cntr=0.3,0.1

Type RM Length L Ch R = 1,5347,306,306,306
BEGIN DESCRIPTION:
Mapping XS 0f2e9d08
END DESCRIPTION:
XS GIS Cut Line= 3
      2520727.92     13532214.47      2520113.33     13531804.74
      2519429.65     13531582.63
#Sta/Elev= 30
  3969.1  208.26  4029.0  208.70  4116.1  208.26  4122.1  207.49  4173.2  207.87
  4194.2  206.95  4260.3  206.71  4273.1  205.72  4281.4  206.56  4365.7  203.90
  4386.3  203.41  4533.7  200.55  4569.8  198.89  4590.8  197.04  4701.7  192.80
  4803.3  189.84  4874.2  188.57  4887.5  187.37  4937.3  188.38  4958.3  187.97
  4968.9  189.25  4980.5  188.35  5000.4  187.18  5013.3  185.44  5013.5  184.94
  5017.3  185.44  5042.0  188.82  5105.5  190.38  5334.8  201.77  5426.6  207.38
#Mann=8,-1,0
  3969.1    0.05       0  4365.7    0.12       0  4386.3    0.05       0
  4701.7    0.12       0  4803.3    0.05       0  4980.5    0.12       0
  5013.3    0.05       0  5017.3    0.12       0
Bank Sta=5013.3,5017.3
Exp/Cntr=0.3,0.1

Type RM Length L Ch R = 1,5041,302,302,302
BEGIN DESCRIPTION:
Mapping XS 836b2186
END DESCRIPTION:
XS GIS Cut Line= 3
      2520852.94     13531888.09      2520377.22     13531537.38
      2519558.84     13531377.87
#Sta/Elev= 30
  3998.3  207.67  4006.5  207.36  4031.9  207.15  4262.5  206.53  4418.9  204.88
  4478.9  204.77  4485.1  205.49  4524.7  204.81  4535.3  205.15  4549.9  203.49
  4585.4  202.74  4587.8  201.85  4627.6  198.31  4642.5  198.14  4673.1  195.50
  4679.2  194.15  4702.1  193.14  4744.4  190.67  4839.1  188.22  4890.7  187.63
  4915.0  188.50  4958.4  188.90  4966.5  187.73  4997.1  186.52  4997.3  186.02
  5001.2  186.52  5039.9  186.86  5105.3  189.41  5413.2  204.67  5423.1  205.23
#Mann=14,-1,0
  3998.3    0.12       0  4006.5    0.04       0  4031.9    0.05       0
  4262.5    0.12       0  4418.9    0.05       0  4524.7   0.013       0
  4587.8    0.05       0  4702.1    0.04       0  4915.0    0.05       0
  4966.5    0.04       0  4997.1    0.04       0  5001.2    0.04       0
  5105.3    0.05       0  5413.2    0.12       0
Bank Sta=4997.1,5001.2
Exp/Cntr=0.3,0.1

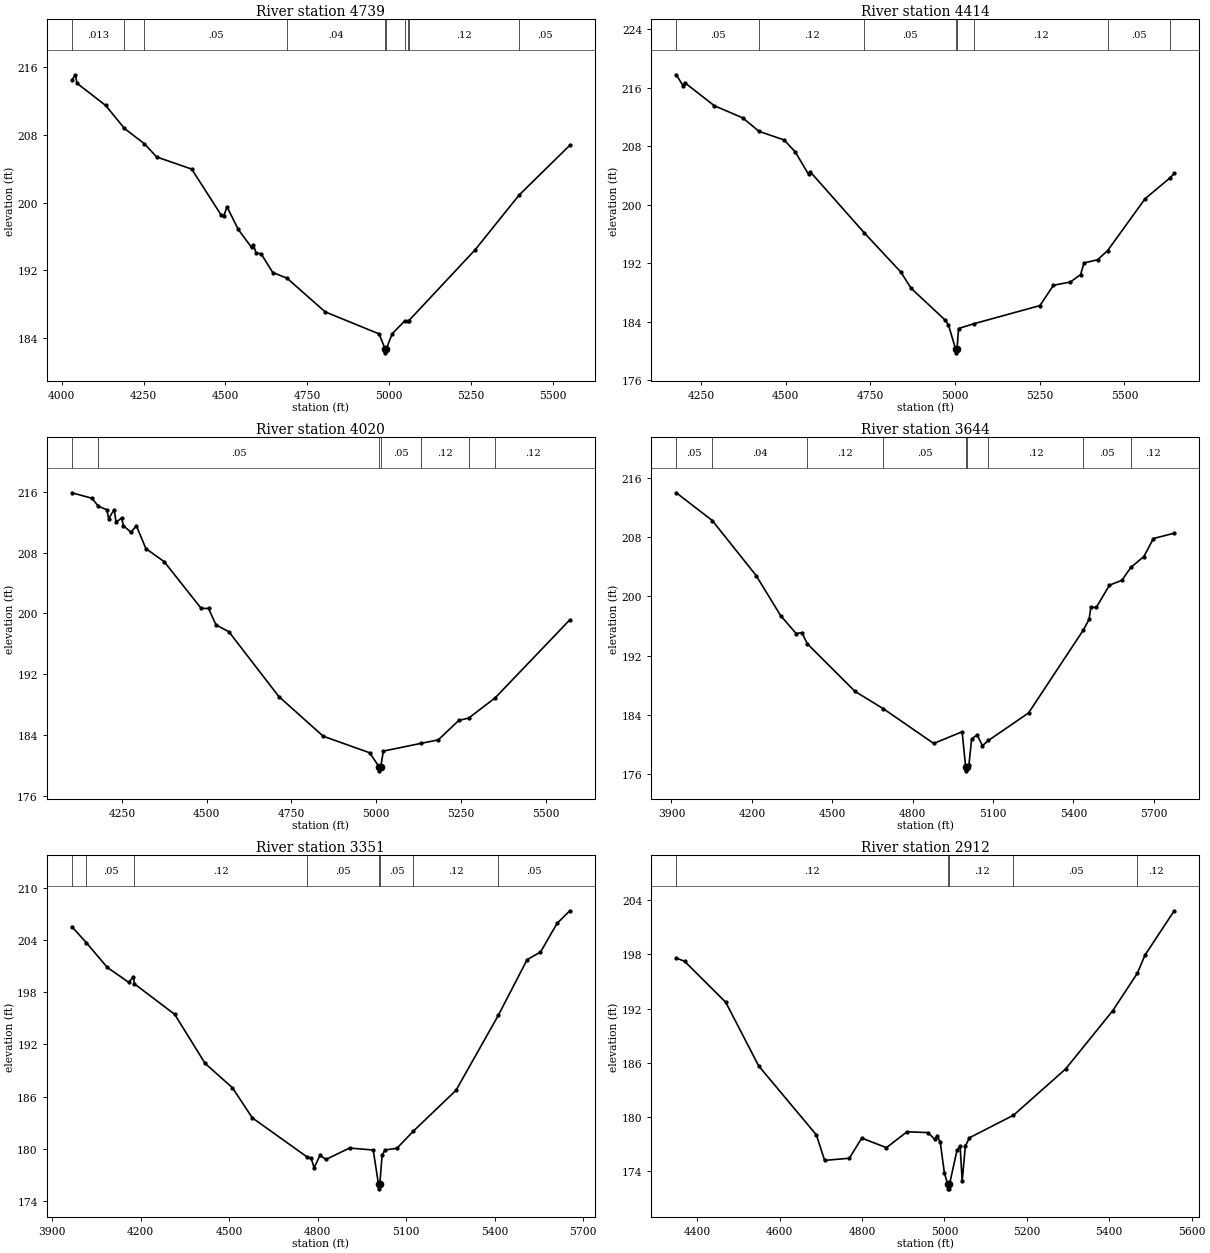
Type RM Length L Ch R = 1,4739,325,325,325
BEGIN DESCRIPTION:
Mapping XS 3c3a3c96
END DESCRIPTION:
XS GIS Cut Line= 3
      2520939.68     13531454.03      2520377.22     13531204.05
      2519474.46     13531124.19
#Sta/Elev= 30
  4030.8  214.50  4041.1  215.13  4046.9  214.11  4134.1  211.50  4191.4  208.78
  4252.3  206.97  4290.0  205.40  4397.1  203.96  4487.0  198.53  4495.5  198.44
  4504.8  199.51  4539.3  196.82  4580.0  194.69  4585.5  195.02  4594.0  194.00
  4608.7  193.96  4644.8  191.72  4688.3  191.05  4804.9  187.06  4969.8  184.45
  4987.8  182.71  4988.1  182.21  4991.9  182.71  5009.9  184.48  5048.1  185.98
  5057.1  185.99  5060.4  186.01  5262.8  194.39  5397.7  200.89  5552.6  206.78
#Mann=10,-1,0
  4030.8   0.013       0  4191.4    0.12       0  4252.3    0.05       0
  4688.3    0.04       0  4987.8    0.04       0  4991.9    0.04       0
  5048.1    0.12       0  5057.1    0.05       0  5060.4    0.12       0
  5397.7    0.05       0
Bank Sta=4987.8,4991.9
Exp/Cntr=0.3,0.1

Type RM Length L Ch R = 1,4414,394,394,394
BEGIN DESCRIPTION:
Mapping XS 7e453908
END DESCRIPTION:
XS GIS Cut Line= 3
      2520936.28     13530974.89      2520446.67     13530867.24
      2519478.92     13530905.40
#Sta/Elev= 30
  4177.2  217.80  4196.9  216.32  4202.0  216.73  4289.6  213.56  4373.0  211.91
  4421.7  210.05  4495.9  208.87  4528.8  207.21  4567.5  204.18  4572.6  204.52
  4732.7  196.13  4840.3  190.78  4870.3  188.57  4970.4  184.24  4980.4  183.59
  5001.8  180.23  5002.1  179.73  5005.9  180.23  5010.4  183.06  5055.3  183.71
  5250.6  186.20  5290.6  188.98  5340.7  189.43  5370.7  190.45  5380.7  192.04
  5420.7  192.47  5450.5  193.73  5560.9  200.82  5634.5  203.68  5647.0  204.29
#Mann=8,-1,0
  4177.2    0.05       0  4421.7    0.12       0  4732.7    0.05       0
  5001.8    0.05       0  5005.9    0.05       0  5055.3    0.12       0
  5450.5    0.05       0  5634.5    0.12       0
Bank Sta=5001.8,5005.9
Exp/Cntr=0.3,0.1

Type RM Length L Ch R = 1,4020,376,376,376
BEGIN DESCRIPTION:
Mapping XS 301ac2aa
END DESCRIPTION:
XS GIS Cut Line= 3
      2520957.11     13530790.87      2520502.22     13530544.33
      2519561.26     13530398.50
#Sta/Elev= 30
  4102.0  215.89  4161.2  215.17  4180.3  214.11  4204.9  213.66  4210.6  212.49
  4226.8  213.66  4232.5  212.03  4248.7  212.55  4254.3  211.55  4276.2  210.69
  4292.4  211.54  4320.5  208.53  4374.2  206.83  4483.5  200.67  4505.4  200.65
  4527.2  198.49  4565.3  197.59  4712.8  189.05  4843.9  183.82  4980.9  181.64
  5009.2  179.76  5009.4  179.26  5013.4  179.76  5021.4  181.86  5132.4  182.88
  5183.3  183.34  5244.0  185.90  5273.6  186.22  5351.9  188.90  5571.6  199.15
#Mann=7,-1,0
  4102.0    0.04       0  4180.3    0.05       0  5009.2    0.05       0
  5013.4    0.05       0  5132.4    0.12       0  5273.6    0.05       0
  5351.9    0.12       0
Bank Sta=5009.2,5013.4
Exp/Cntr=0.3,0.1

Type RM Length L Ch R = 1,3644,293,293,293
BEGIN DESCRIPTION:
Mapping XS b95b6d04
END DESCRIPTION:
XS GIS Cut Line= 4
      2521123.73     13530693.61      2520769.58     13530231.83
      2519773.06     13530082.52      2519512.68     13530148.48
#Sta/Elev= 30
  3918.0  214.00  4052.3  210.25  4216.2  202.81  4307.6  197.39  4365.7  194.97
  4386.5  195.11  4407.2  193.59  4585.5  187.15  4691.3  184.81  4878.7  180.13
  4984.8  181.71  4997.9  176.93  4998.2  176.43  5002.1  176.93  5010.2  177.27
  5020.3  180.76  5040.5  181.27  5060.7  179.83  5082.7  180.53  5232.6  184.25
  5436.8  195.44  5458.6  196.90  5465.2  198.53  5485.4  198.51  5534.7  201.52
  5580.9  202.17  5614.3  203.91  5662.8  205.38  5698.7  207.82  5776.2  208.54
#Mann=9,-1,0
  3918.0    0.05       0  4052.3    0.04       0  4407.2    0.12       0
  4691.3    0.05       0  4997.9    0.05       0  5002.1    0.05       0
  5082.7    0.12       0  5436.8    0.05       0  5614.3    0.12       0
Bank Sta=4997.9,5002.1
Exp/Cntr=0.3,0.1

Type RM Length L Ch R = 1,3351,439,439,439
BEGIN DESCRIPTION:
Mapping XS 0c672cce
END DESCRIPTION:
XS GIS Cut Line= 4
      2521280.02     13530242.25      2520755.70     13529950.58
      2519866.81     13529884.60      2519672.32     13529915.86
#Sta/Elev= 30
  3966.6  205.54  4015.6  203.69  4086.8  200.85  4158.8  199.15  4174.8  199.73
  4178.8  198.96  4315.4  195.45  4418.3  189.82  4511.0  187.02  4578.4  183.56
  4764.8  179.05  4777.9  178.93  4787.9  177.82  4807.9  179.26  4828.0  178.78
  4908.2  180.09  4988.4  179.86  5006.3  175.90  5006.6  175.40  5010.6  175.90
  5018.5  179.26  5028.6  179.87  5068.7  180.06  5123.9  182.01  5269.2  186.73
  5412.3  195.33  5510.4  201.75  5555.5  202.61  5611.7  205.91  5654.9  207.36
#Mann=8,-1,0
  3966.6    0.04       0  4015.6    0.05       0  4178.8    0.12       0
  4764.8    0.05       0  5006.3    0.05       0  5010.6    0.05       0
  5123.9    0.12       0  5412.3    0.05       0
Bank Sta=5006.3,5010.6
Exp/Cntr=0.3,0.1

Type RM Length L Ch R = 1,2912,438,438,438
BEGIN DESCRIPTION:
TRIB 1 TO FIVEMILE CREEK 6.0
END DESCRIPTION:
XS GIS Cut Line= 3
      2521025.00     13529525.00      2520425.00     13529525.00
      2519824.98     13529625.00
#Sta/Elev= 30
  4349.4  197.60  4369.4  197.25  4469.4  192.71  4549.4  185.66  4689.4  178.02
  4709.4  175.20  4769.4  175.44  4799.4  177.67  4859.4  176.61  4909.4  178.37
  4959.5  178.28  4977.3  177.53  4982.3  177.95  4990.0  177.19  5000.1  173.79
  5008.1  172.55  5008.4  172.05  5012.1  172.05  5012.4  172.55  5030.5  176.30
  5038.1  176.82  5043.2  172.90  5050.8  176.77  5060.9  177.71  5167.7  180.20
  5294.1  185.32  5408.1  191.75  5468.1  195.91  5486.7  197.92  5557.7  202.84
#Mann=5,-1,0
  4349.4    0.12       0  5008.1    0.05       0  5012.4    0.12       0
  5167.7    0.05       0  5468.1    0.12       0
Bank Sta=5008.1,5012.4
Exp/Cntr=0.3,0.1

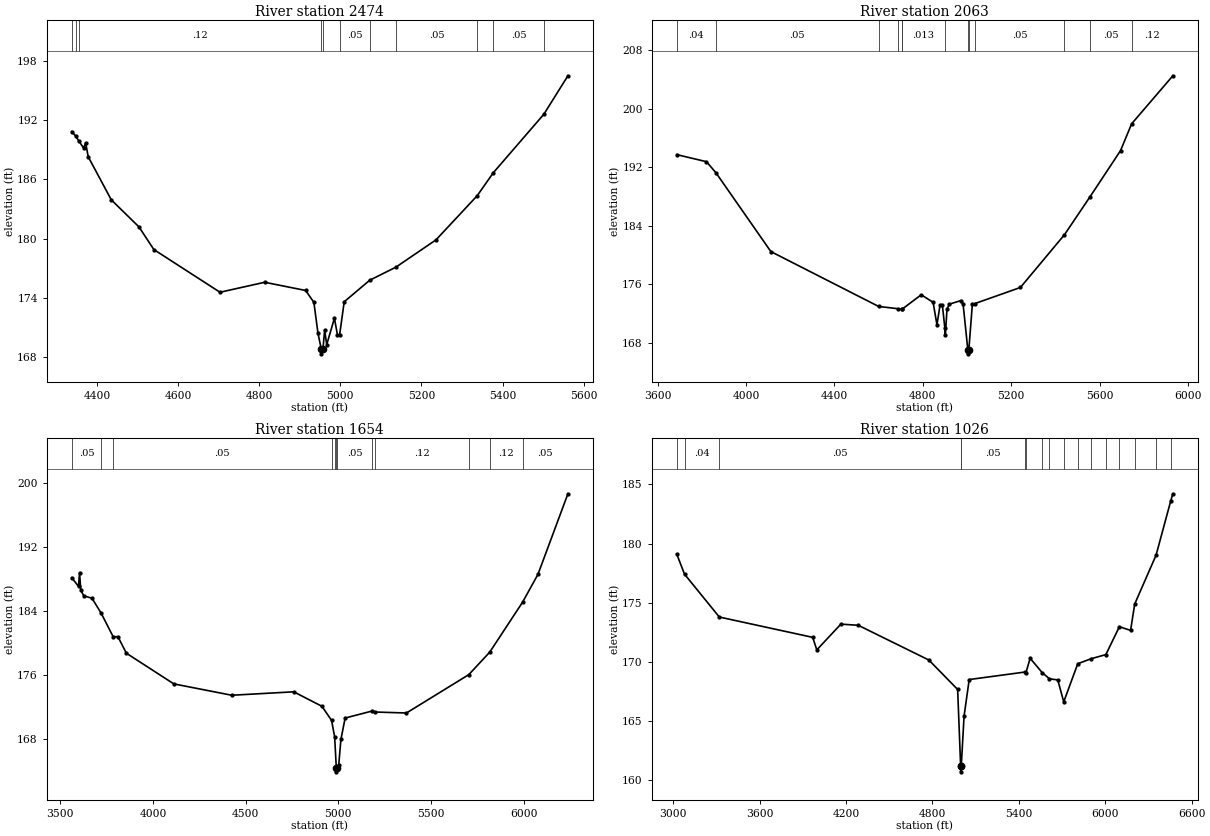
Type RM Length L Ch R = 1,2474,411,411,411
BEGIN DESCRIPTION:
TRIB 1 TO FIVEMILE CREEK 5.0
END DESCRIPTION:
XS GIS Cut Line= 3
      2520925.04     13529225.01      2520275.00     13529125.00
      2519874.98     13529525.02
#Sta/Elev= 30
  4337.8  190.84  4347.3  190.38  4355.5  189.87  4366.9  189.17  4372.0  189.69
  4378.3  188.29  4435.2  183.93  4503.5  181.19  4540.2  178.90  4703.3  174.58
  4813.4  175.59  4914.5  174.76  4934.8  173.56  4944.9  170.43  4952.9  168.85
  4953.2  168.35  4957.2  168.85  4961.3  170.73  4966.4  169.28  4985.4  171.95
  4993.0  170.26  4998.2  170.26  5009.6  173.62  5072.6  175.80  5137.1  177.12
  5235.9  179.88  5337.6  184.35  5377.4  186.68  5501.9  192.59  5561.2  196.48
#Mann=11,-1,0
  4337.8    0.12       0  4347.3   0.013       0  4355.5    0.12       0
  4952.9    0.05       0  4957.2    0.12       0  4998.2    0.05       0
  5072.6    0.12       0  5137.1    0.05       0  5337.6    0.12       0
  5377.4    0.05       0  5501.9    0.12       0
Bank Sta=4952.9,4957.2
Exp/Cntr=0.3,0.1

Type RM Length L Ch R = 1,2063,409,409,409
BEGIN DESCRIPTION:
Mapping XS 0f2c17f9
END DESCRIPTION:
XS GIS Cut Line= 4
      2521283.50     13529068.64      2520339.03     13528710.99
      2519811.25     13528870.72      2519533.47     13529495.73
#Sta/Elev= 30
  3686.2  193.72  3820.9  192.75  3863.9  191.23  4112.3  180.47  4599.6  172.98
  4685.7  172.67  4703.6  172.57  4704.9  172.57  4792.7  174.57  4846.6  173.54
  4863.8  170.48  4877.9  173.13  4888.4  173.17  4899.4  170.08  4901.9  169.01
  4909.3  172.59  4919.7  173.29  4973.0  173.78  4982.4  173.25  5003.8  167.00
  5004.1  166.50  5008.1  167.00  5024.2  173.31  5035.0  173.36  5241.7  175.57
  5441.1  182.78  5557.3  187.99  5694.6  194.26  5745.0  197.93  5931.5  204.49
#Mann=13,-1,0
  3686.2    0.04       0  3863.9    0.05       0  4599.6   0.013       0
  4685.7    0.05       0  4703.6    0.12       0  4704.9   0.013       0
  4899.4    0.12       0  5003.8    0.05       0  5008.1    0.12       0
  5035.0    0.05       0  5441.1    0.12       0  5557.3    0.05       0
  5745.0    0.12       0
Bank Sta=5003.8,5008.1
Exp/Cntr=0.3,0.1

Type RM Length L Ch R = 1,1654,628,628,628
BEGIN DESCRIPTION:
Mapping XS 8632ad5d
END DESCRIPTION:
XS GIS Cut Line= 4
      2521318.21     13528808.22      2520293.89     13528301.27
      2519686.25     13528585.99      2519345.99     13529377.62
#Sta/Elev= 30
  3562.4  188.20  3598.7  187.11  3604.3  188.84  3610.6  186.70  3626.7  185.94
  3671.5  185.63  3720.7  183.77  3785.1  180.84  3811.7  180.81  3856.6  178.76
  4112.7  174.92  4425.1  173.50  4759.3  173.93  4911.4  172.12  4963.5  170.35
  4979.9  168.31  4989.0  164.42  4989.3  163.92  4993.5  164.42  5002.2  164.83
  5013.8  167.97  5036.6  170.65  5182.6  171.53  5200.0  171.40  5367.2  171.28
  5703.6  176.08  5816.4  178.89  5993.5  185.14  6076.6  188.63  6238.0  198.70
#Mann=12,-1,0
  3562.4    0.05       0  3720.7   0.013       0  3785.1    0.05       0
  4963.5    0.12       0  4979.9    0.05       0  4989.0    0.05       0
  4993.5    0.05       0  5182.6   0.013       0  5200.0    0.12       0
  5703.6    0.05       0  5816.4    0.12       0  5993.5    0.05       0
Bank Sta=4989,4993.5
Exp/Cntr=0.3,0.1

Type RM Length L Ch R = 1,1026,0,0,0
BEGIN DESCRIPTION:
Mapping XS 8632ad5daa
END DESCRIPTION:
XS GIS Cut Line= 4
      2521476.26     13528251.12      2520139.75     13527645.73
      2519241.01     13528274.38      2519371.40     13529145.17
#Sta/Elev= 30
  3025.0  179.11  3079.0  177.41  3320.7  173.78  3969.0  172.06  3997.5  171.00
  4164.7  173.18  4285.7  173.08  4775.7  170.14  4975.4  167.65  4996.1  161.18
  4996.4  160.68  5000.6  161.18  5019.9  165.39  5055.6  168.49  5439.7  169.12
  5448.4  169.01  5478.5  170.29  5562.1  169.08  5612.9  168.55  5670.5  168.46
  5711.9  166.60  5809.4  169.83  5904.3  170.26  6004.4  170.60  6098.2  172.96
  6176.1  172.65  6204.6  174.88  6352.9  179.01  6454.7  183.60  6469.5  184.21
#Mann=17,-1,0
  3025.0   0.013       0  3079.0    0.04       0  3320.7    0.05       0
  4996.1    0.05       0  5000.6    0.05       0  5439.7   0.013       0
  5448.4    0.05       0  5562.1    0.12       0  5612.9    0.05       0
  5711.9    0.12       0  5809.4    0.05       0  5904.3    0.12       0
  6004.4    0.05       0  6098.2    0.12       0  6204.6    0.05       0
  6352.9    0.12       0  6454.7    0.05       0
Bank Sta=4996.1,5000.6
Exp/Cntr=0.3,0.1

Chan Stop Cuts=-1