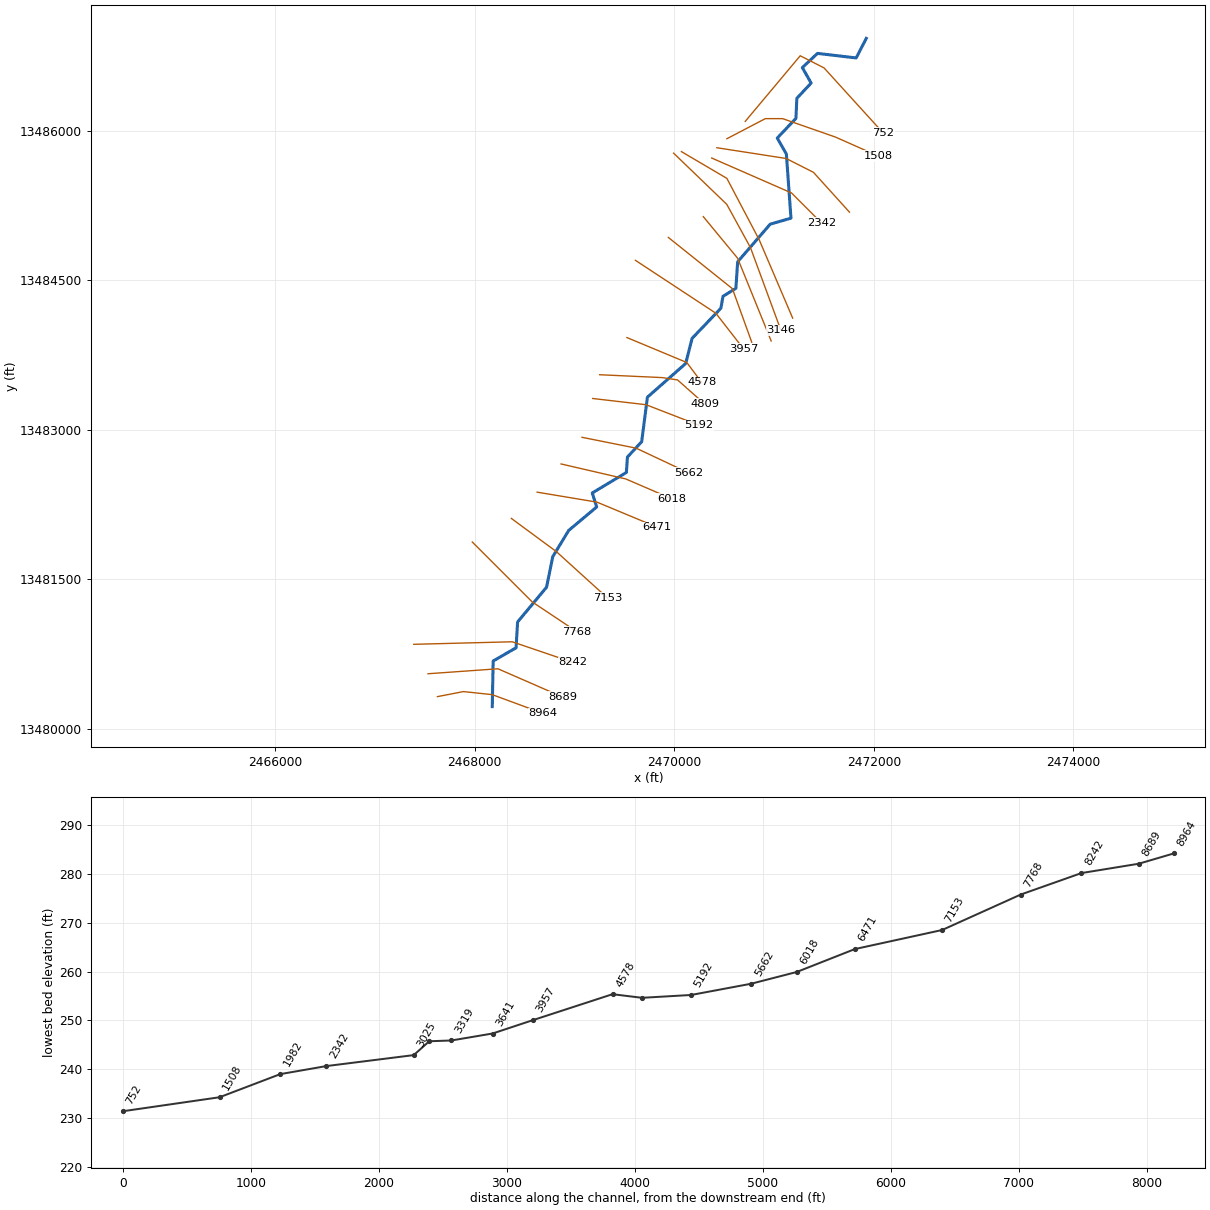
--- TRIB 1 TO HOG CREEK.prj (project) ---

Proj Title=TRIB 1 TO HOG CREEK Base Level Engineering
Current Plan=p01
Default Exp/Contr=0.3,0.1
English Units
Geom File=g01
Flow File=f01
Plan File=p01
Y Axis Title=Elevation
X Axis Title(PF)=Main Channel Distance
X Axis Title(XS)=Station
BEGIN DESCRIPTION:
TRIB 1 TO HOG CREEK
END DESCRIPTION:
DSS Export Rating Curves= 0
DSS Export Rating Curve Sorted= 0
DSS Export Volume Flow Curves= 0
DXF OffsetX= 0
DXF OffsetY= 0
DXF ScaleX= 1
DXF ScaleY= 10

--- TRIB 1 TO HOG CREEK.p01 (plan) ---

Plan Title=Multiple Run
Program Version=4.10
Short Identifier=Multiple
Geom File=g01
Flow File=f01
Subcritical Flow
K Sum by GR= 0
Std Step Tol= 0.01
Critical Tol= 0.01
Num of Std Step Trials= 20
Max Error Tol= 0.3
Flow Tol Ratio= 0.001
Split Flow NTrial= 30
Split Flow Tol= 0.02
Split Flow Ratio= 0.02
Log Output Level= 0
Friction Slope Method= 1
Unsteady Friction Slope Method= 2
Unsteady Bridges Friction Slope Method= 1
Parabolic Critical Depth
Global Vel Dist= 1 , 1 , 1
Global Log Level= 0
CheckData=True
Encroach Param=-1 ,0,0, 0
BEGIN DESCRIPTION:
Multiple Run
END DESCRIPTION:
Computation Interval=1HOUR
Output Interval=1HOUR
Run HTab= 0
Run UNet= 0
Run PostProcess= 0
Run WQNet= 0
UNET Theta= 1
UNET Theta Warmup= 1
UNET ZTol= 0.02
UNET ZSATol= 0.05
UNET MxIter= 20
UNET MaxInSteps= 0
UNET DtIC= 0
UNET DtMin= 0
UNET MaxCRTS= 20
UNET WFStab= 2
UNET SFStab= 1
UNET WFX= 1
UNET SFX= 1
UNET DSS MLevel= 4
UNET DZMax Abort= 100
UNET Convert EG Bridges= 0
UNET Use Existing IB Tables=-1
UNET Froude Reduction=False
UNET Froude Limit= 1
UNET Froude Power= 10
UNET Time Slicing=0,0, 5
UNET Junction Losses=0
Instantaneous Interval=1HOUR
Write IC File= 0
Write IC File at Sim End=0
Echo Input=False
Echo Parameters=False
Echo Output=False
Write Detailed= 0
WQ AD Non Conservative
WQ ULTIMATE=-1
WQ Max Comp Step=1HOUR
WQ Output Interval=15MIN
WQ Output Selected Increments= 0
WQ Output face flow=0
WQ Output face velocity=0
WQ Output face area=0
WQ Output face dispersion=0
WQ Output cell volume=0
WQ Output cell surface area=0
WQ Output cell continuity=0
WQ Output cumulative cell continuity=0
WQ Output face conc=0
WQ Output face dconc_dx=0
WQ Output face courant=0
WQ Output face peclet=0
WQ Output face adv mass=0
WQ Output face disp mass=0
WQ Output cell mass=0
WQ Output cell source sink temp=0
WQ Output cell source sink nsm=0
WQ Output MaxMinRange=-1
WQ Daily Max Min Mean=-1
WQ Daily Range=0
WQ Daily Time=0
WQ Create Restart=0
WQ Fixed Restart=0
WQ System Summary=0
WQ Use Fixed Temperature=0
Sorting and Armoring Iterations= 10
XS Update Threshold= 0.02
Hydraulics Update Threshold= 0.02
Energy Slope Method= 1
Volume Change Method= 0
XS Weighting Method= 0
Number of US Weighted Cross Sections= 1
Number of DS Weighted Cross Sections= 1
Upstream XS Weight=0.25
Main XS Weight=0.5
Downstream XS Weight=0.25
Number of DS XS's Weighted with US Boundary= 1
Upstream Boundary Weight= 1
Weight of XSs Associated with US Boundary= 0
Number of US XS's Weighted with DS Boundary= 1
Downstream Boundary Weight= 0.5
Weight of XSs Associated with DS Boundary= 0.5
Sediment Output Level= 4
Mass or Volume Output= 0
Output Increment Type= 1
Profile and TS Output Increment= 10
XS Output Flag= 0
XS Output Increment= 10
Disregard all LS=0
Disregard all Conn=0
Disregard all Breaches=0
Disregard all Pumps=0

--- TRIB 1 TO HOG CREEK.f01 (steady flow) ---

Flow Title=Multiple
Number of Profiles=7
Profile Names=10-year,25-year,50-year,1pct_min,100-year,1pct_plu,500-year
River Rch & RM= TRIB 1 TO HOG CR,Reach-1,8964
     513     816    1085     699    1395    2784    2282
River Rch & RM= TRIB 1 TO HOG CR,Reach-1,4809
     916    1506    2047    1345    2684    5355    4568
Boundary for River Rch & Prof#=TRIB 1 TO HOG CR,Reach-1,1
Up Type=0
Dn Type=3
Dn Slope=0.005
Boundary for River Rch & Prof#=TRIB 1 TO HOG CR,Reach-1,2
Up Type=0
Dn Type=3
Dn Slope=0.005
Boundary for River Rch & Prof#=TRIB 1 TO HOG CR,Reach-1,3
Up Type=0
Dn Type=3
Dn Slope=0.005
Boundary for River Rch & Prof#=TRIB 1 TO HOG CR,Reach-1,4
Up Type=0
Dn Type=3
Dn Slope=0.005
Boundary for River Rch & Prof#=TRIB 1 TO HOG CR,Reach-1,5
Up Type=0
Dn Type=3
Dn Slope=0.005
Boundary for River Rch & Prof#=TRIB 1 TO HOG CR,Reach-1,6
Up Type=0
Dn Type=3
Dn Slope=0.005
Boundary for River Rch & Prof#=TRIB 1 TO HOG CR,Reach-1,7
Up Type=0
Dn Type=3
Dn Slope=0.005

--- TRIB 1 TO HOG CREEK.g01 (geometry) ---

Geom Title=Existing Conditions
Program Version=4.10

River Reach=TRIB 1 TO HOG CR,Reach-1
Reach XY= 30
        2468175.       13480225.      2468184.01     13480682.06
       2468413.9     13480814.92      2468428.82     13481073.42
      2468719.48     13481422.57      2468780.82     13481727.28
      2468941.64     13481991.68      2469221.87     13482226.63
       2469177.5     13482366.85      2469519.54     13482572.54
      2469530.47     13482727.45      2469672.94     13482880.85
      2469730.47     13483327.45      2470114.48     13483665.21
      2470178.16     13483916.66      2470467.14     13484218.83
      2470488.26     13484338.65      2470617.31     13484418.52
      2470635.48      13484684.8      2470961.33     13485061.77
      2471169.66     13485122.26       2471123.8      13485764.5
      2471032.23     13485925.29      2471219.53     13486122.55
      2471228.54     13486323.54       2471371.9     13486476.65
      2471283.96     13486631.67      2471435.44     13486773.96
      2471823.55     13486728.53        2471925.       13486925.

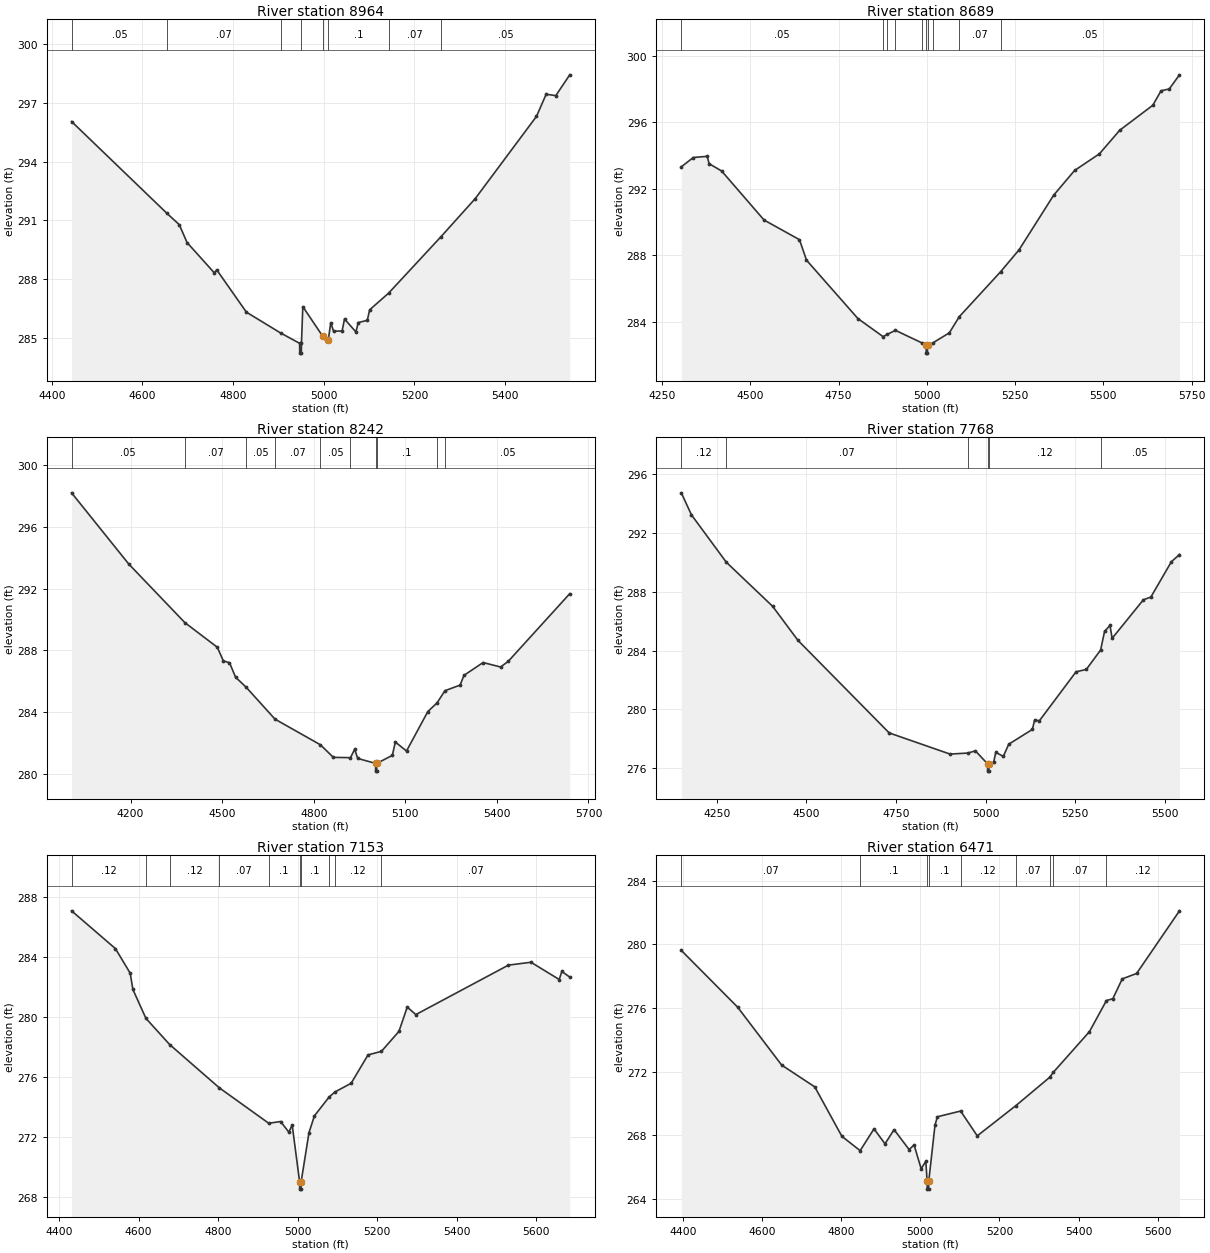
Type RM Length L Ch R = 1 ,8964    ,275,275,275
BEGIN DESCRIPTION:
TRIB 1 TO HOG CREK 17.0
END DESCRIPTION:
XS GIS Cut Line= 4
      2467624.97     13480324.99      2467885.84     13480375.73
      2468174.85     13480344.98      2468683.82     13480157.22
#Sta/Elev= 30
  4443.6  296.04  4654.3  291.35  4681.2  290.78  4698.3  289.87  4758.6  288.32
  4763.7  288.48  4829.2  286.32  4904.5  285.26  4946.7  284.73  4946.9  284.23
  4950.4  284.23  4950.7  284.73  4953.7   286.6  4997.6  285.09  5009.9   284.9
  5015.3  285.78  5021.5  285.35  5040.4  285.36  5045.7  285.97  5070.8  285.31
  5076.1  285.79  5095.9   285.9  5101.2  286.44    5143  287.29  5258.6  290.17
  5334.1  292.11  5469.1   296.3  5490.5  297.43  5511.8  297.36  5542.5  298.42
#Mann= 8 ,-1 , 0
  4443.6     .05       0  4654.3     .07       0  4904.5      .1       0
  4950.7      .1       0  4997.6     .05       0  5009.9      .1       0
    5143     .07       0  5258.6     .05       0
Bank Sta=4997.6,5009.9
XS Rating Curve= 0 ,0
Exp/Cntr=0.3,0.1

Type RM Length L Ch R = 1 ,8689    ,447,447,447
BEGIN DESCRIPTION:
Mapping XS 4b2a2871
END DESCRIPTION:
XS GIS Cut Line= 3
      2467531.05     13480554.46      2468232.02     13480604.38
      2468881.55     13480320.75
#Sta/Elev= 30
  4304.1  293.31  4338.1  293.87  4377.6  293.94  4382.7   293.5  4418.3  293.06
  4538.6  290.11  4638.9  288.93  4658.8   287.7  4804.4  284.19  4875.9   283.1
  4886.8  283.23  4910.8  283.48  4985.3  282.73  4997.8  282.61  4998.1  282.11
  5001.6  282.11  5001.8  282.61  5016.4  282.72  5063.5  283.33  5091.7   284.3
  5209.1  287.01  5261.1  288.32  5359.3  291.61  5418.4  293.09  5488.7  294.09
  5546.4  295.51    5640  297.01  5663.4  297.88  5686.6  297.99  5715.6  298.84
#Mann= 10 ,-1 , 0
  4304.1     .05       0  4875.9     .07       0  4886.8      .1       0
  4910.8     .05       0  4985.3      .1       0  4997.8     .05       0
  5001.8      .1       0  5016.4     .05       0  5091.7     .07       0
  5209.1     .05       0
Bank Sta=4997.8,5001.8
XS Rating Curve= 0 ,0
Exp/Cntr=0.3,0.1

Type RM Length L Ch R = 1 ,8242    ,474,474,474
BEGIN DESCRIPTION:
TRIB 1 TO HOG CREK 16.0
END DESCRIPTION:
XS GIS Cut Line= 3
      2467387.86      13480849.6        2468375.       13480875.
      2468985.05     13480667.32
#Sta/Elev= 30
  4006.8  298.19    4194  293.59  4377.9   289.8  4484.1  288.21  4504.1  287.32
  4524.1  287.21  4544.1  286.27  4578.9  285.62  4673.2  283.56  4822.2   281.9
  4864.2  281.09  4920.4  281.07  4934.2  281.61  4944.2  281.02  5002.7   280.7
  5002.9   280.2  5006.4   280.2  5006.7   280.7  5057.6  281.22  5067.4  282.08
    5104   281.5  5173.8  284.05  5204.4  284.62    5230   285.4  5279.5  285.76
  5292.2  286.39  5354.9  287.22  5412.3  286.93  5437.9  287.31  5638.7  291.67
#Mann= 10 ,-1 , 0
  4006.8     .05       0  4377.9     .07       0  4578.9     .05       0
  4673.2     .07       0  4822.2     .05       0  4920.4      .1       0
  5002.7     .05       0  5006.7      .1       0  5204.4     .07       0
    5230     .05       0
Bank Sta=5002.7,5006.7
XS Rating Curve= 0 ,0
Exp/Cntr=0.3,0.1

Type RM Length L Ch R = 1 ,7768    ,615,615,615
BEGIN DESCRIPTION:
TRIB 1 TO HOG CREK 15.0
END DESCRIPTION:
XS GIS Cut Line= 3
        2467975.       13481875.        2468575.       13481275.
      2469025.04     13480974.98
#Sta/Elev= 30
  4151.5  294.74  4179.8  293.24  4276.9  290.02  4406.1  287.02  4476.8   284.7
  4731.3   278.4    4901  276.96  4950.6  277.03  4971.7  277.18  5005.5   276.3
  5005.8   275.8  5009.3   275.8  5009.5   276.3  5022.6  276.41  5028.6  277.08
  5049.6   276.8  5064.6  277.63  5130.7  278.64  5136.7  279.26  5150.3  279.23
  5252.4  282.56    5281  282.72  5320.9  284.04    5332  285.31  5347.1  285.72
  5353.1  284.84  5440.2  287.46  5461.2  287.65  5518.3  290.05  5540.9  290.54
#Mann= 6 ,-1 , 0
  4151.5     .12       0  4276.9     .07       0  4950.6     .12       0
  5005.5     .05       0  5009.5     .12       0  5320.9     .05       0
Bank Sta=5005.5,5009.5
XS Rating Curve= 0 ,0
Exp/Cntr=0.3,0.1

Type RM Length L Ch R = 1 ,7153    ,682,682,682
BEGIN DESCRIPTION:
Mapping XS 49790a52
END DESCRIPTION:
XS GIS Cut Line= 3
      2468366.18     13482111.82       2468817.3     13481779.41
      2469330.83     13481313.28
#Sta/Elev= 30
  4431.1  287.08  4541.5  284.56  4578.7  282.92  4585.4  281.84  4618.2  279.91
  4678.1  278.16  4802.8  275.28  4927.5  272.91  4957.2  273.03    4978  272.32
  4986.4   272.8    5005  269.02  5005.3  268.52  5008.8  268.52    5009  269.02
  5028.7  272.29  5042.4  273.41  5079.3  274.66  5094.1     275  5134.8  275.58
  5177.3  277.47  5211.1  277.71  5255.1  279.04    5276  280.66  5297.6  280.16
  5530.8  283.46  5587.5  283.65  5658.5   282.5  5665.2  283.04    5685  282.66
#Mann= 10 ,-1 , 0
  4431.1     .12       0  4618.2     .07       0  4678.1     .12       0
  4802.8     .07       0  4927.5      .1       0    5005     .05       0
    5009      .1       0  5079.3     .07       0  5094.1     .12       0
  5211.1     .07       0
Bank Sta=5005,5009
XS Rating Curve= 0 ,0
Exp/Cntr=0.3,0.1

Type RM Length L Ch R = 1 ,6471    ,453,453,453
BEGIN DESCRIPTION:
TRIB 1 TO HOG CREK 12.0
END DESCRIPTION:
XS GIS Cut Line= 3
      2468624.95     13482375.01        2469225.       13482275.
      2469824.98     13482025.01
#Sta/Elev= 30
  4396.4  279.62  4538.4  276.06  4649.9  272.41  4733.5  271.04    4802  267.93
  4848.1  267.03  4883.1   268.4  4910.9  267.46  4933.8  268.35  4971.8   267.1
  4984.4  267.39  5002.2  265.89  5013.9  266.36  5017.4  265.11  5017.6  264.61
  5021.1  264.61  5021.4  265.11  5037.2  268.64  5043.2  269.16  5101.9  269.52
  5143.9  267.96  5241.4  269.86  5326.8  271.64  5335.8  271.95  5427.2  274.51
  5470.3  276.47  5486.3  276.58  5510.1  277.83  5546.4  278.17  5654.7  282.11
#Mann= 9 ,-1 , 0
  4396.4     .07       0  4848.1      .1       0  5017.4     .05       0
  5021.4      .1       0  5101.9     .12       0  5241.4     .07       0
  5326.8     .12       0  5335.8     .07       0  5470.3     .12       0
Bank Sta=5017.4,5021.4
XS Rating Curve= 0 ,0
Exp/Cntr=0.3,0.1

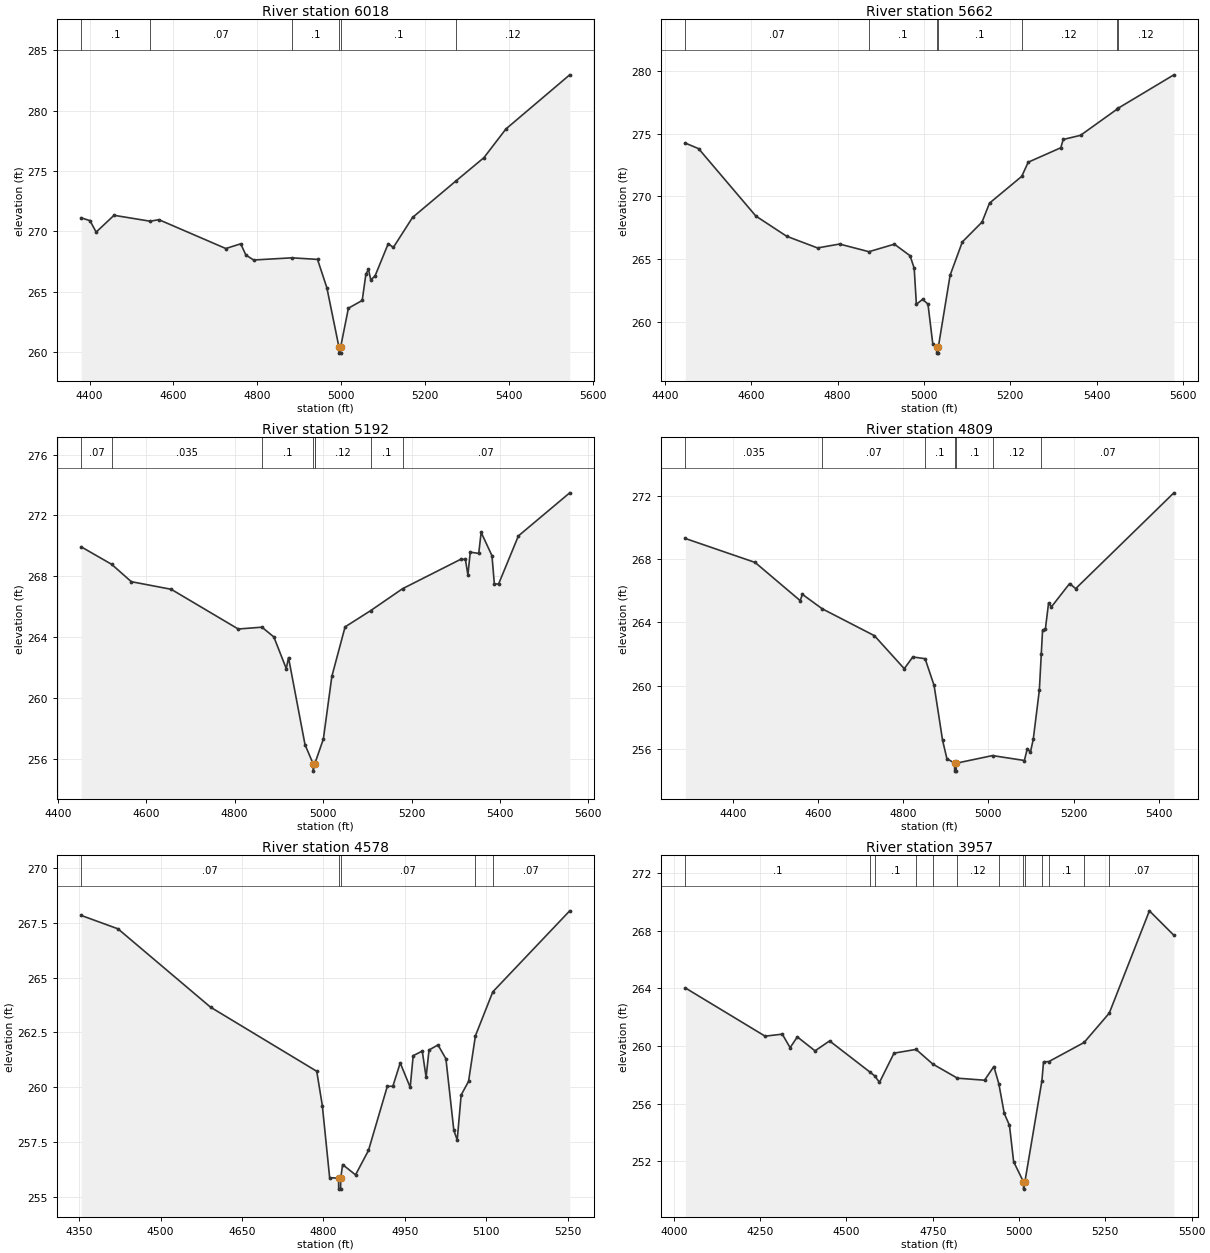
Type RM Length L Ch R = 1 ,6018    ,356,356,356
BEGIN DESCRIPTION:
Mapping XS 30f2ba12
END DESCRIPTION:
XS GIS Cut Line= 3
      2468864.75     13482657.89      2469513.75     13482507.51
      2469970.99     13482310.42
#Sta/Elev= 30
  4380.1  271.12  4400.9  270.89  4415.7  269.94  4458.3  271.33  4544.5  270.84
  4565.1  270.97  4724.7  268.58  4760.2  268.97  4772.5  268.04    4791  267.63
    4882  267.81  4943.2  267.68  4965.5  265.33  4994.3  260.42  4994.5  259.92
    4998  259.92  4998.3  260.42  5016.8  263.64  5049.7  264.28  5058.5  266.46
  5064.6  266.86  5070.1  265.98  5080.3  266.31  5111.7  268.98  5123.9  268.67
  5169.6  271.15  5272.9  274.17  5339.7   276.1  5392.2  278.48  5544.2  282.96
#Mann= 6 ,-1 , 0
  4380.1      .1       0  4544.5     .07       0    4882      .1       0
  4994.3     .05       0  4998.3      .1       0  5272.9     .12       0
Bank Sta=4994.3,4998.3
XS Rating Curve= 0 ,0
Exp/Cntr=0.3,0.1

Type RM Length L Ch R = 1 ,5662    ,470,470,470
BEGIN DESCRIPTION:
TRIB 1 TO HOG CREK 10.0
END DESCRIPTION:
XS GIS Cut Line= 3
      2469074.97     13482925.01       2469616.7     13482816.45
      2470140.24      13482570.1
#Sta/Elev= 30
  4447.5  274.24  4478.1   273.8  4610.7  268.43  4682.1  266.82  4753.5  265.89
  4804.5   266.2  4872.5  265.59  4931.5  266.19  4967.7  265.27  4977.3  264.28
  4982.4   261.4  4996.6  261.79  5009.2  261.42  5020.4  258.24  5029.3  258.01
  5029.5  257.51    5033  257.51  5033.3  258.01  5060.5  263.72  5088.8  266.37
  5134.4  267.95  5151.7  269.46  5226.3  271.59  5241.3  272.72  5316.8  273.87
  5322.3  274.53  5362.4  274.86  5446.5  276.93  5449.6  277.02  5578.6  279.68
#Mann= 7 ,-1 , 0
  4447.5     .07       0  4872.5      .1       0  5029.3     .05       0
  5033.3      .1       0  5226.3     .12       0  5446.5     .07       0
  5449.6     .12       0
Bank Sta=5029.3,5033.3
XS Rating Curve= 0 ,0
Exp/Cntr=0.3,0.1

Type RM Length L Ch R = 1 ,5192    ,383,383,383
BEGIN DESCRIPTION:
Mapping XS de6b8357
END DESCRIPTION:
XS GIS Cut Line= 3
      2469182.44     13483314.17      2469717.12     13483251.67
      2470244.93      13483046.8
#Sta/Elev= 30
  4453.2  269.94  4522.1  268.79  4566.5  267.65  4656.7  267.15  4808.2  264.54
  4861.9  264.66  4888.7  264.02  4916.8  261.94  4921.9  262.66  4959.2  256.94
  4977.3   255.7  4977.6   255.2  4981.3   255.7  4982.3  255.77  5000.7  257.31
  5019.9  261.43  5049.8  264.68  5107.7  265.75  5179.8  267.19  5311.1  269.12
  5321.8  269.12  5327.5  268.09  5332.8  269.59    5352  269.51  5357.4  270.89
  5381.9  269.36  5387.3   267.5  5396.9   267.5  5441.7  270.66  5557.7  273.49
#Mann= 8 ,-1 , 0
  4453.2     .07       0  4522.1    .035       0  4861.9      .1       0
  4977.3     .05       0  4981.3      .1       0  4982.3     .12       0
  5107.7      .1       0  5179.8     .07       0
Bank Sta=4977.3,4981.3
XS Rating Curve= 0 ,0
Exp/Cntr=0.3,0.1

Type RM Length L Ch R = 1 ,4809    ,231,231,231
BEGIN DESCRIPTION:
Mapping XS 7ce7bd5d
END DESCRIPTION:
XS GIS Cut Line= 4
      2469251.38     13483552.34      2469879.02     13483523.69
      2470032.67     13483500.25      2470304.99     13483259.06
#Sta/Elev= 30
  4288.2  269.29    4452  267.78    4558  265.37    4563  265.77  4609.5  264.86
  4732.3  263.16  4802.4  261.08  4822.4  261.82  4851.3  261.71  4872.4  260.03
  4892.4  256.56  4902.5  255.41  4920.5  255.12  4920.8  254.62  4924.3  254.62
  4924.5  255.12  5009.7   255.6  5084.6  255.29  5091.2  256.03  5098.8  255.82
  5105.4  256.63  5119.7  259.73  5124.2  261.99  5127.2  263.49  5133.9  263.59
  5141.4  265.23  5148.1  264.98  5190.8  266.45    5205  266.13  5435.7  272.17
#Mann= 7 ,-1 , 0
  4288.2    .035       0  4609.5     .07       0  4851.3      .1       0
  4920.5     .05       0  4924.5      .1       0  5009.7     .12       0
  5124.2     .07       0
Bank Sta=4920.5,4924.5
XS Rating Curve= 0 ,0
Exp/Cntr=0.3,0.1

Type RM Length L Ch R = 1 ,4578    ,621,621,621
BEGIN DESCRIPTION:
TRIB 1 TO HOG CREK 8.0
END DESCRIPTION:
XS GIS Cut Line= 3
      2469524.99       13483925.        2470125.       13483675.
      2470274.99     13483475.01
#Sta/Elev= 30
  4353.9  267.83  4421.6  267.22  4592.2  263.65  4787.8  260.73  4798.1  259.17
  4811.6  255.88    4828  255.86  4828.3  255.36  4831.8  255.36    4832  255.86
  4835.5  256.48  4859.3  256.01  4883.1  257.12  4917.8  260.04  4928.1  260.05
  4941.6  261.11    4960     260  4965.5  261.44  4982.2  261.65  4989.3  260.46
  4994.7   261.7  5011.2  261.93  5025.8   261.3  5040.4  258.04  5046.6   257.6
  5053.9  259.65  5067.5  260.27  5080.2  262.35  5112.2  264.35  5253.9  268.04
#Mann= 5 ,-1 , 0
  4353.9     .07       0    4828     .05       0    4832     .07       0
  5080.2     .12       0  5112.2     .07       0
Bank Sta=4828,4832
XS Rating Curve= 0 ,0
Exp/Cntr=0.3,0.1

Type RM Length L Ch R = 1 ,3957    ,316,316,316
BEGIN DESCRIPTION:
Mapping XS 3fda548c
END DESCRIPTION:
XS GIS Cut Line= 3
      2469610.39     13484699.21      2470415.96     13484169.48
      2470692.95     13483813.35
#Sta/Elev= 30
  4033.2  264.03  4264.2  260.68    4314  260.82  4336.6  259.88  4357.6  260.63
  4408.9  259.66    4451  260.35  4569.3  258.16  4581.7  257.92  4595.6  257.47
  4637.7   259.5  4701.6  259.76  4750.1  258.74  4821.4  257.76  4899.9  257.62
    4927  258.57  4941.3  257.38  4957.1  255.31  4972.2  254.48  4984.2  251.96
  5012.8  250.55    5013  250.05  5016.8  250.55  5066.1  257.57  5070.9   258.9
  5085.9  258.91  5188.3  260.24  5261.3  262.28  5377.6  269.39  5448.5  267.69
#Mann= 13 ,-1 , 0
  4033.2      .1       0  4569.3     .07       0  4581.7      .1       0
  4701.6     .12       0  4750.1     .07       0  4821.4     .12       0
  4941.3      .1       0  5012.8     .05       0  5016.8      .1       0
  5066.1     .07       0  5085.9      .1       0  5188.3     .05       0
  5261.3     .07       0
Bank Sta=5012.8,5016.8
XS Rating Curve= 0 ,0
Exp/Cntr=0.3,0.1

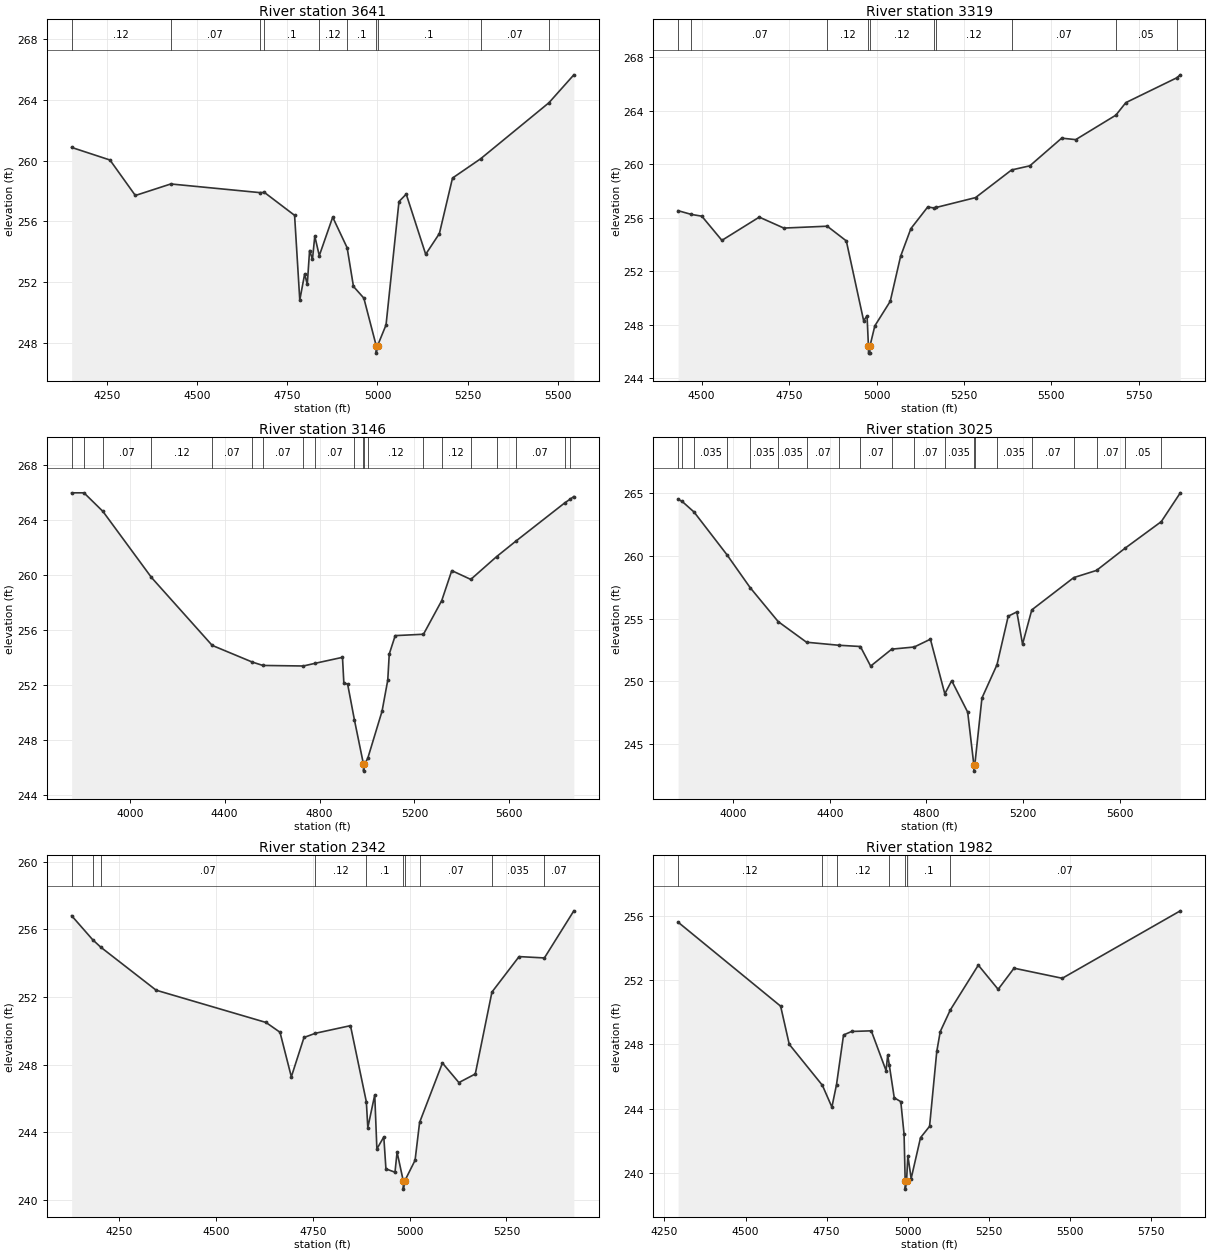
Type RM Length L Ch R = 1 ,3641    ,322,322,322
BEGIN DESCRIPTION:
Mapping XS c00667c2
END DESCRIPTION:
XS GIS Cut Line= 3
      2469940.23     13484928.94      2470582.62     13484415.02
      2470776.49     13483878.43
#Sta/Elev= 30
  4151.6  260.87  4257.9  260.04  4328.3   257.7  4426.7  258.46  4673.3  257.89
  4686.5   257.9  4770.1  256.39  4784.5   250.8    4798  252.52  4805.3  251.84
  4811.7  254.07  4819.7  253.49  4826.1  255.02  4838.6  253.73  4875.8  256.27
  4915.9  254.25  4933.4   251.7  4962.2  250.93  4996.4   247.8  4996.7   247.3
  5000.4   247.8  5023.8  249.16  5059.7   257.3  5079.8  257.79  5133.8  253.82
  5171.8  255.19  5208.2  258.85  5286.1  260.12  5475.8  263.82  5544.8  265.66
#Mann= 10 ,-1 , 0
  4151.6     .12       0  4426.7     .07       0  4673.3     .12       0
  4686.5      .1       0  4838.6     .12       0  4915.9      .1       0
  4996.4     .05       0  5000.4      .1       0  5286.1     .07       0
  5475.8     .05       0
Bank Sta=4996.4,5000.4
XS Rating Curve= 0 ,0
Exp/Cntr=0.3,0.1

Type RM Length L Ch R = 1 ,3319    ,173,173,173
BEGIN DESCRIPTION:
Mapping XS f291ef52
END DESCRIPTION:
XS GIS Cut Line= 3
      2470290.93     13485137.27      2470634.71     13484720.58
      2470971.51     13483890.72
#Sta/Elev= 30
  4432.7  256.53  4470.9  256.25  4500.5  256.12  4557.9  254.31  4664.7  256.05
    4735  255.23    4859  255.37  4913.6  254.27  4963.1   248.3  4972.9  248.66
  4976.9  246.37  4977.2  245.87  4980.7  245.87  4980.9  246.37  4995.1  247.91
  5039.2  249.75  5068.7  253.11  5098.2  255.19  5146.4  256.81  5165.2  256.73
    5170  256.77    5283  257.51  5386.1  259.58  5438.3  259.89  5529.3  261.96
  5569.5  261.85  5684.2  263.68  5712.8  264.62  5857.8  266.47  5868.5   266.7
#Mann= 10 ,-1 , 0
  4432.7     .12       0  4470.9     .07       0    4859     .12       0
  4976.9     .05       0  4980.9     .12       0  5165.2      .1       0
    5170     .12       0  5386.1     .07       0  5684.2     .05       0
  5857.8     .07       0
Bank Sta=4976.9,4980.9
XS Rating Curve= 0 ,0
Exp/Cntr=0.3,0.1

Type RM Length L Ch R = 1 ,3146    ,121,121,121
BEGIN DESCRIPTION:
Mapping XS 67268a00
END DESCRIPTION:
XS GIS Cut Line= 4
      2469993.17      13485773.7      2470526.34     13485260.29
      2470763.18     13484828.22      2471068.45     13483999.13
#Sta/Elev= 30
  3755.4  265.96  3807.3  265.96  3887.1  264.61  4091.8   259.8  4347.6  254.86
    4516  253.65  4561.2   253.4  4731.7  253.36  4782.7  253.56  4896.8  253.99
  4902.5  252.14  4918.6  252.03  4947.4  249.41  4985.3  246.21  4985.5  245.71
  4989.3  246.21  5003.1  246.63  5063.5  250.07  5087.6  252.33  5093.9  254.23
    5119  255.57  5238.1  255.67  5315.1  258.12  5357.4   260.3  5437.5  259.66
  5546.4  261.32  5627.1  262.44  5833.6  265.23  5854.7  265.48  5871.8  265.69
#Mann= 20 ,-1 , 0
  3755.4     .07       0  3807.3     .12       0  3887.1     .07       0
  4091.8     .12       0  4347.6     .07       0    4516    .035       0
  4561.2     .07       0  4731.7    .035       0  4782.7     .07       0
  4947.4    .035       0  4985.3    .035       0  4989.3    .035       0
  5003.1     .12       0  5238.1    .035       0  5315.1     .12       0
  5437.5     .07       0  5546.4    .035       0  5627.1     .07       0
  5833.6     .05       0  5854.7    .035       0
Bank Sta=4985.3,4989.3
XS Rating Curve= 0 ,0
Exp/Cntr=0.3,0.1

Type RM Length L Ch R = 1 ,3025    ,683,683,683
BEGIN DESCRIPTION:
Mapping XS 3eeb0693
END DESCRIPTION:
XS GIS Cut Line= 4
      2470071.33      13485789.3      2470527.03     13485521.09
      2470849.98     13484908.08      2471186.75     13484119.97
#Sta/Elev= 30
  3772.1  264.48  3788.6  264.32  3838.2  263.47  3974.1  260.08  4070.3  257.46
  4186.3  254.76  4303.6  253.12  4436.7  252.88  4526.5  252.78    4569  251.22
  4656.4  252.57  4749.4  252.74  4816.4  253.36    4876  249.02  4904.6  250.06
  4970.7  247.56  4996.2  243.37  4996.4  242.87  5000.2  243.37  5029.7  248.68
    5092  251.33  5138.5  255.19  5174.2  255.53  5197.8  252.97    5236  255.69
  5409.8  258.26    5504  258.83  5621.7  260.59  5772.1  262.71  5850.8     265
#Mann= 20 ,-1 , 0
  3772.1    .035       0  3788.6     .12       0  3838.2    .035       0
  3974.1     .07       0  4070.3    .035       0  4186.3    .035       0
  4303.6     .07       0  4436.7    .035       0  4526.5     .07       0
  4656.4    .035       0  4749.4     .07       0    4876    .035       0
  4996.2     .05       0  5000.2      .1       0    5092    .035       0
    5236     .07       0  5409.8    .035       0    5504     .07       0
  5621.7     .05       0  5772.1     .05       0
Bank Sta=4996.2,5000.2
XS Rating Curve= 0 ,0
Exp/Cntr=0.3,0.1

Type RM Length L Ch R = 1 ,2342    ,360,360,360
BEGIN DESCRIPTION:
TRIB 1 TO HOG CREK 3.0
END DESCRIPTION:
XS GIS Cut Line= 3
      2470375.02     13485724.99        2471175.       13485375.
      2471475.03     13485074.97
#Sta/Elev= 30
  4126.7  256.81    4181  255.39  4201.8  254.95    4345   252.4  4628.8  250.49
    4665  249.91  4694.3  247.27    4727   249.6  4756.6  249.85  4847.1   250.3
  4888.1  245.79  4891.9  244.26  4909.8   246.2  4915.3     243  4933.2  243.71
  4938.7  241.82  4962.1  241.62  4967.5  242.81  4983.4  241.12  4983.7  240.62
  4987.6  241.12    5014  242.33  5025.7  244.57  5084.7  248.09  5127.2  246.93
  5169.6  247.44  5212.6  252.29  5282.7  254.39  5348.1  254.31  5424.2   257.1
#Mann= 10 ,-1 , 0
  4126.7    .035       0    4181     .12       0  4201.8     .07       0
  4756.6     .12       0  4888.1      .1       0  4983.4     .05       0
  4987.6      .1       0  5025.7     .07       0  5212.6    .035       0
  5348.1     .07       0
Bank Sta=4983.4,4987.6
XS Rating Curve= 0 ,0
Exp/Cntr=0.3,0.1

Type RM Length L Ch R = 1 ,1982    ,474,474,474
BEGIN DESCRIPTION:
Mapping XS 5edc1ed4
END DESCRIPTION:
XS GIS Cut Line= 4
      2470426.38     13485828.22      2471120.82     13485720.58
      2471395.12     13485581.69      2471756.25     13485182.36
#Sta/Elev= 30
  4292.2  255.63  4608.3  250.39  4634.9  248.01  4737.1  245.45  4766.4  244.09
  4780.7   245.5  4802.3  248.59  4827.1  248.81  4887.9  248.85  4933.4  246.37
  4938.5  247.33  4943.3  246.73  4958.7  244.67  4978.9  244.43    4989  242.39
  4992.4  239.47  4992.7  238.97  4996.6  239.47  5000.7  241.06  5010.8  239.63
  5039.7  242.18  5067.6  242.89  5089.8  247.56  5100.5   248.8  5131.5  250.15
  5217.9  252.95  5279.1  251.44  5328.1  252.76  5476.8  252.13  5840.8  256.34
#Mann= 7 ,-1 , 0
  4292.2     .12       0  4737.1     .07       0  4780.7     .12       0
  4943.3      .1       0  4992.4     .05       0  4996.6      .1       0
  5131.5     .07       0
Bank Sta=4992.4,4996.6
XS Rating Curve= 0 ,0
Exp/Cntr=0.3,0.1

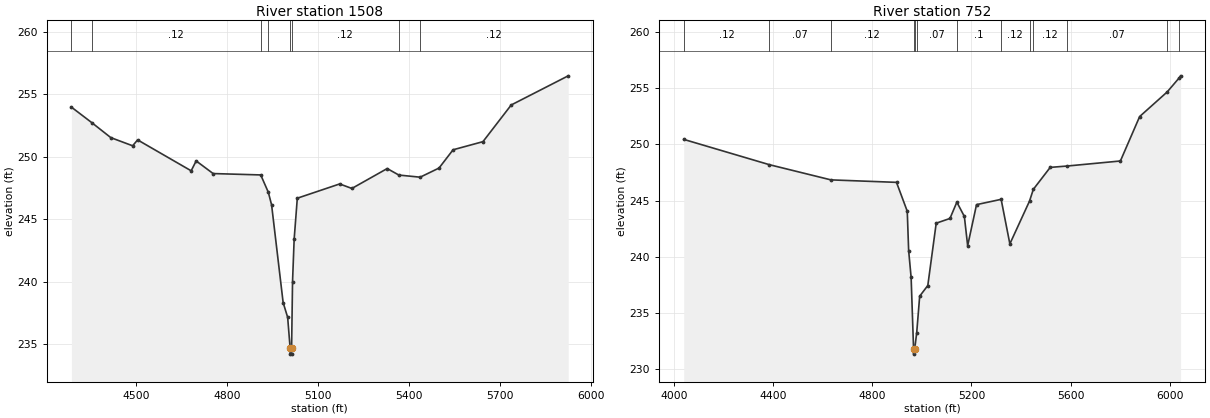
Type RM Length L Ch R = 1 ,1508    ,756,756,756
BEGIN DESCRIPTION:
Mapping XS 8845780a
END DESCRIPTION:
XS GIS Cut Line= 5
      2470527.09     13485918.51      2470912.48     13486119.89
       2471086.1     13486119.89      2471613.87     13485935.86
      2472044.43     13485744.89
#Sta/Elev= 30
  4286.2  253.97  4352.9  252.74  4416.3  251.53  4488.2  250.88  4504.6  251.35
  4681.2  248.88  4697.7  249.67  4753.6  248.66  4910.6  248.55  4935.7  247.16
  4946.4  246.16  4984.5  238.35  4999.4  237.17  5007.5  234.73  5007.9  234.23
  5012.1  234.23  5012.4  234.73  5015.5  240.03  5020.8   243.4  5031.2  246.69
  5170.9  247.83  5211.2  247.47  5327.7  249.06  5366.1  248.54  5436.3  248.37
  5498.6   249.1  5544.9  250.56  5643.5  251.21  5736.6  254.14  5924.6  256.47
#Mann= 8 ,-1 , 0
  4286.2     .07       0  4352.9     .12       0  4910.6      .1       0
  4935.7     .12       0  5007.5     .05       0  5012.4     .12       0
  5366.1     .07       0  5436.3     .12       0
Bank Sta=5007.5,5012.4
XS Rating Curve= 0 ,0
Exp/Cntr=0.3,0.1

Type RM Length L Ch R = 1 ,752     ,0,0,0
BEGIN DESCRIPTION:
TRIB 1 TO HOG CREK 1.0
END DESCRIPTION:
XS GIS Cut Line= 4
       2470711.1     13486092.11      2471262.44     13486750.21
      2471501.16     13486628.68      2472091.92     13485978.75
#Sta/Elev= 30
  4039.2  250.45  4384.8   248.2  4633.1  246.85  4897.7  246.63  4941.1  244.06
  4946.7  240.56  4956.7  238.18  4966.5  231.86  4966.8  231.36  4971.4  231.86
  4979.3  233.28  4991.2  236.51    5024  237.46  5057.9     243  5113.4  243.42
  5141.2  244.87  5171.5   243.6  5184.8     241  5220.6  244.65  5319.9  245.12
  5355.1  241.16  5434.5  244.97  5449.8  246.01  5517.9  247.96  5585.4  248.08
  5801.1  248.53  5878.8  252.48    5990  254.67    6038  255.91  6043.9   256.1
#Mann= 13 ,-1 , 0
  4039.2     .12       0  4384.8     .07       0  4633.1     .12       0
  4966.5     .05       0  4971.4     .12       0  4979.3     .07       0
  5141.2      .1       0  5319.9     .12       0  5434.5      .1       0
  5449.8     .12       0  5585.4     .07       0    5990     .12       0
    6038     .07       0
Bank Sta=4966.5,4971.4
XS Rating Curve= 0 ,0
Exp/Cntr=0.3,0.1

Chan Stop Cuts=-1
Use User Specified Reach Order=0
Composite Channel Slope=5