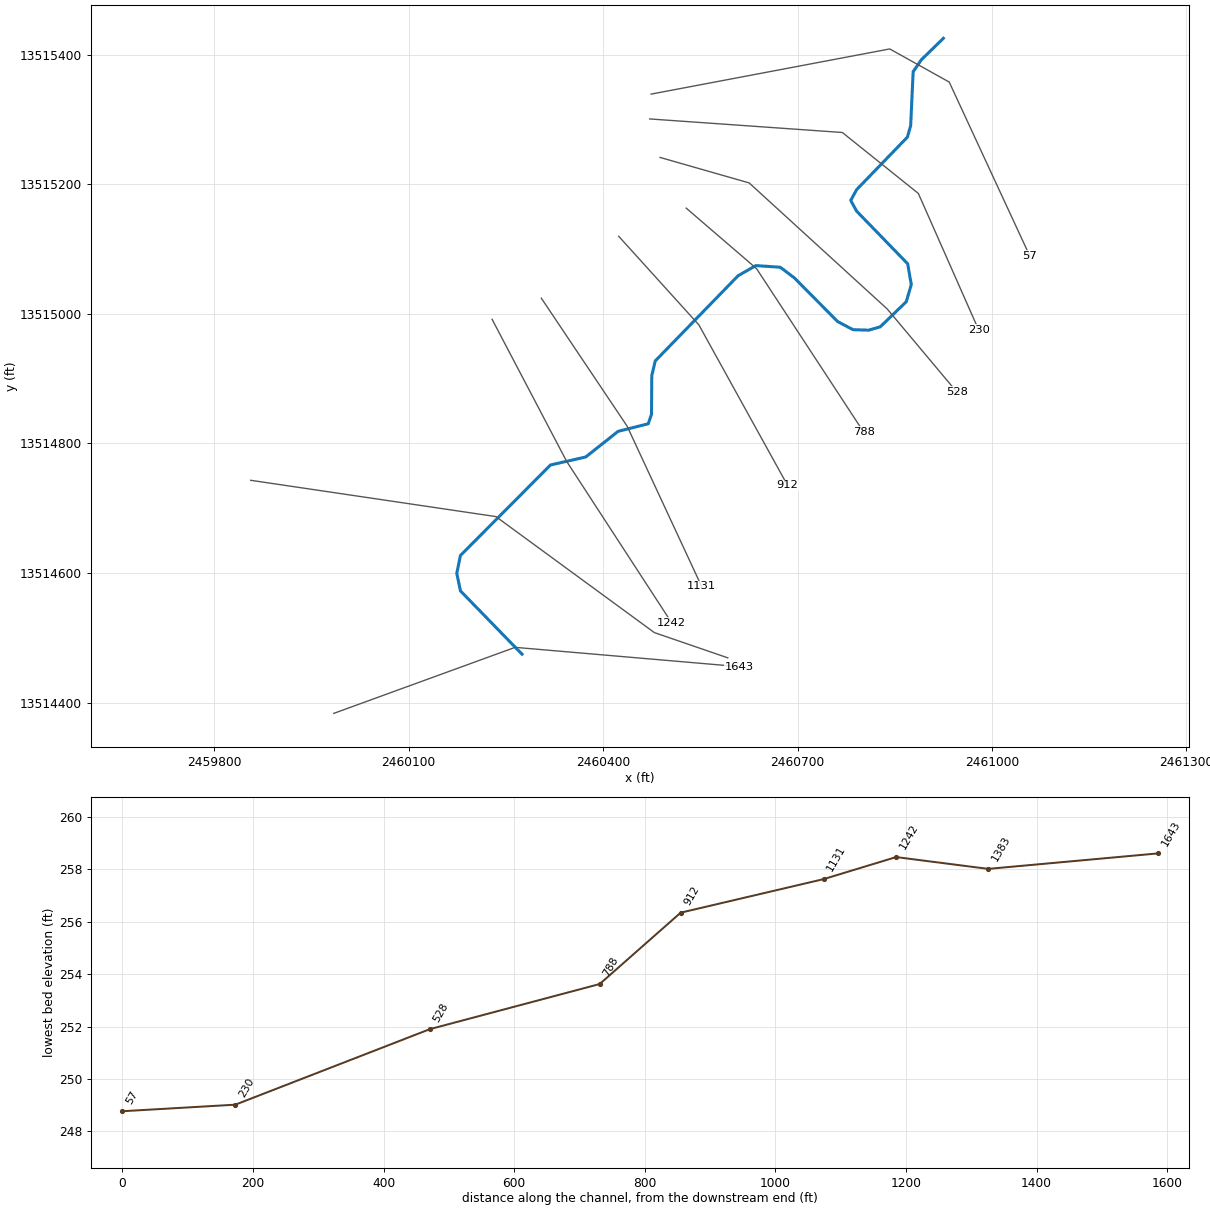
--- TRIB 1 TO HOOSIER CREEK.prj (project) ---

Proj Title=TRIB 1 TO HOOSIER CREEK Base Level Engineering
Current Plan=p01
Default Exp/Contr=0.3,0.1
English Units
Geom File=g01
Flow File=f01
Plan File=p01
Y Axis Title=Elevation
X Axis Title(PF)=Main Channel Distance
X Axis Title(XS)=Station
BEGIN DESCRIPTION:
TRIB 1 TO HOOSIER CREEK
END DESCRIPTION:
DSS Export Rating Curves= 0
DSS Export Rating Curve Sorted= 0
DSS Export Volume Flow Curves= 0
DXF OffsetX= 0
DXF OffsetY= 0
DXF ScaleX= 1
DXF ScaleY= 10

--- TRIB 1 TO HOOSIER CREEK.p01 (plan) ---

Plan Title=Multiple Run
Short Identifier=Multiple
Geom File=g01
Flow File=f01
Subcritical Flow
K Sum by GR= 0
Std Step Tol= 0.01
Critical Tol= 0.01
Num of Std Step Trials= 20
Max Error Tol= 0.3
Flow Tol Ratio= 0.001
Split Flow NTrial= 30
Split Flow Tol= 0.02
Split Flow Ratio= 0.02
Log Output Level= 0
Friction Slope Method= 1
Unsteady Friction Slope Method= 2
Unsteady Bridges Friction Slope Method= 1
Parabolic Critical Depth
Global Vel Dist=  1 , 1 , 1
Global Log Level= 0
CheckData=True
Encroach Param= -1, 0, 0, 0
BEGIN DESCRIPTION:
Multiple Run
END DESCRIPTION:

--- TRIB 1 TO HOOSIER CREEK.f01 (steady flow) ---

Flow Title=Multiple
Number of Profiles=7
Profile Names=10-year,25-year,50-year,1pct_min,100-year,1pct_plu,500-year
River Rch & RM= TRIB 1 TO HOOSIE,Reach-1,1643
     688    1114    1499     977    1949    3888    3259
Boundary for River Rch & Prof#=TRIB 1 TO HOOSIE,Reach-1,1
Up Type=0
Dn Type=3
Dn Slope=0.005
Boundary for River Rch & Prof#=TRIB 1 TO HOOSIE,Reach-1,2
Up Type=0
Dn Type=3
Dn Slope=0.005
Boundary for River Rch & Prof#=TRIB 1 TO HOOSIE,Reach-1,3
Up Type=0
Dn Type=3
Dn Slope=0.005
Boundary for River Rch & Prof#=TRIB 1 TO HOOSIE,Reach-1,4
Up Type=0
Dn Type=3
Dn Slope=0.005
Boundary for River Rch & Prof#=TRIB 1 TO HOOSIE,Reach-1,5
Up Type=0
Dn Type=3
Dn Slope=0.005
Boundary for River Rch & Prof#=TRIB 1 TO HOOSIE,Reach-1,6
Up Type=0
Dn Type=3
Dn Slope=0.005
Boundary for River Rch & Prof#=TRIB 1 TO HOOSIE,Reach-1,7
Up Type=0
Dn Type=3
Dn Slope=0.005

--- TRIB 1 TO HOOSIER CREEK.g01 (geometry) ---

Geom Title=Existing Conditions
Program Version=4.10

River Reach=TRIB 1 TO HOOSIE,Reach-1
Reach XY= 30
        2460275.       13514475.      2460179.98     13514572.69
      2460174.39     13514600.01      2460180.06     13514627.29
      2460318.95     13514766.86       2460373.3     13514779.18
       2460423.2     13514818.74      2460469.75     13514830.44
      2460474.79     13514845.25       2460475.2     13514904.79
      2460480.55     13514927.37      2460608.33     13515058.79
      2460635.64     13515074.45      2460673.35     13515071.89
      2460695.07     13515055.53      2460761.82     13514988.14
       2460785.7     13514975.54       2460809.8     13514974.84
      2460827.61     13514979.96      2460867.66     13515018.57
      2460875.51     13515045.03      2460869.92     13515077.26
      2460791.24     13515158.35       2460782.1       13515175.
      2460791.23     13515191.65      2460869.47     13515272.56
      2460874.52     13515290.19      2460878.39     13515373.59
      2460891.12     13515392.05        2460925.       13515425.

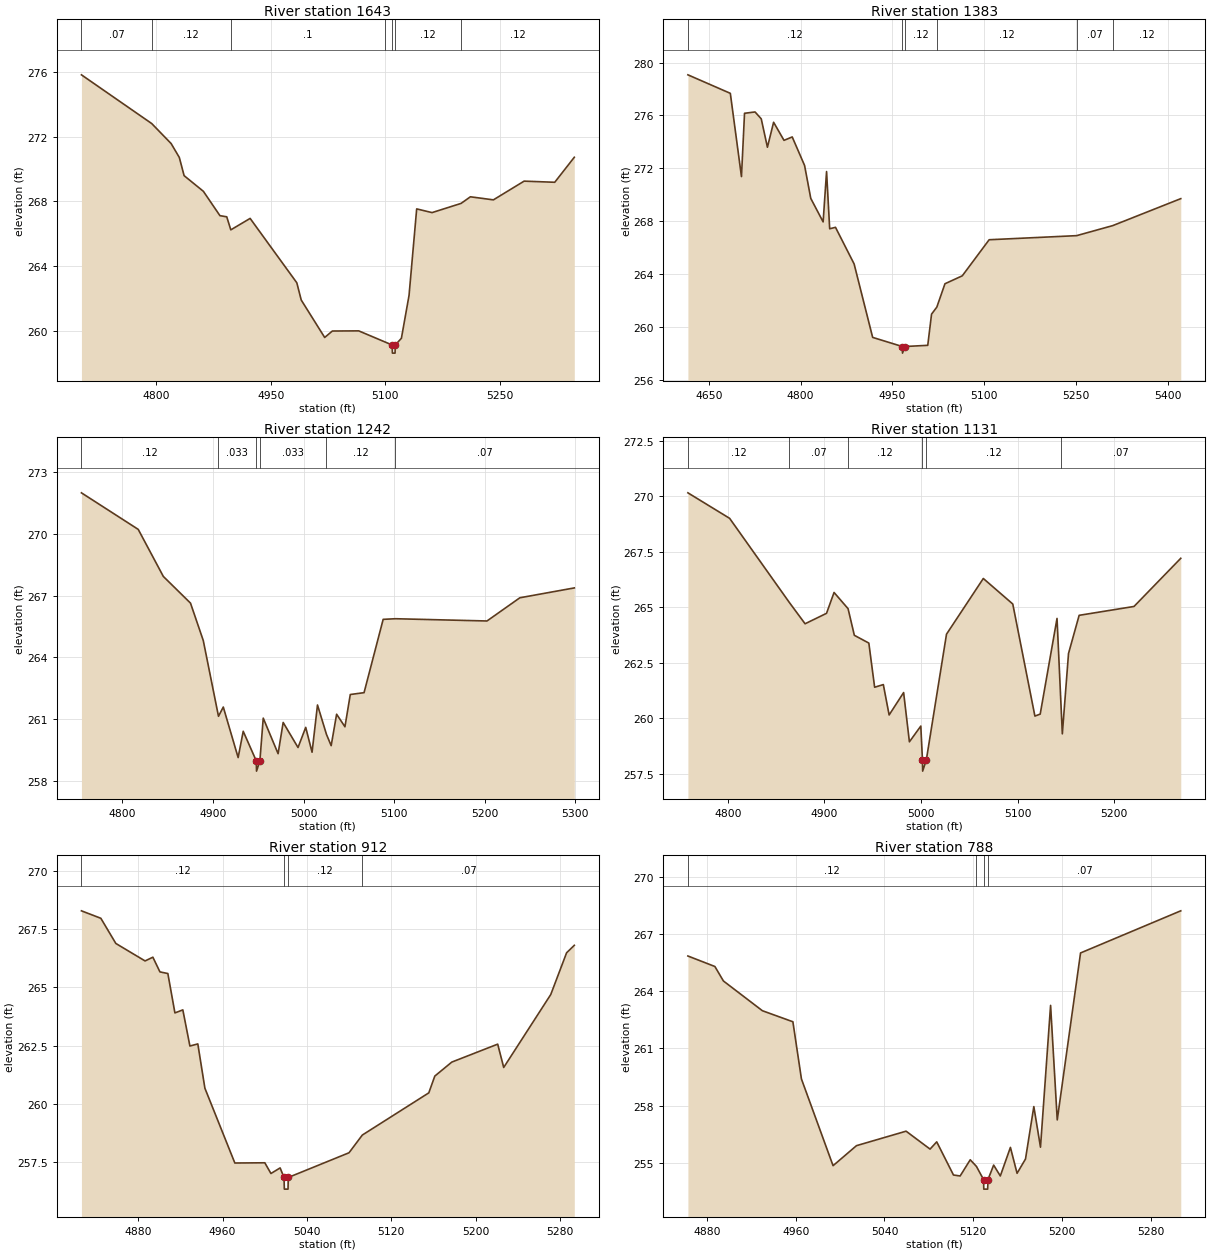
Type RM Length L Ch R = 1 ,1643    ,260,260,260
BEGIN DESCRIPTION:
TRIB 1 TO HOOSIER CREEK 3.0
END DESCRIPTION:
XS GIS Cut Line= 3
      2459984.65     13514383.69      2460264.39     13514485.54
      2460610.51     13514455.75
#Sta/Elev= 30
  4702.3  275.85  4794.3  272.83  4819.7  271.59  4830.4  270.73  4836.7   269.6
  4861.9  268.63  4883.6  267.12  4892.5  267.05  4897.8  266.24  4923.1  266.95
  4984.2  262.96    4990  261.89  5020.7  259.57  5030.7  259.97  5065.2  259.98
  5100.2  259.28    5109   259.1  5109.3   258.6  5112.8   258.6    5113   259.1
  5121.1  259.52  5131.1  262.18  5141.1  267.54  5161.2  267.31  5199.2  267.88
  5211.4  268.29  5241.5   268.1  5281.7  269.26  5321.8  269.19  5347.4  270.74
#Mann= 7 ,-1 , 0
  4702.3     .07       0  4794.3     .12       0  4897.8      .1       0
  5100.2     .12       0    5109     .05       0    5113     .12       0
  5199.2     .12       0
Bank Sta=5109,5113
XS Rating Curve= 0 ,0
Exp/Cntr=0.3,0.1

Type RM Length L Ch R = 1 ,1383    ,141,141,141
BEGIN DESCRIPTION:
Mapping XS 459544c4
END DESCRIPTION:
XS GIS Cut Line= 4
      2459856.47     13514743.25       2460234.7     13514687.27
      2460479.17     13514508.31      2460592.44     13514469.36
#Sta/Elev= 30
    4616  279.07  4685.3  277.67  4703.5  271.37  4708.5  276.16  4725.7  276.26
  4735.8  275.74  4745.9  273.59    4756  275.48    4773  274.11  4786.4  274.37
  4806.6  272.21  4816.7  269.72  4836.9  267.94  4842.5  271.75  4847.6  267.42
  4857.1  267.53  4887.5  264.76  4917.8   259.2  4966.3  258.51  4966.6  258.01
  4970.3  258.51  5007.8   258.6    5014  260.96  5022.6  261.49  5035.9  263.26
  5064.2  263.86  5108.1  266.59    5251   266.9    5310  267.66  5421.1   269.7
#Mann= 6 ,-1 , 0
    4616     .12       0  4966.3     .05       0  4970.3     .12       0
  5022.6     .12       0    5251     .07       0    5310     .12       0
Bank Sta=4966.3,4970.3
XS Rating Curve= 0 ,0
Exp/Cntr=0.3,0.1

Type RM Length L Ch R = 1 ,1242    ,111,111,111
BEGIN DESCRIPTION:
Mapping XS 05ad8aa0
END DESCRIPTION:
XS GIS Cut Line= 3
      2460228.83     13514991.65      2460343.85     13514772.44
      2460505.57     13514523.87
#Sta/Elev= 30
  4754.7  272.01  4817.4  270.23  4845.1  267.94  4875.1  266.64  4889.2  264.82
    4906  261.13  4911.3  261.58  4927.7  259.12  4933.3   260.4  4947.7  258.96
    4948  258.46  4951.7  258.96  4955.4  261.04  4971.8  259.31  4977.4  260.83
  4993.8  259.61  5002.3  260.59  5009.3  259.38  5015.3  261.68  5025.2  260.25
  5030.4   259.7  5036.4  261.23  5045.6  260.62  5051.5  262.19  5066.7  262.28
  5087.8  265.85  5101.4  265.88  5202.4  265.77  5238.7   266.9  5298.8  267.38
#Mann= 6 ,-1 , 0
  4754.7     .12       0    4906    .033       0  4947.7    .033       0
  4951.7    .033       0  5025.2     .12       0  5101.4     .07       0
Bank Sta=4947.7,4951.7
XS Rating Curve= 0 ,0
Exp/Cntr=0.3,0.1

Type RM Length L Ch R = 1 ,1131    ,219,219,219
BEGIN DESCRIPTION:
Mapping XS f1505cec
END DESCRIPTION:
XS GIS Cut Line= 3
      2460304.79     13515024.18      2460437.17      13514826.7
      2460552.03     13514579.64
#Sta/Elev= 30
  4758.7  270.16  4801.9  269.01  4863.7  265.22    4880  264.26  4902.2  264.73
    4910  265.67  4924.5  264.94    4931  263.74    4946  263.39    4952   261.4
    4961  261.52    4967  260.15    4982  261.16    4988  258.94  4999.8  259.65
  5001.5  258.12  5001.7  257.62  5005.5  258.12  5026.4  263.79  5064.5   266.3
    5095  265.15  5117.9   260.1  5123.4  260.19  5140.8   264.5  5144.7  260.81
  5146.3   259.3  5152.7  262.92  5163.7  264.64  5220.5  265.04  5268.9  267.21
#Mann= 6 ,-1 , 0
  4758.7     .12       0  4863.7     .07       0  4924.5     .12       0
  5001.5     .05       0  5005.5     .12       0  5144.7     .07       0
Bank Sta=5001.5,5005.5
XS Rating Curve= 0 ,0
Exp/Cntr=0.3,0.1

Type RM Length L Ch R = 1 ,912     ,124,124,124
BEGIN DESCRIPTION:
Mapping XS e7e3404d
END DESCRIPTION:
XS GIS Cut Line= 3
      2460424.13     13515119.69      2460547.85     13514982.95
      2460684.58     13514735.52
#Sta/Elev= 30
  4826.3  268.28  4844.7  267.96  4858.9  266.88  4886.6  266.13    4894  266.29
  4900.7  265.66  4908.2  265.59  4914.9   263.9  4922.4  264.03  4929.1  262.48
  4936.6  262.57  4943.3  260.67  4971.7  257.46  5000.1  257.47  5005.9  257.01
  5014.6  257.25  5018.3  256.84  5018.6  256.34  5022.1  256.34  5022.3  256.84
  5079.9   257.9  5092.5  258.66  5155.5  260.47  5161.2  261.19  5177.3  261.79
  5220.8  262.56  5226.5  261.56  5271.1  264.69  5286.1  266.48  5293.4   266.8
#Mann= 4 ,-1 , 0
  4826.3     .12       0  5018.3     .05       0  5022.3     .12       0
  5092.5     .07       0
Bank Sta=5018.3,5022.3
XS Rating Curve= 0 ,0
Exp/Cntr=0.3,0.1

Type RM Length L Ch R = 1 ,788     ,260,260,260
BEGIN DESCRIPTION:
Mapping XS f6cd2a00
END DESCRIPTION:
XS GIS Cut Line= 3
       2460528.3     13515163.08      2460636.82     13515069.75
      2460801.76     13514818.01
#Sta/Elev= 30
  4862.9  265.85  4887.2   265.3  4894.9  264.54    4930  262.98  4957.5   262.4
  4965.2   259.4  4993.7  254.85  5014.8   255.9  5059.5  256.66  5081.1  255.72
  5087.1   256.1  5102.2  254.36  5108.2  254.31  5117.3  255.16  5122.9  254.81
  5129.3  254.12  5129.5  253.62    5133  253.62  5133.3  254.12  5138.4  254.88
  5144.4  254.31  5153.5  255.81  5159.5  254.45  5167.1   255.2  5174.6  257.95
  5180.6  255.82  5189.7  263.26  5195.7  257.25  5216.7  266.01    5307  268.22
#Mann= 4 ,-1 , 0
  4862.9     .12       0  5122.9     .07       0  5129.3     .05       0
  5133.3     .07       0
Bank Sta=5129.3,5133.3
XS Rating Curve= 0 ,0
Exp/Cntr=0.3,0.1

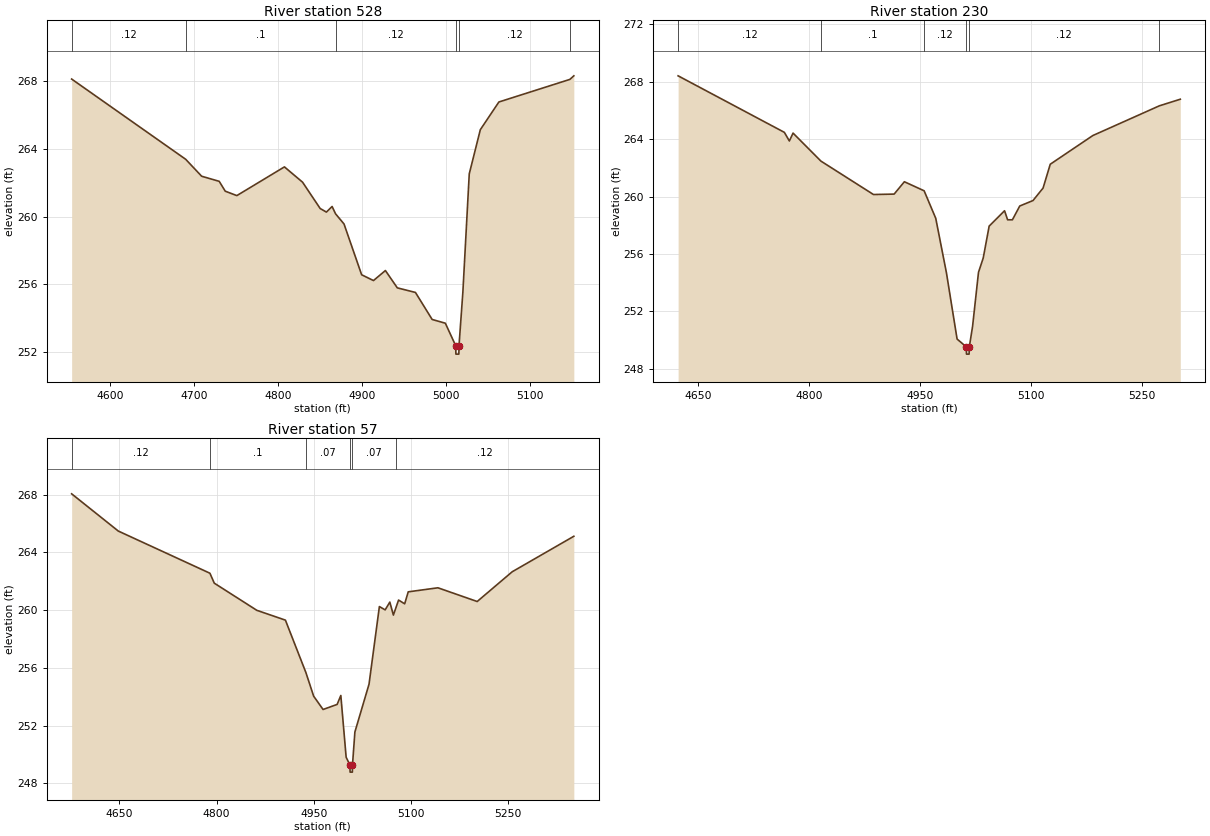
Type RM Length L Ch R = 1 ,528     ,298,298,298
BEGIN DESCRIPTION:
Mapping XS b244f6b2
END DESCRIPTION:
XS GIS Cut Line= 4
      2460488.03     13515241.26       2460625.4     13515201.97
       2460838.5      13515007.4      2460945.66      13514879.5
#Sta/Elev= 30
  4554.1  268.09  4689.9  263.37    4709  262.37  4729.9  262.07  4737.1  261.49
  4750.9  261.23  4807.6  262.92  4829.2  262.02  4850.2  260.47  4857.6  260.26
  4864.4  260.59  4868.5  260.16  4878.6  259.56  4899.6  256.57  4913.7  256.23
  4927.9  256.82  4942.1   255.8  4963.7  255.53  4983.6  253.94  4999.3  253.72
  5011.6   252.4  5011.9   251.9  5015.4   251.9  5015.6   252.4  5020.2  255.55
  5027.8  262.51    5041  265.11  5063.1  266.74  5147.7  268.07  5152.4  268.28
#Mann= 6 ,-1 , 0
  4554.1     .12       0  4689.9      .1       0  4868.5     .12       0
  5011.6     .05       0  5015.6     .12       0  5147.7     .07       0
Bank Sta=5011.6,5015.6
XS Rating Curve= 0 ,0
Exp/Cntr=0.3,0.1

Type RM Length L Ch R = 1 ,230     ,173,173,173
BEGIN DESCRIPTION:
Mapping XS afb03556
END DESCRIPTION:
XS GIS Cut Line= 4
       2460471.9     13515300.66      2460769.14     13515279.76
      2460886.41     13515185.71      2460979.31     13514975.53
#Sta/Elev= 30
  4623.3  268.41  4766.8  264.47  4773.5  263.87  4778.5  264.42  4816.1  262.47
  4887.1  260.14    4915  260.17  4928.8  261.03  4955.5   260.4  4971.2  258.48
  4985.6  254.69    5000  250.07  5012.5  249.52  5012.7  249.02  5016.2  249.02
  5016.5  249.52  5020.9  250.95  5028.9  254.72  5035.3  255.72  5043.3  257.94
  5064.1  259.01  5068.2  258.38  5074.7  258.38  5084.6  259.34  5102.5  259.72
  5116.1  260.59  5125.8  262.25  5183.3  264.25  5273.1  266.32  5301.4  266.78
#Mann= 6 ,-1 , 0
  4623.3     .12       0  4816.1      .1       0  4955.5     .12       0
  5012.5     .05       0  5016.5     .12       0  5273.1     .07       0
Bank Sta=5012.5,5016.5
XS Rating Curve= 0 ,0
Exp/Cntr=0.3,0.1

Type RM Length L Ch R = 1 ,57      ,0,0,0
BEGIN DESCRIPTION:
TRIB 1 TO HOOSIER CREEK 1.0
END DESCRIPTION:
XS GIS Cut Line= 4
      2460474.24     13515338.98      2460842.29     13515408.64
      2460934.02     13515357.55       2461058.1     13515089.67
#Sta/Elev= 30
  4576.5  268.05  4648.5  265.47  4789.8  262.55  4796.6  261.86  4862.2  259.98
  4906.3   259.3  4937.9  255.67  4949.9  254.03  4964.4  253.11  4986.1  253.46
  4991.8  254.08    5000   249.8  5005.8  249.27  5006.1  248.77  5009.6  248.77
  5009.8  249.27  5013.5  251.55  5035.3  254.86  5051.3  260.24  5060.2  260.01
  5067.4  260.55  5072.9  259.65  5076.2  260.08  5080.9  260.69  5090.3  260.43
  5095.8  261.26  5141.6  261.54  5202.2  260.59  5256.2  262.65  5351.3  265.11
#Mann= 6 ,-1 , 0
  4576.5     .12       0  4789.8      .1       0  4937.9     .07       0
  5005.8     .05       0  5009.8     .07       0  5076.2     .12       0
Bank Sta=5005.8,5009.8
XS Rating Curve= 0 ,0
Exp/Cntr=0.3,0.1

Chan Stop Cuts=-1
Use User Specified Reach Order=0
Composite Channel Slope=5