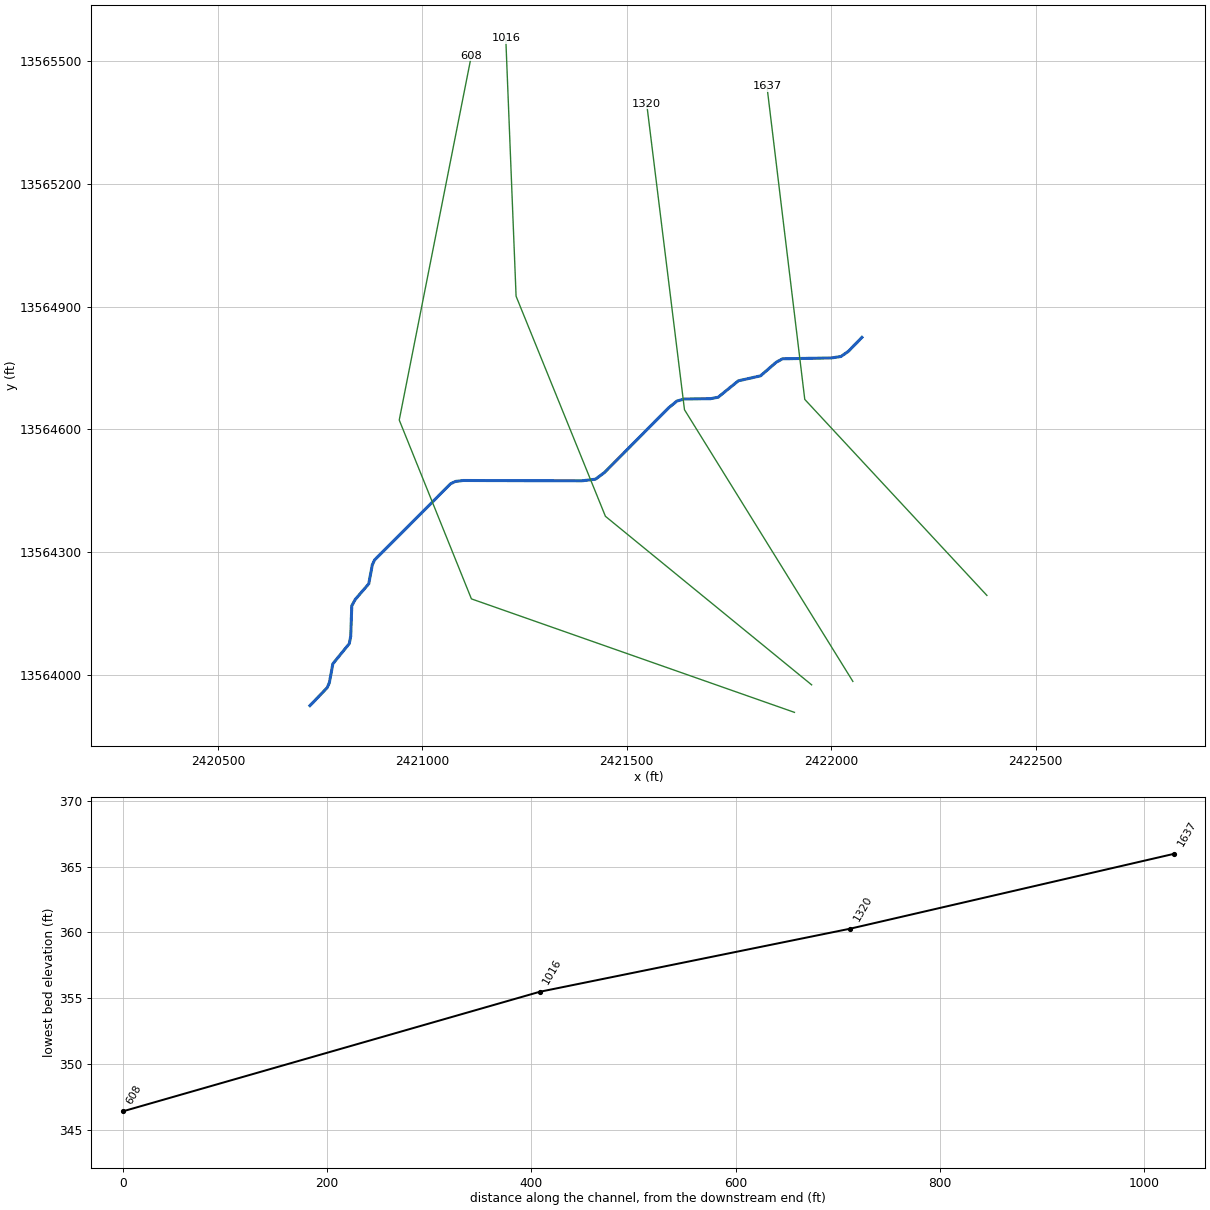
--- TRIB 1 TO LITTLE SALT CREEK.prj (project) ---

Proj Title=TRIB 1 TO LITTLE SALT CREEK Base Level Engineering
Current Plan=p01
Default Exp/Contr=0.3,0.1
English Units
Geom File=g01
Flow File=f01
Plan File=p01
BEGIN DESCRIPTION:
TRIB 1 TO LITTLE SALT CREEK
END DESCRIPTION:

--- TRIB 1 TO LITTLE SALT CREEK.p01 (plan) ---

Plan Title=Multiple Run
Short Identifier=Multiple
Geom File=g01
Flow File=f01
Subcritical Flow
K Sum by GR= 0
Std Step Tol= 0.01
Critical Tol= 0.01
Num of Std Step Trials= 20
Max Error Tol= 0.3
Flow Tol Ratio= 0.001
Split Flow NTrial= 30
Split Flow Tol= 0.02
Split Flow Ratio= 0.02
Log Output Level= 0
Friction Slope Method= 1
Unsteady Friction Slope Method= 2
Unsteady Bridges Friction Slope Method= 1
Parabolic Critical Depth
Global Vel Dist=  1 , 1 , 1
Global Log Level= 0
CheckData=True
Encroach Param= -1, 0, 0, 0
BEGIN DESCRIPTION:
Multiple Run
END DESCRIPTION:

--- TRIB 1 TO LITTLE SALT CREEK.f01 (steady flow) ---

Flow Title=Multiple
Number of Profiles=7
Profile Names=10-year,25-year,50-year,1pct_min,100-year,1pct_plu,500-year
River Rch & RM= TRIB 1 TO LITTLE,Reach-1,1637
     296     459     600     382     763    1523    1218
Boundary for River Rch & Prof#=TRIB 1 TO LITTLE,Reach-1,1
Up Type=0
Dn Type=3
Dn Slope=0.005
Boundary for River Rch & Prof#=TRIB 1 TO LITTLE,Reach-1,2
Up Type=0
Dn Type=3
Dn Slope=0.005
Boundary for River Rch & Prof#=TRIB 1 TO LITTLE,Reach-1,3
Up Type=0
Dn Type=3
Dn Slope=0.005
Boundary for River Rch & Prof#=TRIB 1 TO LITTLE,Reach-1,4
Up Type=0
Dn Type=3
Dn Slope=0.005
Boundary for River Rch & Prof#=TRIB 1 TO LITTLE,Reach-1,5
Up Type=0
Dn Type=3
Dn Slope=0.005
Boundary for River Rch & Prof#=TRIB 1 TO LITTLE,Reach-1,6
Up Type=0
Dn Type=3
Dn Slope=0.005
Boundary for River Rch & Prof#=TRIB 1 TO LITTLE,Reach-1,7
Up Type=0
Dn Type=3
Dn Slope=0.005

--- TRIB 1 TO LITTLE SALT CREEK.g01 (geometry) ---

Geom Title=Existing Conditions

River Reach=TRIB 1 TO LITTLE,Reach-1
Reach XY= 30
      2422075.00     13564825.00      2422042.06     13564791.09
      2422023.63     13564778.30      2422000.09     13564774.79
      2421880.93     13564772.76      2421865.33     13564764.20
      2421827.18     13564731.12      2421772.82     13564718.89
      2421723.41     13564678.83      2421704.90     13564675.24
      2421640.22     13564674.48      2421622.57     13564669.48
      2421601.48     13564652.12      2421445.16     13564494.60
      2421423.54     13564478.54      2421390.20     13564474.51
      2421099.88     13564475.30      2421080.85     13564472.94
      2421068.81     13564467.19      2420883.14     13564281.06
      2420877.50     13564268.97      2420868.86     13564222.83
      2420835.84     13564184.65      2420827.33     13564169.03
      2420824.77     13564095.09      2420821.18     13564076.58
      2420781.03     13564027.22      2420772.49     13563981.04
      2420767.09     13563968.85      2420725.00     13563925.00

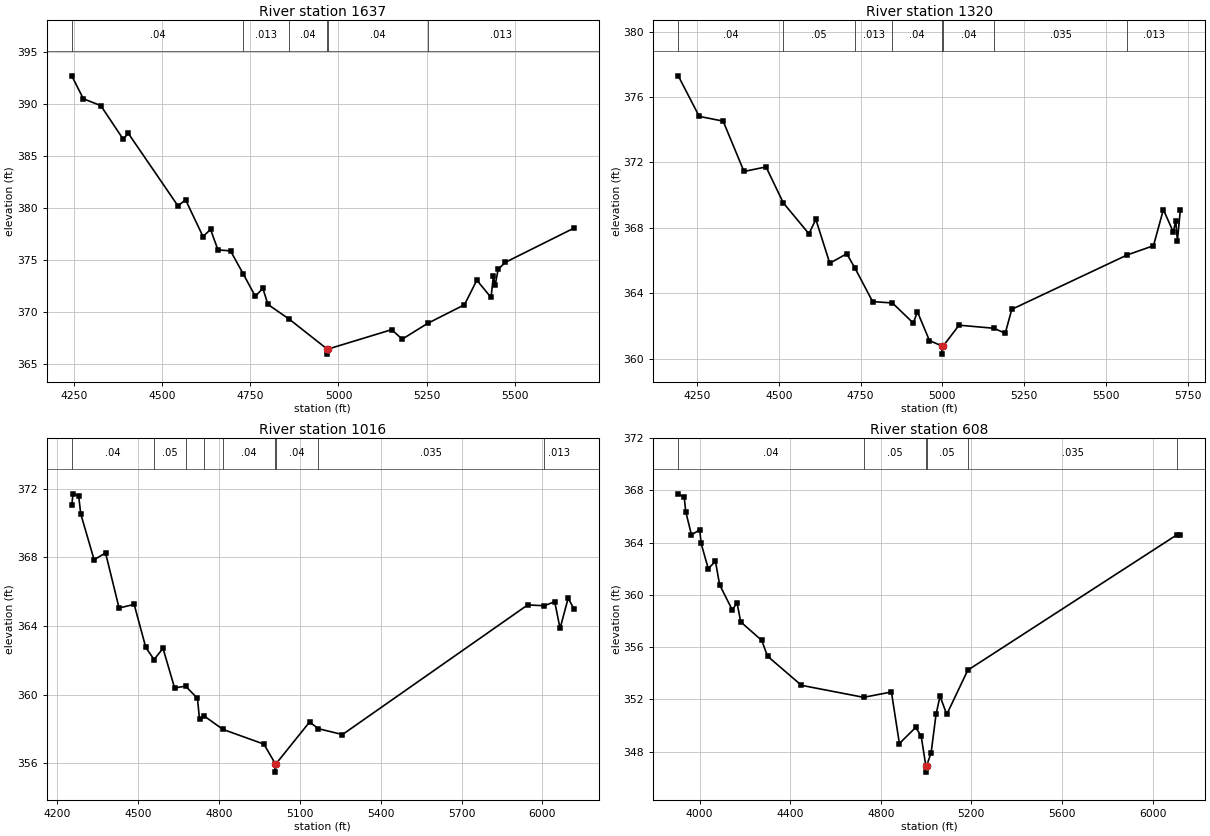
Type RM Length L Ch R = 1,1637,317,317,317
BEGIN DESCRIPTION:
LGII4626
END DESCRIPTION:
XS GIS Cut Line= 3
      2422380.72     13564194.41      2421935.26     13564673.49
      2421842.80     13565438.34
#Sta/Elev= 30
  4243.2  392.72  4275.9  390.52  4325.7  389.85  4389.2  386.62  4403.4  387.20
  4544.6  380.21  4566.1  380.80  4615.5  377.27  4637.0  377.95  4658.0  375.98
  4693.6  375.89  4729.6  373.68  4764.0  371.52  4785.5  372.29  4799.7  370.74
  4860.7  369.31  4967.4  366.46  4967.7  365.96  4971.4  366.46  5150.7  368.31
  5180.9  367.40  5253.1  368.92  5357.5  370.71  5392.5  373.07  5432.8  371.41
  5439.5  373.44  5444.5  372.57  5452.9  374.11  5473.1  374.78  5667.8  378.07
#Mann=6,-1,0
  4243.2    0.04       0  4729.6   0.013       0  4860.7    0.04       0
  4967.4    0.04       0  4971.4    0.04       0  5253.1   0.013       0
Bank Sta=4967.4,4971.4
Exp/Cntr=0.3,0.1

Type RM Length L Ch R = 1,1320,304,304,304
BEGIN DESCRIPTION:
LGII4625
END DESCRIPTION:
XS GIS Cut Line= 3
      2422052.94     13563984.22      2421641.07     13564648.27
      2421548.60     13565396.37
#Sta/Elev= 30
  4192.5  377.30  4256.6  374.82  4329.8  374.53  4393.6  371.45  4460.9  371.73
  4513.8  369.53  4592.1  367.64  4613.3  368.52  4655.8  365.84  4707.8  366.42
  4733.5  365.52  4786.9  363.49  4847.4  363.41  4911.2  362.18  4923.9  362.87
  4960.6  361.11  4998.8  360.78  4999.1  360.28  5002.8  360.78  5051.2  362.05
  5158.5  361.86  5192.3  361.55  5212.4  363.02  5565.8  366.35  5645.7  366.91
  5675.9  369.12  5706.2  367.75  5713.8  368.42  5718.8  367.22  5727.7  369.08
#Mann=8,-1,0
  4192.5    0.04       0  4513.8    0.05       0  4733.5   0.013       0
  4847.4    0.04       0  4998.8    0.04       0  5002.8    0.04       0
  5158.5   0.035       0  5565.8   0.013       0
Bank Sta=4998.8,5002.8
Exp/Cntr=0.3,0.1

Type RM Length L Ch R = 1,1016,408,408,408
BEGIN DESCRIPTION:
LGII4624
END DESCRIPTION:
XS GIS Cut Line= 4
      2421952.06     13563975.84      2421447.74     13564387.70
      2421229.20     13564925.65      2421203.98     13565556.07
#Sta/Elev= 30
  4253.9  371.04  4258.5  371.70  4279.3  371.60  4287.2  370.53  4336.8  367.86
  4379.2  368.26  4429.4  365.05  4485.4  365.26  4528.5  362.75  4559.2  362.05
  4592.4  362.70  4635.4  360.39  4675.9  360.50  4720.2  359.79  4727.8  358.57
  4745.9  358.75  4814.5  357.98  4966.9  357.12  5008.4  355.99  5008.6  355.49
  5012.4  355.99  5136.2  358.41  5168.6  358.02  5258.3  357.68  5945.4  365.23
  6007.2  365.18  6045.5  365.42  6065.5  363.86  6095.5  365.62  6116.6  365.01
#Mann=9,-1,0
  4253.9    0.04       0  4559.2    0.05       0  4675.9    0.04       0
  4745.9   0.013       0  4814.5    0.04       0  5008.4    0.04       0
  5012.4    0.04       0  5168.6   0.035       0  6007.2   0.013       0
Bank Sta=5008.4,5012.4
Exp/Cntr=0.3,0.1

Type RM Length L Ch R = 1,608,0,0,0
BEGIN DESCRIPTION:
LGII4623
END DESCRIPTION:
XS GIS Cut Line= 4
      2421910.02     13563908.60      2421119.93     13564185.97
      2420943.41     13564623.05      2421119.92     13565513.99
#Sta/Elev= 30
  3905.8  367.74  3932.3  367.46  3938.9  366.38  3964.1  364.60  4000.9  364.98
  4006.5  363.97  4038.3  362.01  4070.1  362.57  4088.6  360.77  4144.3  358.85
  4165.5  359.39  4181.6  357.93  4274.5  356.51  4300.2  355.30  4449.9  353.07
  4724.4  352.15  4847.2  352.56  4882.3  348.61  4954.5  349.85  4978.6  349.17
  4998.9  346.92  4999.2  346.42  5002.9  346.92  5022.5  347.91  5044.1  350.84
  5061.8  352.24  5091.4  350.84  5184.3  354.23  6108.7  364.61  6122.8  364.60
#Mann=6,-1,0
  3905.8    0.04       0  4724.4    0.05       0  4998.9    0.05       0
  5002.9    0.05       0  5184.3   0.035       0  6108.7   0.013       0
Bank Sta=4998.9,5002.9
Exp/Cntr=0.3,0.1

Chan Stop Cuts=-1