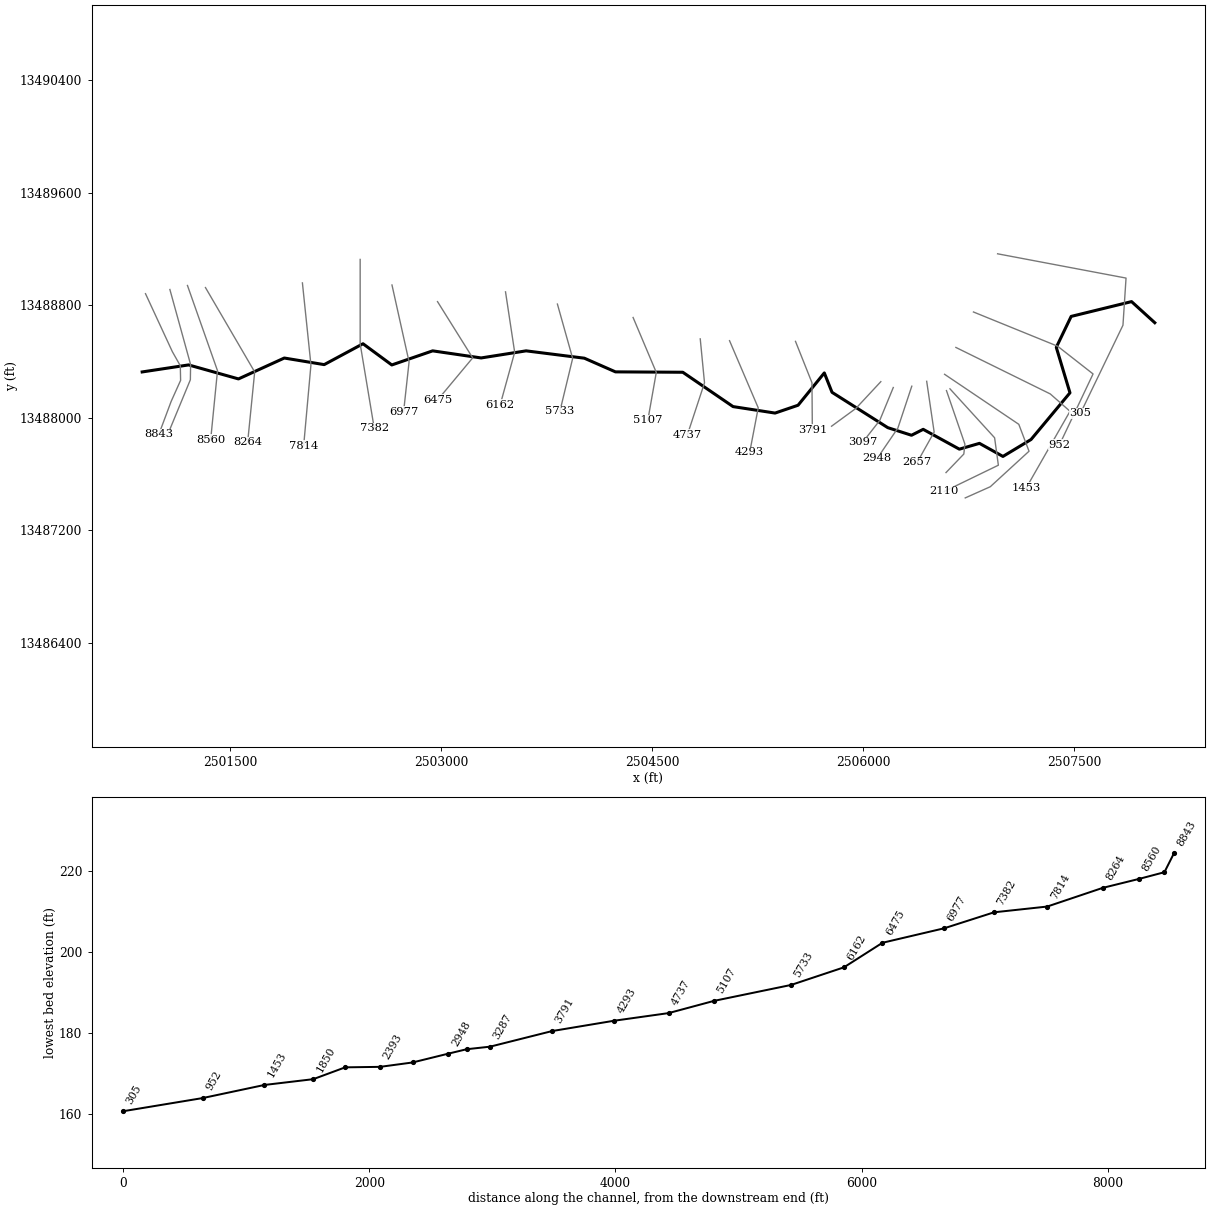
--- TRIB 1 TO MILBY CREEK.prj (project) ---

Proj Title=TRIB 1 TO MILBY CREEK Base Level Engineering
Current Plan=p01
Default Exp/Contr=0.3,0.1
English Units
Geom File=g01
Flow File=f01
Plan File=p01
Y Axis Title=Elevation
X Axis Title(PF)=Main Channel Distance
X Axis Title(XS)=Station
BEGIN DESCRIPTION:
TRIB 1 TO MILBY CREEK
END DESCRIPTION:
DSS Export Rating Curves= 0
DSS Export Rating Curve Sorted= 0
DSS Export Volume Flow Curves= 0
DXF OffsetX= 0
DXF OffsetY= 0
DXF ScaleX= 1
DXF ScaleY= 10

--- TRIB 1 TO MILBY CREEK.p01 (plan) ---

Plan Title=Multiple Run
Short Identifier=Multiple
Geom File=g01
Flow File=f01
Subcritical Flow
K Sum by GR= 0
Std Step Tol= 0.01
Critical Tol= 0.01
Num of Std Step Trials= 20
Max Error Tol= 0.3
Flow Tol Ratio= 0.001
Split Flow NTrial= 30
Split Flow Tol= 0.02
Split Flow Ratio= 0.02
Log Output Level= 0
Friction Slope Method= 1
Unsteady Friction Slope Method= 2
Unsteady Bridges Friction Slope Method= 1
Parabolic Critical Depth
Global Vel Dist=  1 , 1 , 1
Global Log Level= 0
CheckData=True
Encroach Param= -1, 0, 0, 0
BEGIN DESCRIPTION:
Multiple Run
END DESCRIPTION:

--- TRIB 1 TO MILBY CREEK.f01 (steady flow) ---

Flow Title=Multiple
Number of Profiles=7
Profile Names=10-year,25-year,50-year,1pct_min,100-year,1pct_plu,500-year
River Rch & RM= TRIB 1 TO MILBY ,Reach-1,8843
     433     683     903     580    1157    2309    1877
River Rch & RM= TRIB 1 TO MILBY ,Reach-1,5107
     575     915    1219     787    1569    3131    2571
Boundary for River Rch & Prof#=TRIB 1 TO MILBY ,Reach-1,1
Up Type=0
Dn Type=3
Dn Slope=0.005
Boundary for River Rch & Prof#=TRIB 1 TO MILBY ,Reach-1,2
Up Type=0
Dn Type=3
Dn Slope=0.005
Boundary for River Rch & Prof#=TRIB 1 TO MILBY ,Reach-1,3
Up Type=0
Dn Type=3
Dn Slope=0.005
Boundary for River Rch & Prof#=TRIB 1 TO MILBY ,Reach-1,4
Up Type=0
Dn Type=3
Dn Slope=0.005
Boundary for River Rch & Prof#=TRIB 1 TO MILBY ,Reach-1,5
Up Type=0
Dn Type=3
Dn Slope=0.005
Boundary for River Rch & Prof#=TRIB 1 TO MILBY ,Reach-1,6
Up Type=0
Dn Type=3
Dn Slope=0.005
Boundary for River Rch & Prof#=TRIB 1 TO MILBY ,Reach-1,7
Up Type=0
Dn Type=3
Dn Slope=0.005

--- TRIB 1 TO MILBY CREEK.g01 (geometry) ---

Geom Title=Existing Conditions
Program Version=4.10

River Reach=TRIB 1 TO MILBY ,Reach-1
Reach XY= 30
        2500875.       13488325.      2501204.96     13488374.95
      2501559.73     13488275.37      2501885.55      13488423.9
      2502169.14     13488377.06      2502445.16     13488525.47
      2502649.89     13488374.68      2502940.39     13488474.92
      2503285.19     13488424.55      2503604.97     13488474.93
      2504019.06     13488422.74      2504240.22     13488325.52
      2504719.07     13488322.76      2505076.46     13488078.54
        2505375.     13488032.56      2505538.65     13488088.26
      2505725.24     13488318.03      2505780.11     13488180.12
      2506176.58     13487928.82      2506345.21     13487874.79
      2506428.29      13487916.9      2506685.49     13487775.95
      2506828.41     13487817.19      2506995.33     13487724.22
      2507195.16     13487844.63      2507471.89     13488176.65
       2507374.6       13488500.      2507480.41     13488719.83
      2507909.79      13488825.1        2508075.       13488675.

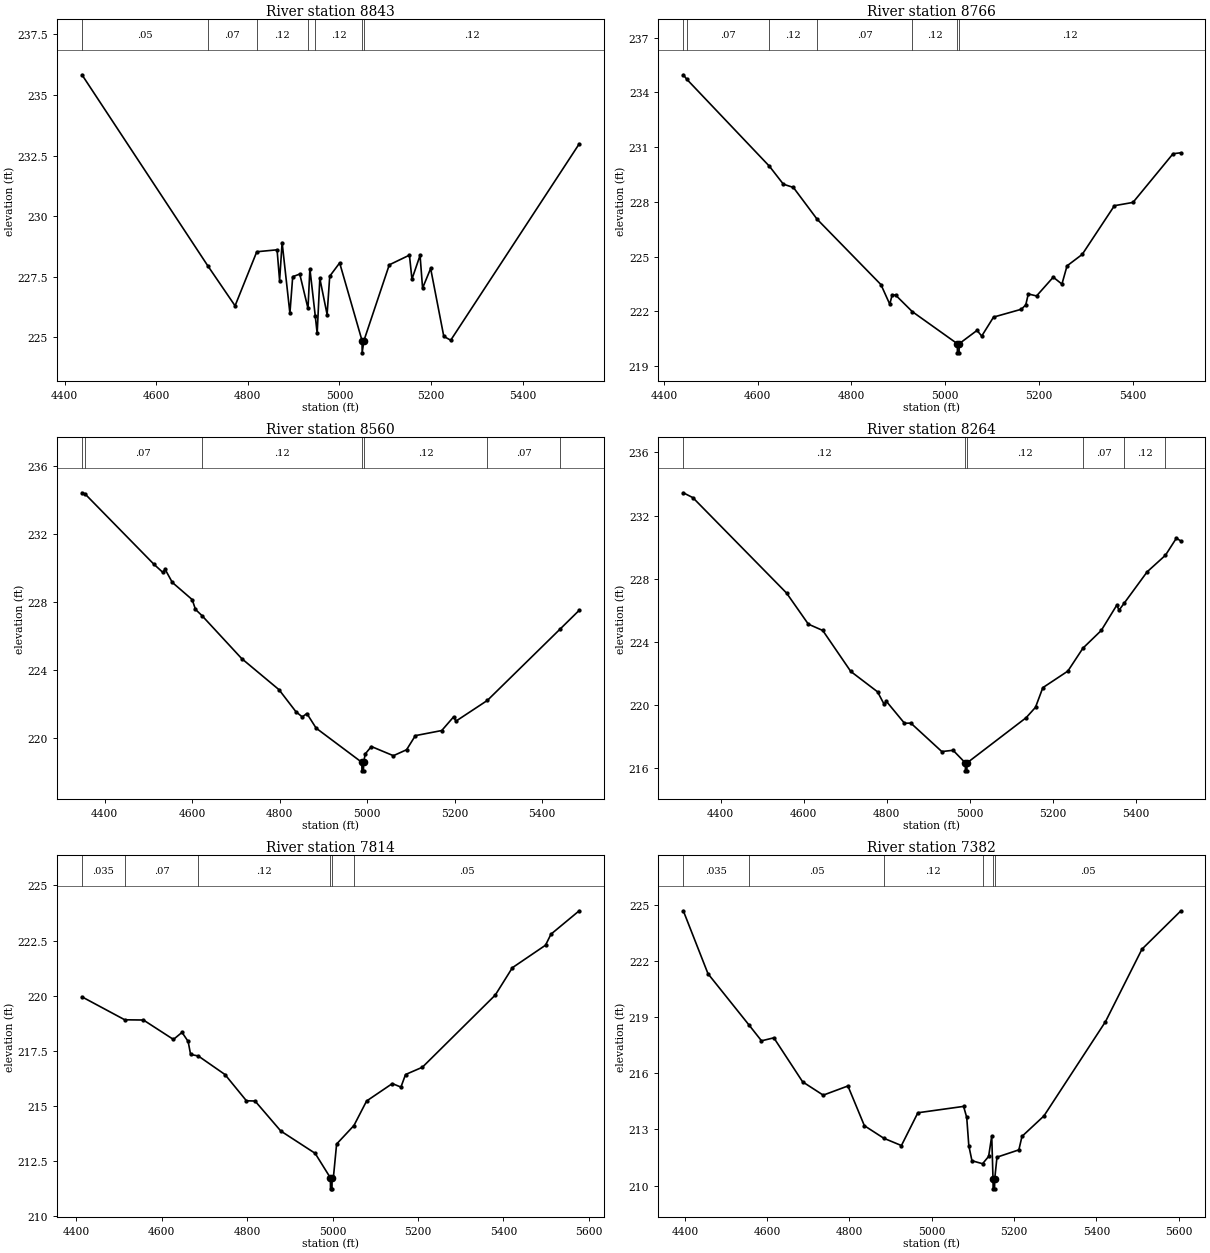
Type RM Length L Ch R = 1 ,8843    ,77,77,77
BEGIN DESCRIPTION:
Mapping XS 0bc45add
END DESCRIPTION:
XS GIS Cut Line= 6
      2500898.69     13488881.42      2501089.68     13488469.06
       2501146.1     13488369.23      2501148.27     13488265.06
        2501081.     13488115.32      2500994.18     13487883.08
#Sta/Elev= 30
    4438  235.83  4712.3  227.96  4772.2   226.3  4819.6  228.53  4863.9  228.61
  4869.4  227.34  4874.9  228.91  4891.9  225.99    4898   227.5  4913.4  227.61
  4931.4  226.19  4935.5  227.83  4947.2  225.89  4951.4  225.16  4957.2  227.43
  4973.1  225.94  4978.8  227.52  5000.5  228.07  5049.4  224.86  5049.6  224.36
  5053.4  224.86  5108.8  227.99  5152.8  228.39  5158.3   227.4    5176  228.38
  5181.5  227.03  5199.1  227.84  5227.8  225.04  5242.9  224.88  5523.4  232.98
#Mann= 7 ,-1 , 0
    4438     .05       0  4712.3     .07       0  4819.6     .12       0
  4931.4     .07       0  4947.2     .12       0  5049.4     .05       0
  5053.4     .12       0
Bank Sta=5049.4,5053.4
XS Rating Curve= 0 ,0
Exp/Cntr=0.3,0.1

Type RM Length L Ch R = 1 ,8766    ,206,206,206
BEGIN DESCRIPTION:
Mapping XS 1ee44aa7
END DESCRIPTION:
XS GIS Cut Line= 4
      2501072.04     13488911.21      2501219.35     13488377.62
      2501217.71      13488269.6      2501065.48     13487901.31
#Sta/Elev= 30
  4441.5  234.97  4448.7  234.73  4625.2  229.95  4654.8  228.97  4676.2  228.79
  4726.7  227.05  4862.9  223.46  4881.6  222.39  4886.8  222.89    4894  222.89
  4929.7  221.98  5025.7  220.22  5025.9  219.72  5029.4  219.72  5029.7  220.22
  5067.7  220.95  5077.7  220.64  5102.9  221.68  5162.2  222.11  5171.6  222.35
    5177  222.95  5194.6  222.84  5230.2  223.87  5248.7  223.49  5259.6  224.49
    5292  225.12  5360.6  227.79  5400.2  227.97  5485.6  230.64  5501.6  230.69
#Mann= 7 ,-1 , 0
  4441.5     .05       0  4448.7     .07       0  4625.2     .12       0
  4726.7     .07       0  4929.7     .12       0  5025.7     .05       0
  5029.7     .12       0
Bank Sta=5025.7,5029.7
XS Rating Curve= 0 ,0
Exp/Cntr=0.3,0.1

Type RM Length L Ch R = 1 ,8560    ,296,296,296
BEGIN DESCRIPTION:
Mapping XS 78845526
END DESCRIPTION:
XS GIS Cut Line= 3
      2501197.05      13488939.7      2501410.59     13488333.79
      2501361.98     13487842.42
#Sta/Elev= 30
  4348.2  234.42  4354.9  234.36  4512.5  230.22  4532.9  229.74  4538.2  229.92
  4554.6  229.15    4600  228.14  4607.6  227.56  4622.3   227.2  4713.2  224.67
  4798.5  222.84    4837  221.55  4851.5  221.24  4862.1  221.44  4883.3  220.58
  4987.7  218.57    4988  218.07  4991.5  218.07  4991.7  218.57  4995.6  219.07
  5009.5   219.5  5059.8  218.96  5089.9  219.31    5110  220.14  5170.3  220.44
  5197.6  221.25  5202.6  220.99  5274.5  222.21  5440.5   226.4  5484.4  227.51
#Mann= 7 ,-1 , 0
  4348.2     .05       0  4354.9     .07       0  4622.3     .12       0
  4987.7     .05       0  4991.7     .12       0  5274.5     .07       0
  5440.5     .12       0
Bank Sta=4987.7,4991.7
XS Rating Curve= 0 ,0
Exp/Cntr=0.3,0.1

Type RM Length L Ch R = 1 ,8264    ,450,450,450
BEGIN DESCRIPTION:
TRIB 1 TO MILBY CREEK 16.0
END DESCRIPTION:
XS GIS Cut Line= 3
        2501325.     13488924.99        2501675.       13488325.
        2501625.     13487825.01
#Sta/Elev= 30
    4310  233.44  4333.1  233.13  4558.5   227.1    4611  225.13  4645.7  224.73
  4713.1  222.14  4777.6  220.85  4793.3  220.07  4799.1  220.24  4842.5  218.86
  4857.8  218.87  4932.3  217.07  4959.5  217.15    4989  216.35  4989.2  215.85
  4992.7  215.85    4993  216.35  5135.3  219.21  5157.9  219.87  5175.5  221.11
  5235.8  222.16  5272.1  223.61  5316.2  224.73  5353.8  226.34  5358.9  226.01
  5371.5  226.46  5426.7  228.44  5470.8  229.49  5497.1  230.57  5507.1   230.4
#Mann= 6 ,-1 , 0
    4310     .12       0    4989     .05       0    4993     .12       0
  5272.1     .07       0  5371.5     .12       0  5470.8     .07       0
Bank Sta=4989,4993
XS Rating Curve= 0 ,0
Exp/Cntr=0.3,0.1

Type RM Length L Ch R = 1 ,7814    ,432,432,432
BEGIN DESCRIPTION:
TRIB 1 TO MILBY CREEK 15.0
END DESCRIPTION:
XS GIS Cut Line= 3
      2502014.37     13488958.08        2502075.       13488375.
      2502023.13     13487799.15
#Sta/Elev= 30
  4413.3  219.95  4513.5  218.91  4557.2   218.9  4627.5  218.02  4647.6  218.34
  4661.9  217.93  4667.7  217.34  4685.7  217.27  4748.2  216.43  4798.4  215.24
  4818.6  215.23  4878.9  213.87  4959.3  212.86    4995  211.75  4995.3  211.25
  4998.8  211.25    4999  211.75    5002  211.75  5009.6  213.28  5050.2  214.12
  5079.8  215.23  5140.1  216.02  5160.2  215.86    5171  216.43  5210.4  216.76
  5381.1  220.03  5421.2  221.27  5498.8  222.29  5511.6  222.79  5577.7  223.85
#Mann= 6 ,-1 , 0
  4413.3    .035       0  4513.5     .07       0  4685.7     .12       0
    4995     .05       0    4999     .12       0  5050.2     .05       0
Bank Sta=4995,4999
XS Rating Curve= 0 ,0
Exp/Cntr=0.3,0.1

Type RM Length L Ch R = 1 ,7382    ,405,405,405
BEGIN DESCRIPTION:
TRIB 1 TO MILBY CREEK 14.0
END DESCRIPTION:
XS GIS Cut Line= 3
        2502425.     13489125.01        2502425.       13488525.
        2502525.     13487924.99
#Sta/Elev= 30
  4396.3  224.67  4456.3  221.31  4556.1  218.57  4586.3  217.73  4616.3  217.89
  4686.3  215.54  4736.3  214.83  4796.3  215.32  4836.3   213.2  4883.5  212.53
  4926.3  212.14  4966.3  213.89  5077.4  214.23    5085  213.64  5090.1  212.13
  5097.7  211.33  5123.5  211.17  5138.2  211.56  5145.8  212.65  5148.9  210.33
  5149.2  209.83  5152.7  209.83  5152.9  210.33  5158.5  211.52  5211.7  211.91
  5219.3  212.63  5272.6  213.72  5422.1  218.75  5510.8  222.62  5604.6  224.65
#Mann= 6 ,-1 , 0
  4396.3    .035       0  4556.1     .05       0  4883.5     .12       0
  5123.5     .05       0  5148.9     .05       0  5152.9     .05       0
Bank Sta=5148.9,5152.9
XS Rating Curve= 0 ,0
Exp/Cntr=0.3,0.1

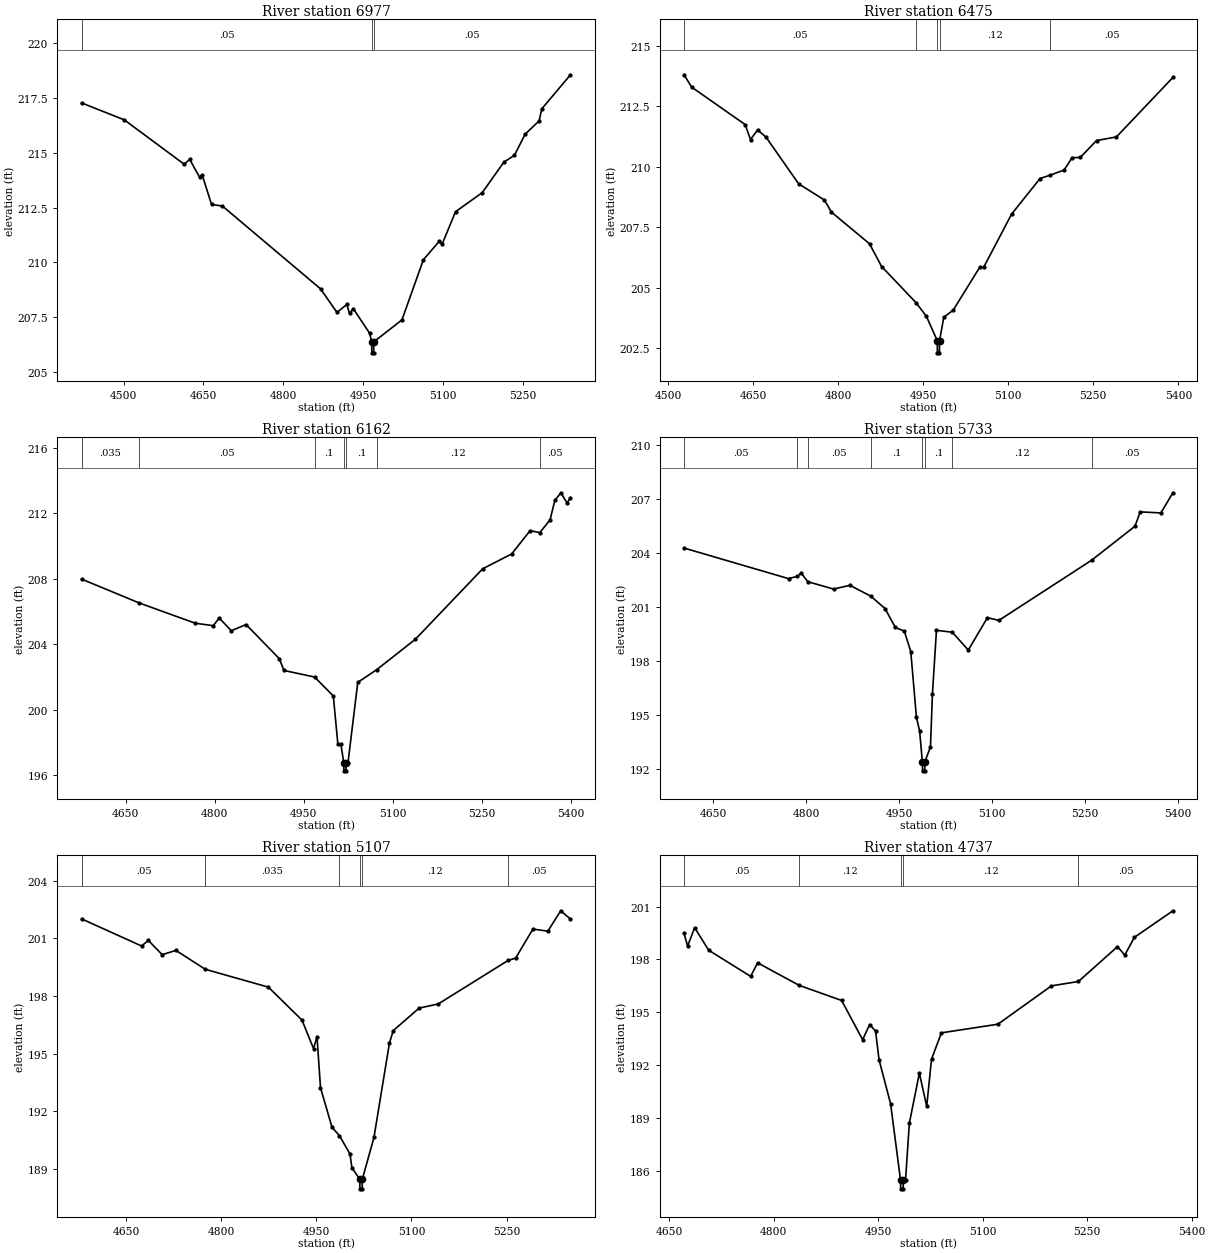
Type RM Length L Ch R = 1 ,6977    ,502,502,502
BEGIN DESCRIPTION:
Mapping XS c88c087b
END DESCRIPTION:
XS GIS Cut Line= 3
      2502651.22     13488943.24      2502772.75     13488396.36
      2502733.68     13488040.42
#Sta/Elev= 30
  4421.1  217.26  4501.3  216.49  4613.9  214.47  4624.2  214.69  4642.8  213.88
  4647.9  213.97  4665.2  212.64  4685.6  212.57    4870   208.8  4900.8  207.73
  4919.3  208.09  4924.5  207.68  4931.5   207.9  4962.2  206.78    4966  206.39
  4966.3  205.89  4969.8  205.89    4970  206.39  5022.9  207.39  5063.2  210.13
  5093.2  210.97  5098.3  210.83  5123.5  212.31  5173.8  213.18  5214.1  214.56
  5234.2  214.88  5254.3  215.84  5280.5  216.44  5285.5  216.99  5339.4  218.54
#Mann= 3 ,-1 , 0
  4421.1     .05       0    4966     .05       0    4970     .05       0
Bank Sta=4966,4970
XS Rating Curve= 0 ,0
Exp/Cntr=0.3,0.1

Type RM Length L Ch R = 1 ,6475    ,313,313,313
BEGIN DESCRIPTION:
TRIB 1 TO MILBY CREEK 12.0
END DESCRIPTION:
XS GIS Cut Line= 3
      2502975.01     13488824.99        2503225.       13488425.
        2502975.       13488125.
#Sta/Elev= 30
  4528.2  213.81  4541.7   213.3  4636.1  211.75  4645.5  211.13  4657.9  211.53
  4672.6  211.24  4730.4   209.3  4775.8  208.63  4788.2  208.13  4855.4  206.82
  4876.7  205.88  4937.6  204.38  4955.7  203.82  4974.9  202.81  4975.1  202.31
  4978.6  202.31  4978.9  202.81  4986.3  203.78  5003.1  204.08    5050  205.86
  5056.5  205.84    5106  208.05  5156.1  209.52  5174.1  209.66  5198.4  209.87
  5212.7  210.38    5227  210.39  5255.7  211.09  5290.8  211.24  5390.4   213.7
#Mann= 5 ,-1 , 0
  4528.2     .05       0  4937.6     .12       0  4974.9     .05       0
  4978.9     .12       0  5174.1     .05       0
Bank Sta=4974.9,4978.9
XS Rating Curve= 0 ,0
Exp/Cntr=0.3,0.1

Type RM Length L Ch R = 1 ,6162    ,429,429,429
BEGIN DESCRIPTION:
Mapping XS 8bff1b22
END DESCRIPTION:
XS GIS Cut Line= 3
      2503458.51     13488894.41      2503523.62     13488464.72
      2503420.11     13488089.53
#Sta/Elev= 30
  4575.9  207.98    4673  206.52  4767.5  205.28  4797.8  205.13  4807.9   205.6
  4828.2  204.82  4853.1   205.2  4909.1  203.11  4916.9  202.39  4968.5  201.99
  5000.1  200.83  5007.8  197.88  5012.9  197.88  5017.7  196.75    5018  196.25
  5021.5  196.25  5021.7  196.75  5024.9  196.76  5041.3  201.66  5073.3  202.44
  5138.4   204.3  5251.8  208.61  5300.7  209.52  5331.8  210.95  5347.9  210.82
  5365.3   211.6  5373.3  212.79  5383.6  213.26    5394  212.63  5399.7  212.97
#Mann= 7 ,-1 , 0
  4575.9    .035       0    4673     .05       0  4968.5      .1       0
  5017.7     .05       0  5021.7      .1       0  5073.3     .12       0
  5347.9     .05       0
Bank Sta=5017.7,5021.7
XS Rating Curve= 0 ,0
Exp/Cntr=0.3,0.1

Type RM Length L Ch R = 1 ,5733    ,626,626,626
BEGIN DESCRIPTION:
Mapping XS d993e4b2
END DESCRIPTION:
XS GIS Cut Line= 3
      2503827.43     13488807.62      2503935.94     13488421.32
       2503844.8     13488043.72
#Sta/Elev= 30
  4602.7  204.29  4771.6  202.59    4786  202.72  4792.1   202.9  4802.6  202.42
  4844.3  202.01  4870.7  202.22  4904.2  201.62  4927.4  200.93    4944  199.88
  4958.6  199.67    4969  198.54  4978.1  194.89  4983.3  194.12  4987.7  192.41
    4988  191.91  4991.5  191.91  4991.7  192.41  5000.8  193.23    5004   196.2
  5010.5  199.72  5036.2  199.61  5061.9  198.62  5092.8  200.42  5111.3  200.27
    5261  203.61  5331.1   205.5  5339.6   206.3  5372.9  206.24  5392.4  207.36
#Mann= 8 ,-1 , 0
  4602.7     .05       0    4786    .035       0  4802.6     .05       0
  4904.2      .1       0  4987.7     .05       0  4991.7      .1       0
  5036.2     .12       0    5261     .05       0
Bank Sta=4987.7,4991.7
XS Rating Curve= 0 ,0
Exp/Cntr=0.3,0.1

Type RM Length L Ch R = 1 ,5107    ,370,370,370
BEGIN DESCRIPTION:
Mapping XS 16c2fb3a
END DESCRIPTION:
XS GIS Cut Line= 3
      2504365.63     13488712.12      2504530.56     13488321.49
      2504470.01     13487979.83
#Sta/Elev= 30
  4579.8  202.01  4674.4   200.6  4685.2  200.89  4706.9  200.15  4728.6  200.37
  4774.9  199.39  4874.5  198.46  4927.4  196.75  4945.6  195.27  4951.1  195.88
  4956.6  193.24  4974.8  191.17  4986.4  190.75  5003.1  189.79  5006.2  189.07
  5018.6  188.48  5018.8  187.98  5022.3  187.98  5022.6  188.48  5040.9  190.65
  5065.3  195.55  5071.3   196.2    5112  197.37  5142.4  197.59  5252.5  199.85
  5264.3  199.97  5291.6  201.48  5315.1  201.37  5335.4  202.43  5350.8     202
#Mann= 6 ,-1 , 0
  4579.8     .05       0  4774.9    .035       0  4986.4     .12       0
  5018.6     .05       0  5022.6     .12       0  5252.5     .05       0
Bank Sta=5018.6,5022.6
XS Rating Curve= 0 ,0
Exp/Cntr=0.3,0.1

Type RM Length L Ch R = 1 ,4737    ,444,444,444
BEGIN DESCRIPTION:
Mapping XS 0115f5dc
END DESCRIPTION:
XS GIS Cut Line= 3
      2504843.06     13488560.22      2504873.44     13488247.71
       2504752.1     13487879.36
#Sta/Elev= 30
  4671.2  199.49  4676.4  198.76  4686.5  199.81  4706.6  198.53  4766.9  197.04
  4776.9  197.81  4836.5  196.53  4897.5  195.67  4927.6  193.44  4937.7   194.3
  4946.2  193.93  4951.2   192.3  4967.8  189.79    4982  185.46  4982.3  184.96
  4985.8  184.96    4986  185.46  4989.2  185.46  4994.7   188.7  5009.1  191.54
  5019.6  189.65  5026.5  192.33  5040.7  193.83  5121.8  194.32  5198.6   196.5
  5237.4  196.75  5293.4  198.73  5303.9  198.25  5317.7  199.26    5373  200.77
#Mann= 5 ,-1 , 0
  4671.2     .05       0  4836.5     .12       0    4982     .05       0
    4986     .12       0  5237.4     .05       0
Bank Sta=4982,4986
XS Rating Curve= 0 ,0
Exp/Cntr=0.3,0.1

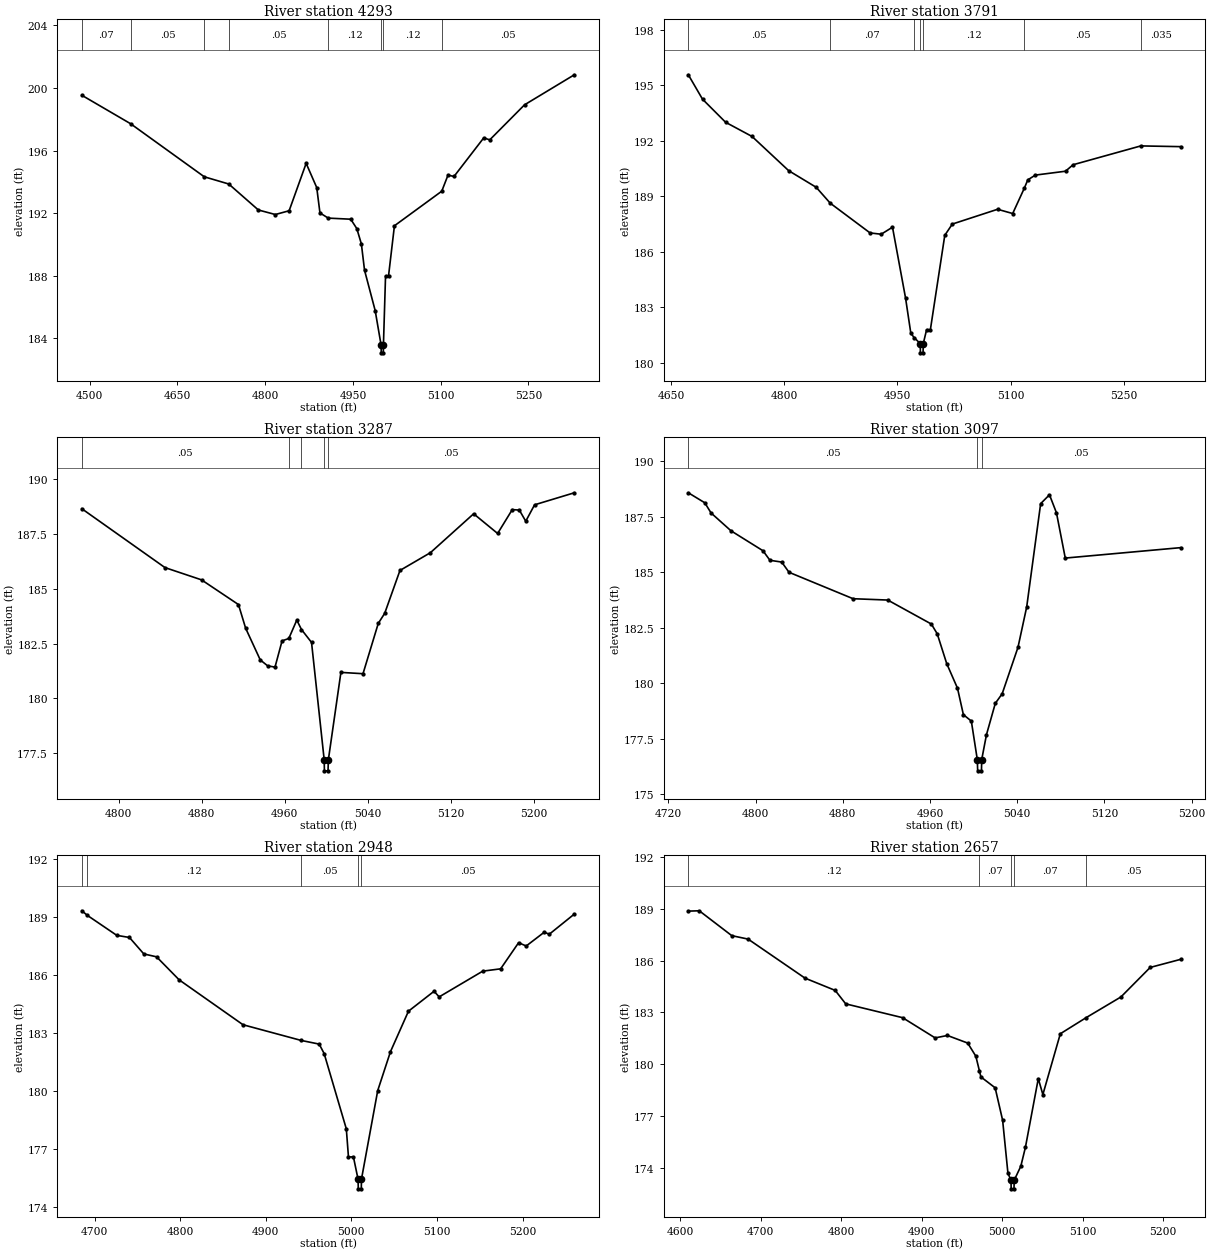
Type RM Length L Ch R = 1 ,4293    ,502,502,502
BEGIN DESCRIPTION:
Mapping XS cfdc4327
END DESCRIPTION:
XS GIS Cut Line= 3
      2505051.38     13488547.23      2505255.39     13488069.76
      2505194.63     13487752.96
#Sta/Elev= 30
  4486.7  199.53  4570.1  197.71    4696  194.32  4737.8  193.86  4788.4   192.2
  4817.4  191.91    4841  192.15  4870.1  195.18  4888.2  193.63  4893.7  192.01
  4907.9  191.68  4946.3  191.61  4956.7  191.01  4964.5  190.03  4969.9  188.35
  4988.1  185.77  4998.2  183.57  4998.5  183.07    5002  183.07  5002.2  183.57
  5005.8  187.98  5010.9  187.98    5021  191.19  5101.9   193.4  5112.6  194.43
  5122.8  194.34  5173.7  196.81  5183.9  196.68  5243.4  198.92  5328.5  200.84
#Mann= 8 ,-1 , 0
  4486.7     .07       0  4570.1     .05       0    4696     .12       0
  4737.8     .05       0  4907.9     .12       0  4998.2     .05       0
  5002.2     .12       0  5101.9     .05       0
Bank Sta=4998.2,5002.2
XS Rating Curve= 0 ,0
Exp/Cntr=0.3,0.1

Type RM Length L Ch R = 1 ,3791    ,504,504,504
BEGIN DESCRIPTION:
Mapping XS 873826a1
END DESCRIPTION:
XS GIS Cut Line= 3
      2505520.31     13488542.43       2505637.5     13488248.14
      2505640.11     13487912.22
#Sta/Elev= 30
  4672.9  195.58  4691.7  194.26  4722.3  193.01  4757.4  192.24  4805.9  190.39
  4842.4  189.49    4861  188.63  4913.8  187.02  4928.5  186.95  4943.5  187.33
  4960.8   183.5  4967.8  181.59  4972.1  181.36  4980.3  181.03  4980.5  180.53
    4984  180.53  4984.3  181.03  4988.7  181.78  4993.7  181.78  5012.8  186.89
  5022.8   187.5  5082.8   188.3  5102.8  188.07  5118.2  189.44  5122.8  189.89
  5132.8  190.15  5172.8  190.36  5182.8  190.71  5272.6  191.73  5325.6  191.69
#Mann= 7 ,-1 , 0
  4672.9     .05       0    4861     .07       0  4972.1     .12       0
  4980.3     .05       0  4984.3     .12       0  5118.2     .05       0
  5272.6    .035       0
Bank Sta=4980.3,4984.3
XS Rating Curve= 0 ,0
Exp/Cntr=0.3,0.1

Type RM Length L Ch R = 1 ,3287    ,190,190,190
BEGIN DESCRIPTION:
Mapping XS e669f159
END DESCRIPTION:
XS GIS Cut Line= 3
      2506127.08     13488255.95        2505950.     13488065.85
       2505776.7      13487939.1
#Sta/Elev= 30
  4764.4  188.66  4844.5  185.97  4879.7  185.41  4915.3  184.28  4922.2   183.2
  4936.3  181.75  4943.4  181.48  4950.5  181.42  4957.3  182.62  4963.8  182.73
  4971.5  183.57    4976  183.14  4985.7  182.55  4997.9  177.18  4998.1  176.68
  5001.6  176.68  5001.9  177.18    5014  181.18  5035.3  181.12    5050  183.42
  5056.2  183.88  5070.9  185.84  5100.2  186.65  5141.9  188.43    5165  187.53
  5179.1  188.62  5185.9   188.6  5192.1  188.09  5200.6  188.84  5238.9  189.39
#Mann= 5 ,-1 , 0
  4764.4     .05       0  4963.8     .12       0    4976     .05       0
  4997.9     .05       0  5001.9     .05       0
Bank Sta=4997.9,5001.9
XS Rating Curve= 0 ,0
Exp/Cntr=0.3,0.1

Type RM Length L Ch R = 1 ,3097    ,149,149,149
BEGIN DESCRIPTION:
Mapping XS fce13c91
END DESCRIPTION:
XS GIS Cut Line= 3
      2506215.63     13488214.29      2506119.27     13487979.91
      2505996.87     13487823.66
#Sta/Elev= 30
  4738.2  188.57  4753.3  188.12  4759.1  187.66  4777.3  186.86  4806.7  185.96
  4813.1  185.53  4823.9  185.45  4830.6  184.99  4889.4   183.8  4921.2  183.74
  4961.2  182.66  4966.6  182.22  4975.3  180.88  4985.2  179.77  4990.6  178.58
  4997.9  178.29  5003.4  176.55  5003.7  176.05  5007.2  176.05  5007.4  176.55
  5011.8  177.68  5019.9  179.09  5026.2  179.52  5040.7  181.61  5048.7  183.43
  5061.5  188.08  5069.6  188.48    5076  187.67  5084.1  185.63  5190.1   186.1
#Mann= 3 ,-1 , 0
  4738.2     .05       0  5003.4     .05       0  5007.4     .05       0
Bank Sta=5003.4,5007.4
XS Rating Curve= 0 ,0
Exp/Cntr=0.3,0.1

Type RM Length L Ch R = 1 ,2948    ,291,291,291
BEGIN DESCRIPTION:
Mapping XS 20fb9f9f
END DESCRIPTION:
XS GIS Cut Line= 3
      2506347.24     13488223.72       2506248.4      13487926.1
      2506100.86     13487709.83
#Sta/Elev= 30
  4685.1  189.33  4691.6  189.09  4725.9  188.06  4740.7  187.95  4757.5   187.1
  4772.4  186.95  4798.8  185.76  4873.4  183.44  4941.3  182.63  4962.4  182.44
  4968.2  181.95  4994.1  178.06  4996.6  176.61  5002.4  176.61  5007.8  175.46
  5008.1  174.96  5011.6  174.96  5011.8  175.46  5030.8  180.04  5045.7  182.05
  5066.7  184.14  5096.6  185.17  5102.6  184.88  5153.5  186.21  5174.4  186.33
  5195.4  187.68  5204.3  187.51  5225.3  188.22  5231.3  188.12  5260.5  189.16
#Mann= 5 ,-1 , 0
  4685.1     .05       0  4691.6     .12       0  4941.3     .05       0
  5007.8     .05       0  5011.8     .05       0
Bank Sta=5007.8,5011.8
XS Rating Curve= 0 ,0
Exp/Cntr=0.3,0.1

Type RM Length L Ch R = 1 ,2657    ,264,264,264
BEGIN DESCRIPTION:
Mapping XS f15472b2
END DESCRIPTION:
XS GIS Cut Line= 3
      2506453.15     13488258.47      2506506.21     13487897.45
      2506385.45     13487681.87
#Sta/Elev= 30
  4609.9  188.86  4623.5  188.88  4663.9  187.44  4684.2  187.24  4754.9  184.98
  4792.4  184.27  4805.5  183.49  4876.2  182.69  4916.6  181.52  4931.9  181.66
  4957.1  181.22  4967.2  180.46  4971.6  179.62  4973.5  179.26  4991.2  178.63
  5000.5  176.75  5007.1  173.68  5010.9  173.28  5011.1  172.78  5014.6  172.78
  5014.9  173.28  5023.1  174.09  5028.8  175.18  5044.8  179.16  5050.5  178.24
  5072.2  181.76  5104.2  182.69  5147.5  183.89  5183.9   185.6  5221.9  186.07
#Mann= 5 ,-1 , 0
  4609.9     .12       0  4971.6     .07       0  5010.9     .05       0
  5014.9     .07       0  5104.2     .05       0
Bank Sta=5010.9,5014.9
XS Rating Curve= 0 ,0
Exp/Cntr=0.3,0.1

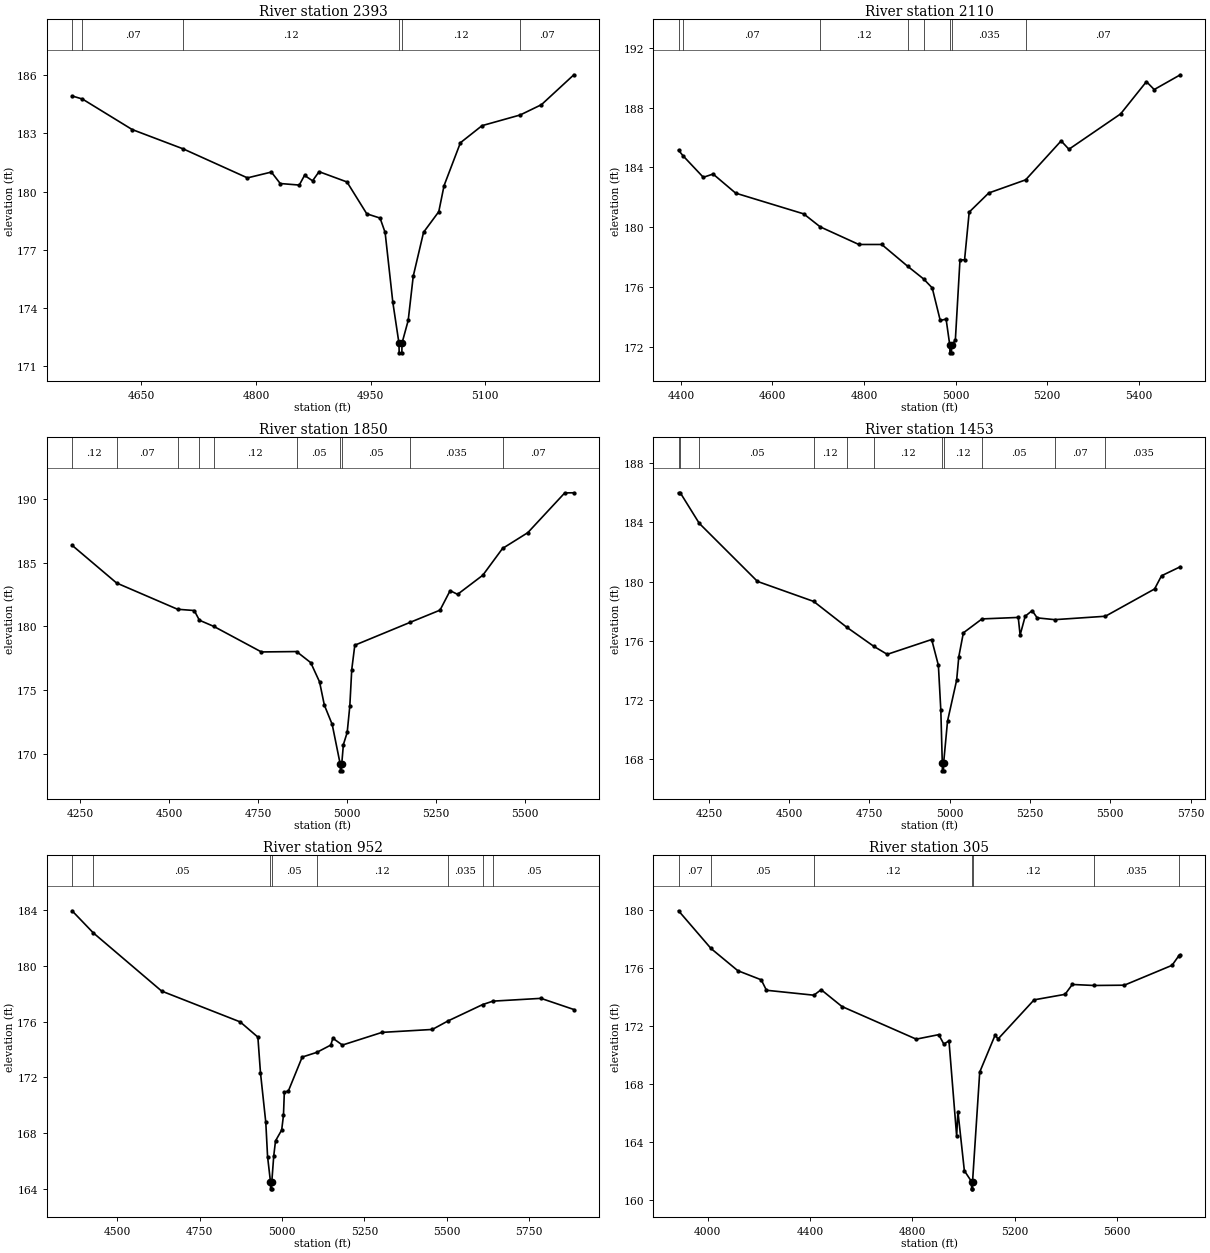
Type RM Length L Ch R = 1 ,2393    ,283,283,283
BEGIN DESCRIPTION:
Mapping XS 435d5069
END DESCRIPTION:
XS GIS Cut Line= 4
      2506593.77      13488192.5      2506724.96     13487811.51
      2506717.15      13487741.2      2506590.56     13487609.45
#Sta/Elev= 30
  4559.5  184.93  4573.1  184.77  4638.1   183.2  4705.1   182.2  4788.9  180.71
  4820.2  181.01  4831.8  180.42  4856.7  180.34  4863.6  180.84  4874.1  180.56
  4882.6  181.03  4919.1   180.5    4945  178.86  4962.4  178.64    4969   177.9
  4979.1   174.3  4987.1   172.2  4987.4   171.7  4990.9   171.7  4991.1   172.2
  4999.2  173.37  5005.8  175.65  5019.3  177.91  5039.2  178.97  5046.1  180.31
  5067.5  182.52  5095.8   183.4  5145.7  183.95  5173.5  184.48  5215.9  186.02
#Mann= 6 ,-1 , 0
  4559.5     .12       0  4573.1     .07       0  4705.1     .12       0
  4987.1     .05       0  4991.1     .12       0  5145.7     .07       0
Bank Sta=4987.1,4991.1
XS Rating Curve= 0 ,0
Exp/Cntr=0.3,0.1

Type RM Length L Ch R = 1 ,2110    ,260,260,260
BEGIN DESCRIPTION:
Mapping XS a6352d9e
END DESCRIPTION:
XS GIS Cut Line= 4
      2506618.59     13488204.99      2506936.05     13487856.93
      2506962.82     13487661.87      2506578.26     13487475.31
#Sta/Elev= 30
    4395  185.16  4404.6  184.79  4449.1  183.34  4470.4  183.56  4519.7  182.28
  4668.3  180.89  4704.3  180.02  4788.6  178.84  4838.6  178.84  4895.6  177.37
    4930  176.53  4948.8  175.93  4966.3  173.75  4979.1  173.84  4987.2  172.08
  4987.4  171.58  4990.9  171.58  4991.2  172.08  4999.3  172.44  5009.4  177.81
  5019.4  177.81  5029.5  181.01  5072.2  182.29  5152.7  183.17  5230.2  185.78
  5247.2  185.22  5360.1  187.59  5416.4  189.75  5433.4  189.22  5490.4  190.21
#Mann= 8 ,-1 , 0
    4395     .12       0  4404.6     .07       0  4704.3     .12       0
  4895.6     .05       0    4930    .035       0  4987.2    .035       0
  4991.2    .035       0  5152.7     .07       0
Bank Sta=4987.2,4991.2
XS Rating Curve= 0 ,0
Exp/Cntr=0.3,0.1

Type RM Length L Ch R = 1 ,1850    ,397,397,397
BEGIN DESCRIPTION:
Mapping XS 59632562
END DESCRIPTION:
XS GIS Cut Line= 5
      2506580.39     13488308.22      2507108.16     13487952.55
      2507180.83     13487761.32      2506905.45     13487508.89
       2506727.3     13487429.29
#Sta/Elev= 30
  4227.4  186.36  4352.5   183.4  4523.7  181.34  4570.6  181.24  4585.1  180.48
  4625.9  179.99  4759.3  177.99  4858.1  178.02  4897.9  177.15  4922.7  175.64
  4936.1  173.82  4958.2   172.3  4980.9  169.16  4981.2  168.66  4984.7  168.66
  4984.9  169.16  4989.6  170.72  5000.3  171.67  5007.7  173.75  5013.1   176.6
  5021.7  178.52  5177.8  180.32  5261.1  181.27  5289.5   182.8  5310.4  182.51
  5381.3  184.01  5436.7  186.11  5507.7  187.35  5611.5  190.47  5637.1  190.48
#Mann= 10 ,-1 , 0
  4227.4     .12       0  4352.5     .07       0  4523.7     .05       0
  4585.1     .07       0  4625.9     .12       0  4858.1     .05       0
  4980.9     .05       0  4984.9     .05       0  5177.8    .035       0
  5436.7     .07       0
Bank Sta=4980.9,4984.9
XS Rating Curve= 0 ,0
Exp/Cntr=0.3,0.1

Type RM Length L Ch R = 1 ,1453    ,501,501,501
BEGIN DESCRIPTION:
Mapping XS 7bc81a08
END DESCRIPTION:
XS GIS Cut Line= 4
       2506660.7     13488499.27      2507331.74     13488168.76
      2507472.17     13488045.35      2507160.51     13487499.88
#Sta/Elev= 30
  4155.1  185.99  4160.8  185.98  4219.6  183.93    4401  180.01  4576.1  178.66
  4678.4  176.93  4763.4  175.63  4805.3  175.09  4943.7  176.09  4964.6  174.35
  4972.2  171.31  4976.8  167.73  4977.1  167.23  4980.6  167.23  4980.8  167.73
  4993.1  170.59  5021.5  173.35  5028.2  174.93  5042.4  176.54  5100.5  177.48
  5213.4  177.58  5219.2  176.39    5235  177.66  5256.6  178.04  5272.4  177.55
  5327.1  177.43  5484.9  177.66  5638.1   179.5  5659.7  180.39  5718.3     181
#Mann= 11 ,-1 , 0
  4155.1     .05       0  4160.8     .07       0  4219.6     .05       0
  4576.1     .12       0  4678.4     .05       0  4763.4     .12       0
  4976.8     .05       0  4980.8     .12       0  5100.5     .05       0
  5327.1     .07       0  5484.9    .035       0
Bank Sta=4976.8,4980.8
XS Rating Curve= 0 ,0
Exp/Cntr=0.3,0.1

Type RM Length L Ch R = 1 ,952     ,647,647,647
BEGIN DESCRIPTION:
Mapping XS 6c74b0b8
END DESCRIPTION:
XS GIS Cut Line= 4
      2506785.64     13488751.32      2507384.02     13488508.03
      2507636.08     13488310.76      2507397.98     13487808.35
#Sta/Elev= 30
  4363.4  183.94  4427.6  182.36  4635.2  178.18  4873.4  175.97    4927  174.88
  4934.8  172.34    4951  168.76  4956.4  166.31  4965.2   164.5  4965.5     164
    4969     164  4969.2   164.5  4975.1  166.36  4980.5  167.44  4999.2  168.22
  5004.6  169.27  5007.2  170.91  5019.7  171.03  5061.4  173.45  5106.1  173.79
  5148.1  174.31  5154.4   174.8  5183.3  174.31  5303.6  175.22  5456.2  175.43
  5502.8  176.03  5608.4  177.21  5639.9  177.46  5785.6  177.66  5885.4  176.86
#Mann= 8 ,-1 , 0
  4363.4     .12       0  4427.6     .05       0  4965.2     .05       0
  4969.2     .05       0  5106.1     .12       0  5502.8    .035       0
  5608.4     .12       0  5639.9     .05       0
Bank Sta=4965.2,4969.2
XS Rating Curve= 0 ,0
Exp/Cntr=0.3,0.1

Type RM Length L Ch R = 1 ,305     ,0,0,0
BEGIN DESCRIPTION:
Mapping XS 76e92bf6
END DESCRIPTION:
XS GIS Cut Line= 4
       2506957.3     13489165.03      2507870.61     13488992.43
      2507848.69     13488657.07       2507546.2     13488030.18
#Sta/Elev= 30
  3886.1  179.92    4013  177.32  4117.8  175.79  4209.4  175.16  4229.8  174.44
  4415.2   174.1  4443.5  174.48  4524.9  173.32  4815.3  171.07  4903.2  171.38
  4923.2  170.73  4943.3  170.95  4973.3  164.39  4978.3  166.08  5003.4     162
  5031.5  161.25  5031.7  160.75  5035.2  160.75  5035.5  161.25  5063.5   168.8
  5123.7  171.35  5135.1  171.08  5276.1  173.78  5397.2  174.16  5425.4  174.84
  5510.1  174.77  5628.8  174.79  5815.3  176.16  5842.3  176.83  5847.7  176.89
#Mann= 7 ,-1 , 0
  3886.1     .07       0    4013     .05       0  4415.2     .12       0
  5031.5     .05       0  5035.5     .12       0  5510.1    .035       0
  5842.3     .05       0
Bank Sta=5031.5,5035.5
XS Rating Curve= 0 ,0
Exp/Cntr=0.3,0.1

Chan Stop Cuts=-1
Use User Specified Reach Order=0
Composite Channel Slope=5