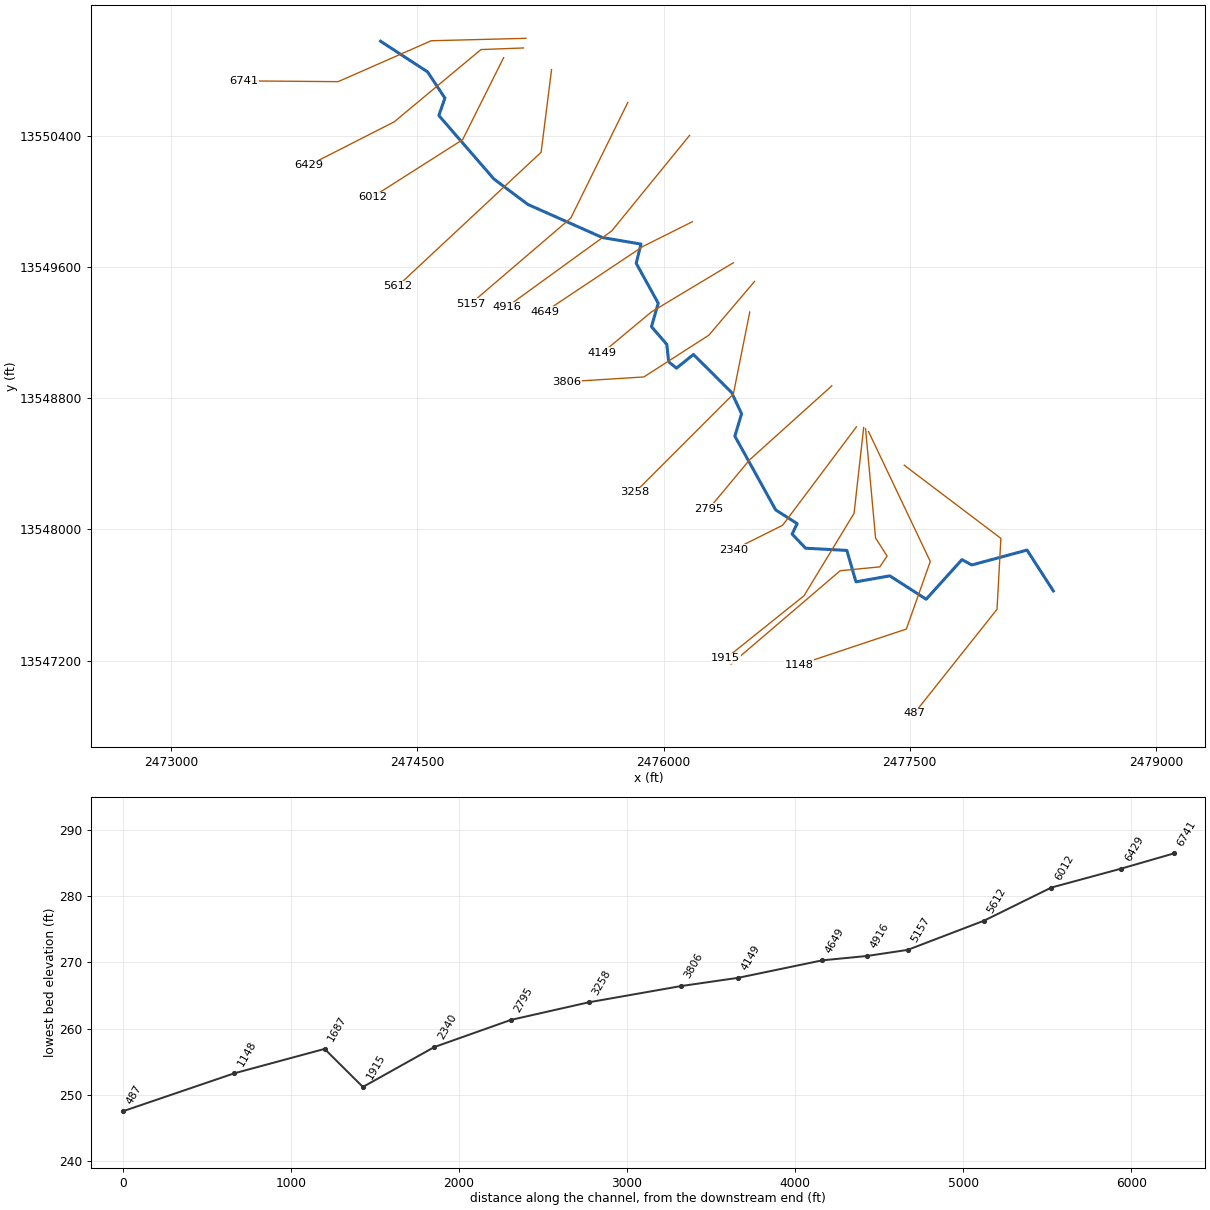
--- TRIB 1 TO SHILOH CREEK.prj (project) ---

Proj Title=TRIB 1 TO SHILOH CREEK Base Level Engineering
Current Plan=p01
Default Exp/Contr=0.3,0.1
English Units
Geom File=g01
Flow File=f01
Plan File=p01
BEGIN DESCRIPTION:
TRIB 1 TO SHILOH CREEK
END DESCRIPTION:

--- TRIB 1 TO SHILOH CREEK.p01 (plan) ---

Plan Title=Multiple Run
Short Identifier=Multiple
Geom File=g01
Flow File=f01
Subcritical Flow
K Sum by GR= 0
Std Step Tol= 0.01
Critical Tol= 0.01
Num of Std Step Trials= 20
Max Error Tol= 0.3
Flow Tol Ratio= 0.001
Split Flow NTrial= 30
Split Flow Tol= 0.02
Split Flow Ratio= 0.02
Log Output Level= 0
Friction Slope Method= 1
Unsteady Friction Slope Method= 2
Unsteady Bridges Friction Slope Method= 1
Parabolic Critical Depth
Global Vel Dist=  1 , 1 , 1
Global Log Level= 0
CheckData=True
Encroach Param= -1, 0, 0, 0
BEGIN DESCRIPTION:
Multiple Run
END DESCRIPTION:

--- TRIB 1 TO SHILOH CREEK.f01 (steady flow) ---

Flow Title=Multiple
Number of Profiles=7
Profile Names=10-year,25-year,50-year,1pct_min,100-year,1pct_plu,500-year
River Rch & RM= TRIB 1 TO SHILOH,Reach-1,6741
     551     882    1178     763    1522    3036    2510
Boundary for River Rch & Prof#=TRIB 1 TO SHILOH,Reach-1,1
Up Type=0
Dn Type=3
Dn Slope=0.005
Boundary for River Rch & Prof#=TRIB 1 TO SHILOH,Reach-1,2
Up Type=0
Dn Type=3
Dn Slope=0.005
Boundary for River Rch & Prof#=TRIB 1 TO SHILOH,Reach-1,3
Up Type=0
Dn Type=3
Dn Slope=0.005
Boundary for River Rch & Prof#=TRIB 1 TO SHILOH,Reach-1,4
Up Type=0
Dn Type=3
Dn Slope=0.005
Boundary for River Rch & Prof#=TRIB 1 TO SHILOH,Reach-1,5
Up Type=0
Dn Type=3
Dn Slope=0.005
Boundary for River Rch & Prof#=TRIB 1 TO SHILOH,Reach-1,6
Up Type=0
Dn Type=3
Dn Slope=0.005
Boundary for River Rch & Prof#=TRIB 1 TO SHILOH,Reach-1,7
Up Type=0
Dn Type=3
Dn Slope=0.005

--- TRIB 1 TO SHILOH CREEK.g01 (geometry) ---

Geom Title=Existing Conditions

River Reach=TRIB 1 TO SHILOH,Reach-1
Reach XY= 30
      2474275.00     13550975.00      2474561.38     13550788.24
      2474667.17     13550628.40      2474630.13     13550522.72
      2474965.32     13550135.78      2475172.57     13549980.52
      2475626.55     13549778.75      2475862.04     13549738.63
      2475832.85     13549621.59      2475967.17     13549378.42
      2475925.95     13549235.49      2476019.46     13549127.41
      2476030.52     13549022.00      2476078.13     13548982.53
      2476181.67     13549066.03      2476414.24     13548834.68
      2476475.10     13548704.90      2476434.15     13548568.27
      2476683.03     13548118.66      2476813.89     13548035.32
      2476783.00     13547971.66      2476865.15     13547885.48
      2477116.75     13547871.93      2477172.01     13547680.45
      2477378.32     13547716.96      2477600.00     13547574.41
      2477818.05     13547815.82      2477878.21     13547783.29
      2478214.71     13547874.03      2478375.00     13547625.00

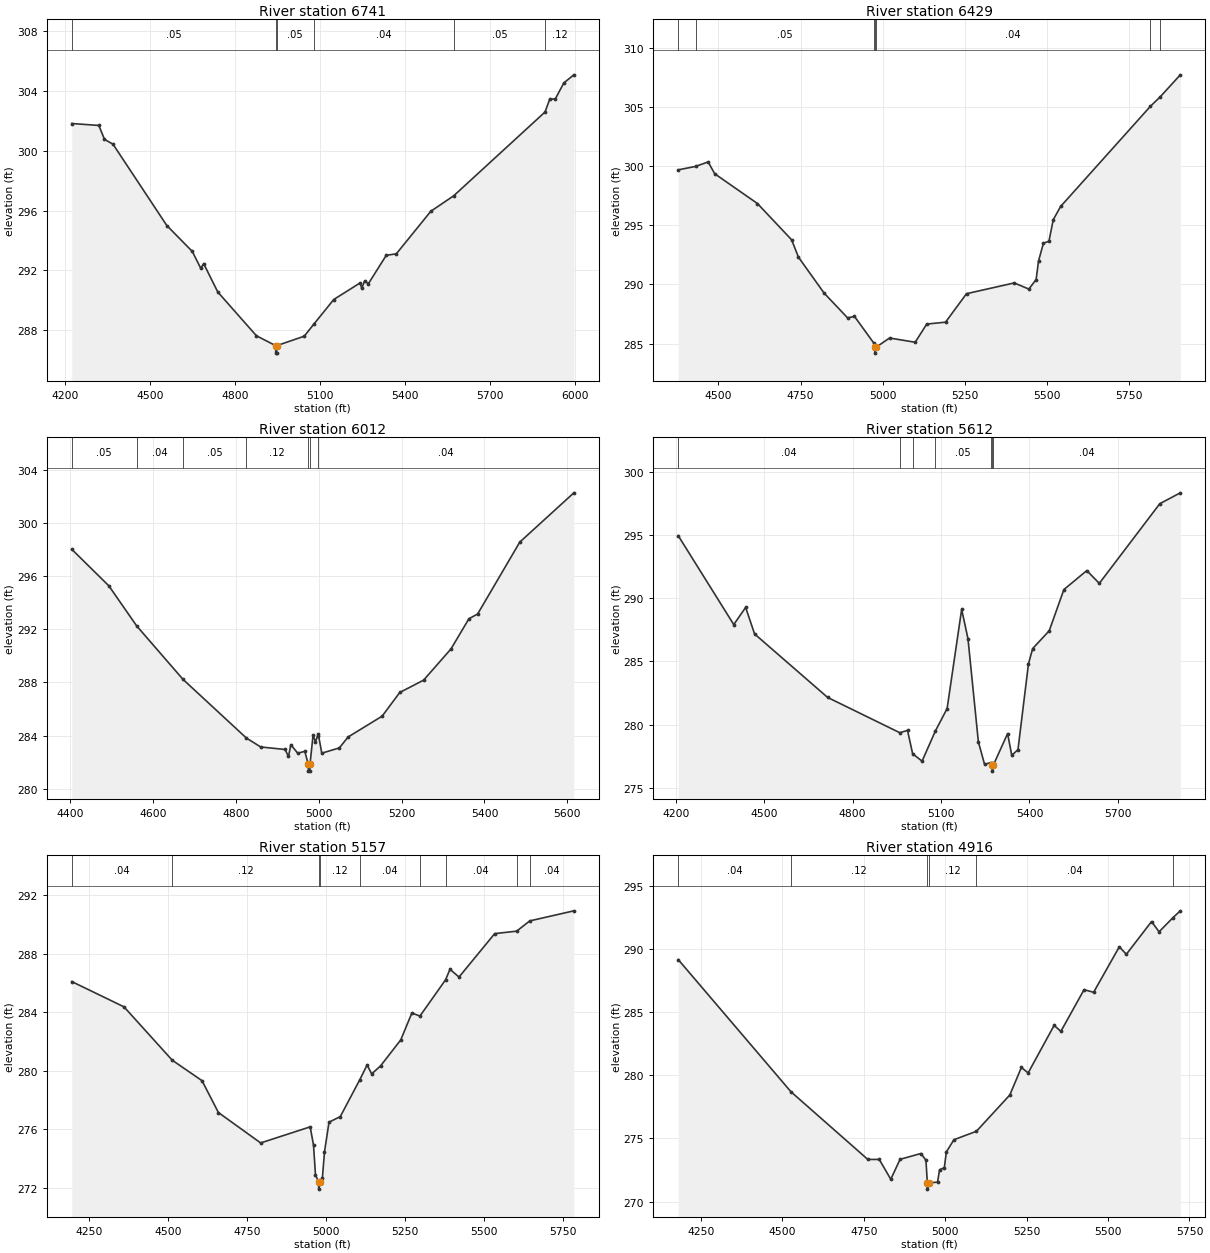
Type RM Length L Ch R = 1,6741,312,312,312
BEGIN DESCRIPTION:
Mapping XS 60640f17
END DESCRIPTION:
XS GIS Cut Line= 4
      2475160.60     13550992.66      2474583.58     13550977.99
      2474016.35     13550728.60      2473439.71     13550733.49
#Sta/Elev= 30
  4224.0  301.81  4319.6  301.68  4339.6  300.75  4369.6  300.43  4559.7  295.00
  4649.7  293.27  4679.7  292.14  4689.8  292.46  4739.8  290.56  4876.2  287.64
  4944.2  286.98  4944.5  286.48  4948.0  286.48  4948.2  286.98  5045.1  287.61
  5078.5  288.40  5149.4  290.06  5242.8  291.17  5248.2  290.80  5258.5  291.30
  5271.6  291.11  5334.9  293.01  5370.4  293.11  5492.2  295.95  5573.5  296.99
  5895.8  302.58  5912.2  303.43  5932.2  303.46  5962.2  304.52  5997.5  305.06
#Mann=6,-1,0
  4224.0    0.05       0  4944.2    0.05       0  4948.2    0.05       0
  5078.5    0.04       0  5573.5    0.05       0  5895.8    0.12       0
Bank Sta=4944.2,4948.2
Exp/Cntr=0.3,0.1

Type RM Length L Ch R = 1,6429,417,417,417
BEGIN DESCRIPTION:
Mapping XS 312890bb
END DESCRIPTION:
XS GIS Cut Line= 4
      2475145.95     13550933.98      2474886.75     13550924.20
      2474358.64     13550484.11      2473840.35     13550220.07
#Sta/Elev= 30
  4377.6  299.70  4430.4  299.99  4468.6  300.37  4488.6  299.37  4618.7  296.85
  4722.8  293.78  4743.6  292.31  4821.7  289.27  4893.3  287.17  4914.1  287.30
  4973.5  285.02  4975.9  284.69  4976.1  284.19  4979.9  284.69  5020.9  285.47
  5099.0  285.11  5134.1  286.65  5191.4  286.81  5255.2  289.22  5400.5  290.13
  5445.0  289.61  5467.2  290.42  5474.4  291.98  5489.5  293.50  5506.1  293.65
  5519.3  295.48  5541.7  296.60  5815.2  305.08  5845.3  305.89  5906.1  307.74
#Mann=7,-1,0
  4377.6    0.04       0  4430.4    0.05       0  4973.5    0.04       0
  4975.9    0.04       0  4979.9    0.04       0  5815.2    0.05       0
  5845.3    0.12       0
Bank Sta=4975.9,4979.9
Exp/Cntr=0.3,0.1

Type RM Length L Ch R = 1,6012,400,400,400
BEGIN DESCRIPTION:
TRIB 1 TO SHILOH CREEK 10.0
END DESCRIPTION:
XS GIS Cut Line= 3
      2475024.99     13550874.98      2474775.00     13550375.00
      2474225.02     13550025.01
#Sta/Elev= 30
  4404.6  298.02  4494.0  295.27  4561.2  292.25  4672.8  288.23  4825.8  283.81
  4860.2  283.14  4918.9  282.95  4927.3  282.43  4932.9  283.31  4949.6  282.67
  4966.6  282.81  4975.1  281.82  4975.4  281.32  4978.9  281.32  4979.1  281.82
  4986.5  284.01  4992.4  283.54  4997.3  283.94  4999.2  284.10  5007.6  282.67
  5050.0  283.07  5071.1  283.89  5153.2  285.46  5195.6  287.24  5253.2  288.17
  5319.2  290.52  5362.4  292.79  5383.5  293.15  5485.1  298.56  5615.5  302.27
#Mann=7,-1,0
  4404.6    0.05       0  4561.2    0.04       0  4672.8    0.05       0
  4825.8    0.12       0  4975.1    0.04       0  4979.1    0.12       0
  4997.3    0.04       0
Bank Sta=4975.1,4979.1
Exp/Cntr=0.3,0.1

Type RM Length L Ch R = 1,5612,455,455,455
BEGIN DESCRIPTION:
Mapping XS 707e6a9c
END DESCRIPTION:
XS GIS Cut Line= 3
      2475317.06     13550801.92      2475253.49     13550298.29
      2474379.08     13549482.50
#Sta/Elev= 30
  4208.3  294.94  4396.7  287.91  4437.0  289.27  4467.3  287.17  4715.1  282.15
  4959.9  279.36  4986.2  279.54  5003.7  277.69  5035.6  277.11  5081.1  279.51
  5120.6  281.27  5169.9  289.11  5191.4  286.79  5226.6  278.64  5247.6  276.86
  5269.5  277.00  5273.9  276.82  5274.2  276.32  5277.9  276.82  5325.8  279.29
  5339.9  277.57  5361.0  278.02  5396.6  284.80  5410.8  286.01  5467.0  287.42
  5516.8  290.68  5594.5  292.18  5637.0  291.17  5842.2  297.47  5911.8  298.33
#Mann=7,-1,0
  4208.3    0.04       0  4959.9    0.12       0  5003.7    0.04       0
  5081.1    0.05       0  5269.5    0.04       0  5273.9    0.05       0
  5277.9    0.04       0
Bank Sta=5273.9,5277.9
Exp/Cntr=0.3,0.1

Type RM Length L Ch R = 1,5157,241,241,241
BEGIN DESCRIPTION:
Mapping XS 4b75edf0
END DESCRIPTION:
XS GIS Cut Line= 3
      2475781.59     13550601.45      2475434.42     13549897.32
      2474823.15     13549374.08
#Sta/Elev= 30
  4194.1  286.10  4359.5  284.37  4512.2  280.72  4606.5  279.32  4658.4  277.14
  4792.2  275.06  4948.9  276.16  4959.5  274.92  4965.8  272.87  4975.7  272.40
  4975.9  271.90  4979.7  272.40  4987.7  272.69  4994.3  274.45  5008.6  276.48
  5044.2  276.86  5106.2  279.39  5129.3  280.40  5143.6  279.78  5172.1  280.34
  5235.8  282.11  5270.9  283.95  5296.5  283.74  5377.6  286.22  5391.6  286.94
  5420.2  286.41  5533.2  289.38  5602.8  289.55  5644.1  290.25  5783.8  290.94
#Mann=9,-1,0
  4194.1    0.04       0  4512.2    0.12       0  4975.7    0.05       0
  4979.7    0.12       0  5106.2    0.04       0  5296.5    0.05       0
  5377.6    0.04       0  5602.8    0.05       0  5644.1    0.04       0
Bank Sta=4975.7,4979.7
Exp/Cntr=0.3,0.1

Type RM Length L Ch R = 1,4916,267,267,267
BEGIN DESCRIPTION:
Mapping XS 6fca75f1
END DESCRIPTION:
XS GIS Cut Line= 3
      2476158.14     13550401.00      2475683.80     13549819.08
      2475043.25     13549354.56
#Sta/Elev= 30
  4179.9  289.15  4526.0  278.69  4762.2  273.33  4797.3  273.33  4832.7  271.76
  4861.2  273.34  4925.2  273.80  4940.7  273.27  4944.9  271.48  4945.2  270.98
  4948.9  271.48  4976.3  271.53  4982.5  272.51  4997.2  272.68  5003.3  273.92
  5026.6  274.89  5095.7  275.56  5198.2  278.43  5233.8  280.61  5254.6  280.18
  5334.3  283.94  5355.1  283.47  5426.3  286.77  5455.6  286.56  5534.5  290.16
  5556.2  289.57  5633.5  292.16  5656.7  291.35  5699.3  292.47  5721.9  293.01
#Mann=6,-1,0
  4179.9    0.04       0  4526.0    0.12       0  4944.9    0.05       0
  4948.9    0.12       0  5095.7    0.04       0  5699.3    0.05       0
Bank Sta=4944.9,4948.9
Exp/Cntr=0.3,0.1

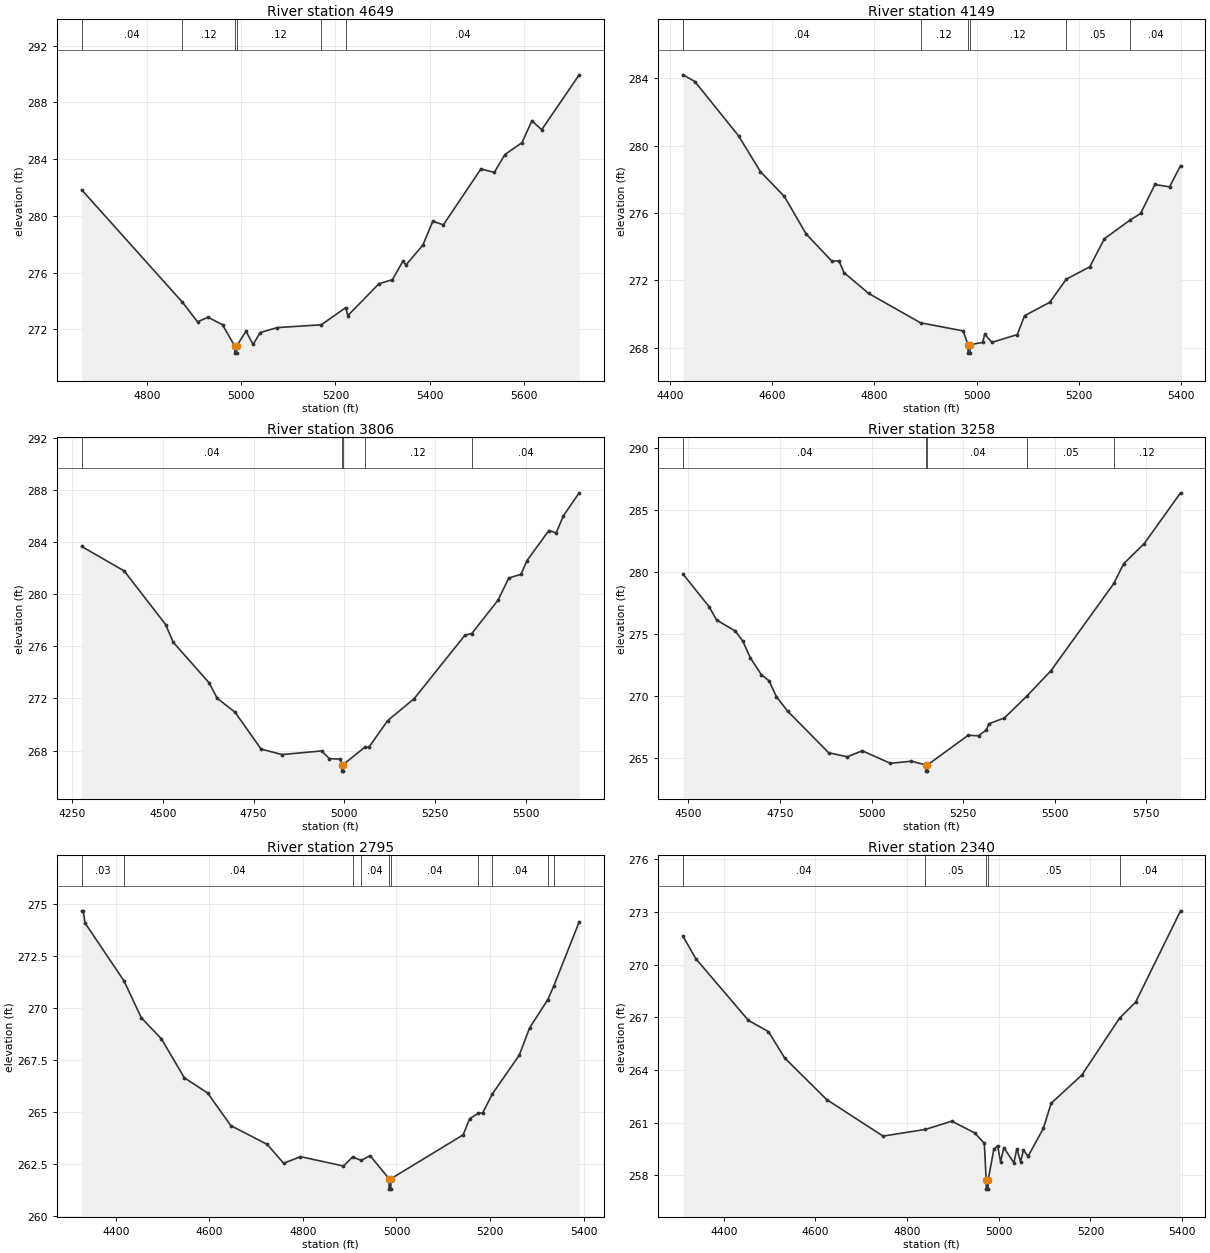
Type RM Length L Ch R = 1,4649,500,500,500
BEGIN DESCRIPTION:
TRIB 1 TO SHILOH CREEK 7.0
END DESCRIPTION:
XS GIS Cut Line= 3
      2476175.02     13549875.01      2475875.00     13549725.00
      2475275.04     13549325.02
#Sta/Elev= 30
  4661.1  281.84  4875.1  273.91  4907.1  272.53  4929.5  272.85  4960.2  272.32
  4986.1  270.82  4986.4  270.32  4989.9  270.32  4990.1  270.82  5010.1  271.86
  5025.1  270.93  5040.1  271.77  5076.2  272.12  5170.1  272.32  5221.7  273.53
  5226.4  272.97  5292.5  275.22  5321.0  275.50  5343.6  276.83  5349.6  276.53
  5385.6  277.94  5406.7  279.62  5429.2  279.37  5508.8  283.31  5537.4  283.07
  5559.9  284.33  5596.0  285.16  5617.0  286.70  5638.0  286.08  5717.6  289.95
#Mann=6,-1,0
  4661.1    0.04       0  4875.1    0.12       0  4986.1    0.05       0
  4990.1    0.12       0  5170.1    0.05       0  5221.7    0.04       0
Bank Sta=4986.1,4990.1
Exp/Cntr=0.3,0.1

Type RM Length L Ch R = 1,4149,343,343,343
BEGIN DESCRIPTION:
TRIB 1 TO SHILOH CREEK 6.0
END DESCRIPTION:
XS GIS Cut Line= 3
      2476425.01     13549625.01      2475925.00     13549325.00
      2475625.02     13549075.02
#Sta/Elev= 30
  4425.3  284.20  4448.6  283.80  4534.2  280.57  4576.9  278.45  4623.6  276.98
  4666.3  274.75  4716.9  273.13  4730.5  273.16  4740.2  272.46  4788.8  271.22
  4890.1  269.48  4973.4  269.00  4983.1  268.18  4983.3  267.68  4986.8  267.68
  4987.1  268.18  5011.7  268.32  5015.6  268.80  5029.9  268.32  5079.4  268.78
  5093.7  269.90  5143.1  270.70  5175.3  272.07  5221.2  272.80  5249.9  274.47
  5300.3  275.58  5320.8  275.97  5348.8  277.69  5377.4  277.55  5398.9  278.81
#Mann=6,-1,0
  4425.3    0.04       0  4890.1    0.12       0  4983.1    0.05       0
  4987.1    0.12       0  5175.3    0.05       0  5300.3    0.04       0
Bank Sta=4983.1,4987.1
Exp/Cntr=0.3,0.1

Type RM Length L Ch R = 1,3806,548,548,548
BEGIN DESCRIPTION:
Mapping XS 46794ece
END DESCRIPTION:
XS GIS Cut Line= 4
      2476554.18     13549511.00      2476275.48     13549183.40
      2475879.40     13548929.12      2475411.70     13548899.89
#Sta/Elev= 30
  4277.0  283.65  4394.0  281.77  4508.1  277.66  4529.1  276.30  4627.9  273.19
  4649.9  272.01  4699.3  270.93  4771.0  268.11  4828.5  267.69  4937.5  267.97
  4958.6  267.38  4989.0  267.34  4992.9  266.92  4993.2  266.42  4996.7  266.42
  4996.9  266.92  5056.0  268.25  5067.6  268.26  5119.1  270.29  5192.2  271.98
  5332.5  276.86  5350.5  276.96  5422.7  279.52  5452.7  281.23  5486.1  281.51
  5502.8  282.57  5562.9  284.87  5583.0  284.69  5603.0  286.00  5646.4  287.76
#Mann=5,-1,0
  4277.0    0.04       0  4992.9    0.04       0  4996.9    0.04       0
  5056.0    0.12       0  5350.5    0.04       0
Bank Sta=4992.9,4996.9
Exp/Cntr=0.3,0.1

Type RM Length L Ch R = 1,3258,463,463,463
BEGIN DESCRIPTION:
TRIB 1 TO SHILOH CREEK 4.0
END DESCRIPTION:
XS GIS Cut Line= 3
      2476525.01     13549325.03      2476425.00     13548825.00
      2475824.97     13548224.97
#Sta/Elev= 30
  4485.3  279.87  4556.7  277.23  4577.1  276.16  4628.1  275.27  4648.5  274.46
  4668.9  273.12  4699.5  271.74  4719.9  271.27  4740.3  269.98  4770.9  268.81
  4883.1  265.45  4934.0  265.13  4974.8  265.61  5051.8  264.60  5108.4  264.77
  5148.8  264.47  5149.0  263.97  5152.5  263.97  5152.8  264.47  5263.9  266.86
  5292.2  266.82  5313.4  267.29  5320.5  267.79  5362.9  268.26  5425.1  270.05
  5490.2  272.08  5661.7  279.11  5688.2  280.69  5744.8  282.33  5843.8  286.42
#Mann=5,-1,0
  4485.3    0.04       0  5148.8    0.04       0  5152.8    0.04       0
  5425.1    0.05       0  5661.7    0.12       0
Bank Sta=5148.8,5152.8
Exp/Cntr=0.3,0.1

Type RM Length L Ch R = 1,2795,455,455,455
BEGIN DESCRIPTION:
TRIB 1 TO SHILOH CREEK 3.0
END DESCRIPTION:
XS GIS Cut Line= 3
      2477025.03     13548875.03      2476525.00     13548425.00
      2476275.02     13548125.02
#Sta/Elev= 30
  4327.3  274.68  4330.7  274.68  4334.4  274.10  4417.9  271.31  4454.8  269.54
  4497.4  268.54  4546.7  266.66  4596.4  265.93  4646.1  264.36  4723.8  263.46
  4759.0  262.55  4794.9  262.87  4886.8  262.42  4906.1  262.85  4924.8  262.69
  4943.6  262.92  4984.2  261.81  4984.4  261.31  4987.9  261.31  4988.2  261.81
  5142.6  263.92  5156.2  264.69  5174.6  264.95  5184.2  264.97  5204.8  265.88
  5262.3  267.74  5284.4  269.05  5323.2  270.41  5336.2  271.07  5390.5  274.15
#Mann=10,-1,0
  4327.3    0.03       0  4417.9    0.04       0  4906.1    0.05       0
  4924.8    0.04       0  4984.2    0.04       0  4988.2    0.04       0
  5174.6    0.05       0  5204.8    0.04       0  5323.2    0.05       0
  5336.2    0.04       0
Bank Sta=4984.2,4988.2
Exp/Cntr=0.3,0.1

Type RM Length L Ch R = 1,2340,425,425,425
BEGIN DESCRIPTION:
TRIB 1 TO SHILOH CREEK 2.0
END DESCRIPTION:
XS GIS Cut Line= 3
      2477174.98     13548624.97      2476725.00     13548025.00
      2476424.98     13547874.99
#Sta/Elev= 30
  4311.1  271.61  4339.2  270.33  4453.8  266.82  4497.5  266.18  4532.9  264.68
  4624.6  262.31  4747.5  260.23  4839.6  260.61  4897.5  261.08  4947.5  260.41
  4968.4  259.82  4972.6  257.71  4972.9  257.21  4976.4  257.21  4976.6  257.71
  4989.2  259.48  4997.5  259.68  5003.8  258.77  5011.1  259.57  5032.9  258.71
  5039.2  259.50  5047.5  258.78  5053.8  259.43  5063.9  259.08  5097.4  260.68
  5114.2  262.10  5181.3  263.71  5263.5  266.95  5298.6  267.86  5396.5  273.06
#Mann=5,-1,0
  4311.1    0.04       0  4839.6    0.05       0  4972.6    0.05       0
  4976.6    0.05       0  5263.5    0.04       0
Bank Sta=4972.6,4976.6
Exp/Cntr=0.3,0.1

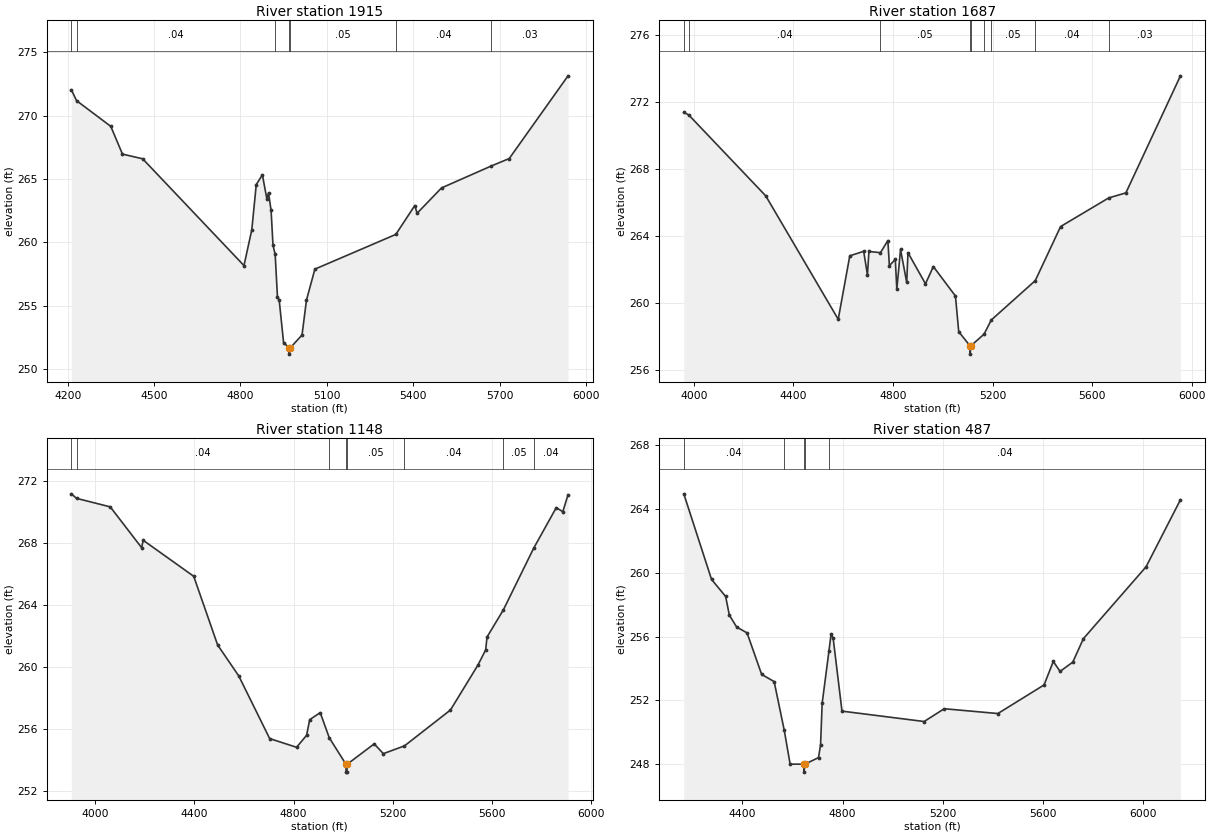
Type RM Length L Ch R = 1,1915,228,228,228
BEGIN DESCRIPTION:
Mapping XS edbab9dc
END DESCRIPTION:
XS GIS Cut Line= 4
      2477219.23     13548621.08      2477160.55     13548097.84
      2476855.73     13547595.93      2476379.11     13547213.53
#Sta/Elev= 30
  4212.9  272.04  4230.9  271.19  4349.8  269.16  4390.3  266.97  4460.5  266.60
  4812.3  258.17  4839.5  261.00  4855.0  264.57  4876.3  265.33  4891.8  263.43
  4897.6  263.91  4906.5  262.52  4913.1  259.77  4920.6  259.06  4928.6  255.69
  4934.5  255.47  4949.9  252.08  4969.3  251.68  4969.5  251.18  4973.3  251.68
  5013.9  252.69  5029.4  255.45  5058.6  257.89  5339.6  260.63  5405.5  262.91
  5413.5  262.30  5498.3  264.30  5670.9  266.03  5733.5  266.62  5937.7  273.15
#Mann=7,-1,0
  4212.9    0.03       0  4230.9    0.04       0  4920.6    0.05       0
  4969.3    0.05       0  4973.3    0.05       0  5339.6    0.04       0
  5670.9    0.03       0
Bank Sta=4969.3,4973.3
Exp/Cntr=0.3,0.1

Type RM Length L Ch R = 1,1687,539,539,539
BEGIN DESCRIPTION:
TRIB 1 TO SHILOH CREEK 1.5
END DESCRIPTION:
XS GIS Cut Line= 6
      2477230.71     13548613.03      2477291.64     13547947.47
      2477361.95     13547837.32      2477317.42     13547771.70
      2477076.03     13547748.27      2476411.14     13547179.37
#Sta/Elev= 30
  3959.2  271.37  3978.7  271.22  4288.6  266.38  4579.8  259.01  4626.3  262.80
  4682.1  263.07  4697.3  261.66  4703.2  263.06  4749.5  262.99  4779.3  263.71
  4785.4  262.21  4809.2  262.59  4815.3  260.79  4830.2  263.18  4855.1  261.21
  4860.1  262.99  4930.4  261.13  4962.1  262.16  5050.9  260.40  5064.1  258.27
  5109.2  257.43  5109.5  256.93  5113.2  257.43  5165.7  258.12  5195.0  258.97
  5371.7  261.32  5473.5  264.55  5666.9  266.26  5735.8  266.56  5955.1  273.55
#Mann=9,-1,0
  3959.2    0.03       0  3978.7    0.04       0  4749.5    0.05       0
  5109.2    0.05       0  5113.2    0.05       0  5165.7    0.04       0
  5195.0    0.05       0  5371.7    0.04       0  5666.9    0.03       0
Bank Sta=5109.2,5113.2
Exp/Cntr=0.3,0.1

Type RM Length L Ch R = 1,1148,661,661,661
BEGIN DESCRIPTION:
TRIB 1 TO SHILOH CREEK 1.0
END DESCRIPTION:
XS GIS Cut Line= 4
      2477248.57     13548596.60      2477625.09     13547804.45
      2477479.23     13547392.72      2476824.99     13547175.00
#Sta/Elev= 30
  3903.4  271.15  3924.1  270.86  4060.2  270.31  4186.9  267.68  4193.0  268.16
  4396.9  265.84  4493.3  261.42  4578.7  259.42  4703.3  255.39  4811.7  254.83
  4852.2  255.60  4864.8  256.61  4907.2  257.06  4943.7  255.44  5011.3  253.73
  5011.5  253.23  5015.0  253.23  5015.3  253.73  5124.9  255.05  5161.8  254.42
  5247.1  254.92  5432.5  257.23  5542.9  260.11  5574.5  261.10  5580.1  261.93
  5646.0  263.68  5767.9  267.64  5859.3  270.26  5885.7  270.00  5906.8  271.09
#Mann=8,-1,0
  3903.4    0.03       0  3924.1    0.04       0  4943.7    0.05       0
  5011.3    0.05       0  5015.3    0.05       0  5247.1    0.04       0
  5646.0    0.05       0  5767.9    0.04       0
Bank Sta=5011.3,5015.3
Exp/Cntr=0.3,0.1

Type RM Length L Ch R = 1,487,0,0,0
BEGIN DESCRIPTION:
TRIB 1 TO SHILOH CREEK 0.5
END DESCRIPTION:
XS GIS Cut Line= 4
      2477466.71     13548390.73      2478055.29     13547945.39
      2478031.85     13547513.10      2477527.57     13546878.84
#Sta/Elev= 30
  4166.5  264.94  4277.2  259.58  4333.5  258.51  4348.1  257.35  4377.2  256.60
  4418.9  256.23  4477.1  253.63  4527.0  253.18  4567.4  250.12  4590.7  248.01
  4645.7  248.01  4646.0  247.51  4649.7  248.01  4704.0  248.42  4712.2  249.23
  4718.5  251.82  4745.7  255.11  4753.9  256.13  4762.2  255.92  4797.6  251.33
  5125.3  250.68  5205.4  251.48  5419.5  251.18  5603.7  252.97  5640.5  254.44
  5667.7  253.82  5718.3  254.40  5760.7  255.87  6010.6  260.37  6147.8  264.57
#Mann=5,-1,0
  4166.5    0.04       0  4567.4    0.05       0  4645.7    0.04       0
  4649.7    0.05       0  4745.7    0.04       0
Bank Sta=4645.7,4649.7
Exp/Cntr=0.3,0.1

Chan Stop Cuts=-1