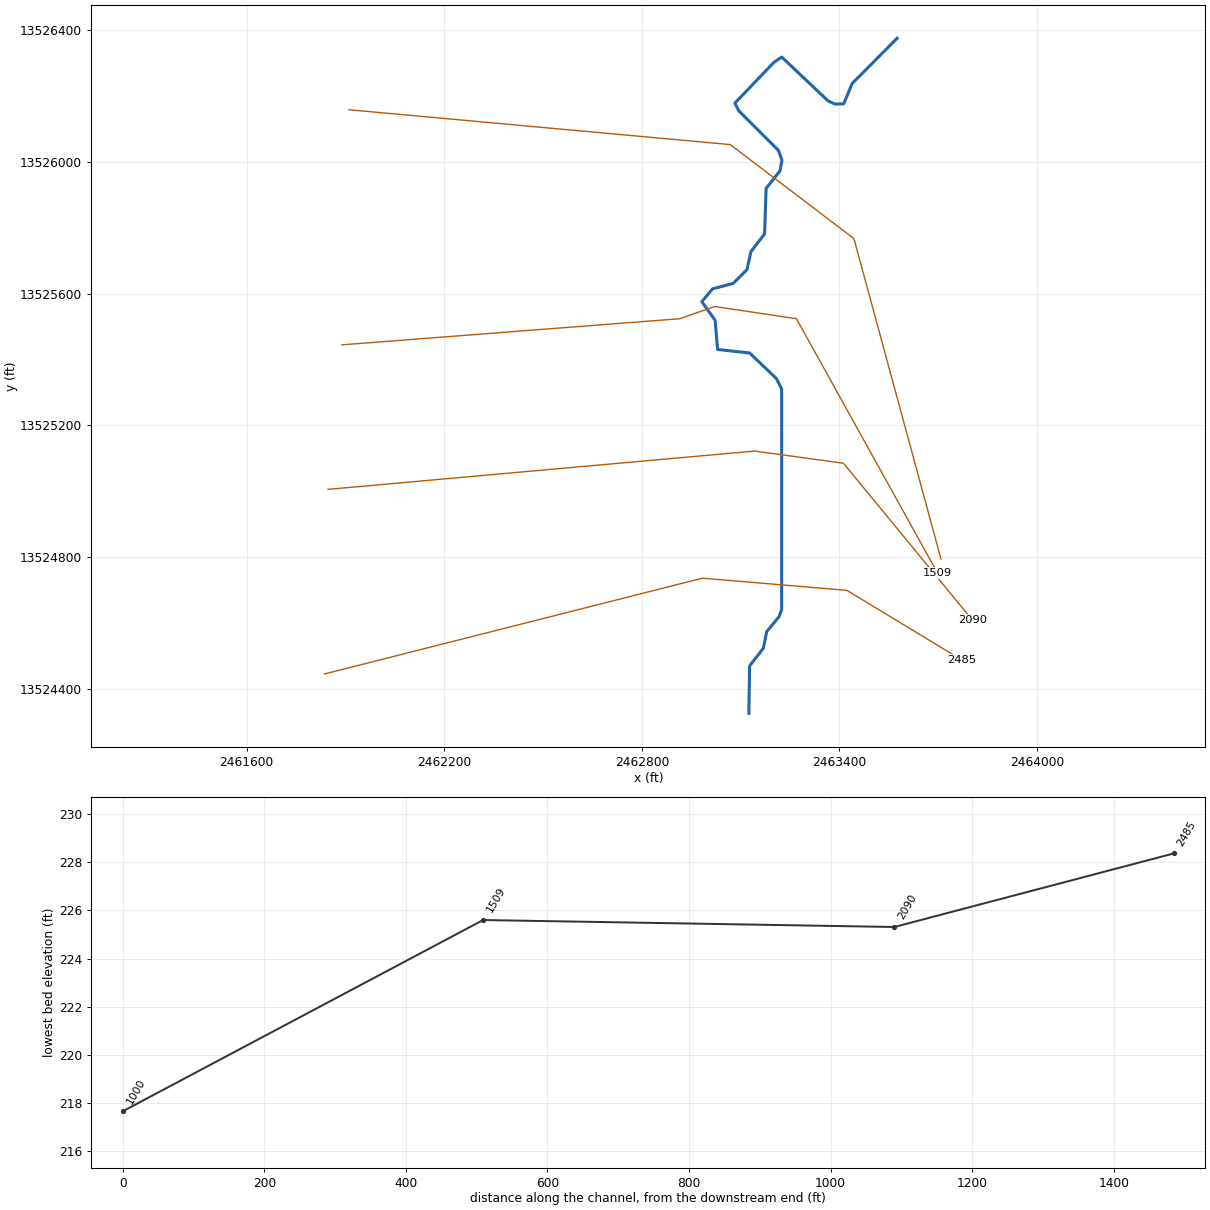
--- TRIB 1 TO SMITH CREEK.prj (project) ---

Proj Title=TRIB 1 TO SMITH CREEK Base Level Engineering
Current Plan=p01
Default Exp/Contr=0.3,0.1
English Units
Geom File=g01
Flow File=f01
Plan File=p01
BEGIN DESCRIPTION:
TRIB 1 TO SMITH CREEK
END DESCRIPTION:

--- TRIB 1 TO SMITH CREEK.p01 (plan) ---

Plan Title=Multiple Run
Short Identifier=Multiple
Geom File=g01
Flow File=f01
Subcritical Flow
K Sum by GR= 0
Std Step Tol= 0.01
Critical Tol= 0.01
Num of Std Step Trials= 20
Max Error Tol= 0.3
Flow Tol Ratio= 0.001
Split Flow NTrial= 30
Split Flow Tol= 0.02
Split Flow Ratio= 0.02
Log Output Level= 0
Friction Slope Method= 1
Unsteady Friction Slope Method= 2
Unsteady Bridges Friction Slope Method= 1
Parabolic Critical Depth
Global Vel Dist=  1 , 1 , 1
Global Log Level= 0
CheckData=True
Encroach Param= -1, 0, 0, 0
BEGIN DESCRIPTION:
Multiple Run
END DESCRIPTION:

--- TRIB 1 TO SMITH CREEK.f01 (steady flow) ---

Flow Title=Multiple
Number of Profiles=7
Profile Names=10-year,25-year,50-year,1pct_min,100-year,1pct_plu,500-year
River Rch & RM= TRIB 1 TO SMITH ,Reach-1,2485
     666    1082    1460     955    1905    3802    3208
Boundary for River Rch & Prof#=TRIB 1 TO SMITH ,Reach-1,1
Up Type=0
Dn Type=3
Dn Slope=0.005
Boundary for River Rch & Prof#=TRIB 1 TO SMITH ,Reach-1,2
Up Type=0
Dn Type=3
Dn Slope=0.005
Boundary for River Rch & Prof#=TRIB 1 TO SMITH ,Reach-1,3
Up Type=0
Dn Type=3
Dn Slope=0.005
Boundary for River Rch & Prof#=TRIB 1 TO SMITH ,Reach-1,4
Up Type=0
Dn Type=3
Dn Slope=0.005
Boundary for River Rch & Prof#=TRIB 1 TO SMITH ,Reach-1,5
Up Type=0
Dn Type=3
Dn Slope=0.005
Boundary for River Rch & Prof#=TRIB 1 TO SMITH ,Reach-1,6
Up Type=0
Dn Type=3
Dn Slope=0.005
Boundary for River Rch & Prof#=TRIB 1 TO SMITH ,Reach-1,7
Up Type=0
Dn Type=3
Dn Slope=0.005

--- TRIB 1 TO SMITH CREEK.g01 (geometry) ---

Geom Title=Existing Conditions

River Reach=TRIB 1 TO SMITH ,Reach-1
Reach XY= 30
      2463125.00     13524325.00      2463127.20     13524469.09
      2463168.89     13524522.82      2463179.19     13524573.26
      2463216.91     13524618.92      2463224.49     13524640.21
      2463224.62     13525309.85      2463208.59     13525341.80
      2463127.38     13525419.46      2463030.11     13525430.11
      2463022.39     13525519.02      2462982.22     13525575.31
      2463014.61     13525614.22      2463077.49     13525630.75
      2463119.27     13525672.45      2463131.15     13525727.15
      2463172.75     13525780.93      2463177.30     13525919.07
      2463219.65     13525972.83      2463225.40     13526004.87
      2463214.81     13526034.68      2463094.21     13526155.00
      2463082.59     13526178.33      2463201.66     13526302.62
      2463225.00     13526317.93      2463365.58     13526185.06
      2463386.02     13526175.39      2463412.97     13526176.12
      2463438.72     13526237.91      2463575.00     13526375.00

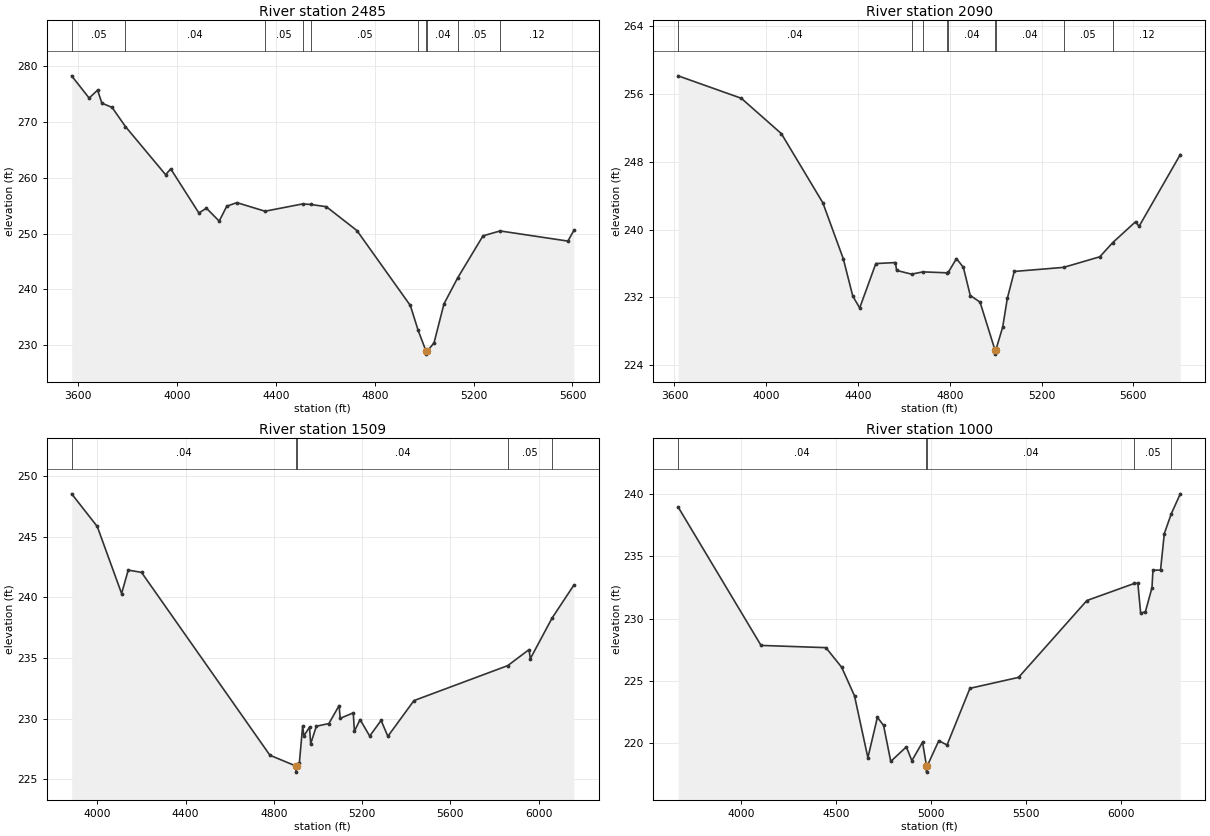
Type RM Length L Ch R = 1,2485,395,395,395
BEGIN DESCRIPTION:
LGII4666
END DESCRIPTION:
XS GIS Cut Line= 4
      2461836.45     13524444.74      2462983.96     13524735.59
      2463422.87     13524698.57      2463770.97     13524487.60
#Sta/Elev= 30
  3574.2  278.32  3644.9  274.33  3679.0  275.75  3696.5  273.42  3737.8  272.65
  3791.7  269.22  3954.4  260.57  3975.0  261.62  4088.8  253.71  4119.5  254.56
  4171.0  252.24  4201.5  254.91  4242.5  255.56  4356.4  254.02  4508.6  255.33
  4541.3  255.23  4604.3  254.83  4728.1  250.55  4944.1  237.10  4975.6  232.66
  5007.9  228.87  5008.2  228.37  5011.9  228.87  5040.0  230.39  5080.2  237.39
  5135.3  242.03  5238.1  249.60  5307.3  250.48  5581.3  248.66  5605.5  250.56
#Mann=10,-1,0
  3574.2    0.05       0  3791.7    0.04       0  4356.4    0.05       0
  4508.6    0.03       0  4541.3    0.05       0  4975.6    0.04       0
  5007.9    0.04       0  5011.9    0.04       0  5135.3    0.05       0
  5307.3    0.12       0
Bank Sta=5007.9,5011.9
Exp/Cntr=0.3,0.1

Type RM Length L Ch R = 1,2090,581,581,581
BEGIN DESCRIPTION:
LGII4665
END DESCRIPTION:
XS GIS Cut Line= 4
      2461846.99     13525005.28      2463142.60     13525121.62
      2463412.30     13525084.60      2463803.05     13524609.37
#Sta/Elev= 30
  3616.0  258.16  3891.3  255.51  4065.8  251.34  4246.5  243.18  4335.8  236.56
  4377.1  232.16  4407.2  230.76  4477.5  236.00  4563.0  236.12  4568.1  235.19
  4633.3  234.75  4682.9  235.02  4785.9  234.91  4793.9  234.99  4828.9  236.59
  4859.0  235.55  4889.1  232.23  4931.6  231.45  4996.6  225.81  4996.9  225.31
  5000.6  225.81  5030.3  228.50  5050.5  231.88  5080.8  235.07  5295.8  235.55
  5453.5  236.80  5509.6  238.47  5609.9  240.95  5624.3  240.38  5804.3  248.87
#Mann=9,-1,0
  3616.0    0.04       0  4633.3    0.03       0  4682.9    0.04       0
  4785.9    0.03       0  4793.9    0.04       0  4996.6    0.04       0
  5000.6    0.04       0  5295.8    0.05       0  5509.6    0.12       0
Bank Sta=4996.6,5000.6
Exp/Cntr=0.3,0.1

Type RM Length L Ch R = 1,1509,509,509,509
BEGIN DESCRIPTION:
LGII4664
END DESCRIPTION:
XS GIS Cut Line= 5
      2461889.33     13525444.20      2462915.21     13525523.52
      2463020.97     13525560.54      2463269.52     13525523.52
      2463697.85     13524751.46
#Sta/Elev= 30
  3883.9  248.52  3999.9  245.83  4110.2  240.31  4140.3  242.24  4200.5  242.05
  4782.2  226.99  4900.6  226.10  4900.8  225.60  4904.6  226.10  4915.4  226.32
  4930.5  229.41  4935.8  228.58  4961.5  229.30  4966.8  227.93  4992.5  229.38
  5049.2  229.60  5095.6  231.08  5100.6  230.03  5159.8  230.48  5164.9  228.96
  5190.7  229.93  5234.2  228.57  5285.9  229.86  5316.5  228.55  5434.6  231.49
  5859.5  234.37  5956.2  235.69  5961.9  234.94  6060.2  238.28  6159.1  241.00
#Mann=5,-1,0
  3883.9    0.04       0  4900.6    0.04       0  4904.6    0.04       0
  5859.5    0.05       0  6060.2    0.12       0
Bank Sta=4900.6,4904.6
Exp/Cntr=0.3,0.1

Type RM Length L Ch R = 1,1000,0,0,0
BEGIN DESCRIPTION:
LGII4663
END DESCRIPTION:
XS GIS Cut Line= 4
      2461910.45     13526158.10      2463068.57     13526052.34
      2463444.03     13525766.78      2463708.45     13524793.71
#Sta/Elev= 30
  3670.2  238.97  4106.6  227.84  4448.0  227.66  4531.1  226.08  4598.6  223.78
  4668.9  218.81  4719.1  222.06  4751.6  221.40  4789.4  218.51  4871.3  219.68
  4900.4  218.57  4956.6  220.06  4977.4  218.15  4977.7  217.65  4981.4  218.15
  5042.2  220.18  5085.5  219.83  5206.1  224.39  5462.1  225.27  5821.5  231.45
  6070.6  232.82  6089.7  232.84  6104.6  230.43  6129.5  230.55  6164.1  232.48
  6169.3  233.90  6209.1  233.89  6229.0  236.83  6266.0  238.44  6313.2  240.03
#Mann=5,-1,0
  3670.2    0.04       0  4977.4    0.04       0  4981.4    0.04       0
  6070.6    0.05       0  6266.0    0.12       0
Bank Sta=4977.4,4981.4
Exp/Cntr=0.3,0.1

Chan Stop Cuts=-1