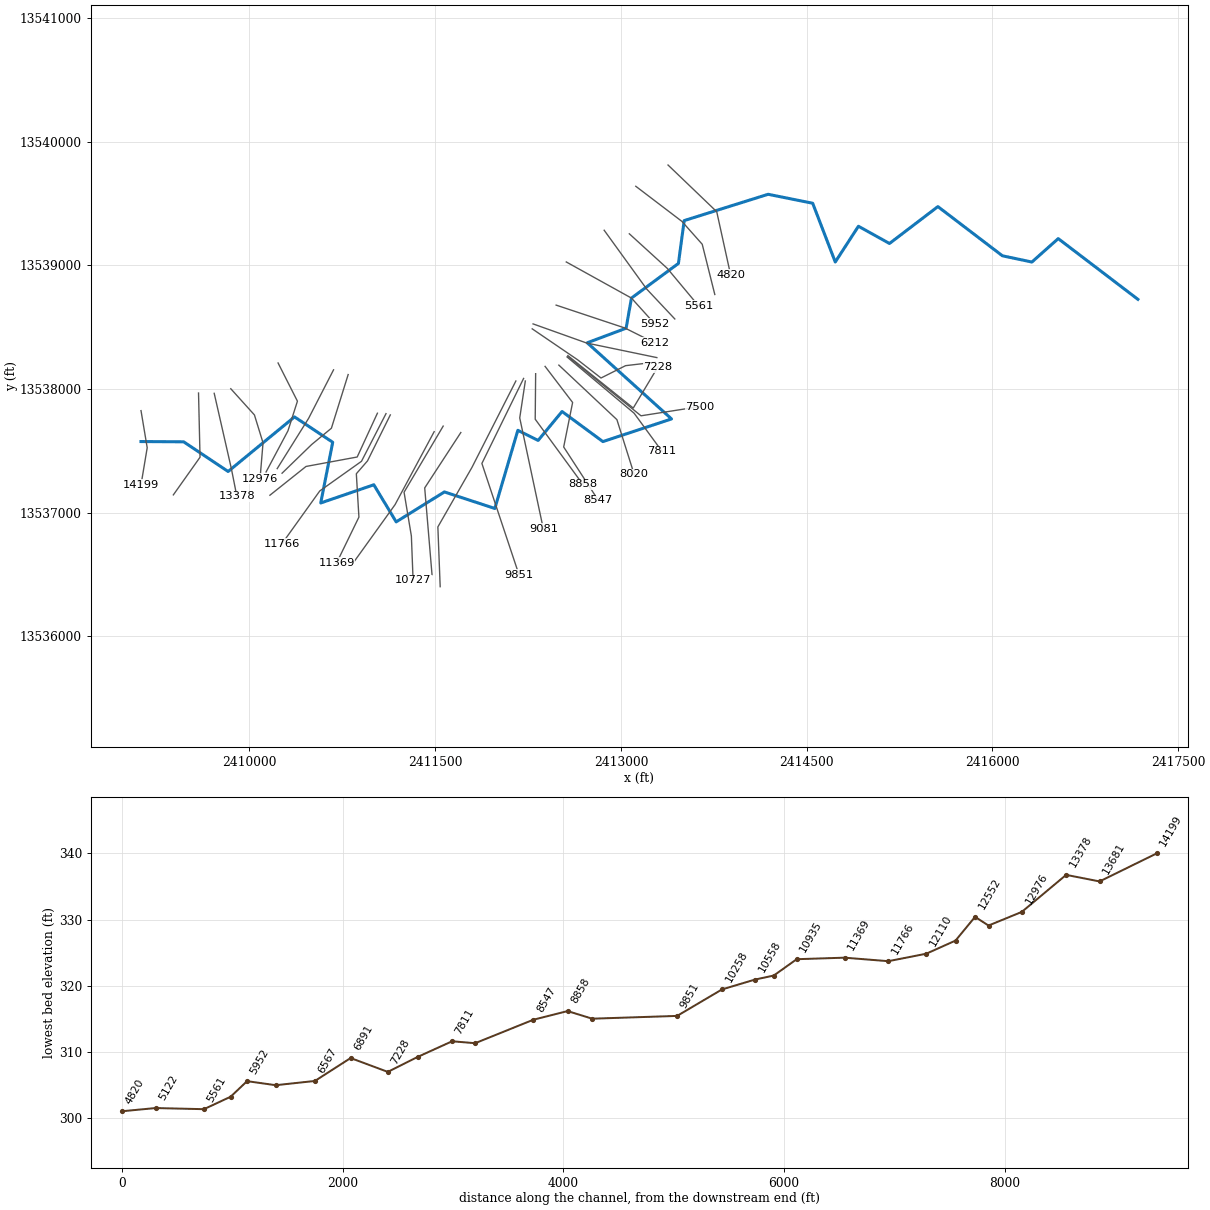
--- TRIB 1 TO THOMAS CREEK.prj (project) ---

Proj Title=TRIB 1 TO THOMAS CREEK Base Level Engineering
Current Plan=p01
Default Exp/Contr=0.3,0.1
English Units
Geom File=g01
Flow File=f01
Plan File=p01
BEGIN DESCRIPTION:
TRIB 1 TO THOMAS CREEK
END DESCRIPTION:

--- TRIB 1 TO THOMAS CREEK.p01 (plan) ---

Plan Title=Multiple Run
Short Identifier=Multiple
Geom File=g01
Flow File=f01
Subcritical Flow
K Sum by GR= 0
Std Step Tol= 0.01
Critical Tol= 0.01
Num of Std Step Trials= 20
Max Error Tol= 0.3
Flow Tol Ratio= 0.001
Split Flow NTrial= 30
Split Flow Tol= 0.02
Split Flow Ratio= 0.02
Log Output Level= 0
Friction Slope Method= 1
Unsteady Friction Slope Method= 2
Unsteady Bridges Friction Slope Method= 1
Parabolic Critical Depth
Global Vel Dist=  1 , 1 , 1
Global Log Level= 0
CheckData=True
Encroach Param= -1, 0, 0, 0
BEGIN DESCRIPTION:
Multiple Run
END DESCRIPTION:

--- TRIB 1 TO THOMAS CREEK.f01 (steady flow) ---

Flow Title=Multiple
Number of Profiles=7
Profile Names=10-year,25-year,50-year,1pct_min,100-year,1pct_plu,500-year
River Rch & RM= TRIB 1 TO THOMAS,Reach-1,14199
     817    1361    1867    1239    2473    4934    4299
River Rch & RM= TRIB 1 TO THOMAS,Reach-1,12674
    1126    1902    2633    1763    3518    7020    6222
River Rch & RM= TRIB 1 TO THOMAS,Reach-1,11369
    1137    1917    2651    1773    3537    7057    6238
River Rch & RM= TRIB 1 TO THOMAS,Reach-1,9851
    1454    2475    3446    2316    4621    9220    8238
River Rch & RM= TRIB 1 TO THOMAS,Reach-1,5803
    1777    3049    4266    2879    5744   11462   10329
River Rch & RM= TRIB 1 TO THOMAS,Reach-1,2029
    1903    3271    4583    3096    6178   12327   11133
Boundary for River Rch & Prof#=TRIB 1 TO THOMAS,Reach-1,1
Up Type=0
Dn Type=3
Dn Slope=0.005
Boundary for River Rch & Prof#=TRIB 1 TO THOMAS,Reach-1,2
Up Type=0
Dn Type=3
Dn Slope=0.005
Boundary for River Rch & Prof#=TRIB 1 TO THOMAS,Reach-1,3
Up Type=0
Dn Type=3
Dn Slope=0.005
Boundary for River Rch & Prof#=TRIB 1 TO THOMAS,Reach-1,4
Up Type=0
Dn Type=3
Dn Slope=0.005
Boundary for River Rch & Prof#=TRIB 1 TO THOMAS,Reach-1,5
Up Type=0
Dn Type=3
Dn Slope=0.005
Boundary for River Rch & Prof#=TRIB 1 TO THOMAS,Reach-1,6
Up Type=0
Dn Type=3
Dn Slope=0.005
Boundary for River Rch & Prof#=TRIB 1 TO THOMAS,Reach-1,7
Up Type=0
Dn Type=3
Dn Slope=0.005

--- TRIB 1 TO THOMAS CREEK.g01 (geometry) ---

Geom Title=Existing Conditions

River Reach=TRIB 1 TO THOMAS,Reach-1
Reach XY= 30
      2409125.00     13537575.00      2409469.52     13537572.92
      2409828.43     13537332.79      2410364.38     13537774.40
      2410673.03     13537569.33      2410576.22     13537078.43
      2411004.98     13537225.45      2411185.47     13536925.53
      2411574.91     13537167.65      2411982.07     13537033.97
      2412167.98     13537666.01      2412331.75     13537584.10
      2412524.99     13537817.92      2412854.82     13537574.71
      2413409.00     13537757.88      2412728.36     13538373.75
      2413042.14     13538491.45      2413085.34     13538735.12
      2413464.52     13539015.20      2413511.26     13539361.80
      2414188.97     13539574.45      2414548.83     13539502.01
      2414731.13     13539026.76      2414918.29     13539316.04
      2415168.96     13539176.61      2415559.92     13539474.82
      2416080.86     13539077.08      2416318.97     13539026.62
      2416531.67     13539216.05      2417175.00     13538725.00

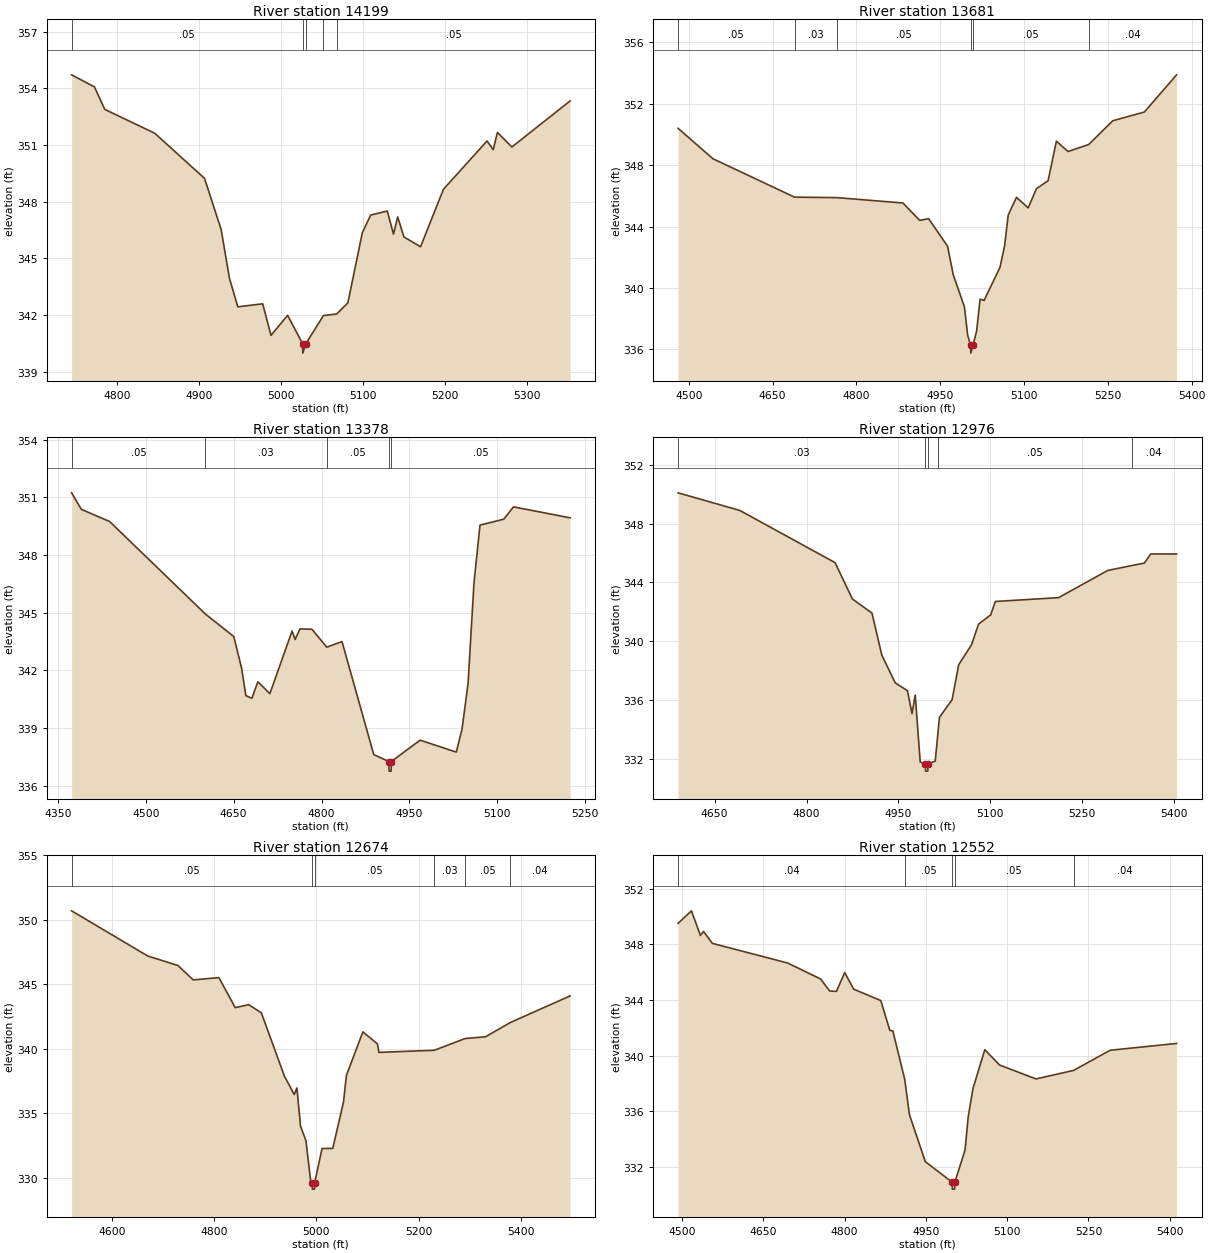
Type RM Length L Ch R = 1,14199,518,518,518
BEGIN DESCRIPTION:
TRIB 1 TO THOMAS CREEK 27.0
END DESCRIPTION:
XS GIS Cut Line= 3
      2409125.00     13537825.00      2409175.00     13537525.00
      2409125.00     13537224.97
#Sta/Elev= 30
  4744.9  354.72  4772.8  354.08  4785.4  352.89  4846.3  351.63  4907.1  349.24
  4927.4  346.53  4937.5  343.96  4947.7  342.44  4978.1  342.60  4988.2  340.93
  5008.5  341.99  5026.8  340.49  5027.0  339.99  5030.8  340.49  5052.2  341.98
  5068.3  342.06  5082.0  342.65  5099.7  346.37  5109.9  347.30  5130.1  347.51
  5137.7  346.29  5142.8  347.20  5150.4  346.14  5170.7  345.62  5198.6  348.66
  5251.8  351.22  5259.4  350.76  5264.5  351.67  5282.2  350.90  5353.2  353.34
#Mann=5,-1,0
  4744.9    0.05       0  5026.8    0.05       0  5030.8    0.05       0
  5052.2     0.1       0  5068.3    0.05       0
Bank Sta=5026.8,5030.8
Exp/Cntr=0.3,0.1

Type RM Length L Ch R = 1,13681,303,303,303
BEGIN DESCRIPTION:
TRIB 1 TO THOMAS CREEK 26.0
END DESCRIPTION:
XS GIS Cut Line= 3
      2409589.46     13537967.41      2409601.64     13537448.27
      2409386.09     13537143.72
#Sta/Elev= 30
  4480.7  350.39  4543.1  348.41  4689.2  345.91  4764.6  345.88  4883.2  345.53
  4913.2  344.40  4929.2  344.51  4963.2  342.71  4973.2  340.87  4993.3  338.77
  4999.1  336.93  5004.4  336.26  5004.7  335.76  5008.5  336.26  5015.1  337.19
  5021.3  339.27  5028.5  339.19  5056.9  341.34  5065.2  342.74  5071.7  344.75
  5086.5  345.90  5107.4  345.21  5122.2  346.46  5143.1  346.98  5157.9  349.55
  5178.8  348.88  5215.9  349.34  5258.8  350.88  5315.4  351.45  5373.1  353.87
#Mann=6,-1,0
  4480.7    0.05       0  4689.2    0.03       0  4764.6    0.05       0
  5004.4    0.05       0  5008.5    0.05       0  5215.9    0.04       0
Bank Sta=5004.4,5008.5
Exp/Cntr=0.3,0.1

Type RM Length L Ch R = 1,13378,402,402,402
BEGIN DESCRIPTION:
TRIB 1 TO THOMAS CREEK 25.0
END DESCRIPTION:
XS GIS Cut Line= 3
      2409716.05     13537965.01      2409855.09     13537354.03
      2409898.49     13537134.07
#Sta/Elev= 30
  4373.4  351.23  4390.0  350.37  4438.2  349.74  4601.9  344.92  4650.3  343.75
  4663.6  342.10  4670.8  340.68  4681.1  340.54  4691.3  341.40  4711.8  340.78
  4749.7  344.04  4754.9  343.60  4763.1  344.15  4783.6  344.13  4808.9  343.20
  4834.9  343.49  4889.1  337.61  4914.9  337.25  4915.2  336.75  4918.8  336.75
  4919.0  337.25  4968.2  338.36  5030.0  337.74  5039.8  338.95  5050.0  341.30
  5060.2  346.57  5070.4  349.55  5111.1  349.86  5127.5  350.50  5224.2  349.93
#Mann=5,-1,0
  4373.4    0.05       0  4601.9    0.03       0  4808.9    0.05       0
  4914.9    0.05       0  4919.0    0.05       0
Bank Sta=4914.9,4919
Exp/Cntr=0.3,0.1

Type RM Length L Ch R = 1,12976,302,302,302
BEGIN DESCRIPTION:
Mapping XS fff8c62b
END DESCRIPTION:
XS GIS Cut Line= 4
      2409849.87     13538002.15      2410040.85     13537790.33
      2410110.30     13537564.63      2410085.99     13537272.99
#Sta/Elev= 30
  4590.3  350.09  4691.2  348.89  4846.7  345.34  4874.9  342.87  4906.9  341.91
  4922.9  339.06  4944.8  337.17  4964.8  336.63  4972.3  335.07  4977.5  336.34
  4985.7  331.78  4994.1  331.66  4994.4  331.16  4998.0  331.16  4998.2  331.66
  5010.2  331.84  5015.1  333.96  5017.1  334.82  5037.7  336.01  5048.5  338.40
  5069.4  339.75  5080.9  341.16  5100.8  341.79  5108.3  342.70  5211.6  342.96
  5291.9  344.81  5330.7  345.14  5351.6  345.31  5362.1  345.93  5404.3  345.93
#Mann=5,-1,0
  4590.3    0.03       0  4994.1    0.03       0  4998.2    0.03       0
  5015.1    0.05       0  5330.7    0.04       0
Bank Sta=4994.1,4998.2
Exp/Cntr=0.3,0.1

Type RM Length L Ch R = 1,12674,122,122,122
BEGIN DESCRIPTION:
Mapping XS f863004a
END DESCRIPTION:
XS GIS Cut Line= 4
      2410231.84     13538210.43      2410388.07     13537901.44
      2410311.69     13537661.86      2410135.01     13537329.28
#Sta/Elev= 30
  4521.5  350.69  4670.1  347.19  4729.3  346.45  4759.3  345.33  4809.4  345.51
  4841.3  343.18  4867.7  343.41  4892.3  342.78  4937.5  337.86  4956.7  336.44
  4961.9  336.95  4969.0  333.97  4979.5  332.87  4988.9  329.67  4991.7  329.60
  4992.0  329.10  4996.2  329.10  4996.6  329.60  5011.0  332.25  5031.9  332.26
  5052.9  335.85  5058.6  337.92  5090.8  341.30  5119.2  340.37  5122.1  339.71
  5230.3  339.87  5290.4  340.78  5330.5  340.92  5378.7  342.02  5495.8  344.09
#Mann=6,-1,0
  4521.5    0.05       0  4991.7    0.05       0  4996.6    0.05       0
  5230.3    0.03       0  5290.4    0.05       0  5378.7    0.04       0
Bank Sta=4991.7,4996.6
Exp/Cntr=0.3,0.1

Type RM Length L Ch R = 1,12552,177,177,177
BEGIN DESCRIPTION:
Mapping XS b6d0d11d
END DESCRIPTION:
XS GIS Cut Line= 3
      2410679.74     13538154.91      2410478.35     13537762.55
      2410224.86     13537356.27
#Sta/Elev= 30
  4492.7  349.51  4517.4  350.41  4533.9  348.64  4539.6  348.93  4556.1  348.07
  4694.9  346.66  4755.8  345.51  4772.4  344.65  4784.9  344.62  4800.2  345.97
  4816.8  344.78  4866.8  343.96  4883.4  341.82  4889.0  341.78  4910.9  338.31
  4919.7  335.75  4949.0  332.38  4998.5  330.91  4998.8  330.41  5003.0  330.41
  5003.4  330.91  5022.2  333.21  5028.1  335.61  5036.9  337.64  5058.7  340.43
  5085.9  339.33  5153.1  338.33  5222.5  338.94  5289.9  340.39  5412.6  340.88
#Mann=5,-1,0
  4492.7    0.04       0  4910.9    0.05       0  4998.5    0.05       0
  5003.4    0.05       0  5222.5    0.04       0
Bank Sta=4998.5,5003.4
Exp/Cntr=0.3,0.1

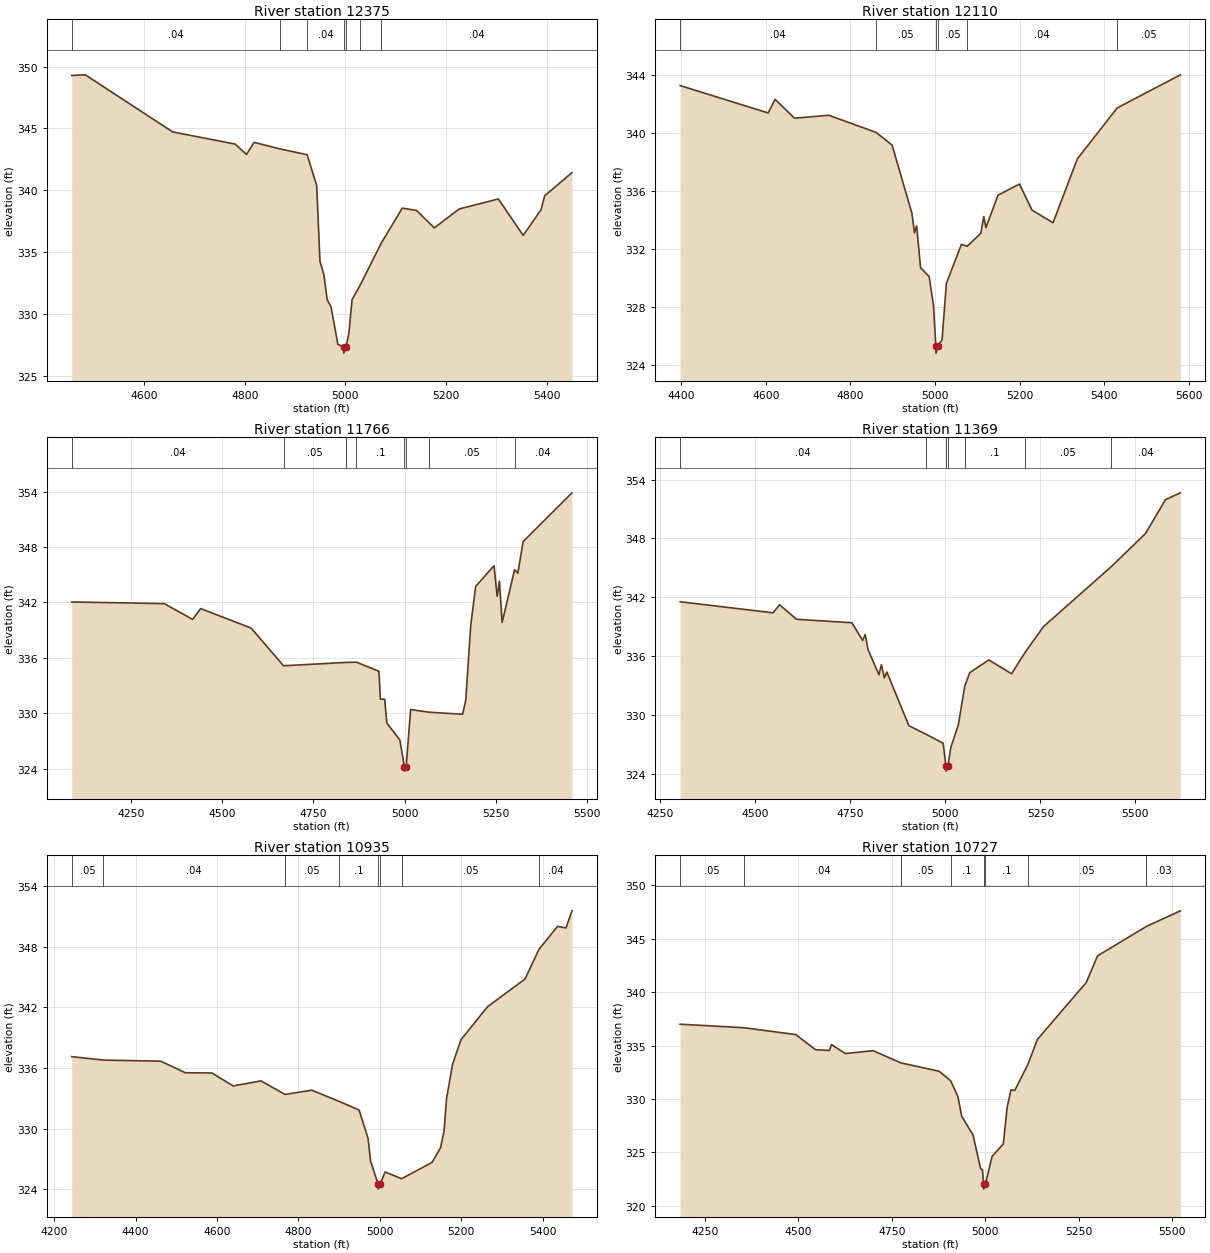
Type RM Length L Ch R = 1,12375,265,265,265
BEGIN DESCRIPTION:
Mapping XS 56b861d1
END DESCRIPTION:
XS GIS Cut Line= 4
      2410797.79     13538116.70      2410662.38     13537682.69
      2410502.66     13537550.75      2410264.05     13537319.06
#Sta/Elev= 30
  4455.9  349.29  4483.0  349.34  4656.7  344.72  4780.7  343.74  4803.4  342.90
  4818.4  343.88  4869.6  343.35  4923.8  342.88  4942.9  340.39  4949.4  334.26
  4957.2  333.19  4963.7  331.15  4971.5  330.56  4985.0  327.54  4996.4  327.33
  4996.8  326.83  5001.3  327.33  5006.7  328.39  5013.2  331.16  5029.5  332.34
  5071.4  335.74  5113.0  338.56  5141.4  338.37  5176.7  336.96  5226.1  338.49
  5304.0  339.30  5353.4  336.35  5388.9  338.44  5395.9  339.55  5450.3  341.43
#Mann=7,-1,0
  4455.9    0.04       0  4869.6    0.05       0  4923.8    0.04       0
  4996.4    0.04       0  5001.3    0.04       0  5029.5    0.05       0
  5071.4    0.04       0
Bank Sta=4996.4,5001.3
Exp/Cntr=0.3,0.1

Type RM Length L Ch R = 1,12110,344,344,344
BEGIN DESCRIPTION:
Mapping XS e312df05
END DESCRIPTION:
XS GIS Cut Line= 4
      2411033.91     13537804.23      2410870.71     13537450.05
      2410457.52     13537373.66      2410165.89     13537141.05
#Sta/Elev= 30
  4397.1  343.30  4605.4  341.41  4621.7  342.35  4667.7  341.05  4748.6  341.25
  4860.8  340.07  4898.5  339.19  4945.4  334.49  4951.4  333.15  4956.5  333.62
  4965.8  330.74  4986.1  330.13  4996.3  328.15  5001.9  325.35  5002.3  324.85
  5006.8  325.35  5016.6  325.75  5026.8  329.65  5062.4  332.35  5076.2  332.22
  5108.1  333.11  5115.3  334.27  5120.4  333.50  5148.8  335.74  5199.7  336.51
  5229.4  334.71  5279.1  333.84  5336.7  338.25  5430.9  341.76  5580.3  344.04
#Mann=6,-1,0
  4397.1    0.04       0  4860.8    0.05       0  5001.9    0.05       0
  5006.8    0.05       0  5076.2    0.04       0  5430.9    0.05       0
Bank Sta=5001.9,5006.8
Exp/Cntr=0.3,0.1

Type RM Length L Ch R = 1,11766,397,397,397
BEGIN DESCRIPTION:
Mapping XS c96593b2
END DESCRIPTION:
XS GIS Cut Line= 4
      2411103.36     13537800.76      2410905.44     13537415.33
      2410568.63     13537175.75      2410263.56     13536749.35
#Sta/Elev= 30
  4087.6  342.04  4341.4  341.86  4418.9  340.15  4441.1  341.32  4579.2  339.22
  4668.1  335.13  4838.4  335.49  4868.0  335.52  4929.7  334.53  4933.4  331.52
  4945.2  331.50  4951.3  328.92  4986.9  327.09  4999.1  324.22  4999.5  323.72
  5004.2  324.22  5016.4  330.39  5067.1  330.10  5158.9  329.88  5167.5  331.42
  5181.0  339.49  5194.6  343.73  5244.9  345.96  5253.5  342.64  5259.7  344.31
  5267.1  339.82  5301.3  345.53  5310.1  345.16  5324.8  348.59  5458.5  353.86
#Mann=8,-1,0
  4087.6    0.04       0  4668.1    0.05       0  4838.4    0.04       0
  4868.0     0.1       0  4999.1    0.05       0  5004.2     0.1       0
  5067.1    0.05       0  5301.3    0.04       0
Bank Sta=4999.1,5004.2
Exp/Cntr=0.3,0.1

Type RM Length L Ch R = 1,11369,434,434,434
BEGIN DESCRIPTION:
Mapping XS 1e8bc49e
END DESCRIPTION:
XS GIS Cut Line= 5
      2411138.09     13537790.36      2410954.05     13537418.80
      2410863.77     13537314.63      2410884.60     13536963.94
      2410704.04     13536592.39
#Sta/Elev= 30
  4301.6  341.54  4546.3  340.41  4563.2  341.24  4608.0  339.75  4753.7  339.40
  4782.2  337.59  4788.8  338.20  4796.4  336.65  4824.9  334.09  4831.5  335.11
  4839.2  333.78  4845.8  334.37  4903.8  328.89  4950.1  327.99  4994.0  327.10
  5001.4  324.75  5001.8  324.25  5006.5  324.75  5014.0  326.65  5034.0  328.98
  5051.0  332.94  5064.1  334.31  5114.2  335.60  5174.3  334.19  5209.5  336.36
  5258.0  339.00  5437.0  345.14  5526.7  348.51  5579.3  351.97  5618.5  352.66
#Mann=7,-1,0
  4301.6    0.04       0  4950.1    0.05       0  5001.4    0.05       0
  5006.5    0.05       0  5051.0     0.1       0  5209.5    0.05       0
  5437.0    0.04       0
Bank Sta=5001.4,5006.5
Exp/Cntr=0.3,0.1

Type RM Length L Ch R = 1,10935,208,208,208
BEGIN DESCRIPTION:
Mapping XS dd6e1f80
END DESCRIPTION:
XS GIS Cut Line= 3
      2411492.25     13537654.93      2411176.27     13537064.63
      2410850.05     13536610.01
#Sta/Elev= 30
  4243.2  337.13  4321.2  336.79  4462.1  336.68  4522.2  335.54  4588.0  335.51
  4640.1  334.23  4708.2  334.73  4767.5  333.39  4832.9  333.81  4900.0  332.71
  4949.2  331.85  4971.3  329.05  4977.5  326.80  4995.9  324.52  4996.3  324.02
  5001.1  324.52  5013.1  325.72  5053.7  325.05  5128.5  326.66  5149.4  328.12
  5158.0  329.75  5164.1  332.96  5178.9  336.38  5199.7  338.81  5264.8  342.07
  5356.9  344.81  5391.4  347.76  5436.7  350.02  5457.6  349.87  5472.3  351.56
#Mann=8,-1,0
  4243.2    0.05       0  4321.2    0.04       0  4767.5    0.05       0
  4900.0     0.1       0  4995.9    0.05       0  5001.1     0.1       0
  5053.7    0.05       0  5391.4    0.04       0
Bank Sta=4995.9,5001.1
Exp/Cntr=0.3,0.1

Type RM Length L Ch R = 1,10727,169,169,169
BEGIN DESCRIPTION:
Mapping XS d0041c5d
END DESCRIPTION:
XS GIS Cut Line= 4
      2411565.16     13537700.05      2411249.19     13537165.33
      2411308.21     13536811.16      2411322.10     13536453.49
#Sta/Elev= 30
  4183.6  337.00  4354.0  336.67  4492.9  336.03  4545.7  334.61  4582.7  334.54
  4588.5  335.09  4625.6  334.25  4699.8  334.52  4774.5  333.37  4876.0  332.60
  4907.1  331.71  4926.5  330.23  4936.8  328.38  4967.2  326.61  4987.3  323.47
  4992.4  323.38  4995.1  322.05  4995.5  321.55  5000.3  322.05  5017.9  324.61
  5048.1  325.79  5058.5  329.24  5068.6  330.85  5078.8  330.80  5113.4  333.20
  5139.6  335.59  5270.0  340.91  5300.0  343.40  5430.9  346.16  5521.7  347.62
#Mann=8,-1,0
  4183.6    0.05       0  4354.0    0.04       0  4774.5    0.05       0
  4907.1     0.1       0  4995.1    0.05       0  5000.3     0.1       0
  5113.4    0.05       0  5430.9    0.03       0
Bank Sta=4995.1,5000.3
Exp/Cntr=0.3,0.1

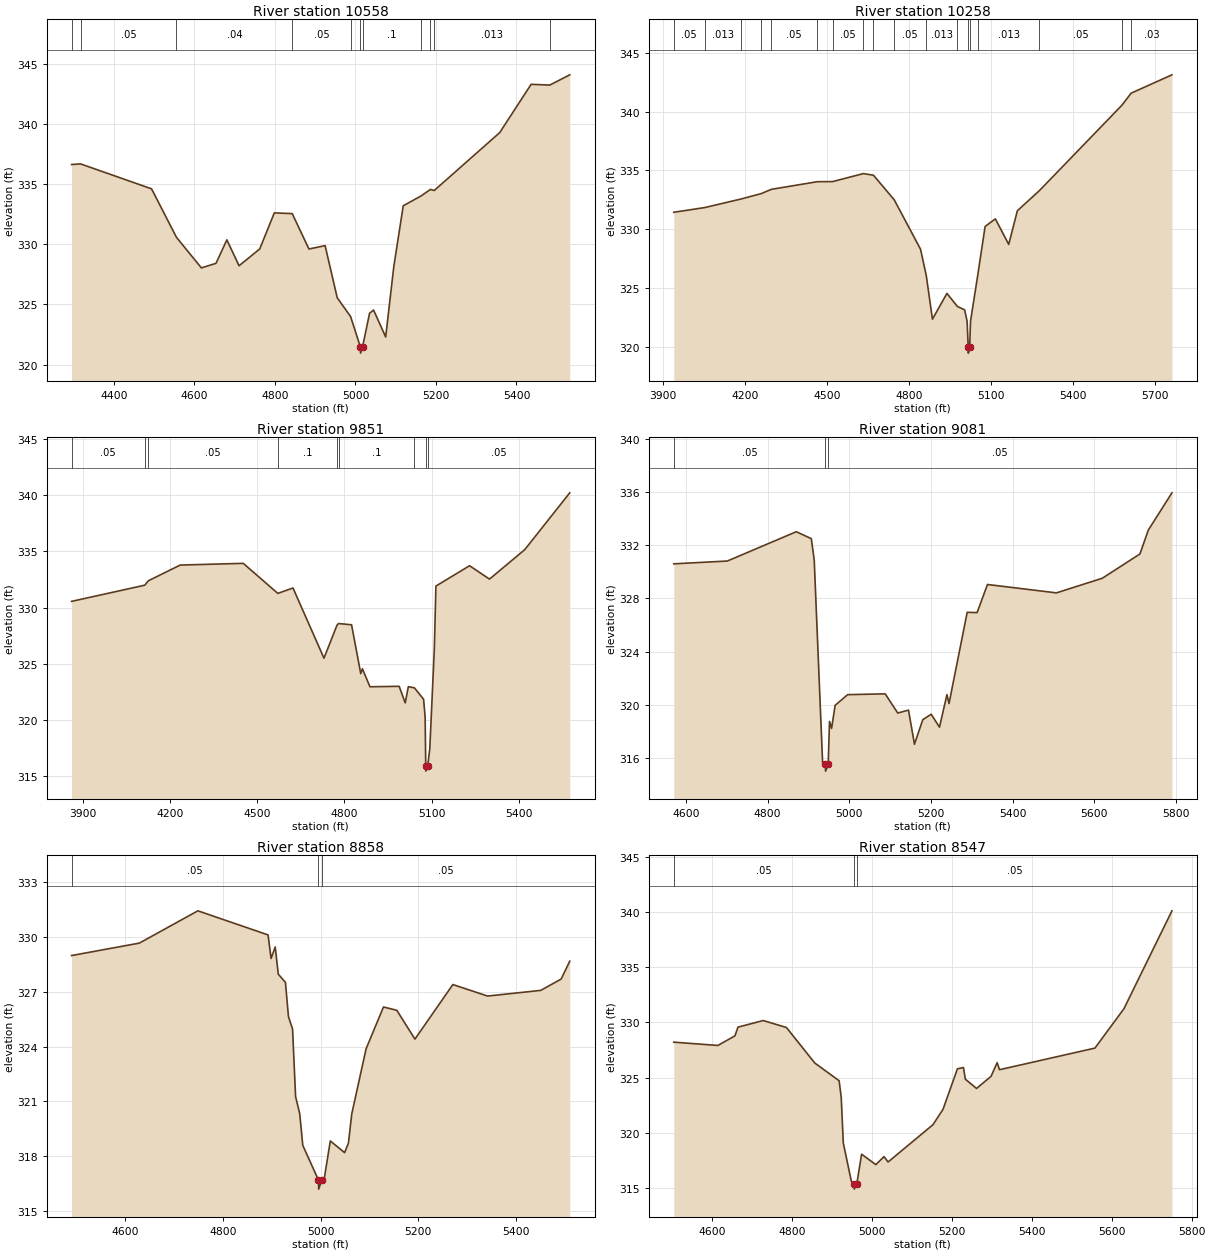
Type RM Length L Ch R = 1,10558,300,300,300
BEGIN DESCRIPTION:
Mapping XS 3c3a7f6b
END DESCRIPTION:
XS GIS Cut Line= 3
      2411707.51     13537647.96      2411415.85     13537200.05
      2411474.82     13536499.32
#Sta/Elev= 30
  4294.7  336.62  4317.1  336.67  4493.4  334.60  4555.3  330.57  4617.2  328.03
  4653.5  328.41  4680.5  330.36  4710.8  328.21  4762.1  329.60  4798.4  332.60
  4842.9  332.54  4884.4  329.60  4924.6  329.88  4954.7  325.55  4987.9  323.99
  5012.3  321.45  5012.7  320.95  5017.5  321.45  5035.0  324.26  5045.0  324.53
  5075.1  322.29  5095.2  328.13  5118.7  333.19  5163.6  334.02  5186.2  334.55
  5195.7  334.46  5358.4  339.27  5436.4  343.28  5482.9  343.22  5532.4  344.07
#Mann=11,-1,0
  4294.7    0.03       0  4317.1    0.05       0  4555.3    0.04       0
  4842.9    0.05       0  4987.9     0.1       0  5012.3    0.05       0
  5017.5     0.1       0  5163.6   0.013       0  5186.2    0.05       0
  5195.7   0.013       0  5482.9    0.03       0
Bank Sta=5012.3,5017.5
Exp/Cntr=0.3,0.1

Type RM Length L Ch R = 1,10258,407,407,407
BEGIN DESCRIPTION:
Mapping XS afef3425
END DESCRIPTION:
XS GIS Cut Line= 4
      2412151.97     13538064.65      2411797.80     13537366.72
      2411522.11     13536884.64      2411540.85     13536401.40
#Sta/Elev= 30
  3939.1  331.44  4052.5  331.84  4183.6  332.56  4258.1  333.02  4295.8  333.39
  4463.8  334.04  4520.2  334.05  4632.4  334.73  4669.4  334.59  4745.2  332.50
  4841.4  328.30  4862.3  326.07  4885.0  322.35  4937.9  324.54  4976.2  323.43
  5002.7  323.14  5011.7  322.17  5015.8  319.96  5016.2  319.46  5021.1  319.96
  5024.2  322.17  5050.9  326.13  5077.5  330.23  5114.9  330.88  5163.9  328.71
  5195.5  331.57  5276.0  333.28  5578.0  340.55  5611.5  341.57  5760.7  343.13
#Mann=18,-1,0
  3939.1    0.05       0  4052.5   0.013       0  4183.6    0.05       0
  4258.1   0.013       0  4295.8    0.05       0  4463.8   0.013       0
  4520.2    0.05       0  4632.4     0.1       0  4669.4   0.013       0
  4745.2    0.05       0  4862.3   0.013       0  4976.2    0.05       0
  5015.8    0.05       0  5021.1    0.05       0  5050.9   0.013       0
  5276.0    0.05       0  5578.0   0.013       0  5611.5    0.03       0
Bank Sta=5015.8,5021.1
Exp/Cntr=0.3,0.1

Type RM Length L Ch R = 1,9851,770,770,770
BEGIN DESCRIPTION:
Mapping XS 55dd5d69
END DESCRIPTION:
XS GIS Cut Line= 3
      2412214.47     13538085.47      2411877.66     13537397.97
      2412177.24     13536498.10
#Sta/Elev= 30
  3861.4  330.55  4113.3  331.99  4125.6  332.38  4235.1  333.78  4452.1  333.93
  4571.0  331.26  4623.2  331.74  4729.8  325.50  4774.7  328.44  4779.8  328.58
  4824.7  328.47  4856.3  324.13  4862.0  324.56  4888.0  322.96  4988.4  323.00
  5009.3  321.53  5020.1  322.97  5041.1  322.86  5072.5  321.85  5077.8  320.28
  5079.9  315.96  5080.4  315.46  5086.7  315.96  5093.8  317.43  5109.5  326.36
  5114.9  331.91  5230.7  333.72  5299.3  332.53  5420.6  335.15  5575.4  340.20
#Mann=9,-1,0
  3861.4    0.05       0  4113.3   0.013       0  4125.6    0.05       0
  4571.0     0.1       0  4774.7    0.05       0  4779.8     0.1       0
  5041.1    0.05       0  5079.9    0.05       0  5086.7    0.05       0
Bank Sta=5079.9,5086.7
Exp/Cntr=0.3,0.1

Type RM Length L Ch R = 1,9081,223,223,223
BEGIN DESCRIPTION:
Mapping XS 8320c2f4
END DESCRIPTION:
XS GIS Cut Line= 3
      2412228.35     13538064.64      2412183.21     13537766.02
      2412373.84     13536868.35
#Sta/Elev= 30
  4570.5  330.60  4701.6  330.81  4870.5  333.01  4907.3  332.49  4914.4  330.88
  4934.9  315.69  4941.7  315.54  4942.2  315.04  4948.6  315.54  4951.8  318.77
  4956.9  318.25  4965.6  319.98  4996.2  320.78  5088.2  320.84  5118.9  319.40
  5145.2  319.62  5159.8  317.06  5180.2  318.90  5200.7  319.31  5221.1  318.34
  5239.3  320.78  5244.4  320.11  5288.9  326.96  5313.1  326.94  5338.6  329.05
  5507.4  328.42  5619.8  329.52  5711.8  331.34  5732.3  333.13  5790.2  335.93
#Mann=3,-1,0
  4570.5    0.05       0  4941.7    0.05       0  4948.6    0.05       0
Bank Sta=4941.7,4948.6
Exp/Cntr=0.3,0.1

Type RM Length L Ch R = 1,8858,311,311,311
BEGIN DESCRIPTION:
Mapping XS 41c1c3c6
END DESCRIPTION:
XS GIS Cut Line= 3
      2412311.69     13538123.71      2412308.21     13537755.61
      2412692.84     13537228.92
#Sta/Elev= 30
  4490.1  328.99  4628.8  329.67  4748.8  331.44  4892.5  330.12  4898.7  328.83
  4907.2  329.46  4913.4  327.97  4928.1  327.52  4934.3  325.64  4942.7  324.96
  4948.9  321.26  4957.4  320.32  4963.6  318.59  4995.7  316.69  4996.2  316.19
  5002.6  316.69  5007.6  316.77  5020.0  318.83  5049.3  318.19  5057.1  318.71
  5064.0  320.32  5093.3  323.88  5128.9  326.17  5156.2  325.99  5193.3  324.41
  5271.0  327.40  5342.1  326.77  5450.9  327.08  5492.7  327.70  5510.4  328.68
#Mann=3,-1,0
  4490.1    0.05       0  4995.7    0.05       0  5002.6    0.05       0
Bank Sta=4995.7,5002.6
Exp/Cntr=0.3,0.1

Type RM Length L Ch R = 1,8547,527,527,527
BEGIN DESCRIPTION:
Mapping XS 71ce96ae
END DESCRIPTION:
XS GIS Cut Line= 4
      2412388.06     13538182.71      2412610.30     13537891.02
      2412538.10     13537530.98      2412816.73     13537101.32
#Sta/Elev= 30
  4504.7  328.21  4615.0  327.91  4657.7  328.78  4665.3  329.57  4728.4  330.17
  4786.5  329.54  4857.3  326.32  4918.3  324.71  4923.6  323.19  4928.7  319.07
  4948.9  315.58  4955.7  315.38  4956.2  314.88  4962.6  315.38  4974.5  318.05
  5010.1  317.10  5030.6  317.83  5040.7  317.34  5152.9  320.72  5178.2  322.12
  5214.1  325.79  5229.2  325.91  5234.0  324.85  5262.0  324.01  5298.3  325.11
  5313.5  326.35  5319.4  325.71  5558.1  327.67  5630.6  331.24  5750.7  340.12
#Mann=3,-1,0
  4504.7    0.05       0  4955.7    0.05       0  4962.6    0.05       0
Bank Sta=4955.7,4962.6
Exp/Cntr=0.3,0.1

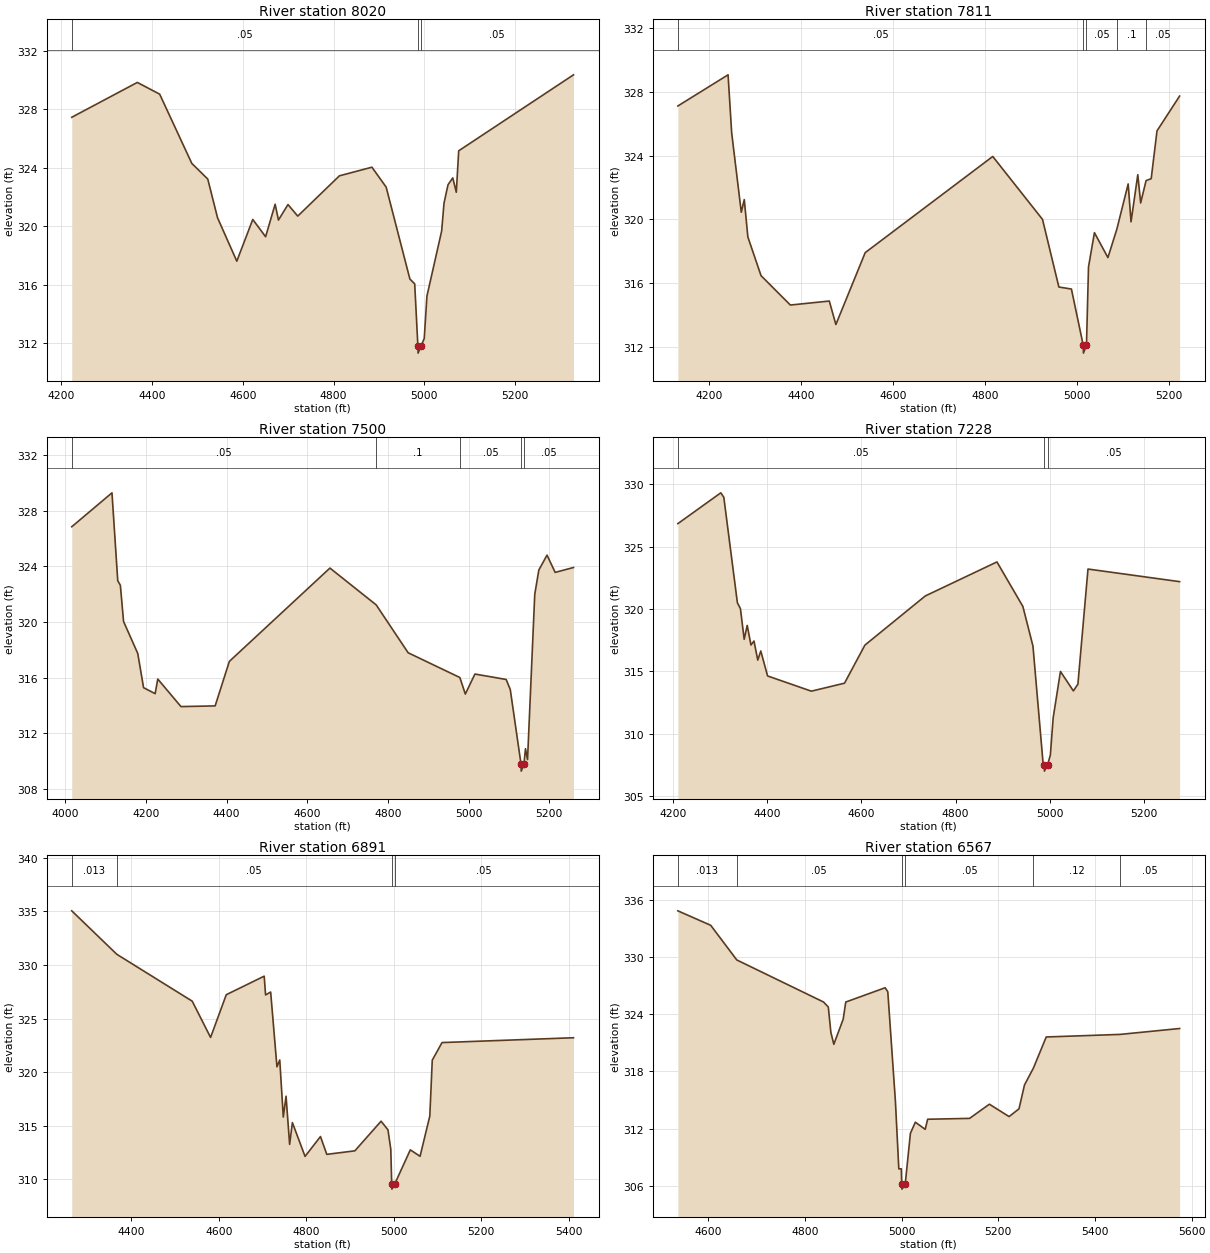
Type RM Length L Ch R = 1,8020,209,209,209
BEGIN DESCRIPTION:
Mapping XS e92b6124
END DESCRIPTION:
XS GIS Cut Line= 3
      2412499.16     13538193.13      2412967.94     13537752.13
      2413106.81     13537311.20
#Sta/Elev= 30
  4223.0  327.45  4367.5  329.83  4416.8  329.03  4487.6  324.30  4522.8  323.23
  4544.3  320.59  4586.8  317.62  4622.0  320.47  4650.3  319.29  4671.3  321.51
  4678.6  320.43  4699.6  321.49  4721.1  320.70  4812.9  323.45  4884.6  324.04
  4916.0  322.68  4968.3  316.40  4978.9  316.07  4985.9  311.84  4986.4  311.34
  4993.0  311.84  4999.9  312.34  5005.9  315.24  5038.3  319.68  5043.5  321.58
  5052.3  322.84  5062.8  323.31  5070.6  322.33  5075.9  325.16  5328.9  330.35
#Mann=3,-1,0
  4223.0    0.05       0  4985.9    0.05       0  4993.0    0.05       0
Bank Sta=4985.9,4993
Exp/Cntr=0.3,0.1

Type RM Length L Ch R = 1,7811,311,311,311
BEGIN DESCRIPTION:
Mapping XS 9342b46a
END DESCRIPTION:
XS GIS Cut Line= 3
      2412565.13     13538259.10      2413106.82     13537804.22
      2413332.50     13537495.21
#Sta/Elev= 30
  4132.7  327.10  4241.8  329.05  4249.6  325.42  4270.5  320.45  4277.0  321.24
  4284.8  318.90  4313.4  316.48  4377.1  314.64  4461.7  314.89  4476.0  313.42
  4539.7  317.92  4816.8  323.94  4924.9  320.00  4960.4  315.77  4987.7  315.64
  5013.3  312.13  5013.8  311.63  5020.4  312.13  5024.8  317.02  5037.7  319.17
  5067.0  317.61  5086.3  319.38  5111.0  322.22  5117.2  319.85  5131.9  322.80
  5138.1  321.03  5149.9  322.43  5161.0  322.55  5173.6  325.54  5222.7  327.72
#Mann=5,-1,0
  4132.7    0.05       0  5013.3    0.05       0  5020.4    0.05       0
  5086.3     0.1       0  5149.9    0.05       0
Bank Sta=5013.3,5020.4
Exp/Cntr=0.3,0.1

Type RM Length L Ch R = 1,7500,272,272,272
BEGIN DESCRIPTION:
Mapping XS a42edb7d
END DESCRIPTION:
XS GIS Cut Line= 3
      2412572.18     13538262.47      2413162.50     13537783.27
      2413639.84     13537858.05
#Sta/Elev= 30
  4016.4  326.85  4116.1  329.29  4130.4  322.97  4136.9  322.64  4144.8  320.04
  4180.0  317.74  4194.4  315.28  4223.1  314.85  4229.6  315.90  4287.1  313.92
  4371.8  313.97  4407.0  317.17  4656.3  323.88  4771.0  321.23  4850.1  317.79
  4978.3  316.01  4991.8  314.82  5015.6  316.26  5093.0  315.87  5103.2  315.15
  5129.9  309.78  5130.4  309.28  5137.1  309.78  5140.9  310.89  5146.0  310.11
  5163.9  321.99  5174.0  323.74  5194.3  324.81  5214.5  323.57  5259.9  323.92
#Mann=5,-1,0
  4016.4    0.05       0  4771.0     0.1       0  4978.3    0.05       0
  5129.9    0.05       0  5137.1    0.05       0
Bank Sta=5129.9,5137.1
Exp/Cntr=0.3,0.1

Type RM Length L Ch R = 1,7228,337,337,337
BEGIN DESCRIPTION:
Mapping XS 6884e759
END DESCRIPTION:
XS GIS Cut Line= 3
      2412572.10     13538269.50      2413099.88     13537845.88
      2413298.75     13538178.40
#Sta/Elev= 30
  4210.9  326.85  4302.0  329.32  4308.4  328.96  4337.2  320.50  4343.6  320.04
  4351.6  317.58  4358.0  318.69  4366.0  317.12  4372.4  317.44  4380.4  315.91
  4386.8  316.64  4401.2  314.64  4494.0  313.42  4564.4  314.06  4607.6  317.11
  4735.6  321.05  4887.7  323.78  4942.7  320.21  4964.1  317.03  4985.5  307.66
  4987.9  307.51  4988.4  307.01  4995.1  307.51  5001.0  308.30  5006.9  311.27
  5022.4  315.00  5049.8  313.44  5059.4  313.98  5080.8  323.21  5275.1  322.20
#Mann=3,-1,0
  4210.9    0.05       0  4987.9    0.05       0  4995.1    0.05       0
Bank Sta=4987.9,4995.1
Exp/Cntr=0.3,0.1

Type RM Length L Ch R = 1,6891,324,324,324
BEGIN DESCRIPTION:
Mapping XS c54f6503
END DESCRIPTION:
XS GIS Cut Line= 5
      2412283.99     13538486.41      2412650.34     13538236.39
      2412839.58     13538088.82      2413037.77     13538188.64
      2413278.20     13538216.93
#Sta/Elev= 30
  4263.6  335.04  4366.6  330.99  4539.1  326.62  4581.1  323.24  4617.0  327.22
  4703.7  328.95  4706.9  327.20  4718.5  327.47  4732.9  320.50  4739.3  321.14
  4747.4  315.82  4753.7  317.76  4761.9  313.27  4768.2  315.30  4797.2  312.15
  4832.4  314.00  4846.9  312.34  4911.1  312.67  4971.0  315.43  4986.8  314.63
  4993.3  312.79  4995.3  309.60  4995.8  309.10  5002.5  309.60  5037.9  312.76
  5060.2  312.16  5082.5  315.91  5088.1  321.12  5110.4  322.76  5411.1  323.21
#Mann=4,-1,0
  4263.6   0.013       0  4366.6    0.05       0  4995.3    0.05       0
  5002.5    0.05       0
Bank Sta=4995.3,5002.5
Exp/Cntr=0.3,0.1

Type RM Length L Ch R = 1,6567,355,355,355
BEGIN DESCRIPTION:
Mapping XS c06ddf8e
END DESCRIPTION:
XS GIS Cut Line= 3
      2412290.99     13538526.32      2412723.26     13538371.81
      2413290.47     13538253.86
#Sta/Elev= 30
  4536.7  334.87  4604.7  333.35  4658.7  329.71  4838.3  325.29  4848.1  324.76
  4853.4  322.10  4859.5  320.85  4878.9  323.49  4884.2  325.29  4965.7  326.79
  4971.2  326.37  4987.0  314.83  4994.0  307.77  4999.2  307.77  5000.0  306.14
  5000.5  305.64  5007.2  306.14  5018.0  311.50  5028.2  312.67  5048.6  311.92
  5053.7  312.98  5140.5  313.07  5181.4  314.56  5222.2  313.26  5242.7  314.07
  5254.1  316.58  5272.7  318.37  5299.1  321.62  5452.0  321.89  5575.1  322.51
#Mann=6,-1,0
  4536.7   0.013       0  4658.7    0.05       0  5000.0    0.05       0
  5007.2    0.05       0  5272.7    0.12       0  5452.0    0.05       0
Bank Sta=5000,5007.2
Exp/Cntr=0.3,0.1

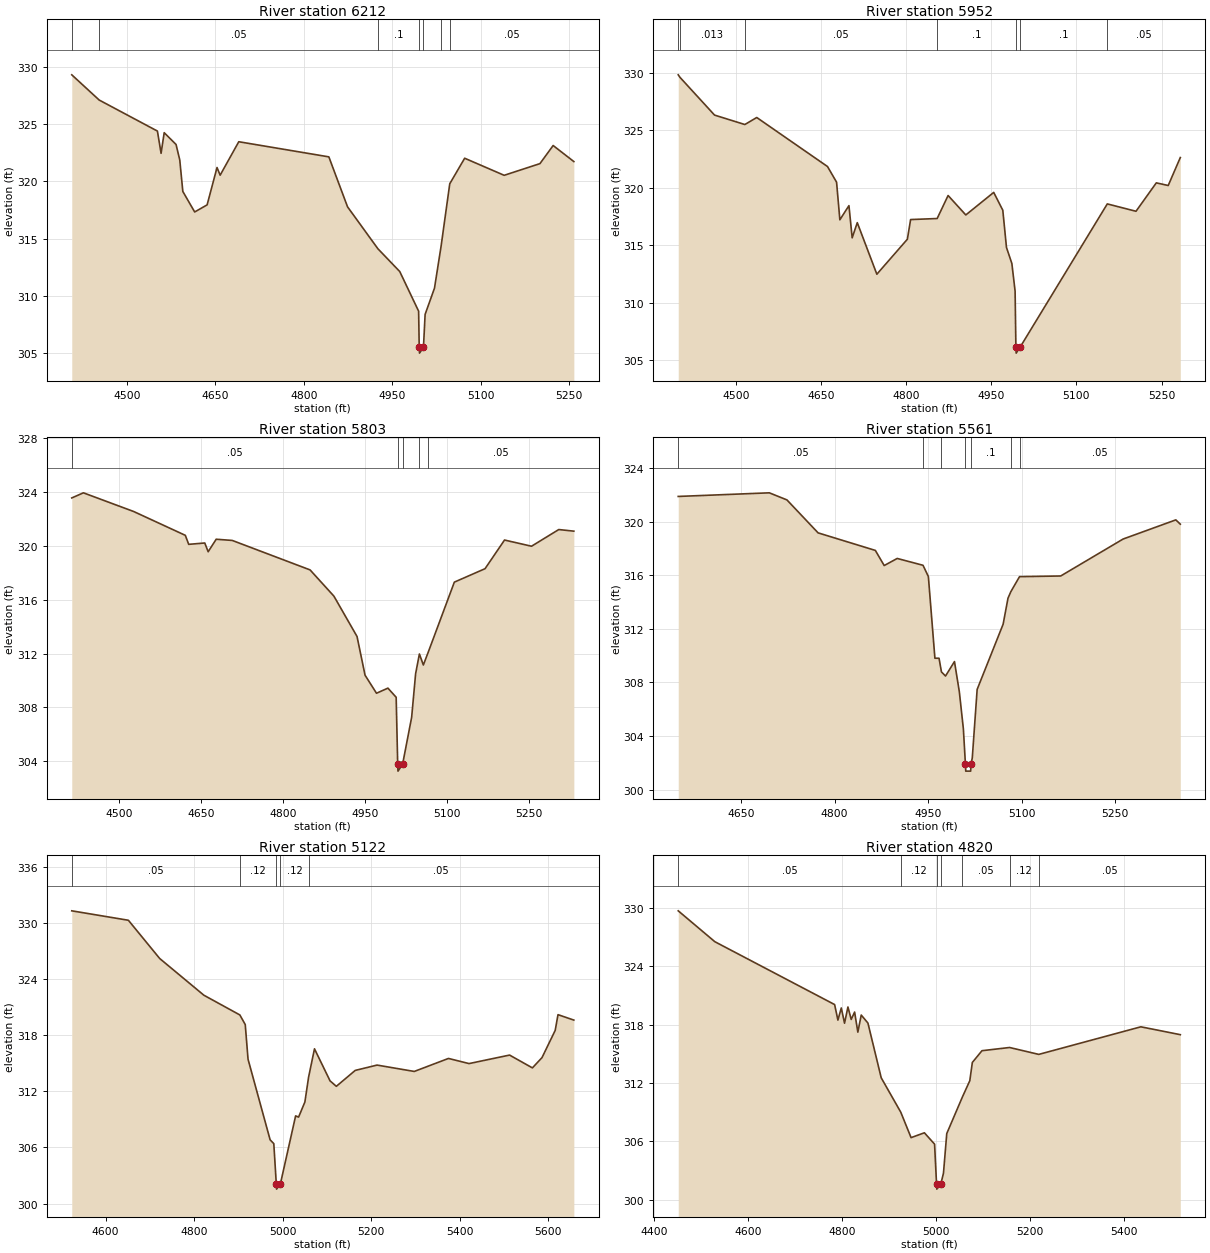
Type RM Length L Ch R = 1,6212,260,260,260
BEGIN DESCRIPTION:
Mapping XS 5a137931
END DESCRIPTION:
XS GIS Cut Line= 3
      2412477.18     13538678.23      2413031.85     13538493.34
      2413270.69     13538373.92
#Sta/Elev= 30
  4406.5  329.29  4453.0  327.09  4551.8  324.38  4558.0  322.44  4563.3  324.24
  4583.4  323.21  4589.7  321.86  4594.9  319.11  4615.0  317.32  4636.1  317.94
  4652.9  321.20  4658.2  320.53  4689.8  323.45  4842.6  322.13  4874.3  317.77
  4925.8  314.11  4962.9  312.12  4994.9  308.66  4995.9  305.50  4996.4  305.00
  5003.1  305.50  5005.9  308.38  5021.8  310.67  5033.0  314.33  5047.7  319.78
  5073.0  322.01  5140.0  320.52  5200.7  321.54  5223.1  323.12  5258.2  321.72
#Mann=7,-1,0
  4406.5   0.013       0  4453.0    0.05       0  4925.8     0.1       0
  4995.9    0.05       0  5003.1     0.1       0  5033.0    0.12       0
  5047.7    0.05       0
Bank Sta=4995.9,5003.1
Exp/Cntr=0.3,0.1

Type RM Length L Ch R = 1,5952,149,149,149
BEGIN DESCRIPTION:
TRIB 1 TO THOMAS CREEK 12.0
END DESCRIPTION:
XS GIS Cut Line= 3
      2412559.04     13539027.17      2413085.34     13538735.12
      2413275.03     13538524.97
#Sta/Elev= 30
  4398.1  329.80  4401.2  329.58  4462.1  326.30  4515.5  325.48  4536.5  326.09
  4661.2  321.83  4677.2  320.47  4683.0  317.20  4699.0  318.43  4704.7  315.63
  4713.7  316.95  4748.2  312.47  4802.0  315.51  4807.7  317.22  4854.5  317.31
  4873.8  319.31  4905.0  317.62  4954.2  319.58  4970.2  318.03  4976.7  314.79
  4986.2  313.40  4991.9  310.99  4993.3  306.11  4993.8  305.61  5000.5  306.11
  5154.4  318.58  5205.0  317.94  5240.8  320.41  5261.8  320.18  5283.1  322.61
#Mann=7,-1,0
  4398.1    0.05       0  4401.2   0.013       0  4515.5    0.05       0
  4854.5     0.1       0  4993.3    0.05       0  5000.5     0.1       0
  5154.4    0.05       0
Bank Sta=4993.3,5000.5
Exp/Cntr=0.3,0.1

Type RM Length L Ch R = 1,5803,242,242,242
BEGIN DESCRIPTION:
Mapping XS 0a35d2c7
END DESCRIPTION:
XS GIS Cut Line= 3
      2412865.00     13539283.72      2413208.45     13538808.05
      2413435.51     13538566.25
#Sta/Elev= 30
  4413.3  323.57  4434.6  323.95  4526.6  322.56  4621.0  320.79  4627.2  320.12
  4656.6  320.22  4662.8  319.57  4677.5  320.50  4706.9  320.41  4849.2  318.22
  4892.8  316.27  4935.1  313.27  4949.8  310.39  4970.7  309.05  4991.6  309.43
  5006.7  308.75  5009.5  303.76  5010.0  303.26  5018.4  303.76  5035.0  307.26
  5042.3  310.51  5049.2  311.97  5056.4  311.15  5065.7  312.14  5113.1  317.31
  5169.3  318.31  5204.9  320.44  5254.3  319.98  5304.1  321.22  5331.7  321.10
#Mann=5,-1,0
  4413.3    0.05       0  5009.5    0.05       0  5018.4    0.05       0
  5049.2     0.1       0  5065.7    0.05       0
Bank Sta=5009.5,5018.4
Exp/Cntr=0.3,0.1

Type RM Length L Ch R = 1,5561,439,439,439
BEGIN DESCRIPTION:
TRIB 1 TO THOMAS CREEK 11.0
END DESCRIPTION:
XS GIS Cut Line= 3
      2413068.19     13539255.00      2413375.00     13538975.00
      2413625.01     13538674.99
#Sta/Elev= 30
  4549.0  321.89  4695.2  322.16  4723.5  321.63  4773.5  319.17  4865.4  317.86
  4879.6  316.73  4900.5  317.26  4941.9  316.75  4950.5  315.91  4961.0  309.81
  4967.6  309.81  4971.5  308.79  4978.0  308.48  4992.4  309.56  5000.2  307.31
  5006.7  304.53  5010.0  301.88  5010.5  301.38  5018.4  301.38  5018.9  301.88
  5021.0  302.37  5028.8  307.48  5070.5  312.35  5078.3  314.29  5082.9  314.78
  5096.8  315.90  5162.9  315.95  5263.1  318.71  5347.7  320.14  5354.9  319.82
#Mann=7,-1,0
  4549.0    0.05       0  4941.9    0.12       0  4971.5     0.1       0
  5010.0    0.05       0  5018.9     0.1       0  5082.9    0.12       0
  5096.8    0.05       0
Bank Sta=5010,5018.9
Exp/Cntr=0.3,0.1

Type RM Length L Ch R = 1,5122,302,302,302
BEGIN DESCRIPTION:
Mapping XS 74bea142
END DESCRIPTION:
XS GIS Cut Line= 4
      2413120.38     13539639.18      2413492.79     13539355.32
      2413656.85     13539170.42      2413758.41     13538764.18
#Sta/Elev= 30
  4523.8  331.30  4651.7  330.29  4722.5  326.20  4822.2  322.28  4903.5  320.17
  4915.7  319.14  4922.0  315.44  4971.9  306.82  4980.2  306.41  4985.9  302.05
  4986.4  301.55  4994.8  302.05  5029.5  309.38  5036.2  309.25  5050.4  310.86
  5058.8  313.52  5072.1  316.55  5107.3  313.12  5121.5  312.54  5164.1  314.24
  5213.5  314.81  5297.5  314.13  5374.8  315.52  5421.2  314.97  5512.8  315.88
  5564.4  314.51  5586.1  315.61  5615.9  318.52  5622.2  320.20  5658.0  319.62
#Mann=5,-1,0
  4523.8    0.05       0  4903.5    0.12       0  4985.9    0.05       0
  4994.8    0.12       0  5058.8    0.05       0
Bank Sta=4985.9,4994.8
Exp/Cntr=0.3,0.1

Type RM Length L Ch R = 1,4820,245,245,245
BEGIN DESCRIPTION:
Mapping XS 606bd727
END DESCRIPTION:
XS GIS Cut Line= 3
      2413380.78     13539811.08      2413774.04     13539433.44
      2413886.03     13538923.00
#Sta/Elev= 30
  4451.2  329.72  4529.1  326.54  4783.8  320.07  4790.8  318.47  4798.0  319.72
  4804.9  318.15  4812.1  319.82  4819.1  318.54  4826.3  319.30  4833.2  317.23
  4840.4  318.99  4854.6  318.17  4882.9  312.53  4924.5  308.99  4946.4  306.37
  4974.7  306.87  4996.4  305.70  5000.6  301.57  5001.1  301.07  5009.5  301.57
  5015.3  302.71  5022.3  306.79  5055.7  310.57  5071.3  312.23  5076.7  314.11
  5097.2  315.32  5155.9  315.65  5218.0  314.94  5435.1  317.78  5519.0  316.97
#Mann=7,-1,0
  4451.2    0.05       0  4924.5    0.12       0  5000.6    0.05       0
  5009.5    0.12       0  5055.7    0.05       0  5155.9    0.12       0
  5218.0    0.05       0
Bank Sta=5000.6,5009.5
Exp/Cntr=0.3,0.1