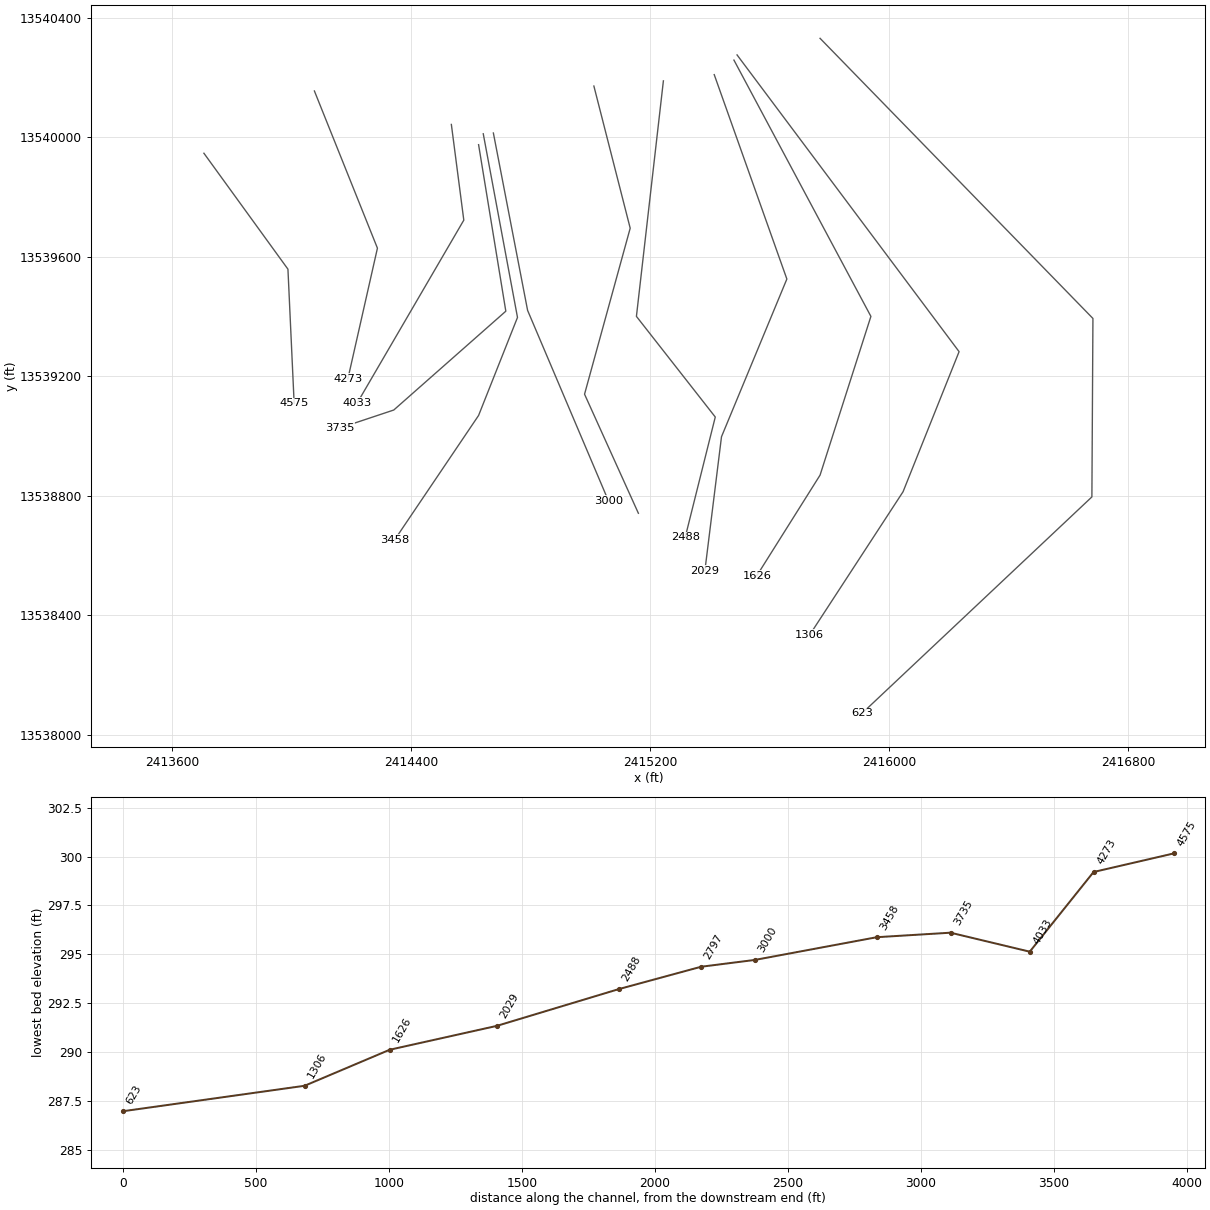
HEC-RAS study TRIB 1 TO THOMAS CREEK.prj: TRIB 1 TO THOMAS CREEK Base Level Engineering

--- TRIB 1 TO THOMAS CREEK.g01 (geometry) --- (continued)

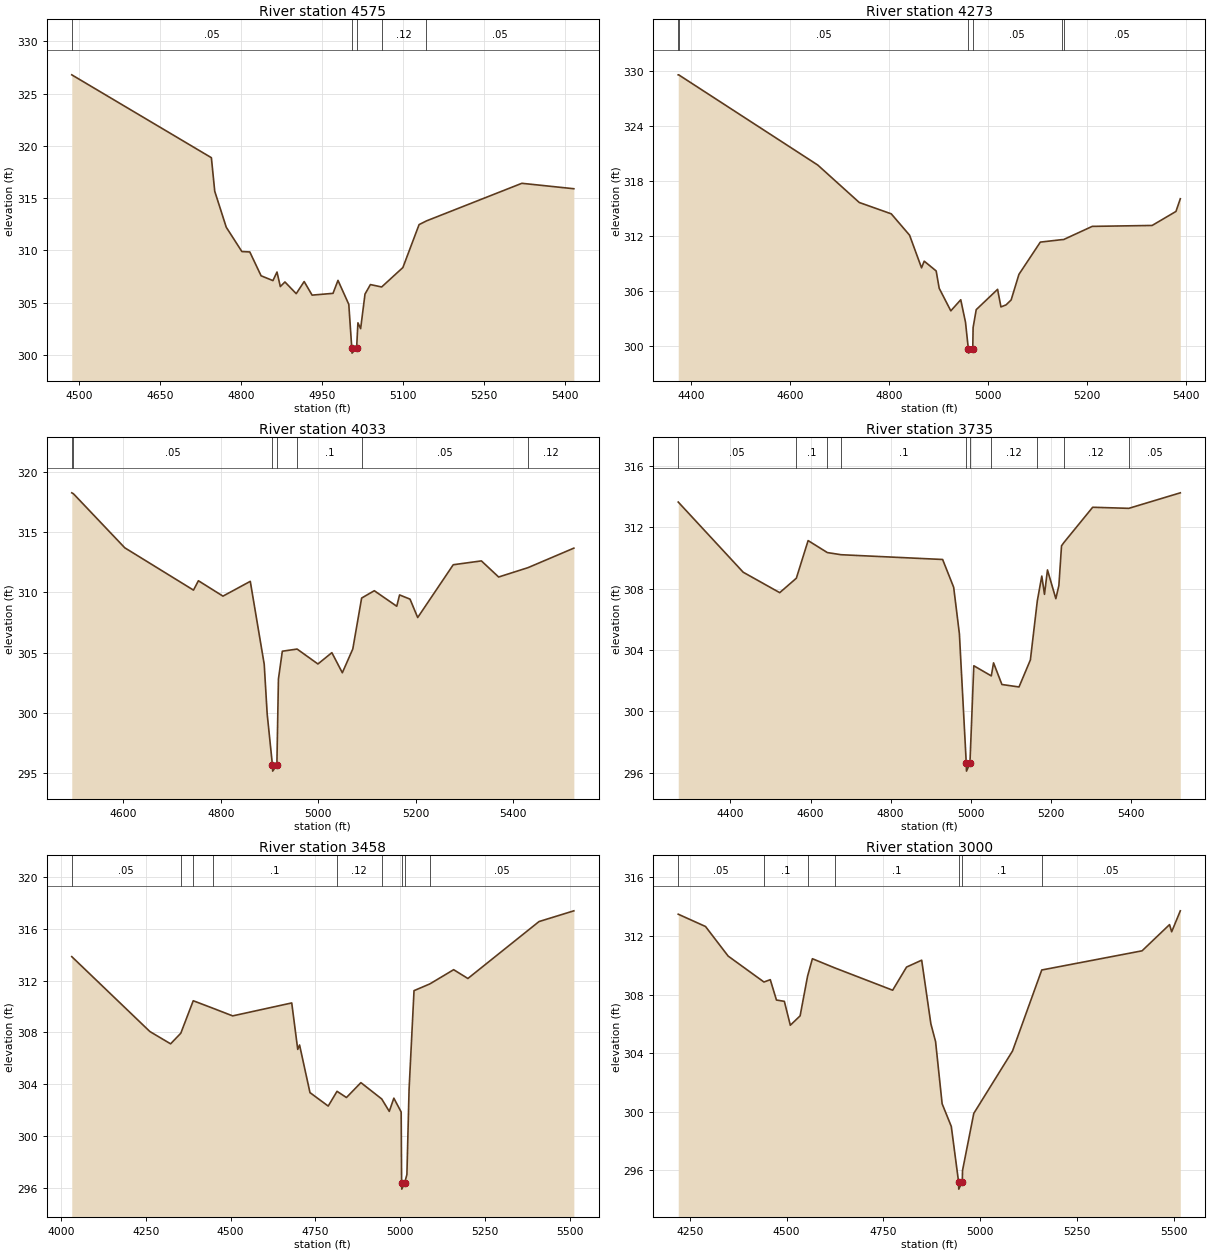
Type RM Length L Ch R = 1,4575,302,302,302
BEGIN DESCRIPTION:
Mapping XS 5b61dd8b
END DESCRIPTION:
XS GIS Cut Line= 3
      2413706.33     13539946.46      2413987.58     13539558.44
      2414008.37     13539108.95
#Sta/Elev= 30
  4486.6  326.79  4745.0  318.86  4751.2  315.65  4772.5  312.21  4801.4  309.88
  4816.1  309.84  4837.0  307.56  4858.9  307.10  4866.4  307.92  4872.6  306.53
  4881.1  306.97  4902.0  305.85  4916.7  307.01  4931.4  305.71  4970.1  305.88
  4979.3  307.12  4999.3  304.83  5004.8  300.66  5005.3  300.16  5013.8  300.66
  5016.2  303.06  5021.2  302.50  5029.3  305.81  5039.3  306.72  5060.1  306.49
  5099.4  308.35  5129.4  312.46  5142.9  312.81  5319.6  316.41  5415.8  315.89
#Mann=5,-1,0
  4486.6    0.05       0  5004.8    0.05       0  5013.8    0.05       0
  5060.1    0.12       0  5142.9    0.05       0
Bank Sta=5004.8,5013.8
Exp/Cntr=0.3,0.1

Type RM Length L Ch R = 1,4273,240,240,240
BEGIN DESCRIPTION:
Mapping XS 0860babc
END DESCRIPTION:
XS GIS Cut Line= 3
      2414076.12     13540154.82      2414287.06     13539628.76
      2414188.11     13539191.28
#Sta/Elev= 30
  4374.0  329.62  4374.9  329.62  4656.2  319.76  4740.1  315.67  4804.8  314.43
  4841.8  312.10  4866.0  308.53  4871.4  309.26  4895.6  308.19  4901.7  306.30
  4925.2  303.83  4945.3  305.04  4954.9  302.59  4960.6  299.71  4961.1  299.21
  4969.6  299.71  4970.3  302.01  4976.6  303.96  5019.8  306.18  5026.6  304.26
  5036.9  304.48  5047.2  305.02  5063.0  307.82  5106.2  311.34  5149.7  311.61
  5153.3  311.62  5211.2  313.06  5332.3  313.16  5380.5  314.69  5389.3  316.08
#Mann=6,-1,0
  4374.0    0.03       0  4374.9    0.05       0  4960.6    0.05       0
  4969.6    0.05       0  5149.7    0.12       0  5153.3    0.05       0
Bank Sta=4960.6,4969.6
Exp/Cntr=0.3,0.1

Type RM Length L Ch R = 1,4033,298,298,298
BEGIN DESCRIPTION:
Mapping XS fcb6c05a
END DESCRIPTION:
XS GIS Cut Line= 3
      2414534.45     13540042.85      2414576.12     13539722.51
      2414219.67     13539111.07
#Sta/Elev= 30
  4494.1  318.28  4497.6  318.20  4602.9  313.71  4744.0  310.19  4754.1  310.97
  4804.5  309.69  4860.6  310.92  4889.2  304.03  4895.3  299.89  4906.1  295.64
  4906.6  295.14  4915.2  295.64  4918.4  302.80  4926.4  305.11  4956.7  305.29
  4999.5  304.05  5028.1  304.99  5049.6  303.32  5071.1  305.30  5089.2  309.53
  5115.2  310.14  5161.3  308.85  5167.1  309.79  5188.6  309.44  5204.3  307.91
  5277.3  312.30  5335.1  312.62  5370.5  311.28  5430.9  312.06  5524.9  313.68
#Mann=7,-1,0
  4494.1    0.03       0  4497.6    0.05       0  4906.1    0.05       0
  4915.2    0.05       0  4956.7     0.1       0  5089.2    0.05       0
  5430.9    0.12       0
Bank Sta=4906.1,4915.2
Exp/Cntr=0.3,0.1

Type RM Length L Ch R = 1,3735,277,277,277
BEGIN DESCRIPTION:
Mapping XS 1f14dc02
END DESCRIPTION:
XS GIS Cut Line= 4
      2414625.60     13539975.13      2414716.75     13539417.82
      2414341.75     13539087.09      2414162.09     13539027.20
#Sta/Elev= 30
  4269.5  313.63  4431.8  309.06  4523.0  307.73  4564.5  308.67  4593.9  311.12
  4642.0  310.34  4676.4  310.20  4929.9  309.89  4957.5  308.08  4971.8  305.05
  4989.0  296.61  4989.5  296.11  4998.1  296.61  5007.8  302.97  5051.5  302.31
  5057.1  303.16  5078.0  301.75  5120.7  301.59  5149.1  303.35  5166.4  307.19
  5177.6  308.81  5184.3  307.62  5191.8  309.21  5212.7  307.34  5220.3  308.20
  5226.9  310.78  5232.7  310.99  5304.7  313.29  5394.9  313.22  5523.6  314.23
#Mann=10,-1,0
  4269.5    0.05       0  4564.5     0.1       0  4642.0    0.05       0
  4676.4     0.1       0  4989.0    0.05       0  4998.1     0.1       0
  5051.5    0.12       0  5166.4    0.05       0  5232.7    0.12       0
  5394.9    0.05       0
Bank Sta=4989,4998.1
Exp/Cntr=0.3,0.1

Type RM Length L Ch R = 1,3458,458,458,458
BEGIN DESCRIPTION:
Mapping XS d70421a9
END DESCRIPTION:
XS GIS Cut Line= 4
      2414641.23     13540011.54      2414755.81     13539396.98
      2414625.60     13539068.86      2414344.33     13538652.16
#Sta/Elev= 30
  4031.6  313.85  4262.0  308.06  4323.1  307.11  4353.2  307.93  4389.9  310.44
  4447.1  309.87  4506.2  309.27  4680.4  310.27  4698.1  306.68  4703.5  307.02
  4734.2  303.34  4788.0  302.30  4814.0  303.44  4841.8  302.96  4884.4  304.11
  4945.8  302.85  4968.1  301.89  4981.6  302.91  5003.2  301.84  5004.5  296.38
  5005.0  295.88  5013.7  296.38  5020.1  297.01  5026.5  303.57  5041.1  311.22
  5087.7  311.74  5158.0  312.84  5200.0  312.16  5409.8  316.56  5512.5  317.39
#Mann=9,-1,0
  4031.6    0.05       0  4353.2     0.1       0  4389.9    0.05       0
  4447.1     0.1       0  4814.0    0.12       0  4945.8     0.1       0
  5004.5    0.05       0  5013.7     0.1       0  5087.7    0.05       0
Bank Sta=5004.5,5013.7
Exp/Cntr=0.3,0.1

Type RM Length L Ch R = 1,3000,203,203,203
BEGIN DESCRIPTION:
Mapping XS 8791c204
END DESCRIPTION:
XS GIS Cut Line= 3
      2414675.08     13540014.19      2414789.67     13539420.42
      2415060.25     13538783.00
#Sta/Elev= 30
  4220.1  313.49  4290.6  312.65  4349.1  310.63  4441.6  308.86  4457.9  309.02
  4473.9  307.63  4494.3  307.54  4509.7  305.91  4535.0  306.55  4554.2  309.25
  4566.7  310.45  4624.0  309.83  4774.1  308.30  4810.0  309.88  4849.1  310.35
  4872.8  306.01  4885.0  304.79  4901.9  300.55  4925.6  299.00  4944.4  295.22
  4944.9  294.72  4954.0  295.22  4954.6  295.99  4983.7  299.89  5083.8  304.15
  5159.3  309.68  5418.5  310.99  5489.5  312.78  5495.0  312.29  5517.3  313.72
#Mann=7,-1,0
  4220.1    0.05       0  4441.6     0.1       0  4554.2    0.05       0
  4624.0     0.1       0  4944.4    0.05       0  4954.0     0.1       0
  5159.3    0.05       0
Bank Sta=4944.4,4954
Exp/Cntr=0.3,0.1

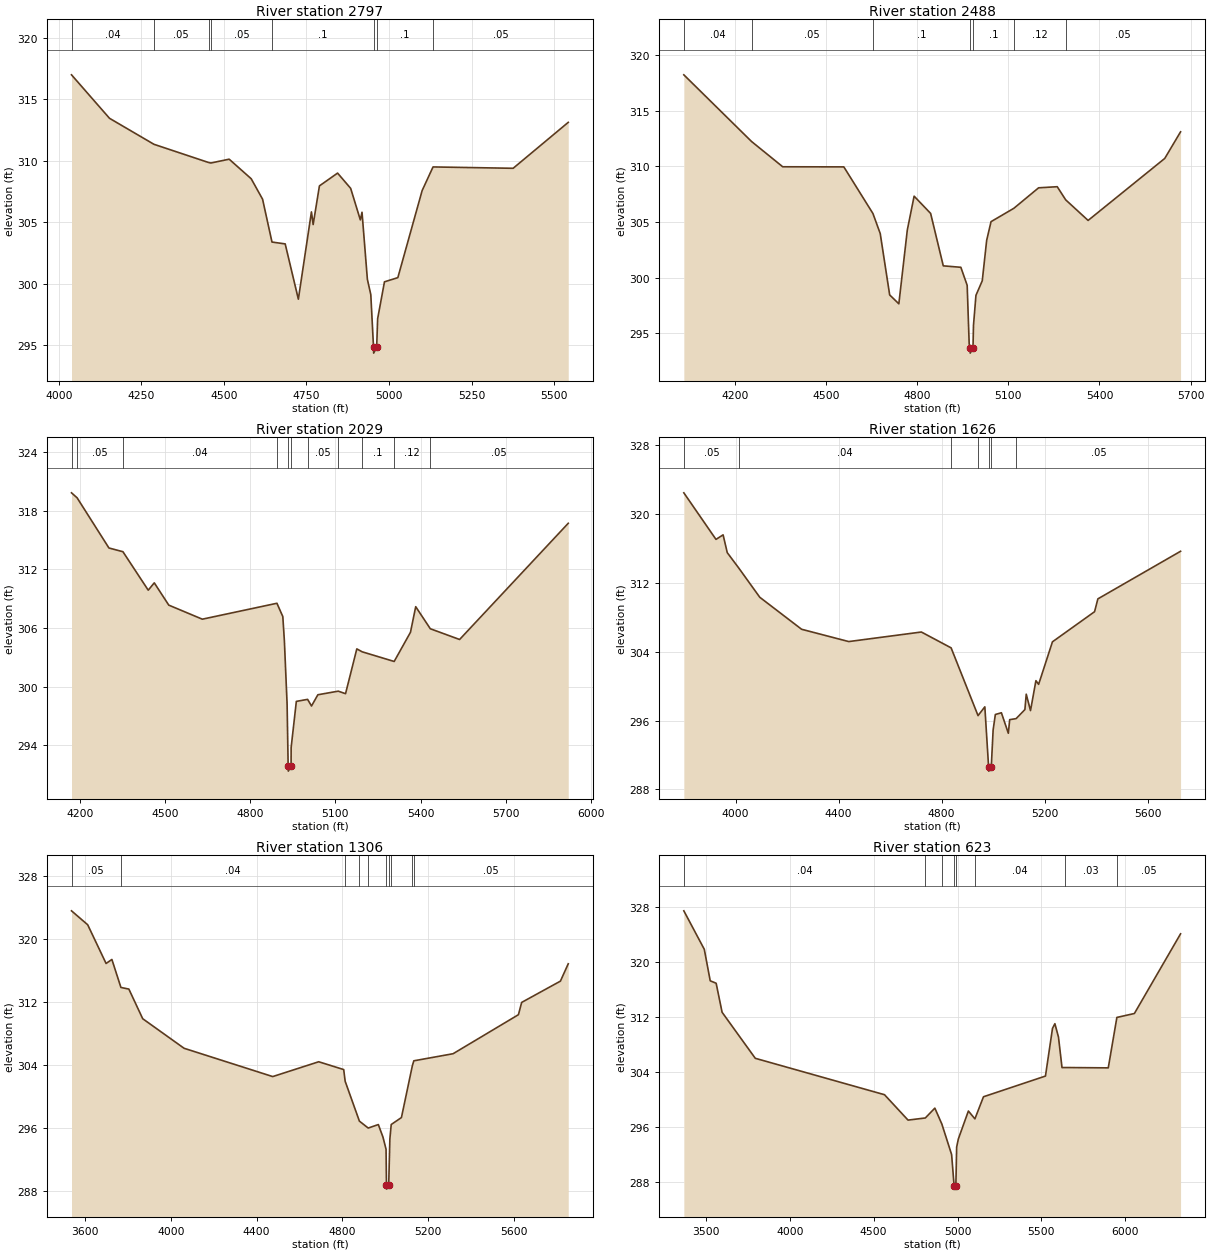
Type RM Length L Ch R = 1,2797,309,309,309
BEGIN DESCRIPTION:
Mapping XS a2d72220
END DESCRIPTION:
XS GIS Cut Line= 4
      2415011.45     13540171.31      2415132.98     13539695.60
      2414980.20     13539140.04      2415160.39     13538741.55
#Sta/Elev= 30
  4038.4  316.97  4153.5  313.44  4288.0  311.33  4453.6  309.85  4460.8  309.81
  4515.9  310.12  4582.7  308.53  4617.1  306.87  4645.6  303.39  4685.6  303.24
  4725.5  298.75  4765.1  305.84  4770.3  304.81  4789.3  307.95  4844.3  308.99
  4883.9  307.75  4913.2  305.19  4918.3  305.81  4934.5  300.37  4944.9  299.12
  4953.1  294.87  4953.6  294.37  4962.7  294.87  4965.6  297.16  4986.3  300.16
  5026.8  300.50  5100.4  307.57  5133.4  309.49  5376.0  309.38  5542.9  313.11
#Mann=8,-1,0
  4038.4    0.04       0  4288.0    0.05       0  4453.6    0.12       0
  4460.8    0.05       0  4645.6     0.1       0  4953.1    0.05       0
  4962.7     0.1       0  5133.4    0.05       0
Bank Sta=4953.1,4962.7
Exp/Cntr=0.3,0.1

Type RM Length L Ch R = 1,2488,459,459,459
BEGIN DESCRIPTION:
Mapping XS 3ad14f9a
END DESCRIPTION:
XS GIS Cut Line= 4
      2415244.09     13540188.66      2415153.82     13539400.46
      2415417.70     13539063.65      2415317.01     13538660.88
#Sta/Elev= 30
  4030.9  318.23  4254.0  312.24  4356.7  309.97  4558.0  309.96  4653.9  305.77
  4677.9  303.97  4709.0  298.46  4739.2  297.66  4767.1  304.29  4789.5  307.33
  4843.9  305.78  4885.6  301.07  4943.5  300.94  4964.3  299.32  4970.9  294.07
  4973.9  293.73  4974.4  293.23  4983.5  293.73  4985.1  295.73  4993.2  298.42
  5014.0  299.73  5028.5  303.36  5042.9  305.04  5118.1  306.24  5199.6  308.08
  5261.0  308.18  5288.8  307.00  5362.7  305.15  5615.2  310.72  5667.3  313.11
#Mann=7,-1,0
  4030.9    0.04       0  4254.0    0.05       0  4653.9     0.1       0
  4973.9    0.05       0  4983.5     0.1       0  5118.1    0.12       0
  5288.8    0.05       0
Bank Sta=4973.9,4983.5
Exp/Cntr=0.3,0.1

Type RM Length L Ch R = 1,2029,403,403,403
BEGIN DESCRIPTION:
Mapping XS 337fe688
END DESCRIPTION:
XS GIS Cut Line= 4
      2415414.22     13540209.52      2415657.29     13539525.46
      2415438.54     13538997.68      2415383.00     13538549.89
#Sta/Elev= 30
  4171.2  319.85  4190.9  319.34  4303.0  314.20  4352.2  313.82  4441.3  309.88
  4462.6  310.63  4513.6  308.35  4631.7  306.91  4894.3  308.54  4915.0  307.18
  4920.5  304.70  4930.1  298.21  4933.8  291.85  4934.3  291.35  4944.1  291.85
  4944.3  293.76  4962.6  298.49  5002.2  298.70  5016.0  298.02  5038.4  299.17
  5110.2  299.54  5135.8  299.28  5175.5  303.87  5194.2  303.57  5307.0  302.58
  5364.4  305.57  5382.8  308.19  5434.2  305.93  5537.3  304.83  5919.7  316.73
#Mann=11,-1,0
  4171.2    0.04       0  4190.9    0.05       0  4352.2    0.04       0
  4894.3     0.1       0  4933.8    0.05       0  4944.1     0.1       0
  5002.2    0.05       0  5110.2    0.12       0  5194.2     0.1       0
  5307.0    0.12       0  5434.2    0.05       0
Bank Sta=4933.8,4944.1
Exp/Cntr=0.3,0.1

Type RM Length L Ch R = 1,1626,320,320,320
BEGIN DESCRIPTION:
Mapping XS 4dc65e75
END DESCRIPTION:
XS GIS Cut Line= 4
      2415480.18     13540258.13      2415938.54     13539400.46
      2415768.40     13538869.21      2415556.58     13538532.37
#Sta/Elev= 30
  3799.4  322.46  3924.2  317.05  3951.8  317.58  3968.0  315.51  4013.2  313.70
  4094.1  310.33  4256.5  306.61  4439.5  305.18  4721.4  306.29  4836.9  304.45
  4941.4  296.58  4967.8  297.60  4982.4  290.63  4982.9  290.13  4992.8  290.63
  5000.0  294.92  5008.6  296.71  5032.1  296.91  5059.0  294.53  5064.3  296.11
  5089.3  296.23  5123.3  297.28  5128.5  299.07  5145.1  297.16  5166.1  300.64
  5176.6  300.21  5230.2  305.15  5393.7  308.65  5406.6  310.14  5727.6  315.67
#Mann=7,-1,0
  3799.4    0.05       0  4013.2    0.04       0  4836.9    0.05       0
  4941.4    0.12       0  4982.4    0.05       0  4992.8    0.12       0
  5089.3    0.05       0
Bank Sta=4982.4,4992.8
Exp/Cntr=0.3,0.1

Type RM Length L Ch R = 1,1306,683,683,683
BEGIN DESCRIPTION:
Mapping XS b32dce80
END DESCRIPTION:
XS GIS Cut Line= 4
      2415490.59     13540275.50      2416233.68     13539282.40
      2416046.18     13538813.65      2415733.65     13538334.44
#Sta/Elev= 30
  3536.3  323.60  3611.9  321.83  3697.6  316.92  3724.7  317.43  3766.8  313.88
  3803.9  313.67  3868.5  309.91  4061.5  306.16  4475.0  302.57  4689.6  304.45
  4806.1  303.46  4813.0  301.97  4879.3  296.92  4920.4  296.04  4967.7  296.48
  4989.2  294.90  5003.7  293.35  5005.6  288.79  5006.1  288.29  5016.0  288.79
  5021.5  294.66  5027.8  296.49  5075.4  297.37  5126.3  303.94  5133.2  304.57
  5316.4  305.47  5621.2  310.42  5636.3  311.98  5817.1  314.68  5853.6  316.88
#Mann=10,-1,0
  3536.3    0.05       0  3766.8    0.04       0  4813.0    0.05       0
  4879.3    0.04       0  4920.4    0.05       0  5005.6    0.05       0
  5016.0    0.05       0  5027.8     0.1       0  5126.3    0.12       0
  5133.2    0.05       0
Bank Sta=5005.6,5016
Exp/Cntr=0.3,0.1

Type RM Length L Ch R = 1,623,0,0,0
BEGIN DESCRIPTION:
TRIB 1 TO THOMAS CREEK 1.0
END DESCRIPTION:
XS GIS Cut Line= 4
      2415768.42     13540330.99      2416681.59     13539393.51
      2416678.12     13538796.29      2415908.63     13538071.86
#Sta/Elev= 30
  3367.7  327.43  3489.7  321.84  3525.1  317.26  3560.4  316.91  3595.9  312.69
  3793.9  306.00  4564.6  300.71  4704.9  297.02  4808.0  297.33  4864.9  298.76
  4906.6  296.45  4964.9  292.01  4979.7  287.49  4980.2  286.99  4990.2  287.49
  4994.9  293.10  5004.9  294.27  5064.9  298.34  5103.8  297.20  5154.9  300.41
  5524.6  303.42  5566.6  310.35  5580.8  311.03  5602.2  309.09  5623.3  304.65
  5640.9  304.66  5899.2  304.61  5950.6  311.94  6055.0  312.51  6330.5  324.09
#Mann=8,-1,0
  3367.7    0.04       0  4808.0    0.12       0  4906.6     0.1       0
  4979.7    0.05       0  4990.2     0.1       0  5103.8    0.04       0
  5640.9    0.03       0  5950.6    0.05       0
Bank Sta=4979.7,4990.2
Exp/Cntr=0.3,0.1

Chan Stop Cuts=-1