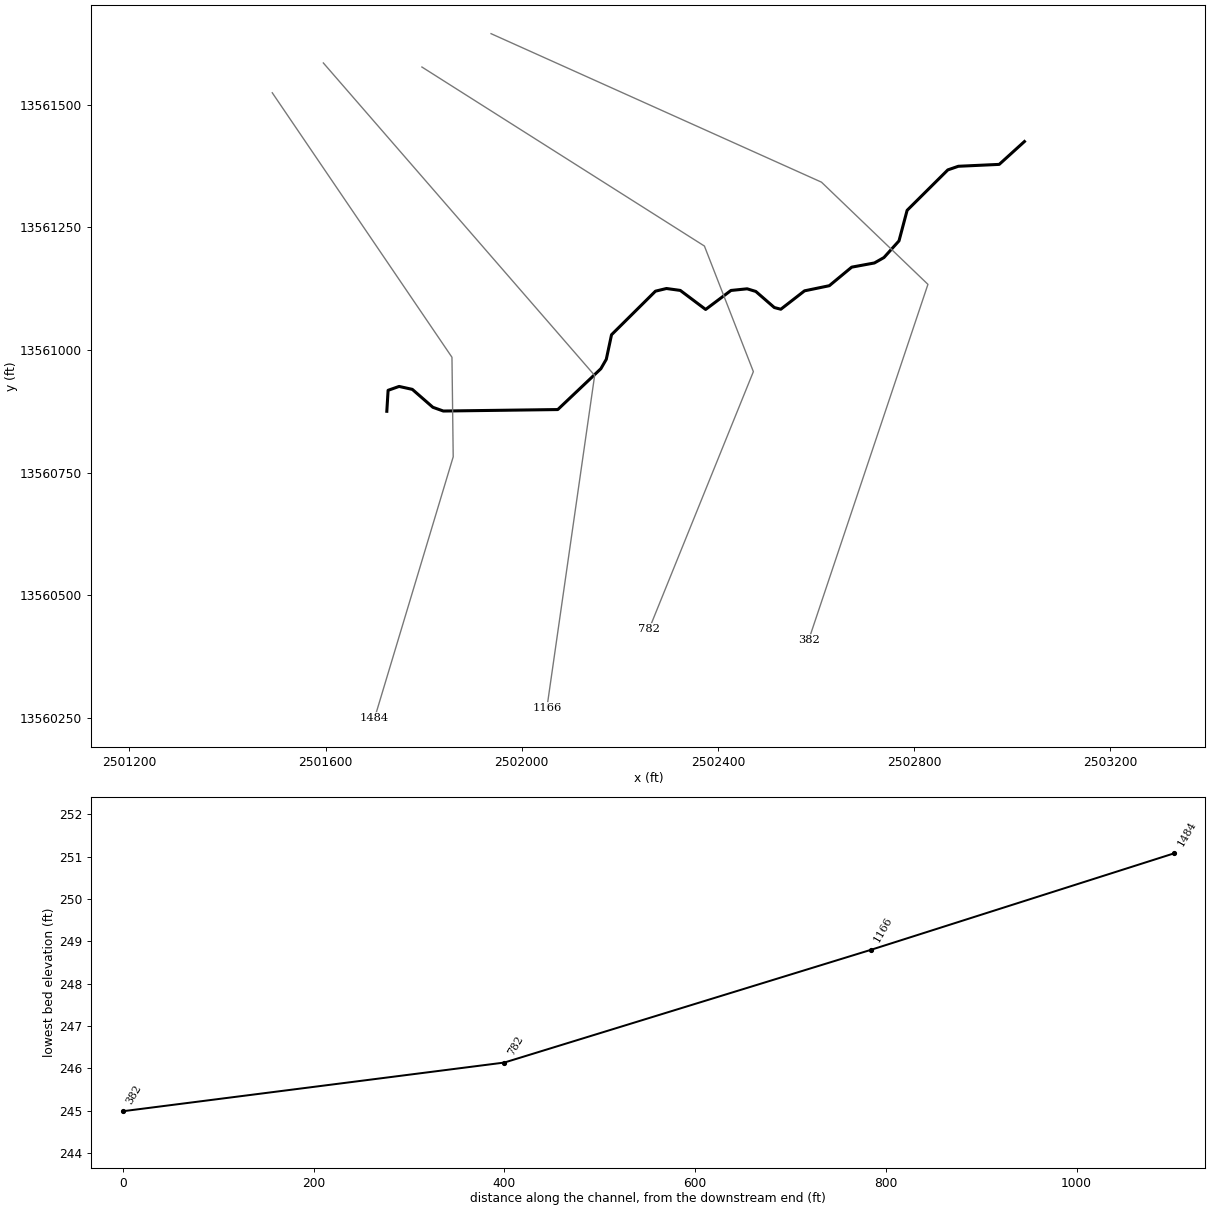
--- TRIB 1 TO THREEMILE CREEK.prj (project) ---

Proj Title=TRIB 1 TO THREEMILE CREEK Base Level Engineering
Current Plan=p01
Default Exp/Contr=0.3,0.1
English Units
Geom File=g01
Flow File=f01
Plan File=p01
Y Axis Title=Elevation
X Axis Title(PF)=Main Channel Distance
X Axis Title(XS)=Station
BEGIN DESCRIPTION:
TRIB 1 TO THREEMILE CREEK
END DESCRIPTION:
DSS Export Rating Curves= 0
DSS Export Rating Curve Sorted= 0
DSS Export Volume Flow Curves= 0
DXF OffsetX= 0
DXF OffsetY= 0
DXF ScaleX= 1
DXF ScaleY= 10

--- TRIB 1 TO THREEMILE CREEK.p01 (plan) ---

Plan Title=Multiple Run
Short Identifier=Multiple
Geom File=g01
Flow File=f01
Subcritical Flow
K Sum by GR= 0
Std Step Tol= 0.01
Critical Tol= 0.01
Num of Std Step Trials= 20
Max Error Tol= 0.3
Flow Tol Ratio= 0.001
Split Flow NTrial= 30
Split Flow Tol= 0.02
Split Flow Ratio= 0.02
Log Output Level= 0
Friction Slope Method= 1
Unsteady Friction Slope Method= 2
Unsteady Bridges Friction Slope Method= 1
Parabolic Critical Depth
Global Vel Dist=  1 , 1 , 1
Global Log Level= 0
CheckData=True
Encroach Param= -1, 0, 0, 0
BEGIN DESCRIPTION:
Multiple Run
END DESCRIPTION:

--- TRIB 1 TO THREEMILE CREEK.f01 (steady flow) ---

Flow Title=Multiple
Number of Profiles=7
Profile Names=10-year,25-year,50-year,1pct_min,100-year,1pct_plu,500-year
River Rch & RM= TRIB 1 TO THREEM,Reach-1,1484
     288     441     571     360     718    1432    1120
Boundary for River Rch & Prof#=TRIB 1 TO THREEM,Reach-1,1
Up Type=0
Dn Type=3
Dn Slope=0.005
Boundary for River Rch & Prof#=TRIB 1 TO THREEM,Reach-1,2
Up Type=0
Dn Type=3
Dn Slope=0.005
Boundary for River Rch & Prof#=TRIB 1 TO THREEM,Reach-1,3
Up Type=0
Dn Type=3
Dn Slope=0.005
Boundary for River Rch & Prof#=TRIB 1 TO THREEM,Reach-1,4
Up Type=0
Dn Type=3
Dn Slope=0.005
Boundary for River Rch & Prof#=TRIB 1 TO THREEM,Reach-1,5
Up Type=0
Dn Type=3
Dn Slope=0.005
Boundary for River Rch & Prof#=TRIB 1 TO THREEM,Reach-1,6
Up Type=0
Dn Type=3
Dn Slope=0.005
Boundary for River Rch & Prof#=TRIB 1 TO THREEM,Reach-1,7
Up Type=0
Dn Type=3
Dn Slope=0.005

--- TRIB 1 TO THREEMILE CREEK.g01 (geometry) ---

Geom Title=Existing Conditions

River Reach=TRIB 1 TO THREEM,Reach-1
Reach XY= 30
      2501725.00     13560875.00      2501727.61     13560917.76
      2501750.00     13560925.67      2501777.00     13560919.69
      2501818.88     13560883.14      2501840.20     13560875.52
      2502073.55     13560878.53      2502161.38     13560961.76
      2502172.47     13560981.04      2502183.15     13561031.07
      2502272.70     13561119.89      2502295.16     13561125.33
      2502323.35     13561121.43      2502375.00     13561082.62
      2502426.65     13561121.36      2502459.64     13561124.71
      2502477.28     13561119.33      2502515.08     13561086.51
      2502528.31     13561083.07      2502576.64     13561120.58
      2502627.19     13561131.05      2502672.84     13561168.88
      2502719.15     13561177.42      2502738.57     13561188.47
      2502769.25     13561222.46      2502785.78     13561284.69
      2502868.80     13561367.16      2502890.19     13561374.53
      2502973.59     13561378.39      2503025.00     13561425.00

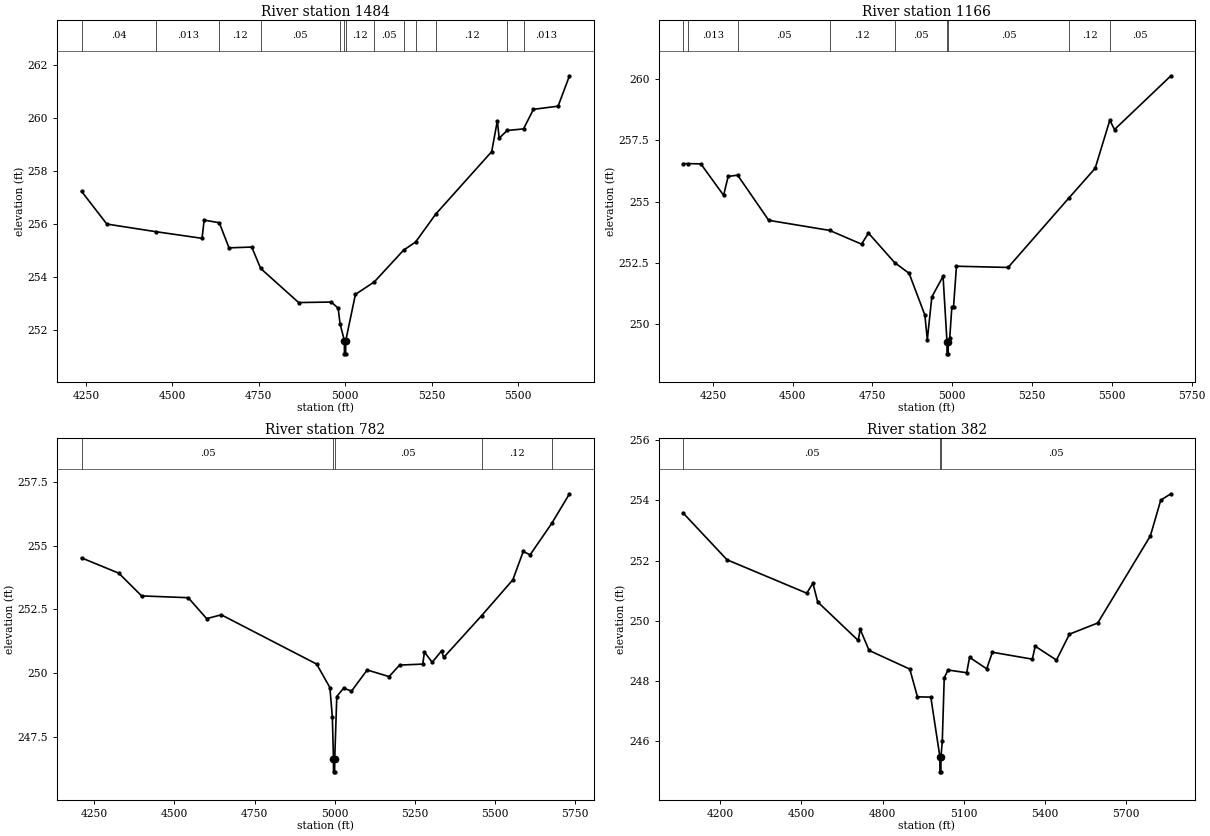
Type RM Length L Ch R = 1,1484,318,318,318
BEGIN DESCRIPTION:
TRIB 1 TO THREEMILE CREEK 3.0
END DESCRIPTION:
XS GIS Cut Line= 4
      2501491.44     13561524.39      2501857.82     13560985.13
      2501860.35     13560782.22      2501700.12     13560249.57
#Sta/Elev= 30
  4237.5  257.23  4310.7  255.99  4453.3  255.70  4586.1  255.45  4592.1  256.14
  4635.9  256.04  4664.0  255.09  4729.8  255.12  4755.6  254.31  4865.4  253.02
  4959.6  253.04  4979.6  252.81  4985.1  252.22  4997.6  251.58  4997.8  251.08
  5001.3  251.08  5001.6  251.58  5029.6  253.33  5084.0  253.80  5168.6  255.00
  5203.5  255.31  5262.0  256.37  5423.6  258.73  5440.0  259.90  5445.2  259.24
  5468.3  259.53  5515.6  259.59  5544.3  260.33  5615.6  260.45  5648.6  261.60
#Mann=13,-1,0
  4237.5    0.04       0  4453.3   0.013       0  4635.9    0.12       0
  4755.6    0.05       0  4985.1    0.12       0  4997.6    0.05       0
  5001.6    0.12       0  5084.0    0.05       0  5168.6    0.12       0
  5203.5    0.05       0  5262.0    0.12       0  5468.3    0.05       0
  5515.6   0.013       0
Bank Sta=4997.6,5001.6
Exp/Cntr=0.3,0.1

Type RM Length L Ch R = 1,1166,384,384,384
BEGIN DESCRIPTION:
TRIB 1 TO THREEMILE CREEK 2.0
END DESCRIPTION:
XS GIS Cut Line= 3
      2501595.59     13561585.18      2502148.73     13560948.11
      2502051.32     13560270.07
#Sta/Elev= 30
  4156.3  256.55  4172.6  256.55  4212.5  256.54  4283.7  255.26  4298.0  256.03
  4327.7  256.08  4425.2  254.24  4615.6  253.83  4715.8  253.27  4737.6  253.72
  4819.4  252.52  4864.9  252.08  4914.2  250.38  4921.9  249.38  4936.1  251.12
  4971.2  251.96  4983.5  249.30  4983.7  248.80  4987.2  248.80  4987.5  249.30
  4992.1  249.43  4998.8  250.72  5004.1  250.72  5013.2  252.37  5174.9  252.32
  5366.8  255.17  5447.7  256.36  5493.6  258.32  5508.3  257.94  5685.0  260.13
#Mann=9,-1,0
  4156.3    0.04       0  4172.6   0.013       0  4327.7    0.05       0
  4615.6    0.12       0  4819.4    0.05       0  4983.5    0.05       0
  4987.5    0.05       0  5366.8    0.12       0  5493.6    0.05       0
Bank Sta=4983.5,4987.5
Exp/Cntr=0.3,0.1

Type RM Length L Ch R = 1,782,400,400,400
BEGIN DESCRIPTION:
TRIB 1 TO THREEMILE CREEK 1.0
END DESCRIPTION:
XS GIS Cut Line= 4
      2501796.55     13561576.90      2502372.50     13561211.91
      2502472.33     13560955.84      2502259.85     13560431.13
#Sta/Elev= 30
  4209.9  254.52  4326.4  253.92  4397.5  253.03  4542.9  252.96  4600.5  252.14
  4646.1  252.29  4943.7  250.36  4985.0  249.44  4992.7  248.28  4996.1  246.64
  4996.3  246.14  4999.8  246.14  5000.1  246.64  5006.5  249.09  5028.0  249.42
  5052.4  249.30  5101.4  250.13  5169.7  249.87  5202.4  250.32  5274.7  250.36
  5280.1  250.83  5304.2  250.43  5333.7  250.88  5340.1  250.62  5458.7  252.26
  5555.9  253.66  5588.3  254.77  5609.8  254.64  5677.2  255.87  5732.7  257.03
#Mann=5,-1,0
  4209.9    0.05       0  4996.1    0.05       0  5000.1    0.05       0
  5458.7    0.12       0  5677.2    0.05       0
Bank Sta=4996.1,5000.1
Exp/Cntr=0.3,0.1

Type RM Length L Ch R = 1,382,0,0,0
BEGIN DESCRIPTION:
TRIB 1 TO THREEMILE CREEK 0.0
END DESCRIPTION:
XS GIS Cut Line= 4
      2501937.50     13561644.91      2502611.22     13561342.12
      2502828.23     13561133.79      2502585.35     13560409.48
#Sta/Elev= 30
  4062.1  253.59  4224.9  252.03  4519.8  250.92  4542.4  251.25  4560.1  250.63
  4710.0  249.35  4717.2  249.72  4750.1  249.02  4900.5  248.40  4928.8  247.48
  4978.2  247.47  5011.7  245.49  5011.9  244.99  5015.4  244.99  5015.7  245.49
  5020.6  246.00  5027.8  248.11  5041.7  248.37  5110.8  248.28  5121.4  248.79
  5184.7  248.41  5205.7  248.96  5353.4  248.73  5364.0  249.16  5442.5  248.70
  5490.5  249.56  5595.0  249.93  5789.5  252.82  5828.0  254.01  5865.5  254.22
#Mann=3,-1,0
  4062.1    0.05       0  5011.7    0.05       0  5015.7    0.05       0
Bank Sta=5011.7,5015.7
Exp/Cntr=0.3,0.1

Chan Stop Cuts=-1