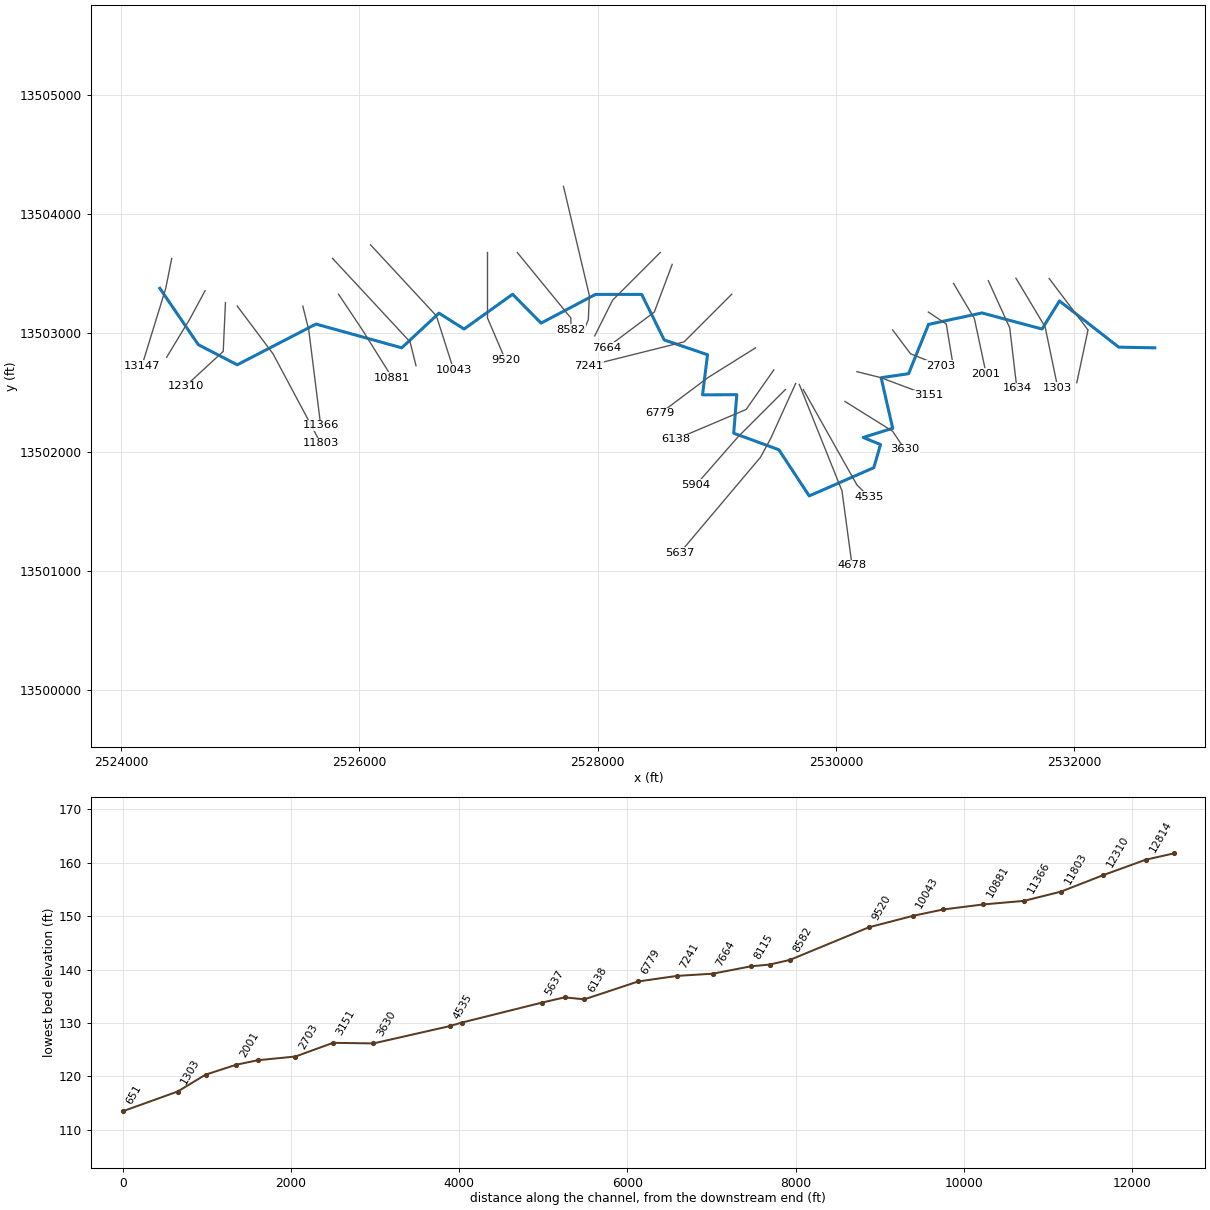
--- TRIB 1 TO TWELVEMILE CREEK.prj (project) ---

Proj Title=TRIB 1 TO TWELVEMILE CREEK Base Level Engineering
Current Plan=p01
Default Exp/Contr=0.3,0.1
English Units
Geom File=g01
Flow File=f01
Plan File=p01
Y Axis Title=Elevation
X Axis Title(PF)=Main Channel Distance
X Axis Title(XS)=Station
BEGIN DESCRIPTION:
TRIB 1 TO TWELVEMILE CREEK
END DESCRIPTION:
DSS Export Rating Curves= 0
DSS Export Rating Curve Sorted= 0
DSS Export Volume Flow Curves= 0
DXF OffsetX= 0
DXF OffsetY= 0
DXF ScaleX= 1
DXF ScaleY= 10

--- TRIB 1 TO TWELVEMILE CREEK.p01 (plan) ---

Plan Title=Multiple Run
Short Identifier=Multiple
Geom File=g01
Flow File=f01
Subcritical Flow
K Sum by GR= 0
Std Step Tol= 0.01
Critical Tol= 0.01
Num of Std Step Trials= 20
Max Error Tol= 0.3
Flow Tol Ratio= 0.001
Split Flow NTrial= 30
Split Flow Tol= 0.02
Split Flow Ratio= 0.02
Log Output Level= 0
Friction Slope Method= 1
Unsteady Friction Slope Method= 2
Unsteady Bridges Friction Slope Method= 1
Parabolic Critical Depth
Global Vel Dist=  1 , 1 , 1
Global Log Level= 0
CheckData=True
Encroach Param= -1, 0, 0, 0
BEGIN DESCRIPTION:
Multiple Run
END DESCRIPTION:

--- TRIB 1 TO TWELVEMILE CREEK.f01 (steady flow) ---

Flow Title=Multiple
Number of Profiles=7
Profile Names=10-year,25-year,50-year,1pct_min,100-year,1pct_plu,500-year
River Rch & RM= TRIB 1 TO TWELVE,Reach-1,13147
     647    1030    1372     883    1763    3517    2879
River Rch & RM= TRIB 1 TO TWELVE,Reach-1,12814
     858    1389    1868    1215    2423    4835    4035
River Rch & RM= TRIB 1 TO TWELVE,Reach-1,8582
    1073    1754    2375    1553    3099    6184    5223
Boundary for River Rch & Prof#=TRIB 1 TO TWELVE,Reach-1,1
Up Type=0
Dn Type=3
Dn Slope=0.005
Boundary for River Rch & Prof#=TRIB 1 TO TWELVE,Reach-1,2
Up Type=0
Dn Type=3
Dn Slope=0.005
Boundary for River Rch & Prof#=TRIB 1 TO TWELVE,Reach-1,3
Up Type=0
Dn Type=3
Dn Slope=0.005
Boundary for River Rch & Prof#=TRIB 1 TO TWELVE,Reach-1,4
Up Type=0
Dn Type=3
Dn Slope=0.005
Boundary for River Rch & Prof#=TRIB 1 TO TWELVE,Reach-1,5
Up Type=0
Dn Type=3
Dn Slope=0.005
Boundary for River Rch & Prof#=TRIB 1 TO TWELVE,Reach-1,6
Up Type=0
Dn Type=3
Dn Slope=0.005
Boundary for River Rch & Prof#=TRIB 1 TO TWELVE,Reach-1,7
Up Type=0
Dn Type=3
Dn Slope=0.005

--- TRIB 1 TO TWELVEMILE CREEK.g01 (geometry) ---

Geom Title=Existing Conditions
Program Version=4.10

River Reach=TRIB 1 TO TWELVE,Reach-1
Reach XY= 30
        2524325.       13503375.      2524648.05     13502901.14
      2524974.96     13502732.52      2525635.62     13503074.39
       2526354.9      13502874.9      2526667.94     13503166.03
      2526878.33     13503032.61      2527285.68     13503324.47
       2527524.9     13503082.32      2527981.11      13503323.2
      2528369.29     13503323.11      2528557.86     13502941.28
      2528921.63     13502816.85      2528879.59     13502480.17
       2529167.2     13502481.84      2529141.28     13502158.26
      2529519.97     13502019.92        2529775.      13501632.1
      2530316.86     13501868.94      2530373.63     13502063.46
      2530227.91     13502122.94      2530475.61     13502199.64
      2530378.52     13502624.01      2530608.76     13502657.76
      2530776.25     13503071.55       2531225.1     13503167.67
      2531728.69      13503032.7      2531875.23     13503268.03
      2532372.57     13502880.52        2532675.       13502875.

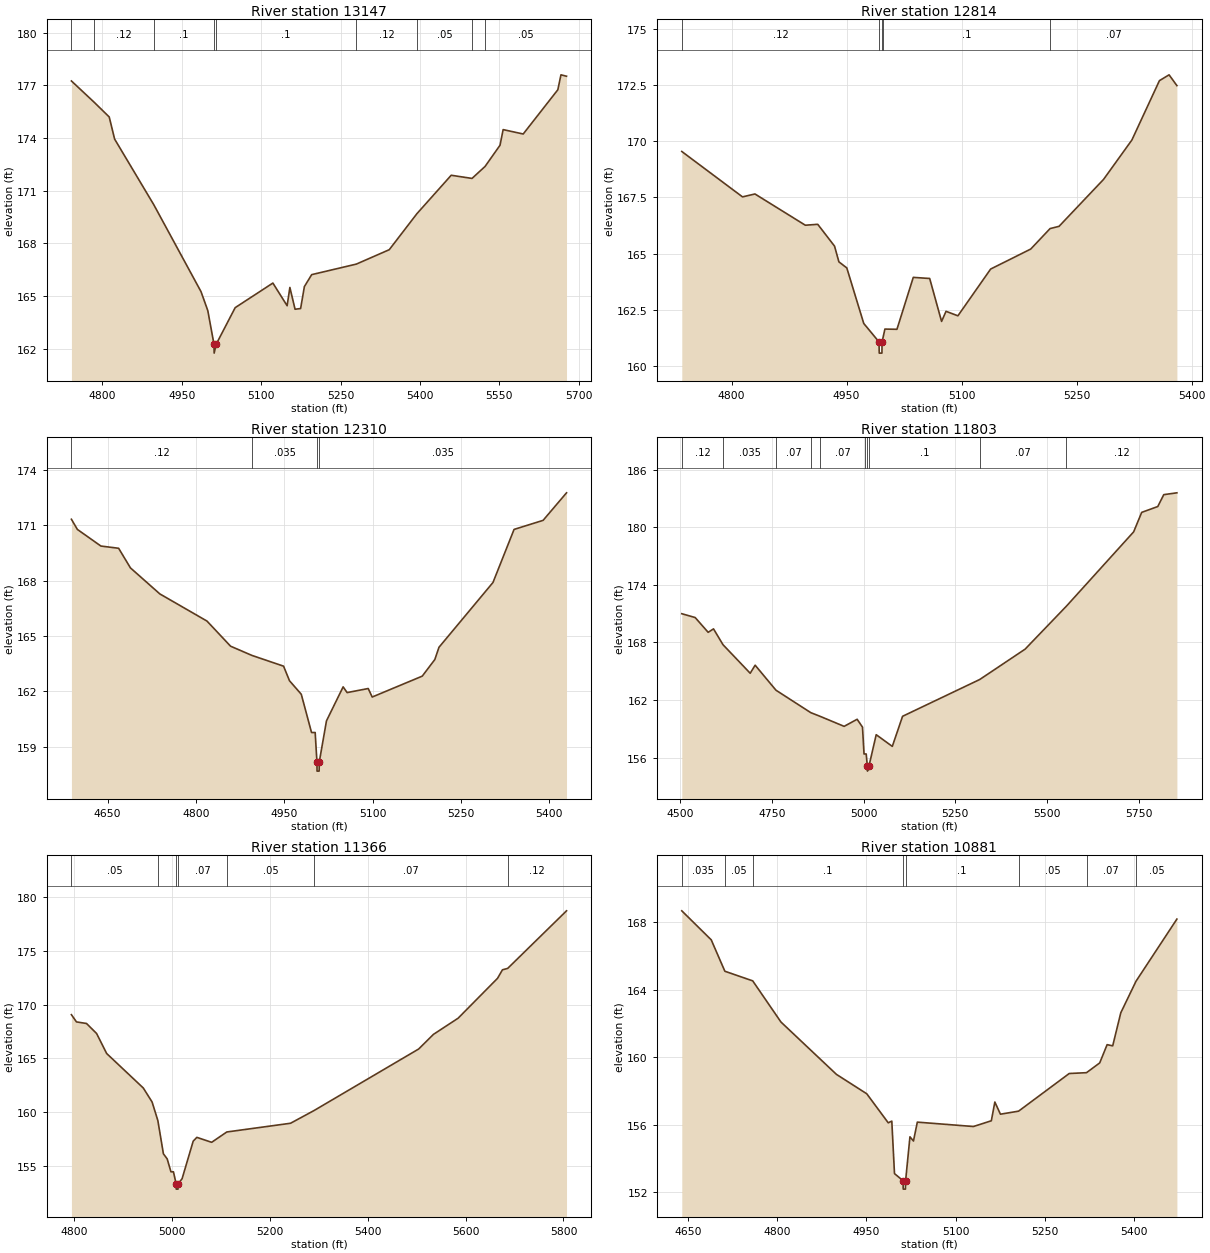
Type RM Length L Ch R = 1 ,13147   ,333,333,333
BEGIN DESCRIPTION:
TRIB 1 TO TWELVEMILE CREEK 25.0
END DESCRIPTION:
XS GIS Cut Line= 3
      2524425.01     13503625.04        2524375.       13503375.
      2524174.99     13502724.96
#Sta/Elev= 30
  4741.7  177.24  4784.6  176.03  4813.1  175.19  4823.3  173.93  4897.5  170.18
  4986.5  165.24  4999.3  164.16    5011  162.24  5011.3  161.74    5015  162.24
    5051  164.33  5122.2  165.73  5149.1  164.44  5154.3  165.48  5164.1  164.24
  5174.6  164.28  5181.7  165.53  5195.5  166.21  5279.8  166.81    5342  167.63
  5394.2  169.68    5459  171.87  5498.3  171.69  5522.9  172.37  5551.2  173.58
  5557.1  174.47    5595  174.22  5660.4  176.74  5666.3  177.59  5676.8  177.51
#Mann= 9 ,-1 , 0
  4741.7     .05       0  4784.6     .12       0  4897.5      .1       0
    5011     .05       0    5015      .1       0  5279.8     .12       0
  5394.2     .05       0  5498.3     .07       0  5522.9     .05       0
Bank Sta=5011,5015
XS Rating Curve= 0 ,0
Exp/Cntr=0.3,0.1

Type RM Length L Ch R = 1 ,12814   ,504,504,504
BEGIN DESCRIPTION:
Mapping XS c65def94
END DESCRIPTION:
XS GIS Cut Line= 3
      2524705.08     13503354.43      2524577.78     13503118.45
      2524382.15     13502795.51
#Sta/Elev= 30
  4735.1  169.54  4814.3  167.52  4830.5  167.65  4896.2  166.26  4912.4   166.3
  4934.3  165.33    4940  164.63  4950.3  164.36  4972.4  161.89  4992.3  161.07
  4992.6  160.57  4996.1  160.57  4996.3  161.07  4996.9  161.16    5000  161.64
  5015.7  161.63    5037  163.94  5058.4  163.89  5073.9  161.98  5079.7  162.43
  5095.2  162.23  5137.9  164.31  5190.2   165.2  5215.4  166.11  5227.1  166.21
  5285.2   168.3  5322.1  170.05    5358  172.69  5370.6  172.95  5380.8  172.47
#Mann= 5 ,-1 , 0
  4735.1     .12       0  4992.3     .05       0  4996.3     .12       0
  4996.9      .1       0  5215.4     .07       0
Bank Sta=4992.3,4996.3
XS Rating Curve= 0 ,0
Exp/Cntr=0.3,0.1

Type RM Length L Ch R = 1 ,12310   ,507,507,507
BEGIN DESCRIPTION:
Mapping XS 358de44a
END DESCRIPTION:
XS GIS Cut Line= 3
       2524875.9     13503255.07      2524857.27     13502845.17
       2524540.5     13502553.24
#Sta/Elev= 30
  4588.4  171.32  4598.5  170.77  4638.5  169.87  4668.6  169.75  4688.6  168.69
  4738.6  167.28  4818.7  165.81  4858.8  164.45  4895.2  163.95  4948.8  163.37
  4958.9  162.58  4978.9  161.85  4996.3  159.78  5002.5  159.78  5005.5  158.19
  5005.7  157.69  5009.2  157.69  5009.5  158.19  5021.7  160.41    5050  162.25
  5056.8  161.94  5092.6  162.16  5099.4   161.7  5184.4  162.83  5205.8  163.73
  5212.8  164.39  5304.6   167.9  5340.4  170.77  5389.7  171.26  5429.5  172.75
#Mann= 4 ,-1 , 0
  4588.4     .12       0  4895.2    .035       0  5005.5    .035       0
  5009.5    .035       0
Bank Sta=5005.5,5009.5
XS Rating Curve= 0 ,0
Exp/Cntr=0.3,0.1

Type RM Length L Ch R = 1 ,11803   ,437,437,437
BEGIN DESCRIPTION:
TRIB 1 TO TWELVEMILE CREEK 22.0
END DESCRIPTION:
XS GIS Cut Line= 3
        2524975.       13503225.        2525275.       13502825.
        2525675.       13502075.
#Sta/Elev= 30
  4504.1     171  4540.6   170.6    4576  169.06  4590.6  169.42  4616.4  167.77
  4690.6  164.79  4704.1  165.63  4760.9  163.02  4855.8  160.68  4881.6  160.29
  4946.8  159.25  4982.2  159.99  4996.8  159.17    5001  156.37  5002.3  156.37
  5006.9  156.37  5010.1  155.08  5010.4  154.58  5014.3  155.08  5034.2  158.38
  5078.1  157.16  5106.1   160.3  5316.6  164.14  5440.1   167.3  5552.9  171.79
  5736.2  179.54  5758.1  181.57    5802  182.18  5818.3  183.42  5854.1  183.61
#Mann= 10 ,-1 , 0
  4504.1     .12       0  4616.4    .035       0  4760.9     .07       0
  4855.8     .05       0  4881.6     .07       0  5002.3      .1       0
  5010.1     .05       0  5014.3      .1       0  5316.6     .07       0
  5552.9     .12       0
Bank Sta=5010.1,5014.3
XS Rating Curve= 0 ,0
Exp/Cntr=0.3,0.1

Type RM Length L Ch R = 1 ,11366   ,485,485,485
BEGIN DESCRIPTION:
TRIB 1 TO TWELVEMILE CREEK 21.0
END DESCRIPTION:
XS GIS Cut Line= 3
      2525525.01     13503224.97        2525575.       13503025.
      2525674.99     13502225.05
#Sta/Elev= 30
  4793.9  169.07  4804.2   168.4  4824.8  168.25  4845.4  167.32    4866  165.46
  4940.8  162.26  4958.8  160.96  4970.6  159.24    4982  156.14  4989.7  155.67
  4997.4  154.47  5002.5  154.47    5008  153.36  5008.2  152.86  5011.9  152.86
  5012.2  153.36  5020.2  153.83  5042.9  157.32  5050.4  157.67  5080.6  157.21
  5111.6  158.17  5241.9  158.98  5289.9  160.16  5503.9  165.88  5534.1  167.24
  5584.5  168.74  5665.2  172.45  5675.2  173.24  5685.9  173.37  5806.2  178.72
#Mann= 7 ,-1 , 0
  4793.9     .05       0  4970.6     .07       0    5008     .05       0
  5012.2     .07       0  5111.6     .05       0  5289.9     .07       0
  5685.9     .12       0
Bank Sta=5008,5012.2
XS Rating Curve= 0 ,0
Exp/Cntr=0.3,0.1

Type RM Length L Ch R = 1 ,10881   ,475,475,475
BEGIN DESCRIPTION:
TRIB 1 TO TWELVEMILE CREEK 20.0
END DESCRIPTION:
XS GIS Cut Line= 3
      2525825.02     13503324.96        2526025.       13503025.
      2526274.99     13502625.01
#Sta/Elev= 30
  4639.6  168.68  4689.1  166.96    4712   165.1  4758.8  164.53  4806.3  162.09
  4899.5  158.99  4950.5  157.84  4986.6  156.12  4992.6  156.22  4997.1  153.11
  5011.5  152.69  5011.8  152.19  5015.5  152.19  5015.8  152.69  5023.1  155.29
    5029  155.04  5035.5  156.16  5129.8   155.9  5159.9  156.24  5165.8  157.35
  5175.2  156.63  5205.7  156.81  5290.8  159.04  5319.9  159.09  5342.1  159.67
  5354.5  160.75  5363.9  160.68  5377.5  162.64  5403.1  164.51  5471.8  168.19
#Mann= 8 ,-1 , 0
  4639.6    .035       0    4712     .05       0  4758.8      .1       0
  5011.5     .05       0  5015.8      .1       0  5205.7     .05       0
  5319.9     .07       0  5403.1     .05       0
Bank Sta=5011.5,5015.8
XS Rating Curve= 0 ,0
Exp/Cntr=0.3,0.1

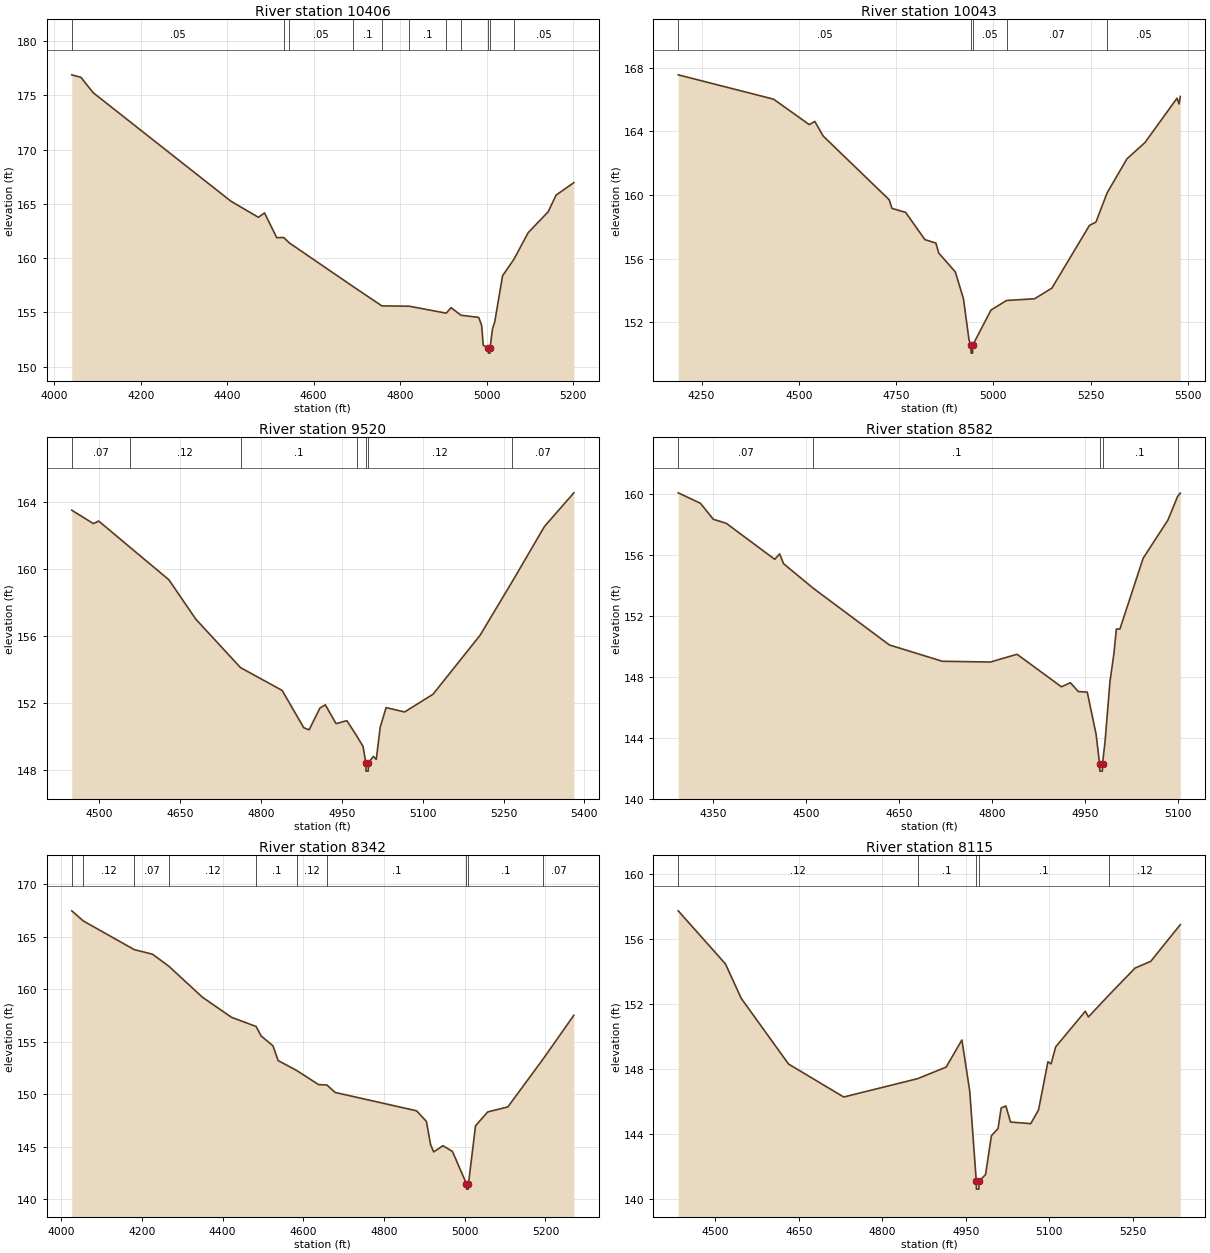
Type RM Length L Ch R = 1 ,10406   ,363,363,363
BEGIN DESCRIPTION:
TRIB 1 TO TWELVEMILE CREEK 19.0
END DESCRIPTION:
XS GIS Cut Line= 3
      2525775.01     13503624.99        2526425.       13502925.
        2526475.     13502724.98
#Sta/Elev= 30
  4040.5  176.88  4061.7  176.65  4090.1  175.23  4408.7  165.24  4472.2  163.76
  4486.4  164.16  4514.7  161.88  4530.6   161.9  4543.8   161.4  4690.3  157.41
  4757.8   155.6  4821.4  155.57  4906.7  154.93  4917.8  155.44  4940.8  154.74
  4981.8  154.54  4988.6  153.81  4992.3  151.97  5003.9  151.75  5004.1  151.25
  5007.9  151.25  5008.2  151.75  5013.8   153.5  5018.9  154.12    5037  158.37
  5063.4   159.9  5096.2  162.34  5142.6  164.27  5160.7   165.8  5201.9  166.95
#Mann= 11 ,-1 , 0
  4040.5     .05       0  4530.6      .1       0  4543.8     .05       0
  4690.3      .1       0  4757.8     .05       0  4821.4      .1       0
  4906.7     .05       0  4940.8     .07       0  5003.9     .05       0
  5008.2     .07       0  5063.4     .05       0
Bank Sta=5003.9,5008.2
XS Rating Curve= 0 ,0
Exp/Cntr=0.3,0.1

Type RM Length L Ch R = 1 ,10043   ,523,523,523
BEGIN DESCRIPTION:
Mapping XS a4a523a8
END DESCRIPTION:
XS GIS Cut Line= 3
      2526093.26     13503739.54      2526646.03     13503143.29
      2526791.46     13502688.43
#Sta/Elev= 30
  4189.9  167.55  4434.9  166.02  4526.8  164.42    4541  164.62  4562.5   163.7
    4732   159.7  4739.4  159.15  4774.5   158.9  4823.9  157.19  4852.2  156.97
  4859.6  156.34  4902.1  155.16  4923.1  153.47  4937.3  150.89  4942.4  150.55
  4942.7  150.05  4946.5  150.05  4946.8  150.55  4993.9  152.76  5033.8  153.36
  5106.1  153.47  5150.4  154.14  5246.9  158.08  5263.6  158.29  5292.4  160.13
  5343.4  162.27  5389.6  163.29    5472  166.08  5477.3  165.72  5480.5  166.19
#Mann= 5 ,-1 , 0
  4189.9     .05       0  4942.4     .05       0  4946.8     .05       0
  5033.8     .07       0  5292.4     .05       0
Bank Sta=4942.4,4946.8
XS Rating Curve= 0 ,0
Exp/Cntr=0.3,0.1

Type RM Length L Ch R = 1 ,9520    ,938,938,938
BEGIN DESCRIPTION:
TRIB 1 TO TWELVEMILE CREEK 17.0
END DESCRIPTION:
XS GIS Cut Line= 3
        2527075.     13503675.04        2527075.       13503125.
      2527224.99     13502775.03
#Sta/Elev= 30
  4449.6  163.52  4489.6  162.72  4499.6  162.87  4557.3  161.31  4629.6  159.36
  4679.6     157  4762.5   154.1  4839.6  152.74  4879.6  150.51  4889.6  150.38
  4909.6  151.68  4919.6  151.88  4939.6  150.75  4959.6  150.93  4977.6  150.03
  4989.6  149.39  4994.7  148.41  4995.1  147.91  4999.2  147.91  4999.5  148.41
  5008.7  148.79  5014.1  148.61  5021.4  150.53  5032.3  151.71  5066.7  151.45
  5119.3  152.51  5206.4  156.03    5266  159.24    5326  162.55  5380.4  164.56
#Mann= 7 ,-1 , 0
  4449.6     .07       0  4557.3     .12       0  4762.5      .1       0
  4977.6     .12       0  4994.7     .05       0  4999.5     .12       0
    5266     .07       0
Bank Sta=4994.7,4999.5
XS Rating Curve= 0 ,0
Exp/Cntr=0.3,0.1

Type RM Length L Ch R = 1 ,8582    ,240,240,240
BEGIN DESCRIPTION:
TRIB 1 TO TWELVEMILE CREEK 16.0
END DESCRIPTION:
XS GIS Cut Line= 3
        2527325.     13503674.99        2527775.       13503125.
        2527775.     13503025.03
#Sta/Elev= 30
  4293.3   160.1  4329.2  159.41    4350  158.36  4370.8   158.1  4449.1  155.73
    4457  156.09  4463.4  155.44  4511.6  153.82  4634.3   150.1  4719.7  149.03
  4797.2  148.98  4840.3  149.49    4912  147.35  4926.4  147.62  4939.3  147.04
  4953.7     147    4968  144.22  4973.5  142.31  4973.9  141.81    4978  141.81
  4978.3  142.31  4982.4  143.75  4990.3  147.68  4996.7  149.54  5000.7  151.15
  5006.4  151.15  5043.9   155.8  5083.9  158.31  5099.5  159.86  5103.9  160.08
#Mann= 5 ,-1 , 0
  4293.3     .07       0  4511.6      .1       0  4973.5     .05       0
  4978.3      .1       0  5099.5     .07       0
Bank Sta=4973.5,4978.3
XS Rating Curve= 0 ,0
Exp/Cntr=0.3,0.1

Type RM Length L Ch R = 1 ,8342    ,227,227,227
BEGIN DESCRIPTION:
Mapping XS d5b9bc3a
END DESCRIPTION:
XS GIS Cut Line= 4
       2527712.7     13504230.03       2527929.7     13503314.26
      2527921.02     13503110.27      2527882.15     13503019.56
#Sta/Elev= 30
  4026.5  167.48  4055.3  166.51  4181.4  163.78  4226.7  163.34  4266.6  162.21
  4350.3  159.24  4422.2  157.33  4483.3  156.45  4495.6  155.55    4525  154.61
  4537.8   153.2    4584  152.25    4638  150.91  4658.6  150.87  4679.1  150.16
  4880.8  148.41  4905.2   147.4  4915.5  145.19  4923.1  144.49  4946.3  145.08
  4969.8  144.53  5004.5  141.44  5004.9  140.94    5009  140.94  5009.4  141.44
  5026.9  146.98    5057   148.3    5107  148.78  5195.1  153.39  5270.5  157.52
#Mann= 10 ,-1 , 0
  4026.5     .07       0  4055.3     .12       0  4181.4     .07       0
  4266.6     .12       0  4483.3      .1       0    4584     .12       0
  4658.6      .1       0  5004.5     .05       0  5009.4      .1       0
  5195.1     .07       0
Bank Sta=5004.5,5009.4
XS Rating Curve= 0 ,0
Exp/Cntr=0.3,0.1

Type RM Length L Ch R = 1 ,8115    ,451,451,451
BEGIN DESCRIPTION:
TRIB 1 TO TWELVEMILE CREEK 15.0
END DESCRIPTION:
XS GIS Cut Line= 3
      2528524.98     13503674.98        2528125.       13503275.
      2527974.99     13502974.98
#Sta/Elev= 30
  4433.8  157.73  4518.6  154.46  4546.9  152.34  4631.8   148.3  4730.8  146.27
  4863.5   147.4  4914.6  148.11  4942.9  149.78    4957  146.63  4968.7   141.1
    4969   140.6  4973.3   140.6  4973.7   141.1  4985.3  141.49  4995.9  143.89
  5007.8  144.33  5013.4   145.6  5021.8  145.72  5030.2  144.73  5066.5  144.63
  5080.5  145.48  5097.3  148.44  5102.9  148.31  5111.3  149.36  5164.4  151.55
    5170   151.2  5206.1  152.52  5253.8  154.21  5281.8  154.62  5334.9  156.88
#Mann= 5 ,-1 , 0
  4433.8     .12       0  4863.5      .1       0  4968.7     .05       0
  4973.7      .1       0  5206.1     .12       0
Bank Sta=4968.7,4973.7
XS Rating Curve= 0 ,0
Exp/Cntr=0.3,0.1

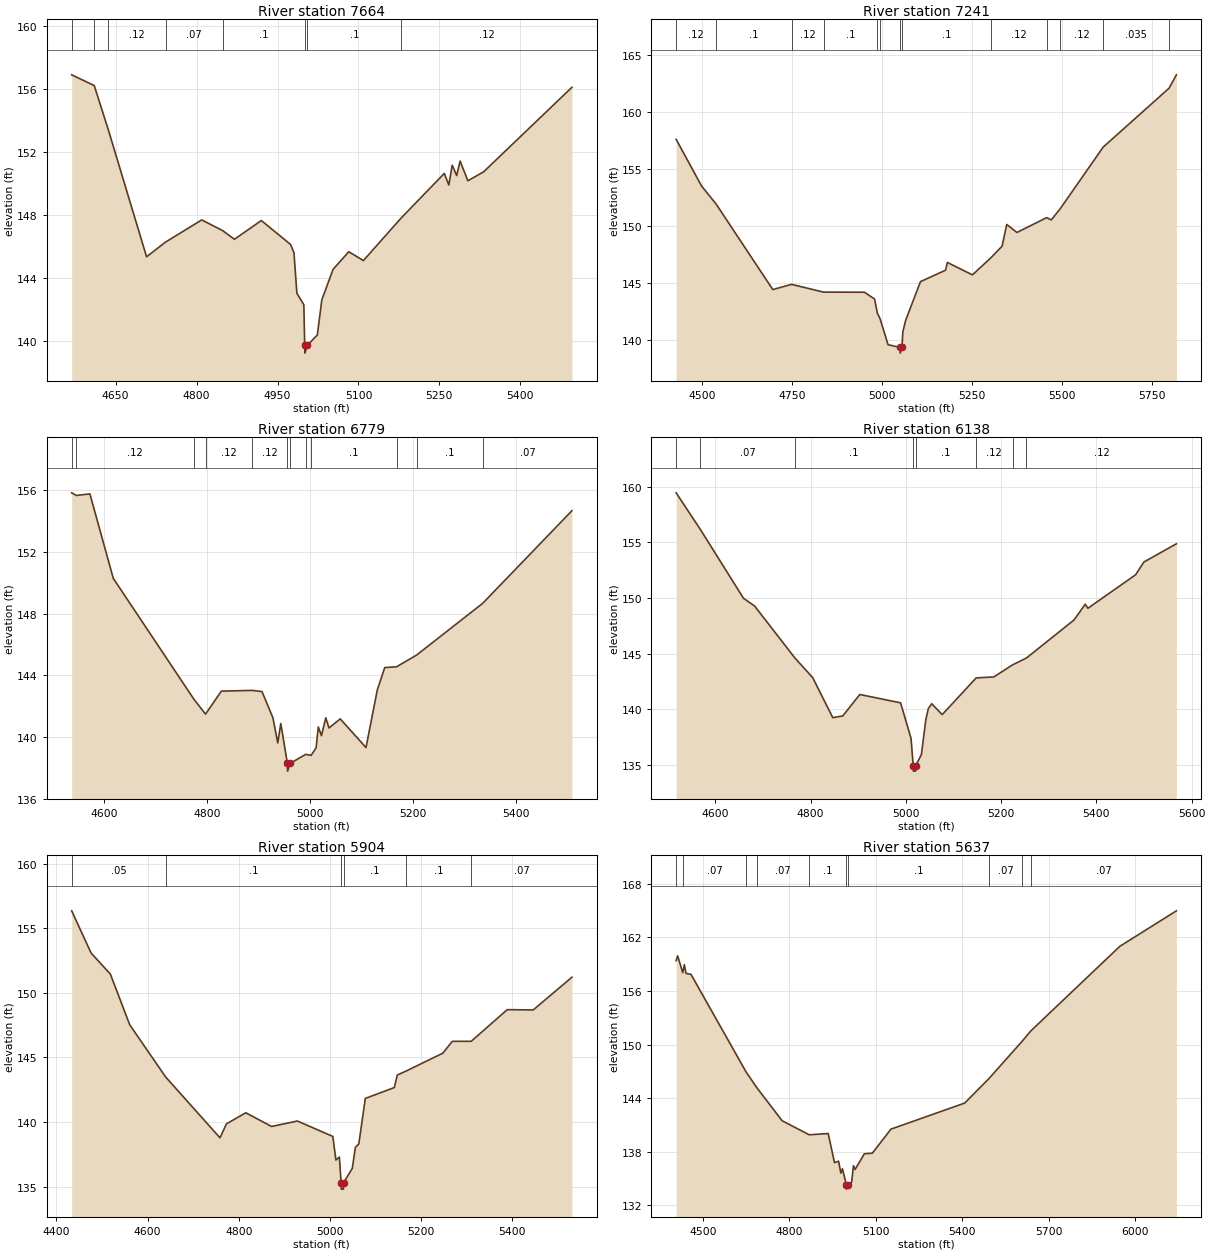
Type RM Length L Ch R = 1 ,7664    ,423,423,423
BEGIN DESCRIPTION:
TRIB 1 TO TWELVEMILE CREEK 14.0
END DESCRIPTION:
XS GIS Cut Line= 3
      2528624.98     13503574.96        2528475.       13503175.
      2528074.96     13502874.97
#Sta/Elev= 30
  4568.5  156.88  4610.3   156.2    4636  153.44  4707.3  145.34  4742.4  146.27
  4809.6  147.68  4848.8  146.99  4870.2  146.45    4920  147.64  4974.3  146.12
  4980.5   145.6  4985.9  143.03  4998.8   142.3  5000.4  139.73  5000.8  139.23
  5005.4  139.73  5023.8  140.38  5032.1   142.6  5052.9  144.54  5082.1  145.66
  5109.2   145.1  5179.2   147.8  5259.2  150.63  5267.5  149.89  5273.8  151.15
  5282.1  150.49  5288.4  151.41  5302.9  150.16  5332.1  150.73  5495.7  156.09
#Mann= 8 ,-1 , 0
  4568.5     .12       0  4610.3     .07       0    4636     .12       0
  4742.4     .07       0  4848.8      .1       0  5000.4     .05       0
  5005.4      .1       0  5179.2     .12       0
Bank Sta=5000.4,5005.4
XS Rating Curve= 0 ,0
Exp/Cntr=0.3,0.1

Type RM Length L Ch R = 1 ,7241    ,462,462,462
BEGIN DESCRIPTION:
TRIB 1 TO TWELVEMILE CREEK 13.0
END DESCRIPTION:
XS GIS Cut Line= 3
      2529125.02     13503325.02        2528725.       13502925.
      2527925.04     13502725.01
#Sta/Elev= 30
  4426.9  157.57  4497.6  153.47  4537.8   151.9  4695.6  144.39  4747.5  144.85
  4836.6  144.17  4950.2  144.16  4978.5  143.56  4986.1  142.33  4993.5  141.85
  5015.8  139.56  5049.4  139.32  5049.7  138.82  5054.4  139.32    5057  140.69
  5064.8   141.7    5106  145.09  5175.6  146.09  5180.7  146.77  5250.3  145.68
  5302.4   147.2  5332.8   148.2  5345.7   150.1    5374   149.4  5456.8   150.7
  5469.4   150.5    5495  151.51  5613.6  156.88  5796.9  162.05  5817.2  163.22
#Mann= 13 ,-1 , 0
  4426.9     .12       0  4537.8      .1       0  4747.5     .12       0
  4836.6      .1       0  4986.1     .12       0  4993.5      .1       0
  5049.4     .05       0  5054.4      .1       0  5302.4     .12       0
  5456.8     .12       0    5495     .12       0  5613.6    .035       0
  5796.9     .07       0
Bank Sta=5049.4,5054.4
XS Rating Curve= 0 ,0
Exp/Cntr=0.3,0.1

Type RM Length L Ch R = 1 ,6779    ,641,641,641
BEGIN DESCRIPTION:
TRIB 1 TO TWELVEMILE CREEK 12.0
END DESCRIPTION:
XS GIS Cut Line= 3
      2529324.99     13502874.99        2528925.       13502625.
      2528524.99     13502324.99
#Sta/Elev= 30
  4537.6  155.84  4546.8  155.67    4573  155.77  4618.4  150.29  4774.7  142.46
  4797.6  141.48  4828.3  142.97  4888.6  143.02  4907.3  142.94  4928.5  141.24
  4937.9  139.61  4943.8  140.87  4956.6  138.28    4957  137.78  4961.8  138.28
  4992.4  138.87  5002.6   138.8  5012.4  139.29  5016.6  140.65  5022.8  140.08
  5031.2  141.24  5037.4  140.58  5059.3  141.17  5109.3  139.31  5131.2  143.04
  5145.7   144.5  5168.6  144.55  5207.5  145.31    5336  148.67  5509.3  154.68
#Mann= 12 ,-1 , 0
  4537.6     .07       0  4546.8     .12       0  4774.7     .12       0
  4797.6     .12       0  4888.6     .12       0  4956.6     .05       0
  4961.8     .12       0  4992.4     .12       0  5002.6      .1       0
  5168.6     .07       0  5207.5      .1       0    5336     .07       0
Bank Sta=4956.6,4961.8
XS Rating Curve= 0 ,0
Exp/Cntr=0.3,0.1

Type RM Length L Ch R = 1 ,6138    ,234,234,234
BEGIN DESCRIPTION:
Mapping XS 52d35ad4
END DESCRIPTION:
XS GIS Cut Line= 3
      2529478.24     13502689.92      2529245.32     13502357.61
      2528652.17     13502106.06
#Sta/Elev= 30
  4517.9  159.45  4568.7  156.16  4659.3  149.97  4682.7  149.27  4766.7  144.63
  4804.8  142.82  4846.7  139.24  4867.6  139.39  4903.4  141.32  4989.1  140.57
    5011  137.37  5015.5  134.93  5015.9  134.43  5020.5  134.43  5020.9  134.93
  5032.7  135.91  5041.9  139.02  5047.3  140.06  5054.4  140.49  5076.4  139.51
  5147.7  142.81  5184.8   142.9    5224  143.98  5253.3   144.6  5353.1  148.02
  5376.7  149.44  5382.2  149.07  5482.3  152.08  5499.8  153.23    5568  154.87
#Mann= 8 ,-1 , 0
  4517.9     .05       0  4568.7     .07       0  4766.7      .1       0
  5015.5     .05       0  5020.9      .1       0  5147.7     .12       0
    5224     .07       0  5253.3     .12       0
Bank Sta=5015.5,5020.9
XS Rating Curve= 0 ,0
Exp/Cntr=0.3,0.1

Type RM Length L Ch R = 1 ,5904    ,267,267,267
BEGIN DESCRIPTION:
TRIB 1 TO TWELVEMILE CREEK 10.0
END DESCRIPTION:
XS GIS Cut Line= 3
      2529575.02     13502525.02        2529175.       13502125.
      2528825.01     13501725.01
#Sta/Elev= 30
  4433.7  156.34  4476.2  153.08  4518.6  151.44    4561  147.52  4639.8  143.48
    4759  138.77  4773.1  139.85  4815.6  140.71  4872.1  139.65  4928.7  140.07
  5006.5  138.88  5013.2  137.05  5020.8  137.28  5024.7   135.3  5025.1   134.8
  5029.7   134.8  5030.1   135.3  5049.2  136.41  5055.9  138.03  5063.5   138.3
  5077.7  141.82  5141.3  142.66  5147.9  143.63  5166.6  143.93  5247.6  145.32
  5268.5  146.24  5309.9  146.24    5389  148.69    5446  148.67  5530.9   151.2
#Mann= 6 ,-1 , 0
  4433.7     .05       0  4639.8      .1       0  5024.7     .05       0
  5030.1      .1       0  5166.6      .1       0  5309.9     .07       0
Bank Sta=5024.7,5030.1
XS Rating Curve= 0 ,0
Exp/Cntr=0.3,0.1

Type RM Length L Ch R = 1 ,5637    ,959,959,959
BEGIN DESCRIPTION:
Mapping XS 2a6b2cb4
END DESCRIPTION:
XS GIS Cut Line= 4
      2529661.46     13502576.39      2529453.25     13502117.67
      2529366.45     13501957.08      2528689.71     13501154.53
#Sta/Elev= 30
  4407.5  159.39  4412.8  159.93  4430.5  158.05  4435.9  158.94    4442  157.96
  4458.9  157.87  4649.9  146.96  4687.3  145.19  4775.4  141.48  4869.3  139.91
  4935.2  140.05  4957.1  136.79  4971.1  136.96    4979  135.63  4984.7  136.11
  4998.1  134.33  4998.6  133.83  5003.6  134.33  5016.6  134.61  5022.8  136.45
  5028.5  136.03  5060.8  137.79  5088.4  137.85  5152.9  140.54    5409  143.46
  5491.9  146.16  5608.7  150.39  5638.6  151.54  5947.4     161  6143.6  164.97
#Mann= 10 ,-1 , 0
  4407.5     .05       0  4430.5     .07       0  4649.9     .12       0
  4687.3     .07       0  4869.3      .1       0  4998.1     .05       0
  5003.6      .1       0  5491.9     .07       0  5608.7      .1       0
  5638.6     .07       0
Bank Sta=4998.1,5003.6
XS Rating Curve= 0 ,0
Exp/Cntr=0.3,0.1

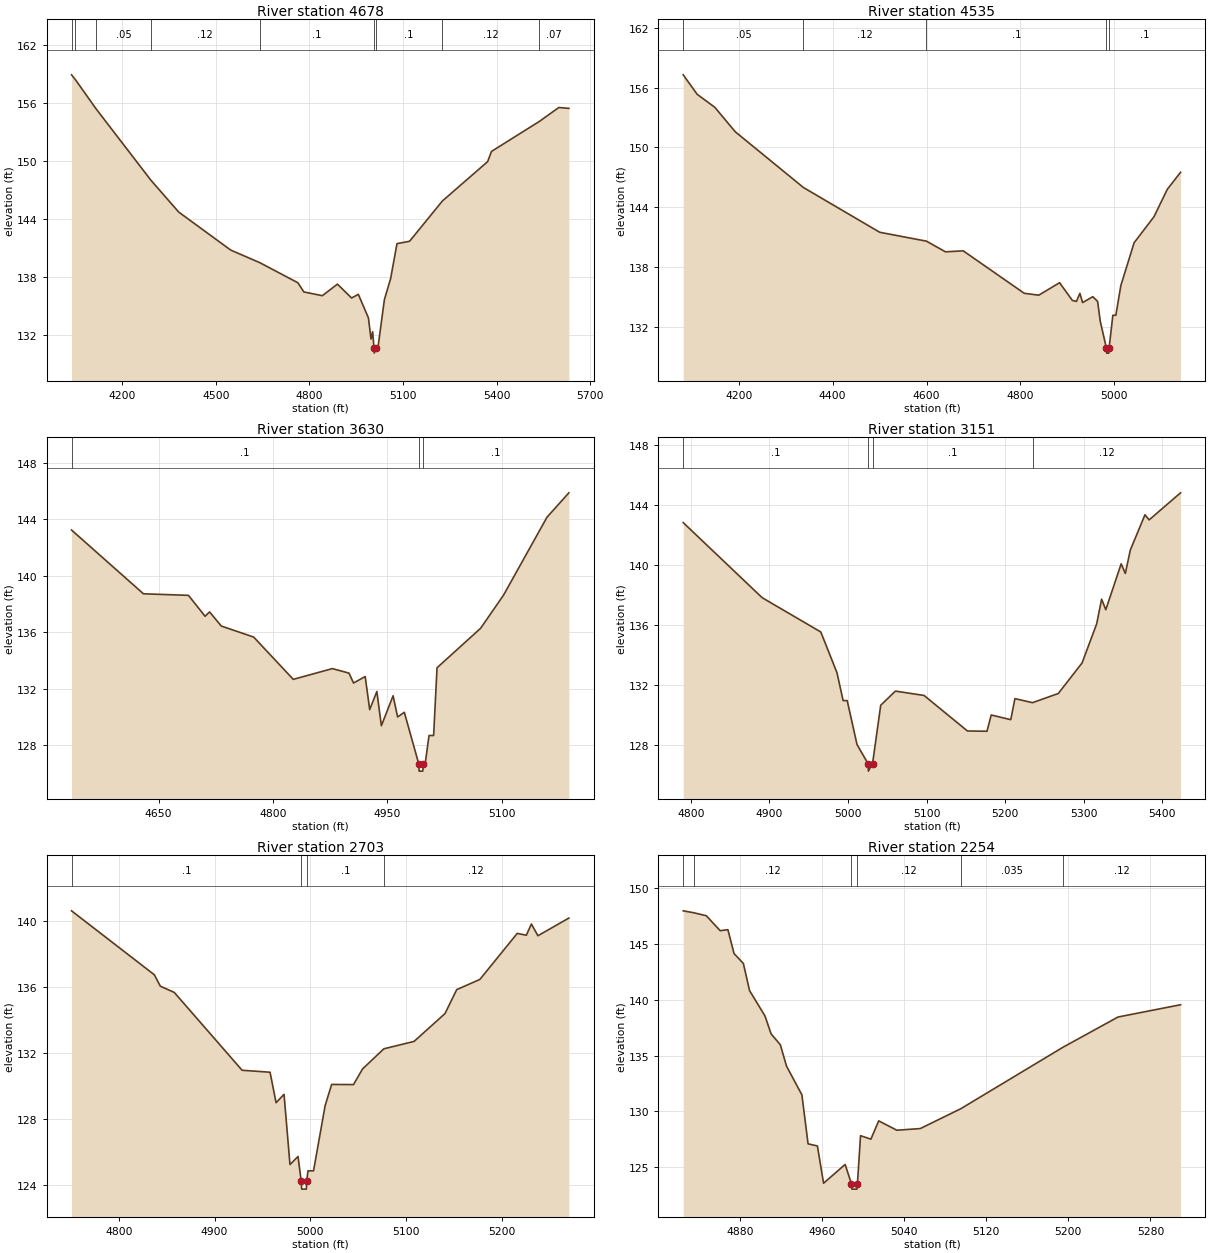
Type RM Length L Ch R = 1 ,4678    ,143,143,143
BEGIN DESCRIPTION:
Mapping XS 567052cf
END DESCRIPTION:
XS GIS Cut Line= 3
      2529691.85     13502567.76        2530050.     13501674.59
      2530134.47     13501049.37
#Sta/Elev= 30
  4037.7  158.95  4049.7  158.47  4115.9  155.44  4292.1  148.01    4381  144.71
  4547.8  140.76  4640.7  139.46    4763  137.37  4781.9  136.42  4841.1  136.03
  4889.5  137.23  4934.9  135.79  4956.5  136.17  4988.8  133.73  4997.1  131.53
  5002.3  132.29  5006.8  130.57  5007.3  130.07  5012.5  130.57  5019.8  130.75
  5039.9  135.61  5060.1  137.83  5080.3  141.43  5120.7  141.68  5225.8  145.86
  5370.7  149.94    5383     151  5536.2  154.11  5598.8  155.56  5630.9  155.47
#Mann= 9 ,-1 , 0
  4037.7     .05       0  4049.7     .07       0  4115.9     .05       0
  4292.1     .12       0  4640.7      .1       0  5006.8     .05       0
  5012.5      .1       0  5225.8     .12       0  5536.2     .07       0
Bank Sta=5006.8,5012.5
XS Rating Curve= 0 ,0
Exp/Cntr=0.3,0.1

Type RM Length L Ch R = 1 ,4535    ,905,905,905
BEGIN DESCRIPTION:
TRIB 1 TO TWELVEMILE CREEK 7.0
END DESCRIPTION:
XS GIS Cut Line= 3
      2529724.98     13502525.04        2530175.       13501725.
      2530274.97     13501625.03
#Sta/Elev= 30
  4081.8  157.27  4111.5  155.32  4149.1  154.02  4192.4  151.58  4337.8  145.99
  4500.3  141.51  4599.8  140.62  4640.5  139.55  4678.2  139.65  4808.2   135.4
  4839.1  135.21  4883.4  136.46  4910.8  134.68  4919.4  134.59  4926.7  135.39
  4932.5  134.47  4954.2  135.06  4964.4  134.59  4970.1   132.6  4983.2  129.91
  4983.6  129.41  4988.4  129.41  4988.9  129.91  4996.9   133.2  5003.3   133.2
  5013.9  136.17  5042.2  140.46  5084.6  143.07  5112.9  145.81  5141.1  147.51
#Mann= 5 ,-1 , 0
  4081.8     .05       0  4337.8     .12       0  4599.8      .1       0
  4983.2     .05       0  4988.9      .1       0
Bank Sta=4983.2,4988.9
XS Rating Curve= 0 ,0
Exp/Cntr=0.3,0.1

Type RM Length L Ch R = 1 ,3630    ,479,479,479
BEGIN DESCRIPTION:
TRIB 1 TO TWELVEMILE CREEK 6.0
END DESCRIPTION:
XS GIS Cut Line= 3
      2530075.02     13502424.99        2530475.       13502175.
      2530575.03     13502024.96
#Sta/Elev= 30
  4535.8  143.23  4630.1  138.72  4689.1  138.61  4710.9  137.13  4716.8  137.44
  4732.1  136.44  4774.6  135.66  4826.5  132.67  4877.8  133.43  4899.6  133.11
  4905.5  132.41  4920.8  132.87  4926.7  130.53  4936.1  131.81    4942  129.39
  4957.4  131.51  4963.3  130.01  4972.1  130.34  4991.1  126.68  4991.5  126.18
  4996.3  126.18  4996.8  126.68  4999.8  126.85  5004.5   128.7  5010.5   128.7
    5015  133.49  5072.1  136.28  5102.1  138.62  5159.2  144.14  5187.8  145.86
#Mann= 3 ,-1 , 0
  4535.8      .1       0  4991.1     .05       0  4996.8      .1       0
Bank Sta=4991.1,4996.8
XS Rating Curve= 0 ,0
Exp/Cntr=0.3,0.1

Type RM Length L Ch R = 1 ,3151    ,448,448,448
BEGIN DESCRIPTION:
TRIB 1 TO TWELVEMILE CREEK 5.0
END DESCRIPTION:
XS GIS Cut Line= 3
      2530175.01       13502675.        2530375.       13502625.
      2530774.96     13502475.01
#Sta/Elev= 30
  4790.2  142.81  4890.7  137.82  4965.4  135.54    4986  132.83  4993.8  130.98
    4999  130.98  5011.5  128.06  5025.5  126.79    5026  126.29  5031.3  126.79
  5041.7  130.67  5060.4  131.61  5096.9  131.32  5152.1  128.96    5177  128.94
  5182.4  130.02  5207.3  129.71  5212.6  131.11    5235  130.84  5267.8  131.45
  5298.1  133.48  5316.7  136.08    5323  137.72  5328.3  137.02  5347.9  140.07
  5353.2  139.43  5359.5  140.98  5378.2  143.33  5383.5  142.99  5423.5  144.79
#Mann= 4 ,-1 , 0
  4790.2      .1       0  5025.5     .05       0  5031.3      .1       0
    5235     .12       0
Bank Sta=5025.5,5031.3
XS Rating Curve= 0 ,0
Exp/Cntr=0.3,0.1

Type RM Length L Ch R = 1 ,2703    ,449,449,449
BEGIN DESCRIPTION:
TRIB 1 TO TWELVEMILE CREEK 4.0
END DESCRIPTION:
XS GIS Cut Line= 3
      2530474.99     13503025.02        2530625.       13502825.
      2530875.02     13502724.99
#Sta/Elev= 30
  4750.7  140.61  4837.2  136.73  4843.4  136.04    4858  135.66  4928.8  130.94
    4958  130.82  4964.3  128.97  4972.6  129.48  4978.8  125.22  4987.2  125.71
  4990.5  124.23    4991  123.73  4995.9  123.73  4996.3  124.23  4997.6  124.84
  5003.4  124.84  5015.5  128.79  5022.3  130.08  5045.1  130.07  5054.6  131.02
  5076.8  132.24  5108.4  132.69  5140.7  134.38  5152.9  135.83  5177.1  136.45
  5216.1  139.24  5225.6  139.13  5230.9  139.81  5237.7   139.1    5270  140.17
#Mann= 4 ,-1 , 0
  4750.7      .1       0  4990.5     .05       0  4996.3      .1       0
  5076.8     .12       0
Bank Sta=4990.5,4996.3
XS Rating Curve= 0 ,0
Exp/Cntr=0.3,0.1

Type RM Length L Ch R = 1 ,2254    ,253,253,253
BEGIN DESCRIPTION:
TRIB 1 TO TWELVEMILE CREEK 3.0
END DESCRIPTION:
XS GIS Cut Line= 3
      2530775.03     13503174.98        2530925.       13503075.
        2530975.     13502774.98
#Sta/Elev= 30
  4824.9  147.98    4835  147.81  4847.4  147.54  4860.9   146.2  4868.4  146.29
  4874.4  144.15  4883.5  143.26  4889.5  140.83  4904.5  138.56  4910.5  136.95
  4919.5  135.97  4925.5  134.06  4940.5  131.48  4946.5  127.09  4955.6   126.9
  4961.6  123.56  4982.6  125.24  4988.7  123.53  4989.2  123.03  4994.1  123.03
  4994.6  123.53  4997.6  127.82  5007.7  127.51  5015.3  129.15    5033  128.31
  5055.8  128.46  5095.3  130.24  5194.8  135.75  5248.4  138.46  5309.3  139.56
#Mann= 6 ,-1 , 0
  4824.9    .035       0    4835     .12       0  4988.7     .05       0
  4994.6     .12       0  5095.3    .035       0  5194.8     .12       0
Bank Sta=4988.7,4994.6
XS Rating Curve= 0 ,0
Exp/Cntr=0.3,0.1

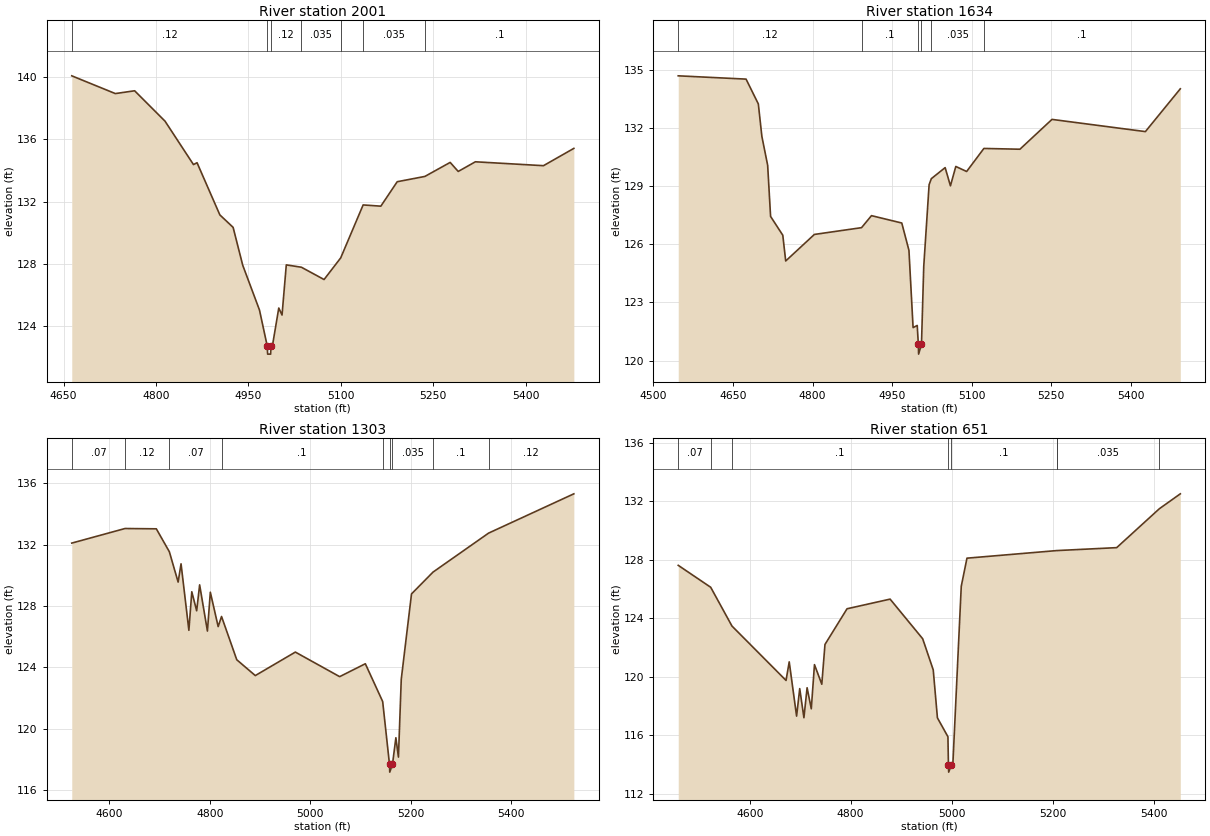
Type RM Length L Ch R = 1 ,2001    ,367,367,367
BEGIN DESCRIPTION:
Mapping XS 3daff261
END DESCRIPTION:
XS GIS Cut Line= 3
      2530986.47     13503415.12      2531160.96     13503120.83
      2531259.62     13502658.68
#Sta/Elev= 30
  4663.3  140.07    4734  138.93  4765.3  139.11  4814.6  137.16  4860.8  134.37
  4866.6  134.49  4903.6  131.14  4925.1  130.34  4940.7  127.91  4967.9  125.03
  4980.6   122.7  4981.1   122.2    4986   122.2  4986.5   122.7  4989.4  122.85
  4999.2  125.16  5004.5  124.71  5011.4  127.93  5035.9  127.78  5072.7  126.99
  5099.7  128.38  5136.1  131.78  5164.8   131.7  5191.4  133.27  5236.3  133.61
  5277.3  134.51  5290.4  133.93  5318.2  134.55  5428.7   134.3    5478  135.41
#Mann= 7 ,-1 , 0
  4663.3     .12       0  4980.6     .05       0  4986.5     .12       0
  5035.9    .035       0  5099.7      .1       0  5136.1    .035       0
  5236.3      .1       0
Bank Sta=4980.6,4986.5
XS Rating Curve= 0 ,0
Exp/Cntr=0.3,0.1

Type RM Length L Ch R = 1 ,1634    ,331,331,331
BEGIN DESCRIPTION:
Mapping XS 40a66df0
END DESCRIPTION:
XS GIS Cut Line= 3
      2531278.16     13503438.53      2531457.84     13503042.71
      2531517.73     13502534.92
#Sta/Elev= 30
    4547   134.7  4674.8  134.53  4697.9  133.25  4704.6  131.57  4715.5  130.08
    4721  127.44    4744  126.47  4749.5  125.14  4803.5  126.51  4892.4  126.86
  4911.1  127.48  4968.2   127.1  4981.7  125.69  4989.5   121.7  4997.3  121.81
  4999.4  120.83  4999.9  120.33  5005.3  120.83  5009.6  124.86  5019.7  129.08
  5023.9  129.39  5049.9  129.96  5059.9  129.02    5070  130.02  5090.4  129.76
  5122.9  130.95  5190.8  130.91  5251.2  132.45  5427.2  131.82    5493  134.03
#Mann= 6 ,-1 , 0
    4547     .12       0  4892.4      .1       0  4999.4     .05       0
  5005.3      .1       0  5023.9    .035       0  5122.9      .1       0
Bank Sta=4999.4,5005.3
XS Rating Curve= 0 ,0
Exp/Cntr=0.3,0.1

Type RM Length L Ch R = 1 ,1303    ,652,652,652
BEGIN DESCRIPTION:
Mapping XS 7a6e90e1
END DESCRIPTION:
XS GIS Cut Line= 3
      2531509.92     13503459.37      2531754.71     13503050.52
      2531861.23     13502538.71
#Sta/Elev= 30
  4525.4   132.1  4631.4  133.05  4693.7  133.03  4719.6  131.54  4737.1  129.56
  4742.9  130.75  4758.5  126.42  4764.3  128.93    4774  127.69  4779.9  129.38
  4795.4  126.37  4801.2   128.9  4816.8  126.66  4823.5  127.32  4853.8   124.5
  4890.7  123.47  4970.4     125  5058.6   123.4  5109.7  124.24  5144.2  121.78
  5157.8  117.68  5158.3  117.18  5163.7  117.68  5170.5  119.42  5175.6  118.16
  5181.2  123.23  5201.6  128.79  5244.4  130.21    5355  132.75  5524.7  135.31
#Mann= 9 ,-1 , 0
  4525.4     .07       0  4631.4     .12       0  4719.6     .07       0
  4823.5      .1       0  5144.2    .035       0  5157.8     .05       0
  5163.7    .035       0  5244.4      .1       0    5355     .12       0
Bank Sta=5157.8,5163.7
XS Rating Curve= 0 ,0
Exp/Cntr=0.3,0.1

Type RM Length L Ch R = 1 ,651     ,0,0,0
BEGIN DESCRIPTION:
TRIB 1 TO TWELVEMILE CREEK 1.0
END DESCRIPTION:
XS GIS Cut Line= 3
      2531788.57     13503456.77      2532114.83      13503024.6
      2532020.34     13502581.77
#Sta/Elev= 30
  4458.5  127.63  4522.8  126.13  4564.9  123.48    4672  119.76  4678.3  121.03
  4692.9  117.32  4699.1   119.2  4707.4  117.21  4713.7  119.26    4722  117.82
  4728.3  120.84  4742.8   119.5  4749.1  122.22  4792.8  124.66  4878.1  125.32
  4942.6  122.61  4963.5  120.48  4971.8   117.2  4992.6  115.91  4993.6  113.99
  4994.1  113.49  4999.6  113.99  5002.3  113.99    5019   126.2  5030.3  128.12
  5208.5  128.64  5208.7  128.64  5326.8  128.84  5411.3   131.5  5452.8  132.52
#Mann= 8 ,-1 , 0
  4458.5     .07       0  4522.8     .12       0  4564.9      .1       0
  4993.6     .05       0  4999.6      .1       0  5208.5     .12       0
  5208.7    .035       0  5411.3     .12       0
Bank Sta=4993.6,4999.6
XS Rating Curve= 0 ,0
Exp/Cntr=0.3,0.1

Chan Stop Cuts=-1
Use User Specified Reach Order=0
Composite Channel Slope=5