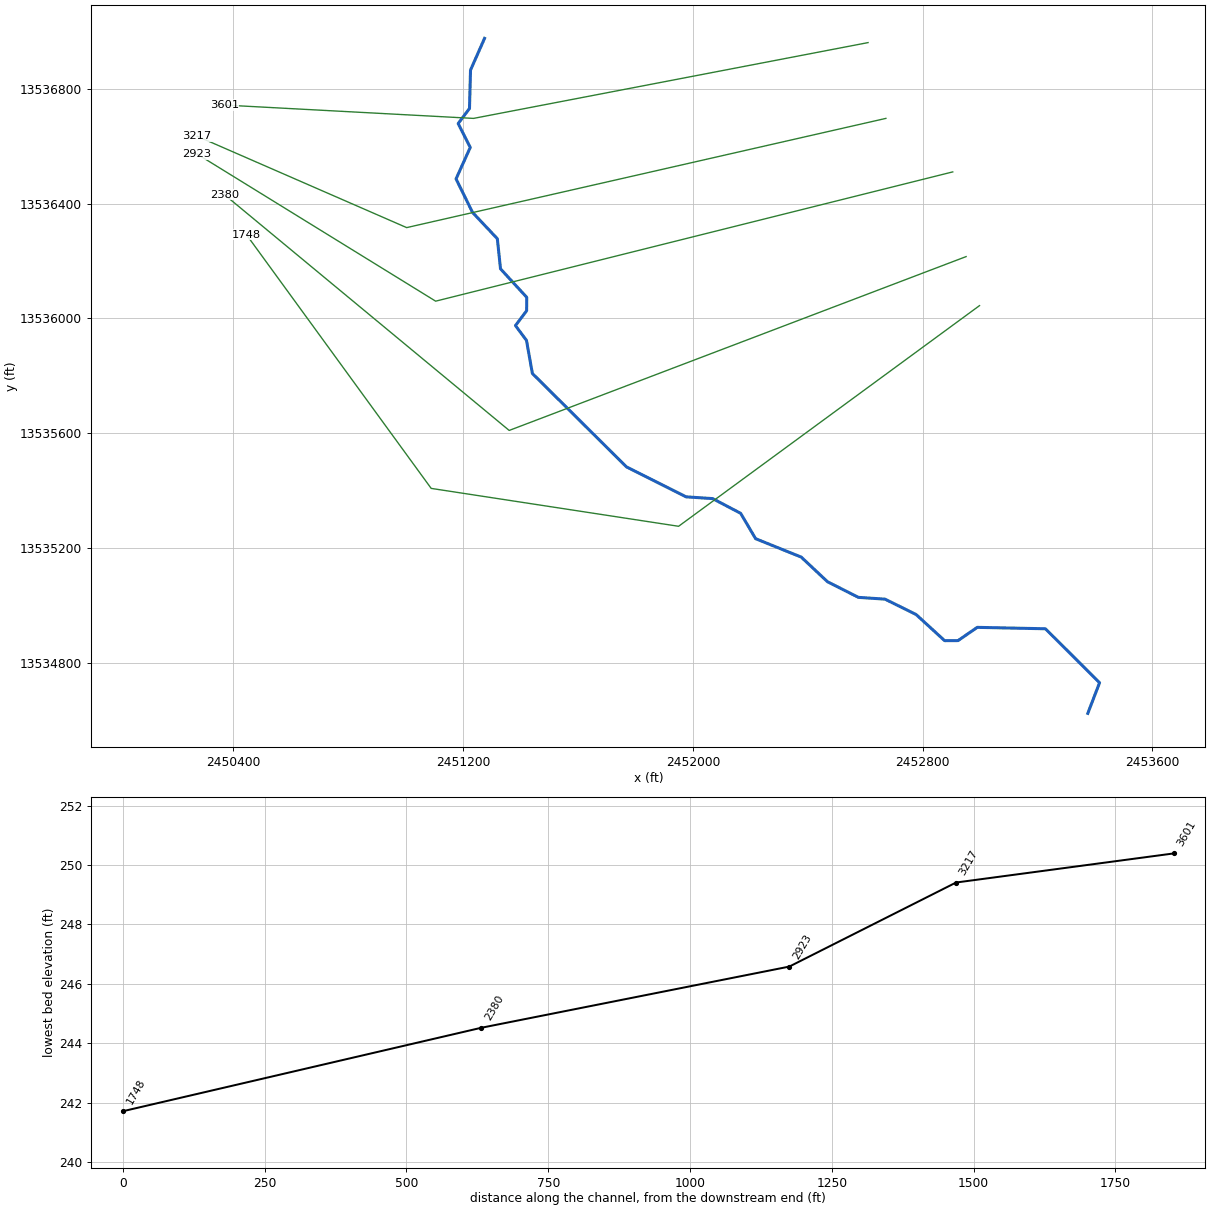
--- TRIB 1 TO YORKTOWN CREEK.prj (project) ---

Proj Title=TRIB 1 TO YORKTOWN CREEK Base Level Engineering
Current Plan=p01
Default Exp/Contr=0.3,0.1
English Units
Geom File=g01
Flow File=f01
Plan File=p01
Y Axis Title=Elevation
X Axis Title(PF)=Main Channel Distance
X Axis Title(XS)=Station
BEGIN DESCRIPTION:
TRIB 1 TO YORKTOWN CREEK
END DESCRIPTION:
DSS Export Rating Curves= 0
DSS Export Rating Curve Sorted= 0
DSS Export Volume Flow Curves= 0
DXF OffsetX= 0
DXF OffsetY= 0
DXF ScaleX= 1
DXF ScaleY= 10

--- TRIB 1 TO YORKTOWN CREEK.p01 (plan) ---

Plan Title=Multiple Run
Short Identifier=Multiple
Geom File=g01
Flow File=f01
Subcritical Flow
K Sum by GR= 0
Std Step Tol= 0.01
Critical Tol= 0.01
Num of Std Step Trials= 20
Max Error Tol= 0.3
Flow Tol Ratio= 0.001
Split Flow NTrial= 30
Split Flow Tol= 0.02
Split Flow Ratio= 0.02
Log Output Level= 0
Friction Slope Method= 1
Unsteady Friction Slope Method= 2
Unsteady Bridges Friction Slope Method= 1
Parabolic Critical Depth
Global Vel Dist=  1 , 1 , 1
Global Log Level= 0
CheckData=True
Encroach Param= -1, 0, 0, 0
BEGIN DESCRIPTION:
Multiple Run
END DESCRIPTION:

--- TRIB 1 TO YORKTOWN CREEK.f01 (steady flow) ---

Flow Title=Multiple
Number of Profiles=7
Profile Names=10-year,25-year,50-year,1pct_min,100-year,1pct_plu,500-year
River Rch & RM= TRIB 1 TO YORKTO,Reach-1,3601
     414     650     856     547    1092    2179    1756
River Rch & RM= TRIB 1 TO YORKTO,Reach-1,2380
     533     849    1131     730    1456    2906    2387
Boundary for River Rch & Prof#=TRIB 1 TO YORKTO,Reach-1,1
Up Type=0
Dn Type=3
Dn Slope=0.005
Boundary for River Rch & Prof#=TRIB 1 TO YORKTO,Reach-1,2
Up Type=0
Dn Type=3
Dn Slope=0.005
Boundary for River Rch & Prof#=TRIB 1 TO YORKTO,Reach-1,3
Up Type=0
Dn Type=3
Dn Slope=0.005
Boundary for River Rch & Prof#=TRIB 1 TO YORKTO,Reach-1,4
Up Type=0
Dn Type=3
Dn Slope=0.005
Boundary for River Rch & Prof#=TRIB 1 TO YORKTO,Reach-1,5
Up Type=0
Dn Type=3
Dn Slope=0.005
Boundary for River Rch & Prof#=TRIB 1 TO YORKTO,Reach-1,6
Up Type=0
Dn Type=3
Dn Slope=0.005
Boundary for River Rch & Prof#=TRIB 1 TO YORKTO,Reach-1,7
Up Type=0
Dn Type=3
Dn Slope=0.005

--- TRIB 1 TO YORKTOWN CREEK.g01 (geometry) ---

Geom Title=Existing Conditions

River Reach=TRIB 1 TO YORKTO,Reach-1
Reach XY= 30
      2451275.00     13536975.00      2451226.13     13536864.53
      2451222.53     13536730.86      2451183.11     13536678.29
      2451225.20     13536595.20      2451175.75     13536485.69
      2451233.16     13536368.95      2451319.46     13536277.42
      2451330.54     13536172.58      2451421.83     13536073.35
      2451421.42     13536026.65      2451382.59     13535975.01
      2451420.91     13535923.50      2451441.46     13535808.25
      2451768.94     13535483.14      2451976.59     13535378.83
      2452069.06     13535372.68      2452166.51     13535321.47
      2452218.68     13535233.07      2452377.29     13535169.15
      2452468.95     13535083.16      2452576.58     13535028.83
      2452669.03     13535022.67      2452777.29     13534969.15
      2452876.64     13534878.14      2452923.25     13534878.34
      2452990.21     13534924.46      2453227.45     13534919.54
      2453416.02     13534731.72      2453375.00     13534625.00

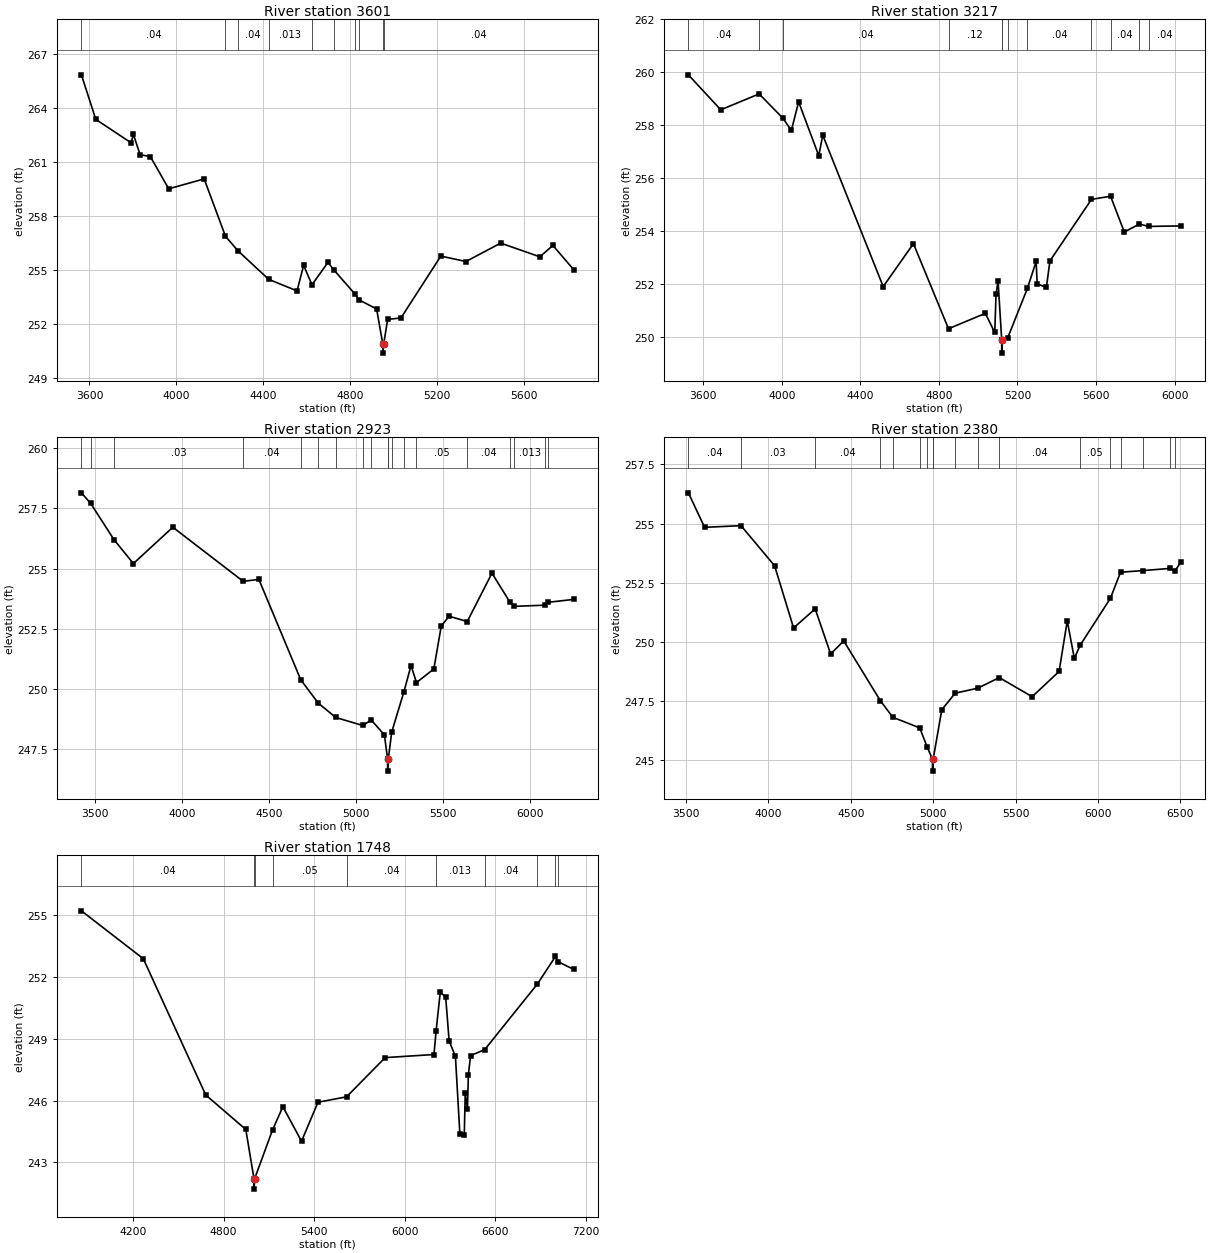
Type RM Length L Ch R = 1,3601,384,384,384
BEGIN DESCRIPTION:
LGII4605
END DESCRIPTION:
XS GIS Cut Line= 3
      2452610.02     13536960.12      2451236.60     13536696.29
      2450368.78     13536742.79
#Sta/Elev= 30
  3563.0  265.82  3629.2  263.35  3792.1  262.05  3802.3  262.52  3833.3  261.39
  3880.2  261.29  3965.2  259.50  4128.2  260.05  4226.4  256.87  4283.3  256.07
  4425.5  254.48  4555.9  253.84  4586.4  255.26  4624.7  254.18  4698.4  255.42
  4724.3  255.02  4823.9  253.65  4841.7  253.34  4922.4  252.84  4951.0  250.89
  4951.2  250.39  4955.0  250.89  4973.2  252.26  5034.5  252.34  5218.1  255.77
  5333.7  255.47  5493.9  256.49  5674.2  255.73  5734.2  256.36  5830.6  255.01
#Mann=10,-1,0
  3563.0    0.04       0  4226.4   0.013       0  4283.3    0.04       0
  4425.5   0.013       0  4624.7    0.12       0  4724.3    0.04       0
  4823.9    0.12       0  4841.7    0.04       0  4951.0    0.04       0
  4955.0    0.04       0
Bank Sta=4951,4955
Exp/Cntr=0.3,0.1

Type RM Length L Ch R = 1,3217,294,294,294
BEGIN DESCRIPTION:
LGII4604
END DESCRIPTION:
XS GIS Cut Line= 3
      2452672.14     13536696.30      2451003.81     13536316.08
      2450274.39     13536634.23
#Sta/Elev= 30
  3524.5  259.91  3689.3  258.59  3884.7  259.19  4006.3  258.27  4048.8  257.81
  4085.7  258.89  4188.2  256.86  4208.8  257.63  4516.4  251.92  4670.3  253.54
  4848.8  250.33  5036.2  250.91  5084.3  250.19  5090.8  251.64  5101.1  252.13
  5119.6  249.91  5119.8  249.41  5123.6  249.91  5149.4  249.97  5250.8  251.86
  5294.9  252.87  5300.3  252.02  5347.2  251.89  5365.1  252.89  5576.7  255.21
  5673.8  255.33  5743.7  253.98  5820.9  254.28  5867.2  254.19  6031.4  254.21
#Mann=12,-1,0
  3524.5    0.04       0  3884.7    0.03       0  4006.3    0.04       0
  4848.8    0.12       0  5119.6    0.05       0  5123.6    0.12       0
  5149.4    0.05       0  5250.8    0.04       0  5576.7   0.013       0
  5673.8    0.04       0  5820.9    0.12       0  5867.2    0.04       0
Bank Sta=5119.6,5123.6
Exp/Cntr=0.3,0.1

Type RM Length L Ch R = 1,2923,543,543,543
BEGIN DESCRIPTION:
LGII4603
END DESCRIPTION:
XS GIS Cut Line= 3
      2452904.94     13536510.07      2451104.69     13536060.01
      2450274.39     13536572.16
#Sta/Elev= 30
  3420.8  258.15  3474.1  257.71  3608.3  256.20  3719.7  255.21  3946.4  256.72
  4351.0  254.47  4441.2  254.55  4681.8  250.38  4782.4  249.41  4883.1  248.81
  5037.3  248.48  5087.5  248.70  5162.8  248.09  5181.4  247.08  5181.6  246.58
  5185.4  247.08  5204.8  248.20  5275.5  249.89  5315.9  250.97  5347.4  250.26
  5447.2  250.83  5489.7  252.61  5534.6  253.02  5639.2  252.80  5781.3  254.81
  5883.4  253.62  5908.3  253.43  6087.7  253.48  6105.8  253.60  6252.0  253.72
#Mann=19,-1,0
  3420.8    0.03       0  3474.1    0.04       0  3608.3    0.03       0
  4351.0    0.04       0  4681.8    0.05       0  4782.4    0.04       0
  4883.1    0.05       0  5037.3    0.12       0  5087.5    0.05       0
  5181.4    0.05       0  5185.4    0.05       0  5204.8    0.12       0
  5275.5    0.04       0  5347.4    0.05       0  5639.2    0.04       0
  5883.4    0.12       0  5908.3   0.013       0  6087.7    0.12       0
  6105.8    0.04       0
Bank Sta=5181.4,5185.4
Exp/Cntr=0.3,0.1

Type RM Length L Ch R = 1,2380,632,632,632
BEGIN DESCRIPTION:
LGII4602
END DESCRIPTION:
XS GIS Cut Line= 3
      2452951.44     13536215.19      2451360.75     13535609.96
      2450370.24     13536430.23
#Sta/Elev= 30
  3514.5  256.30  3612.9  254.84  3834.0  254.91  4037.8  253.21  4152.9  250.58
  4283.9  251.39  4377.7  249.48  4457.3  250.03  4679.5  247.50  4754.8  246.80
  4918.4  246.35  4963.0  245.55  4995.9  245.02  4996.2  244.52  4999.9  245.02
  5052.2  247.12  5133.7  247.82  5270.2  248.03  5401.0  248.48  5600.4  247.67
  5764.0  248.74  5813.5  250.88  5856.5  249.29  5892.0  249.85  6074.9  251.83
  6136.8  252.94  6275.6  253.01  6435.6  253.10  6467.2  253.00  6502.5  253.36
#Mann=18,-1,0
  3514.5    0.04       0  3834.0    0.03       0  4283.9    0.04       0
  4679.5    0.03       0  4754.8    0.05       0  4918.4    0.04       0
  4963.0    0.12       0  4995.9    0.05       0  4999.9    0.12       0
  5133.7    0.04       0  5270.2    0.12       0  5401.0    0.04       0
  5892.0    0.05       0  6074.9    0.12       0  6136.8    0.04       0
  6275.6    0.12       0  6435.6   0.013       0  6467.2    0.12       0
Bank Sta=4995.9,4999.9
Exp/Cntr=0.3,0.1

Type RM Length L Ch R = 1,1748,0,0,0
BEGIN DESCRIPTION:
LGII4601
END DESCRIPTION:
XS GIS Cut Line= 4
      2452998.04     13536044.50      2451950.48     13535276.30
      2451089.17     13535408.21      2450446.13     13536291.42
#Sta/Elev= 30
  3858.2  255.19  4268.3  252.87  4682.1  246.27  4947.5  244.60  5001.9  242.21
  5002.2  241.71  5005.9  242.21  5124.7  244.58  5193.1  245.70  5316.7  244.03
  5425.8  245.92  5615.1  246.18  5870.9  248.08  6194.4  248.23  6208.7  249.39
  6236.1  251.25  6272.0  251.01  6294.8  248.89  6336.5  248.14  6365.9  244.40
  6395.2  244.34  6401.4  246.35  6416.1  245.59  6422.3  247.25  6437.0  248.18
  6529.7  248.46  6880.1  251.65  6999.5  252.98  7015.7  252.73  7121.1  252.35
#Mann=10,-1,0
  3858.2    0.04       0  5001.9    0.04       0  5005.9    0.04       0
  5124.7    0.05       0  5615.1    0.04       0  6208.7   0.013       0
  6529.7    0.04       0  6880.1    0.12       0  6999.5    0.04       0
  7015.7    0.12       0
Bank Sta=5001.9,5005.9
Exp/Cntr=0.3,0.1

Chan Stop Cuts=-1