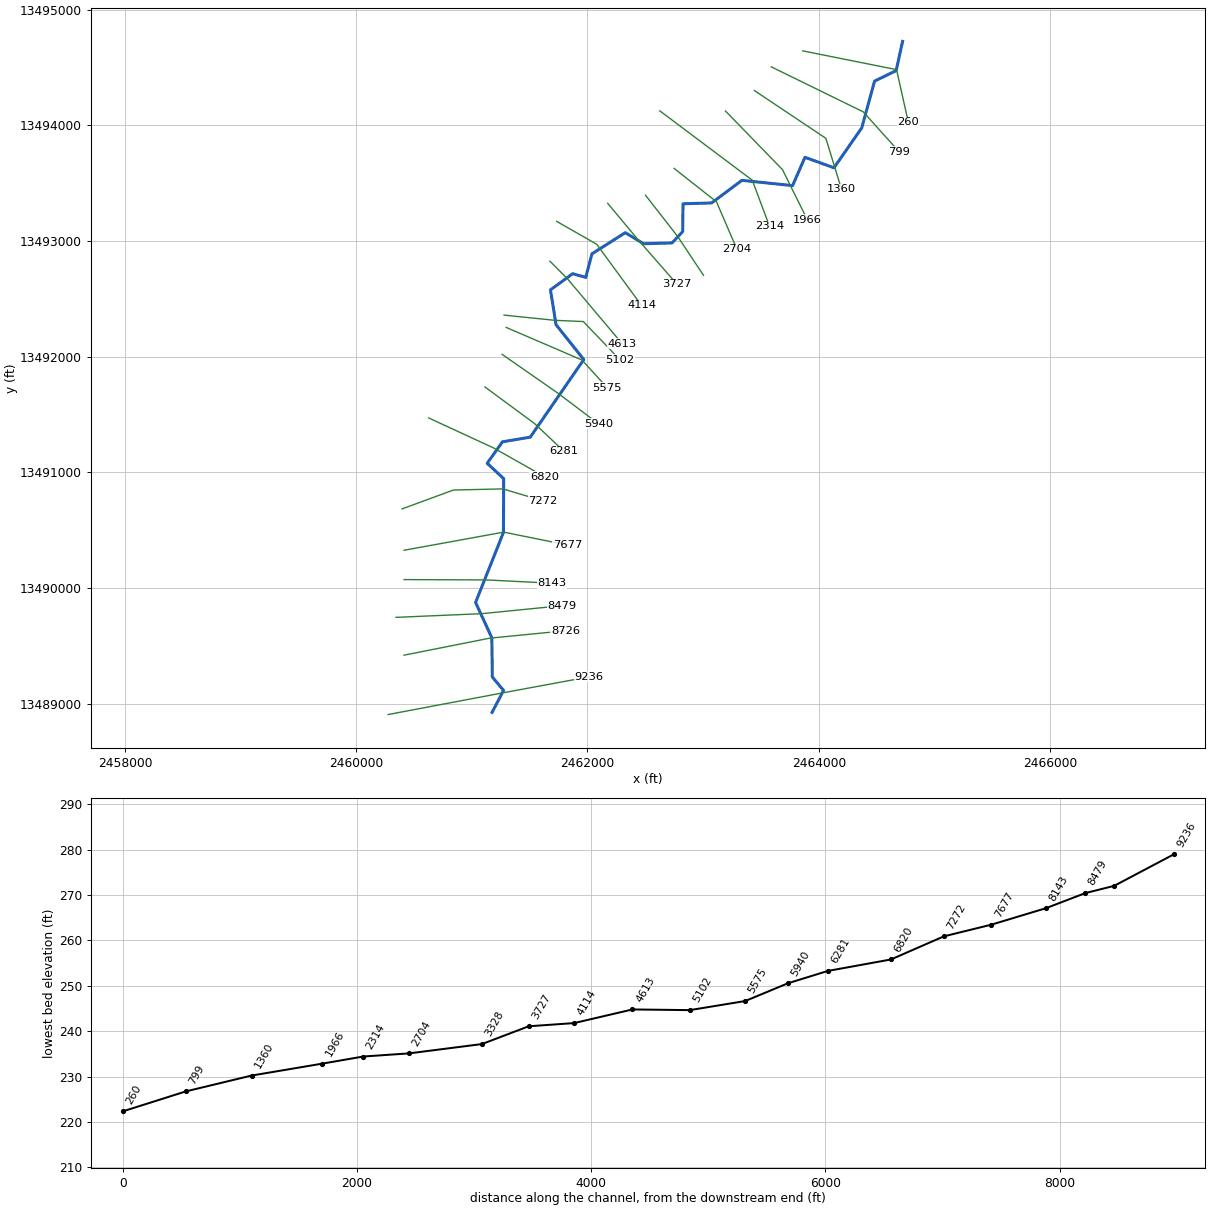
--- TRIB 10 TO EIGHTEENMILE CREEK.prj (project) ---

Proj Title=TRIB 10 TO EIGHTEENMILE CREEK Base Level Engineering
Current Plan=p01
Default Exp/Contr=0.3,0.1
English Units
Geom File=g01
Flow File=f01
Plan File=p01
Y Axis Title=Elevation
X Axis Title(PF)=Main Channel Distance
X Axis Title(XS)=Station
BEGIN DESCRIPTION:
TRIB 10 TO EIGHTEENMILE CREEK
END DESCRIPTION:
DSS Export Rating Curves= 0
DSS Export Rating Curve Sorted= 0
DSS Export Volume Flow Curves= 0
DXF OffsetX= 0
DXF OffsetY= 0
DXF ScaleX= 1
DXF ScaleY= 10

--- TRIB 10 TO EIGHTEENMILE CREEK.p01 (plan) ---

Plan Title=Multiple Run
Program Version=4.10
Short Identifier=Multiple
Geom File=g01
Flow File=f01
Subcritical Flow
K Sum by GR= 0
Std Step Tol= 0.01
Critical Tol= 0.01
Num of Std Step Trials= 20
Max Error Tol= 0.3
Flow Tol Ratio= 0.001
Split Flow NTrial= 30
Split Flow Tol= 0.02
Split Flow Ratio= 0.02
Log Output Level= 0
Friction Slope Method= 1
Unsteady Friction Slope Method= 2
Unsteady Bridges Friction Slope Method= 1
Parabolic Critical Depth
Global Vel Dist= 1 , 1 , 1
Global Log Level= 0
CheckData=True
Encroach Param=-1 ,0,0, 0
BEGIN DESCRIPTION:
Multiple Run
END DESCRIPTION:
Computation Interval=1HOUR
Output Interval=1HOUR
Run HTab= 0
Run UNet= 0
Run PostProcess= 0
Run WQNet= 0
UNET Theta= 1
UNET Theta Warmup= 1
UNET ZTol= 0.02
UNET ZSATol= 0.05
UNET MxIter= 20
UNET MaxInSteps= 0
UNET DtIC= 0
UNET DtMin= 0
UNET MaxCRTS= 20
UNET WFStab= 2
UNET SFStab= 1
UNET WFX= 1
UNET SFX= 1
UNET DSS MLevel= 4
UNET DZMax Abort= 100
UNET Convert EG Bridges= 0
UNET Use Existing IB Tables=-1
UNET Froude Reduction=False
UNET Froude Limit= 1
UNET Froude Power= 10
UNET Time Slicing=0,0, 5
UNET Junction Losses=0
Instantaneous Interval=1HOUR
Write IC File= 0
Write IC File at Sim End=0
Echo Input=False
Echo Parameters=False
Echo Output=False
Write Detailed= 0
WQ AD Non Conservative
WQ ULTIMATE=-1
WQ Max Comp Step=1HOUR
WQ Output Interval=15MIN
WQ Output Selected Increments= 0
WQ Output face flow=0
WQ Output face velocity=0
WQ Output face area=0
WQ Output face dispersion=0
WQ Output cell volume=0
WQ Output cell surface area=0
WQ Output cell continuity=0
WQ Output cumulative cell continuity=0
WQ Output face conc=0
WQ Output face dconc_dx=0
WQ Output face courant=0
WQ Output face peclet=0
WQ Output face adv mass=0
WQ Output face disp mass=0
WQ Output cell mass=0
WQ Output cell source sink temp=0
WQ Output cell source sink nsm=0
WQ Output MaxMinRange=-1
WQ Daily Max Min Mean=-1
WQ Daily Range=0
WQ Daily Time=0
WQ Create Restart=0
WQ Fixed Restart=0
WQ System Summary=0
WQ Use Fixed Temperature=0
Sorting and Armoring Iterations= 10
XS Update Threshold= 0.02
Hydraulics Update Threshold= 0.02
Energy Slope Method= 1
Volume Change Method= 0
XS Weighting Method= 0
Number of US Weighted Cross Sections= 1
Number of DS Weighted Cross Sections= 1
Upstream XS Weight=0.25
Main XS Weight=0.5
Downstream XS Weight=0.25
Number of DS XS's Weighted with US Boundary= 1
Upstream Boundary Weight= 1
Weight of XSs Associated with US Boundary= 0
Number of US XS's Weighted with DS Boundary= 1
Downstream Boundary Weight= 0.5
Weight of XSs Associated with DS Boundary= 0.5
Sediment Output Level= 4
Mass or Volume Output= 0
Output Increment Type= 1
Profile and TS Output Increment= 10
XS Output Flag= 0
XS Output Increment= 10
Disregard all LS=0
Disregard all Conn=0
Disregard all Breaches=0
Disregard all Pumps=0

--- TRIB 10 TO EIGHTEENMILE CREEK.f01 (steady flow) ---

Flow Title=Multiple
Number of Profiles=7
Profile Names=10-year,25-year,50-year,1pct_min,100-year,1pct_plu,500-year
River Rch & RM= TRIB 10 TO EIGHT,Reach-1,9236
     371     582     767     491     980    1956    1581
River Rch & RM= TRIB 10 TO EIGHT,Reach-1,6820
     859    1420    1939    1282    2557    5103    4402
River Rch & RM= TRIB 10 TO EIGHT,Reach-1,4613
    1038    1727    2369    1570    3133    6252    5430
Boundary for River Rch & Prof#=TRIB 10 TO EIGHT,Reach-1,1
Up Type=0
Dn Type=3
Dn Slope=0.005
Boundary for River Rch & Prof#=TRIB 10 TO EIGHT,Reach-1,2
Up Type=0
Dn Type=3
Dn Slope=0.005
Boundary for River Rch & Prof#=TRIB 10 TO EIGHT,Reach-1,3
Up Type=0
Dn Type=3
Dn Slope=0.005
Boundary for River Rch & Prof#=TRIB 10 TO EIGHT,Reach-1,4
Up Type=0
Dn Type=3
Dn Slope=0.005
Boundary for River Rch & Prof#=TRIB 10 TO EIGHT,Reach-1,5
Up Type=0
Dn Type=3
Dn Slope=0.005
Boundary for River Rch & Prof#=TRIB 10 TO EIGHT,Reach-1,6
Up Type=0
Dn Type=3
Dn Slope=0.005
Boundary for River Rch & Prof#=TRIB 10 TO EIGHT,Reach-1,7
Up Type=0
Dn Type=3
Dn Slope=0.005

--- TRIB 10 TO EIGHTEENMILE CREEK.g01 (geometry) ---

Geom Title=Existing Conditions
Program Version=4.10

River Reach=TRIB 10 TO EIGHT,Reach-1
Reach XY= 30
        2461175.       13488925.      2461274.06     13489114.51
      2461177.07     13489230.86      2461172.93     13489569.14
      2461032.53     13489875.01      2461273.37     13490481.04
      2461275.46     13490945.25      2461132.76     13491078.05
      2461264.94     13491263.89      2461505.21     13491304.02
      2461967.92       13491975.      2461728.07     13492276.43
      2461680.08     13492577.31      2461871.69     13492716.93
      2461985.05     13492685.05      2462038.36     13492888.34
      2462326.74     13493071.69      2462485.44     13492976.06
      2462731.21      13492982.8      2462823.39     13493081.02
      2462826.22     13493321.56      2463073.54     13493328.54
       2463335.5      13493523.8      2463773.75     13493478.36
      2463880.69     13493723.13      2464131.38     13493632.33
      2464371.39      13493976.5      2464482.68     13494381.52
      2464669.29     13494472.42        2464725.       13494725.

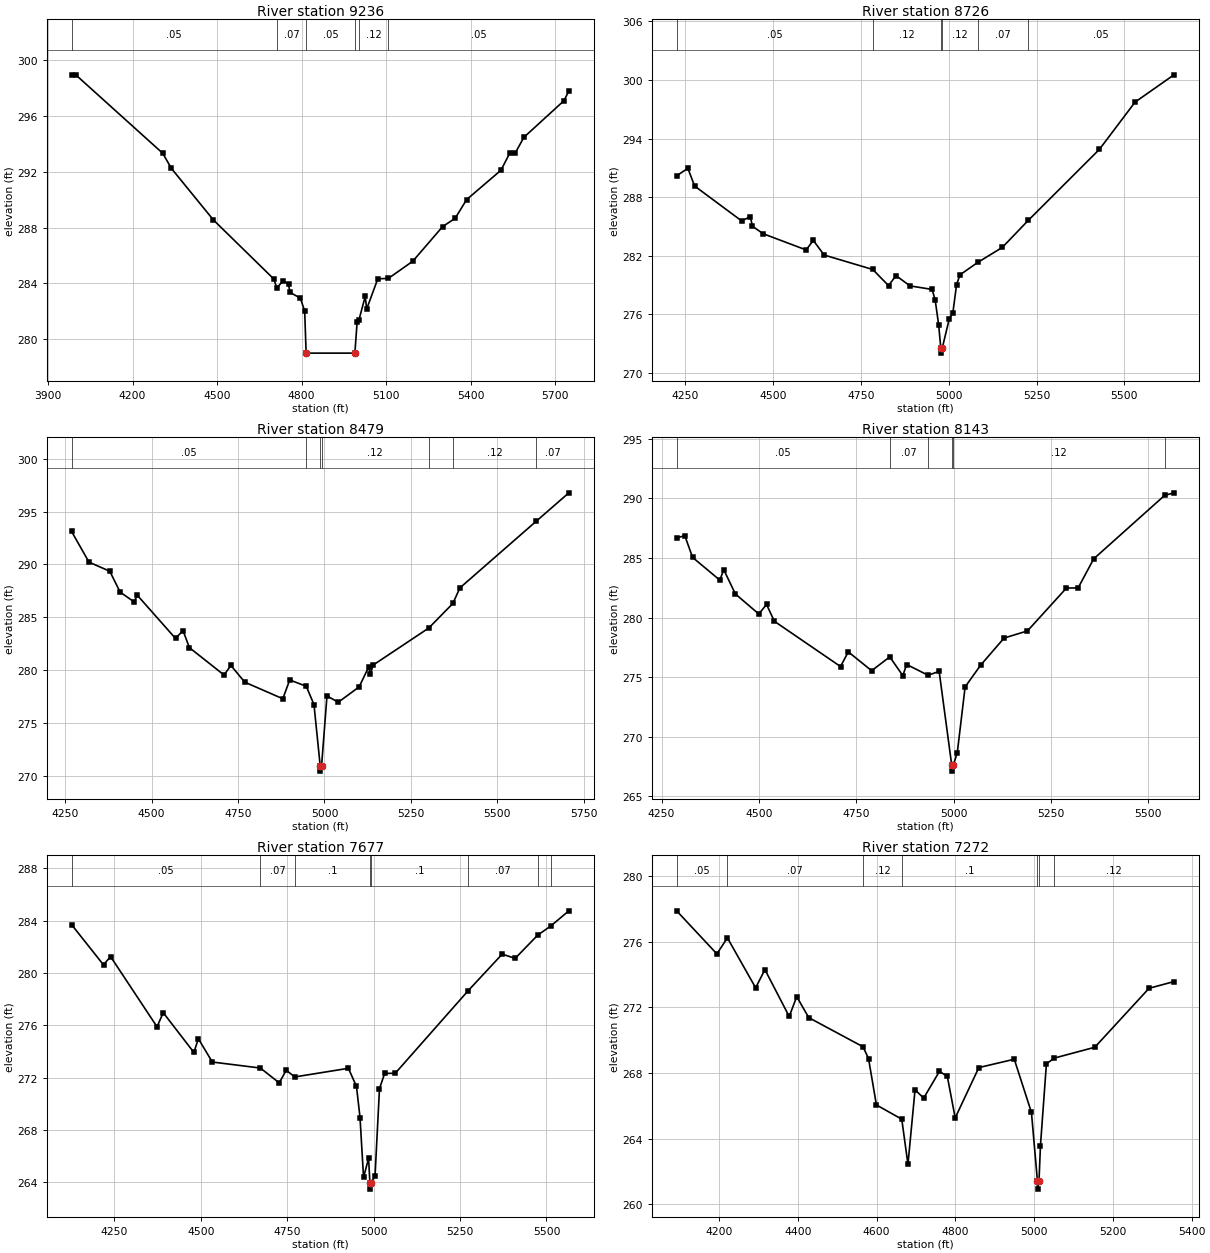
Type RM Length L Ch R = 1 ,9236    ,510,510,510
BEGIN DESCRIPTION:
TRIB 10 TO EIGHTEENMILE CREEK 19.0
END DESCRIPTION:
XS GIS Cut Line= 3
      2460276.75     13488906.35      2461275.68     13489095.08
      2462011.84     13489231.52
#Sta/Elev= 30
  3983.4  298.96    4000  298.93  4307.3  293.33  4337.8  292.25  4486.6  288.56
  4701.2  284.32  4712.1  283.67  4734.7   284.2  4753.6  283.94  4758.7  283.36
  4795.8  282.94    4811  282.01  4816.1     279  4989.1     279  4997.1  281.22
  5003.5  281.37  5025.9  283.07    5031  282.16  5070.5  284.33  5108.1  284.36
  5194.6  285.59  5300.4  288.07  5345.1  288.67  5385.8  290.01  5507.8  292.12
  5538.3  293.32  5558.7  293.37  5589.2  294.48  5731.6  297.11  5748.7  297.81
#Mann= 6 ,-1 , 0
  3983.4     .05       0  4712.1     .07       0  4816.1     .05       0
  4989.1     .07       0  5003.5     .12       0  5108.1     .05       0
Bank Sta=4816.1,4989.1
XS Rating Curve= 0 ,0
Exp/Cntr=0.3,0.1

Type RM Length L Ch R = 1 ,8726    ,247,247,247
BEGIN DESCRIPTION:
Mapping XS 81193661
END DESCRIPTION:
XS GIS Cut Line= 3
      2460413.58     13489419.29       2461155.7     13489566.55
      2461811.08     13489630.67
#Sta/Elev= 30
  4225.9  290.19  4257.9  290.95  4277.1  289.14  4410.9  285.57  4435.7  286.01
  4441.4  285.03    4472  284.26  4594.4   282.6  4614.8  283.58  4645.5  282.08
    4784   280.6  4828.8  278.95  4850.2  279.97    4890  278.92  4952.6  278.56
  4961.4  277.52  4971.6   274.9  4977.6  272.54  4977.8  272.04  4981.6  272.54
  5001.9  275.58  5011.9  276.16  5022.4  279.04    5032  280.05  5082.6  281.32
  5152.6  282.86  5226.3  285.62  5428.8  292.89  5530.4  297.73    5641  300.52
#Mann= 6 ,-1 , 0
  4225.9     .05       0    4784     .12       0  4977.6     .05       0
  4981.6     .12       0  5082.6     .07       0  5226.3     .05       0
Bank Sta=4977.6,4981.6
XS Rating Curve= 0 ,0
Exp/Cntr=0.3,0.1

Type RM Length L Ch R = 1 ,8479    ,336,336,336
BEGIN DESCRIPTION:
Mapping XS ddec20db
END DESCRIPTION:
XS GIS Cut Line= 3
      2460344.55     13489746.36       2461085.2     13489778.06
      2461778.64     13489847.06
#Sta/Elev= 30
  4268.6  293.13  4319.1  290.22  4379.2  289.36  4409.2  287.38  4449.2  286.47
  4459.2  287.07  4569.3     283    4591  283.74  4609.4  282.13  4709.5  279.54
  4729.5  280.44  4769.5  278.86  4879.6  277.29  4899.6  279.07  4947.4  278.47
  4969.7  276.74  4987.7  270.94    4988  270.44  4991.7  270.94  5007.3  277.56
  5039.9  276.96  5100.2  278.41  5127.9  280.29    5133  279.61  5140.4  280.47
  5301.9  283.99  5371.4  286.31  5391.6  287.78    5612  294.08  5706.8  296.78
#Mann= 7 ,-1 , 0
  4268.6     .05       0  4947.4     .12       0  4987.7     .05       0
  4991.7     .12       0  5301.9     .07       0  5371.4     .12       0
    5612     .07       0
Bank Sta=4987.7,4991.7
XS Rating Curve= 0 ,0
Exp/Cntr=0.3,0.1

Type RM Length L Ch R = 1 ,8143    ,466,466,466
BEGIN DESCRIPTION:
Mapping XS 546a1bd9
END DESCRIPTION:
XS GIS Cut Line= 3
      2460413.99     13490072.75      2461125.38     13490069.84
      2461690.87     13490041.54
#Sta/Elev= 30
  4288.6  286.69  4309.6  286.87  4329.6  285.05  4399.6  283.14  4409.6  284.02
  4439.6  281.98  4499.6   280.3  4519.6   281.1  4539.6  279.69  4709.6  275.89
  4729.6  277.12  4789.6  275.54  4836.1   276.7  4869.6  275.13  4879.6  276.06
  4934.4  275.16    4963  275.48  4995.3  267.61  4995.6  267.11  4999.3  267.61
  5009.6  268.66  5029.7  274.18  5069.7  276.01  5129.8  278.28  5189.9  278.88
    5290  282.48    5320  282.49  5360.1  284.93  5542.4  290.26  5566.2  290.47
#Mann= 6 ,-1 , 0
  4288.6     .05       0  4836.1     .07       0  4934.4     .12       0
  4995.3     .05       0  4999.3     .12       0  5542.4     .07       0
Bank Sta=4995.3,4999.3
XS Rating Curve= 0 ,0
Exp/Cntr=0.3,0.1

Type RM Length L Ch R = 1 ,7677    ,405,405,405
BEGIN DESCRIPTION:
Mapping XS b3b9ae22
END DESCRIPTION:
XS GIS Cut Line= 3
      2460413.98     13490326.21      2461275.55     13490483.07
      2461827.23     13490371.35
#Sta/Elev= 30
  4126.1  283.69  4218.6  280.61  4238.9  281.25  4373.4  275.88  4391.4  276.96
    4480  273.92    4493  274.97  4533.3  273.19  4672.4  272.73  4726.8   271.6
  4747.2  272.56  4771.8  272.05    4927  272.71  4950.4  271.32  4960.6  268.95
  4970.8  264.37  4985.4  265.84  4989.1  263.98  4989.4  263.48  4993.1  263.98
  5004.1  264.52  5016.9  271.16  5031.9  272.32  5062.5  272.33  5272.8  278.62
  5371.8  281.43  5409.4  281.11  5474.5  282.88  5512.3  283.58  5564.7  284.74
#Mann= 8 ,-1 , 0
  4126.1     .05       0  4672.4     .07       0  4771.8      .1       0
  4989.1     .05       0  4993.1      .1       0  5272.8     .07       0
  5474.5     .05       0  5512.3     .07       0
Bank Sta=4989.1,4993.1
XS Rating Curve= 0 ,0
Exp/Cntr=0.3,0.1

Type RM Length L Ch R = 1 ,7272    ,452,452,452
BEGIN DESCRIPTION:
Mapping XS 4aba732f
END DESCRIPTION:
XS GIS Cut Line= 4
      2460396.63     13490683.85      2460840.94     13490846.89
       2461268.5     13490856.72      2461615.36     13490753.31
#Sta/Elev= 30
  4092.2   277.9  4194.4  275.27  4221.1  276.25  4292.8   273.2  4316.4  274.31
  4378.1  271.45  4397.2  272.66  4427.7  271.38  4565.6   269.6  4579.5  268.88
  4599.5  266.05  4663.9  265.18  4679.6  262.42  4697.6  266.97  4719.6  266.47
  4759.6   268.1  4779.6  267.79  4799.6  265.26  4859.6  268.33  4949.6  268.84
  4993.2  265.59  5008.4  261.41  5008.6  260.91  5012.4  261.41  5016.1  263.57
  5031.2  268.56  5051.3  268.91    5154  269.57  5291.8  273.17  5355.1  273.58
#Mann= 7 ,-1 , 0
  4092.2     .05       0  4221.1     .07       0  4565.6     .12       0
  4663.9      .1       0  5008.4     .05       0  5012.4      .1       0
  5051.3     .12       0
Bank Sta=5008.4,5012.4
XS Rating Curve= 0 ,0
Exp/Cntr=0.3,0.1

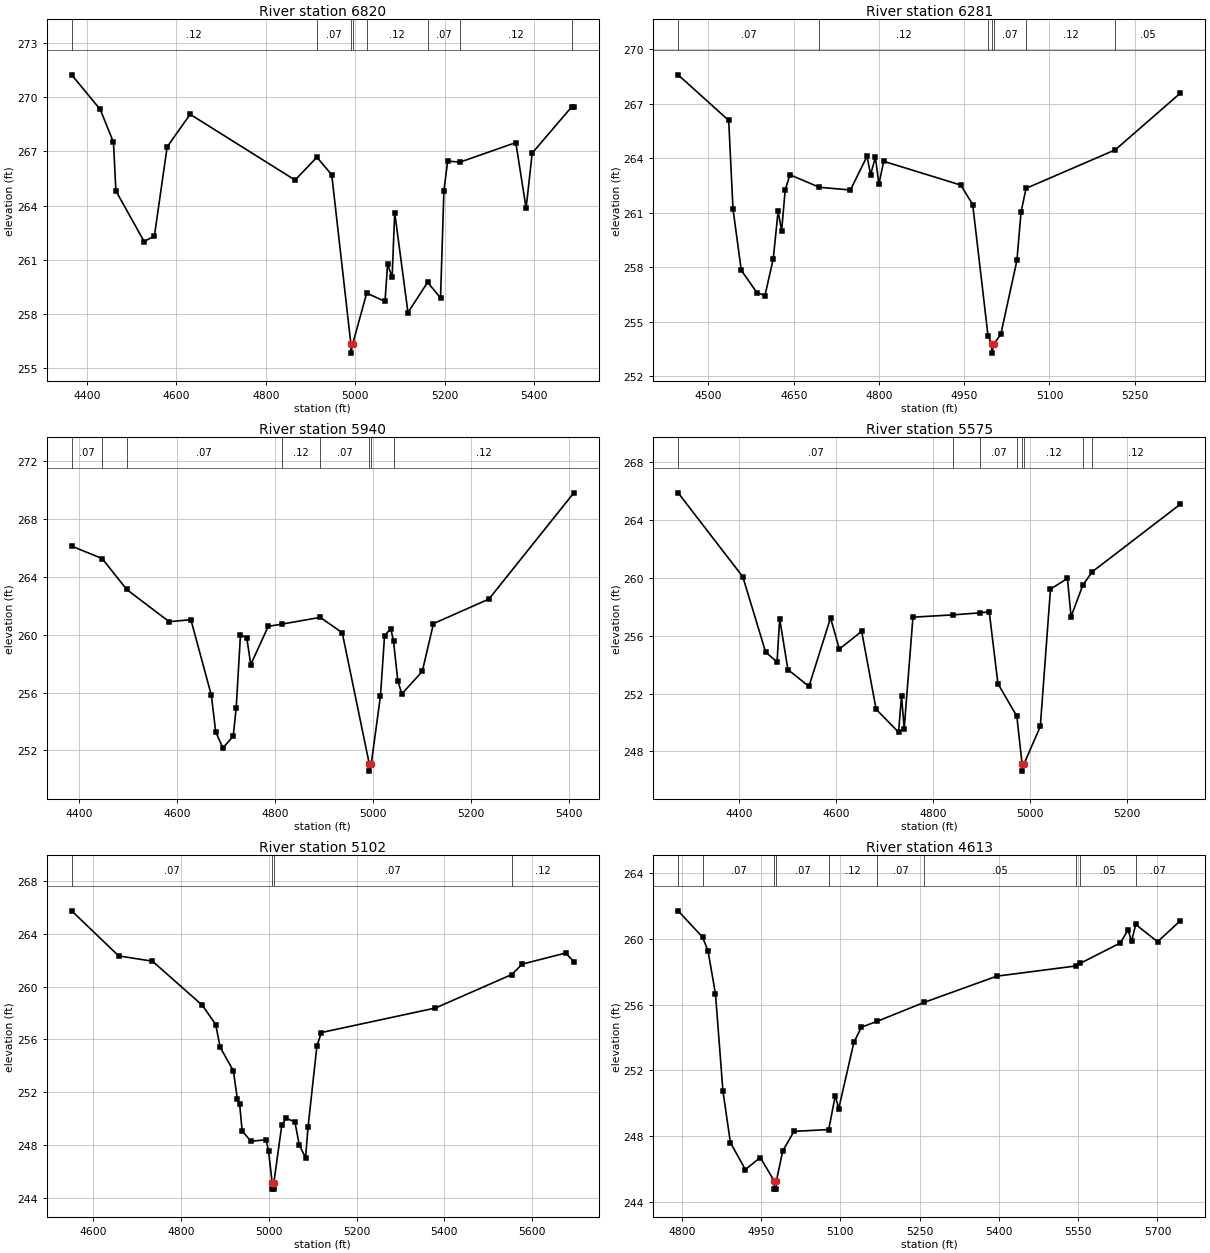
Type RM Length L Ch R = 1 ,6820    ,539,539,539
BEGIN DESCRIPTION:
Mapping XS 0b5ec37e
END DESCRIPTION:
XS GIS Cut Line= 3
      2460626.98     13491470.07      2461190.95     13491209.23
      2461628.04     13490962.48
#Sta/Elev= 30
  4365.7  271.25  4429.6  269.33  4459.2  267.51  4464.7  264.81  4527.9     262
  4550.8  262.31  4579.3  267.25  4630.7  269.06  4865.5  265.41  4914.2  266.68
  4947.5   265.7  4990.3  256.31  4990.5  255.81  4994.3  256.31  5025.6  259.14
  5066.6  258.68  5072.4  260.75  5082.5  260.01  5088.3  263.61    5118  258.06
  5161.9  259.74  5190.8  258.87  5198.4  264.83  5206.7  266.46  5234.7  266.41
  5359.2  267.49  5382.2  263.85  5395.9  266.91  5484.5  269.48    5489  269.48
#Mann= 8 ,-1 , 0
  4365.7     .12       0  4914.2     .07       0  4990.3     .05       0
  4994.3     .07       0  5025.6     .12       0  5161.9     .07       0
  5234.7     .12       0  5484.5     .07       0
Bank Sta=4990.3,4994.3
XS Rating Curve= 0 ,0
Exp/Cntr=0.3,0.1

Type RM Length L Ch R = 1 ,6281    ,341,341,341
BEGIN DESCRIPTION:
Mapping XS 00b8ba42
END DESCRIPTION:
XS GIS Cut Line= 3
      2461113.37     13491738.01      2461543.46     13491420.73
      2461797.29       13491181.
#Sta/Elev= 30
  4446.6   268.6  4535.6  266.09  4543.1  261.23  4557.7  257.84  4585.3  256.61
  4599.4  256.45    4614  258.47  4622.5  261.09  4628.7  260.02    4635  262.26
  4643.3   263.1    4695  262.41  4749.8  262.26    4779  264.12  4785.3   263.1
  4793.7  264.07  4799.9  262.58  4808.3  263.84    4944  262.53  4964.9  261.46
  4991.8  254.25  4998.2  253.78  4998.5  253.28  5002.2  253.78  5014.4  254.32
  5042.7  258.38    5050  261.05  5058.8  262.35  5215.7  264.47  5330.2  267.59
#Mann= 7 ,-1 , 0
  4446.6     .07       0    4695     .12       0  4991.8     .07       0
  4998.2     .05       0  5002.2     .07       0  5058.8     .12       0
  5215.7     .05       0
Bank Sta=4998.2,5002.2
XS Rating Curve= 0 ,0
Exp/Cntr=0.3,0.1

Type RM Length L Ch R = 1 ,5940    ,365,365,365
BEGIN DESCRIPTION:
Mapping XS f676fc2a
END DESCRIPTION:
XS GIS Cut Line= 3
      2461261.48     13492019.97      2461747.91     13491681.59
      2462093.34     13491420.75
#Sta/Elev= 30
  4384.7  266.13  4447.1  265.27  4497.1  263.13  4583.9   260.9  4628.2  261.04
    4670   255.8  4678.8  253.28  4693.5  252.16  4714.6  252.98  4720.7  254.95
  4729.4  259.99  4742.3  259.79  4750.4  257.93  4786.1  260.58  4813.2  260.73
  4892.3   261.2  4937.2  260.14  4992.4  251.06  4992.7  250.56  4996.4  251.06
  5015.3  255.78  5023.6  259.93  5036.3  260.43    5042  259.54  5050.7  256.79
    5059  255.91  5100.6  257.46  5123.5  260.77  5236.8  262.47  5410.1  269.82
#Mann= 8 ,-1 , 0
  4384.7     .07       0  4447.1     .12       0  4497.1     .07       0
  4813.2     .12       0  4892.3     .07       0  4992.4     .05       0
  4996.4     .07       0    5042     .12       0
Bank Sta=4992.4,4996.4
XS Rating Curve= 0 ,0
Exp/Cntr=0.3,0.1

Type RM Length L Ch R = 1 ,5575    ,473,473,473
BEGIN DESCRIPTION:
Mapping XS 007ec3b9
END DESCRIPTION:
XS GIS Cut Line= 3
      2461296.69     13492252.65      2461952.36     13491970.64
      2462170.42     13491731.48
#Sta/Elev= 30
  4273.3  265.89    4407  260.08  4454.1  254.87  4477.7  254.19  4483.1  257.18
  4500.1  253.66  4543.6   252.5  4588.2  257.24  4606.3  255.08  4652.5  256.31
  4682.3  250.92  4728.7  249.33  4734.8  251.85  4740.3  249.58  4758.4  257.29
  4842.1  257.45  4897.1  257.59    4916  257.66    4934  252.68    4973  250.44
  4983.8  247.14    4984  246.64  4987.8  247.14  5021.5  249.73  5042.5  259.23
  5077.6  259.97    5085  257.32  5109.3   259.5  5128.5  260.42  5310.7   265.1
#Mann= 8 ,-1 , 0
  4273.3     .07       0  4842.1     .12       0  4897.1     .07       0
    4973     .12       0  4983.8     .05       0  4987.8     .12       0
  5109.3      .1       0  5128.5     .12       0
Bank Sta=4983.8,4987.8
XS Rating Curve= 0 ,0
Exp/Cntr=0.3,0.1

Type RM Length L Ch R = 1 ,5102    ,489,489,489
BEGIN DESCRIPTION:
Mapping XS 9cc5fb24
END DESCRIPTION:
XS GIS Cut Line= 4
      2461278.25     13492358.94      2461719.24      13492313.8
      2461964.03     13492303.38      2462280.02     13491973.51
#Sta/Elev= 30
  4550.2  265.74  4657.5  262.32  4734.5  261.92  4848.5  258.57  4878.7  257.12
  4888.7  255.41  4918.9  253.61  4928.2  251.45  4933.3  251.06    4939  249.05
  4959.1  248.27  4993.5  248.38  4999.3  247.52  5007.3  245.14  5007.5  244.64
    5011  244.64  5011.3  245.14  5029.3  249.47  5039.3  250.02  5059.3  249.73
  5069.3  247.97  5083.6  247.03  5089.3  249.37  5109.4  255.48  5119.4  256.51
  5379.5  258.37  5553.8  260.91  5577.6   261.7  5676.6  262.54  5695.3  261.89
#Mann= 4 ,-1 , 0
  4550.2     .07       0  5007.3     .05       0  5011.3     .07       0
  5553.8     .12       0
Bank Sta=5007.3,5011.3
XS Rating Curve= 0 ,0
Exp/Cntr=0.3,0.1

Type RM Length L Ch R = 1 ,4613    ,499,499,499
BEGIN DESCRIPTION:
TRIB 10 TO EIGHTEENMILE CREEK 10.0
END DESCRIPTION:
XS GIS Cut Line= 3
      2461675.03     13492824.97        2461825.       13492675.
      2462300.84       13492111.
#Sta/Elev= 30
  4793.2   261.7  4839.5   260.1  4849.7  259.27  4863.9  256.65    4878  250.74
  4892.1  247.62  4920.4  245.98  4948.7  246.71  4974.9  245.29  4975.2  244.79
  4978.8  244.79  4979.1  245.29  4991.1  247.11  5012.4   248.3  5078.1  248.41
  5090.5  250.47    5097  249.67  5125.6   253.7  5139.9  254.63  5170.1  254.99
  5258.1  256.13    5396  257.73  5545.7  258.35  5553.3   258.5    5630  259.75
  5644.3  260.55  5650.9  259.85  5658.9  260.87  5700.3  259.82  5743.2   261.1
#Mann= 10 ,-1 , 0
  4793.2    .035       0  4839.5     .07       0  4974.9     .05       0
  4979.1     .07       0  5078.1     .12       0  5170.1     .07       0
  5258.1     .05       0  5545.7     .07       0  5553.3     .05       0
  5658.9     .07       0
Bank Sta=4974.9,4979.1
XS Rating Curve= 0 ,0
Exp/Cntr=0.3,0.1

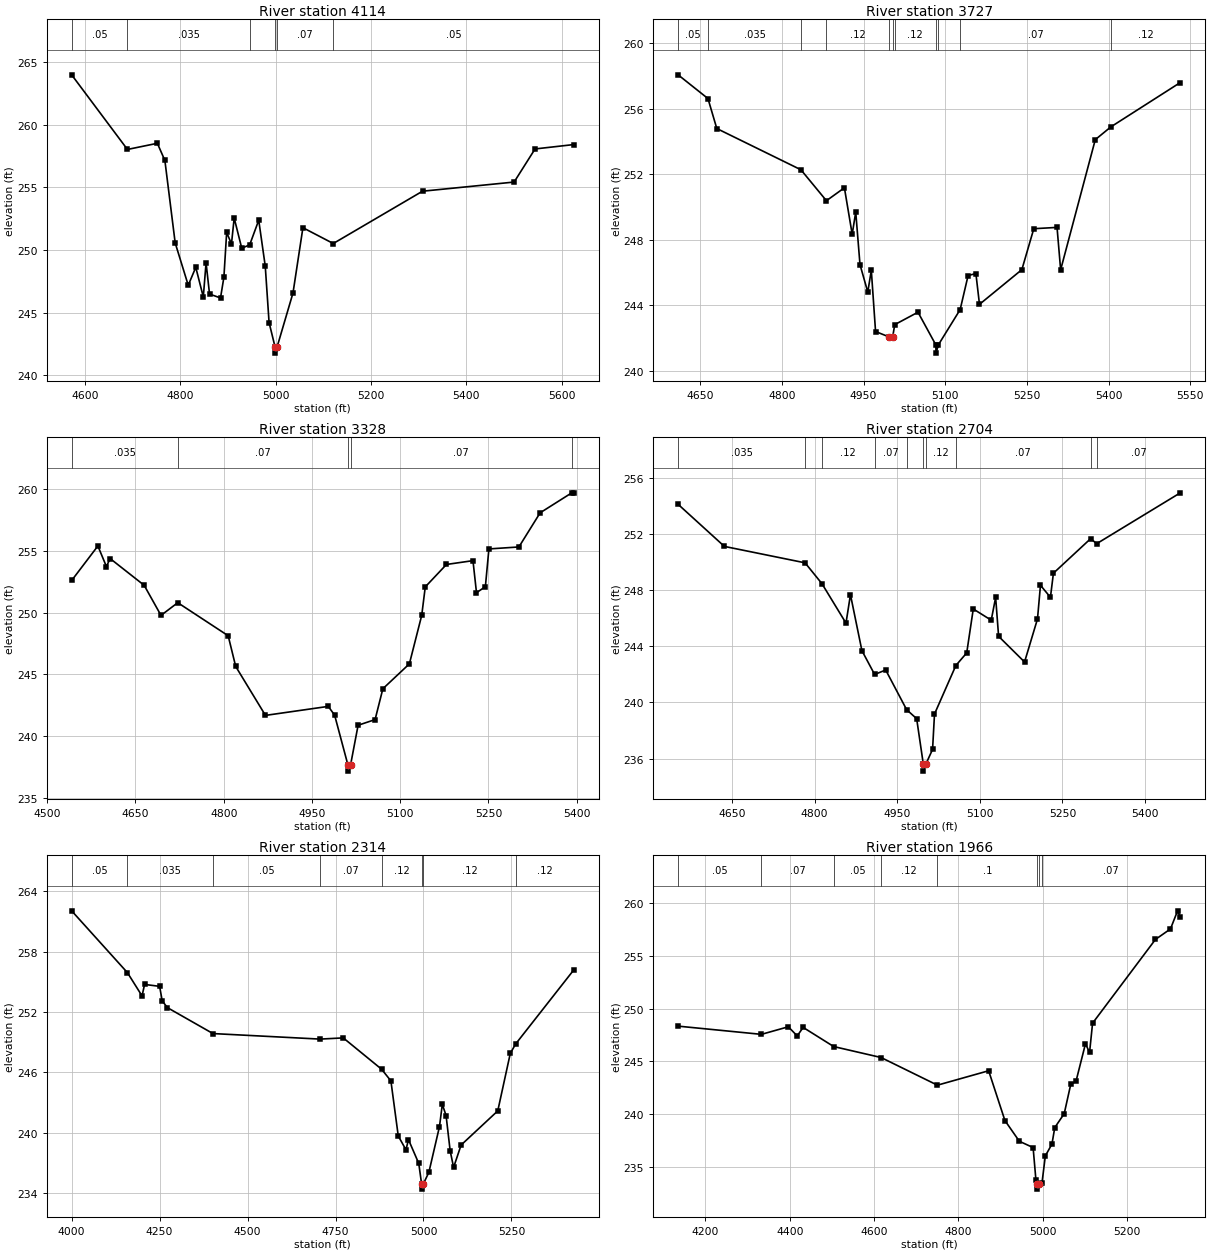
Type RM Length L Ch R = 1 ,4114    ,387,387,387
BEGIN DESCRIPTION:
Mapping XS 80e7b43b
END DESCRIPTION:
XS GIS Cut Line= 3
      2461733.83     13493169.15      2462079.27     13492971.76
      2462467.05     13492442.96
#Sta/Elev= 30
  4572.2  263.97  4689.2  258.02    4752  258.51  4767.8  257.14  4789.4  250.57
  4816.8  247.19  4832.6  248.62  4848.4  246.26  4854.2  248.98  4861.5  246.49
  4884.5  246.18  4891.6  247.83  4897.4   251.4  4907.5  250.49  4913.2  252.55
  4929.1  250.14  4945.8  250.42  4964.7  252.38  4978.4  248.71  4986.4  244.22
  4998.9  242.28  4999.2  241.78  5003.3  242.28  5036.6  246.58  5057.4  251.78
  5121.1  250.52  5308.3  254.69  5500.5  255.42  5544.4  258.06  5625.8  258.41
#Mann= 6 ,-1 , 0
  4572.2     .05       0  4689.2    .035       0  4945.8     .07       0
  4998.9     .05       0  5003.3     .07       0  5121.1     .05       0
Bank Sta=4998.9,5003.3
XS Rating Curve= 0 ,0
Exp/Cntr=0.3,0.1

Type RM Length L Ch R = 1 ,3727    ,399,399,399
BEGIN DESCRIPTION:
TRIB 10 TO EIGHTEENMILE CREEK 8.0
END DESCRIPTION:
XS GIS Cut Line= 3
      2462174.98     13493325.02        2462425.       13493025.
      2462774.97     13492625.03
#Sta/Elev= 30
  4609.5  258.08  4664.3  256.63  4680.5   254.8    4835  252.28  4881.8  250.39
  4914.8  251.18  4929.1  248.34  4935.6   249.7  4943.4  246.49  4957.7  244.81
  4964.2  246.14    4972   242.4  4996.8  242.07  5003.4  242.07  5007.2  242.82
  5049.9  243.58  5082.7  241.58    5083  241.08  5087.2  241.58  5127.3  243.74
  5141.9  245.82  5156.2  245.94  5162.8  244.06  5240.6  246.18  5262.5  248.68
  5305.2  248.76  5311.8  246.17  5375.4  254.12    5404   254.9  5531.5  257.61
#Mann= 11 ,-1 , 0
  4609.5     .05       0  4664.3    .035       0    4835     .07       0
  4881.8     .12       0  4996.8     .05       0  5003.4     .07       0
  5007.2     .12       0  5082.7     .07       0  5087.2     .12       0
  5127.3     .07       0    5404     .12       0
Bank Sta=4996.8,5003.4
XS Rating Curve= 0 ,0
Exp/Cntr=0.3,0.1

Type RM Length L Ch R = 1 ,3328    ,624,624,624
BEGIN DESCRIPTION:
Mapping XS 0907c1bf
END DESCRIPTION:
XS GIS Cut Line= 3
      2462502.24      13493394.8      2462777.23     13493042.26
      2463002.82     13492703.87
#Sta/Elev= 30
  4541.5  252.62  4586.1  255.42  4600.6  253.75  4606.9   254.4  4664.8  252.23
  4693.4  249.79  4721.9  250.82  4807.6  248.14  4820.4  245.65    4871  241.68
  4977.8  242.41  4988.6   241.7  5011.2  237.66  5011.5  237.16  5015.7  237.66
  5028.5  240.88  5057.4  241.34  5070.6  243.84  5115.7  245.86  5136.7   249.8
  5142.7   252.1  5178.7  253.92  5223.8  254.23  5229.8  251.63  5244.9  252.12
  5250.9  255.18  5301.9  255.34    5338  258.11  5391.8  259.73  5395.3  259.72
#Mann= 5 ,-1 , 0
  4541.5    .035       0  4721.9     .07       0  5011.2     .05       0
  5015.7     .07       0  5391.8     .12       0
Bank Sta=5011.2,5015.7
XS Rating Curve= 0 ,0
Exp/Cntr=0.3,0.1

Type RM Length L Ch R = 1 ,2704    ,390,390,390
BEGIN DESCRIPTION:
Mapping XS a3b4877d
END DESCRIPTION:
XS GIS Cut Line= 3
      2462749.02     13493627.42      2463115.63     13493338.36
      2463291.75     13492929.77
#Sta/Elev= 30
  4552.1  254.12  4636.1  251.12  4782.6  249.95  4813.3  248.46  4856.9  245.65
    4865  247.68  4885.8  243.69  4908.9  241.99    4929  242.31    4967  239.48
  4985.2  238.84  4997.3   235.6  4997.6   235.1  5001.9   235.6  5014.1  236.65
  5017.6  239.17  5056.4  242.63  5076.1  243.53    5088  246.66  5120.6  245.86
  5128.6  247.48    5134  244.71  5181.1  242.88  5204.6  245.95    5210  248.35
  5228.1  247.49  5233.5  249.21  5301.3  251.68  5311.9  251.31  5463.9  254.94
#Mann= 10 ,-1 , 0
  4552.1    .035       0  4782.6     .05       0  4813.3     .12       0
  4908.9     .07       0    4967     .12       0  4997.3     .05       0
  5001.9     .12       0  5056.4     .07       0  5301.3     .12       0
  5311.9     .07       0
Bank Sta=4997.3,5001.9
XS Rating Curve= 0 ,0
Exp/Cntr=0.3,0.1

Type RM Length L Ch R = 1 ,2314    ,348,348,348
BEGIN DESCRIPTION:
TRIB 10 TO EIGHTEENMILE CREEK 5.0
END DESCRIPTION:
XS GIS Cut Line= 3
      2462624.96     13494125.03        2463425.       13493525.
      2463574.98     13493125.04
#Sta/Elev= 30
  4000.1  262.05  4158.6  255.91  4200.1   253.6  4207.4  254.74  4250.1  254.55
  4257.4  253.12    4272  252.44  4401.7  249.86  4706.1  249.31    4772  249.43
  4880.9  246.32  4907.4  245.16  4928.3  239.69  4950.1  238.32  4957.4  239.32
  4986.6  236.96  4994.7  234.91    4995  234.41  4999.3  234.91  5015.3  236.08
  5045.5  240.63  5053.5  242.83  5064.2  241.72  5075.8  238.22  5085.6  236.57
  5106.9  238.79  5211.1  242.18  5246.7  247.89    5262  248.83  5427.3  256.19
#Mann= 8 ,-1 , 0
  4000.1     .05       0  4158.6    .035       0  4401.7     .05       0
  4706.1     .07       0  4880.9     .12       0  4994.7     .05       0
  4999.3     .12       0    5262     .12       0
Bank Sta=4994.7,4999.3
XS Rating Curve= 0 ,0
Exp/Cntr=0.3,0.1

Type RM Length L Ch R = 1 ,1966    ,606,606,606
BEGIN DESCRIPTION:
Mapping XS 1f0aafba
END DESCRIPTION:
XS GIS Cut Line= 3
       2463193.5     13494123.12      2463686.58     13493616.15
      2463901.86     13493182.12
#Sta/Elev= 30
  4135.1  248.34  4332.8  247.56  4396.6  248.28  4417.7  247.41  4431.8  248.22
  4504.3   246.4  4616.6  245.36  4750.4  242.73    4872   244.1  4910.6  239.37
  4944.8   237.4  4977.5   236.8  4984.1  233.75  4987.3  233.35  4987.7  232.85
    4992  233.35  4998.6  233.44  5006.5  236.01  5022.2  237.13  5028.9   238.7
  5051.3  240.02  5066.8  242.81  5079.3   243.1  5101.7  246.66  5111.5  245.85
  5118.6  248.62  5267.8  256.58  5303.5  257.58  5320.3   259.3  5326.8  258.73
#Mann= 8 ,-1 , 0
  4135.1     .05       0  4332.8     .07       0  4504.3     .05       0
  4616.6     .12       0  4750.4      .1       0  4987.3     .05       0
    4992      .1       0  4998.6     .07       0
Bank Sta=4987.3,4992
XS Rating Curve= 0 ,0
Exp/Cntr=0.3,0.1

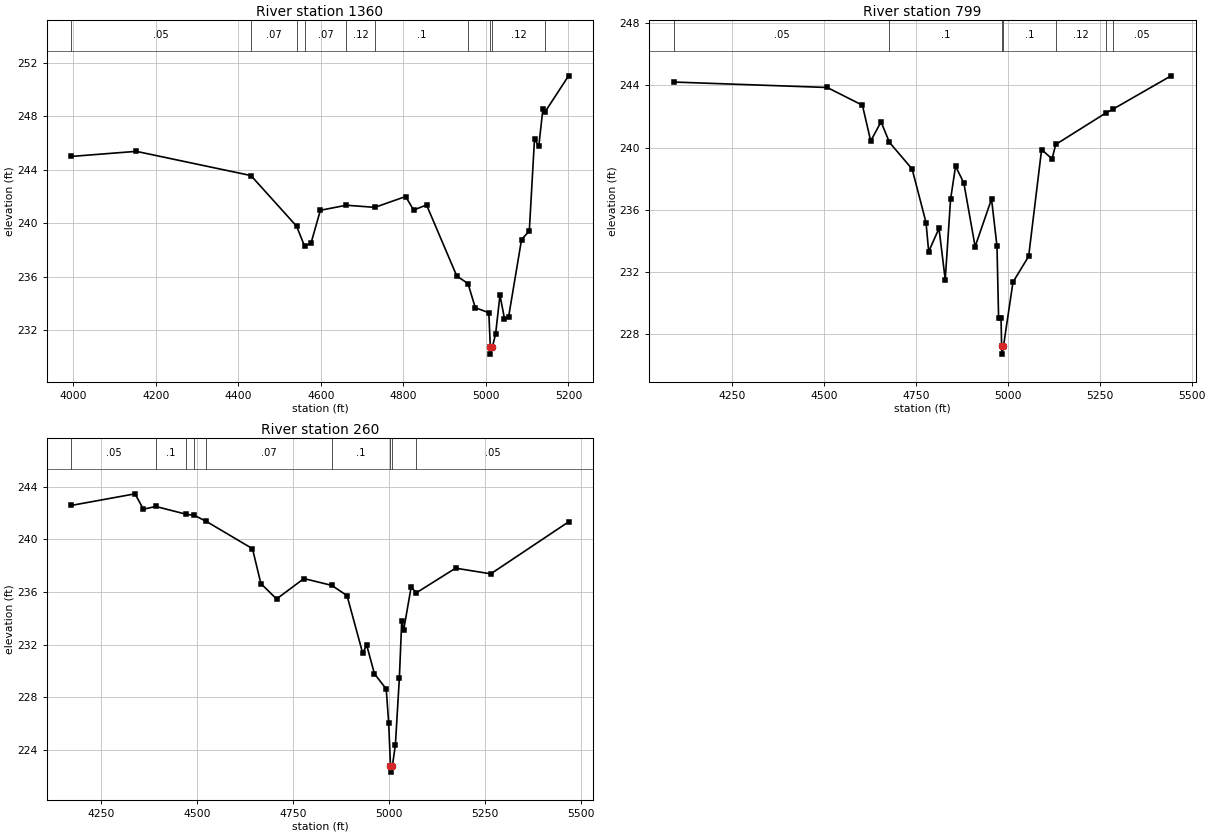
Type RM Length L Ch R = 1 ,1360    ,561,561,561
BEGIN DESCRIPTION:
Mapping XS 7232a91f
END DESCRIPTION:
XS GIS Cut Line= 3
       2463443.5      13494300.2      2464061.58     13493886.98
        2464197.       13493446.
#Sta/Elev= 30
  3995.6     245  4152.8  245.38  4430.6  243.57  4541.3  239.78  4560.7  238.28
  4576.3  238.52  4598.9  240.97  4661.9  241.35  4730.8  241.19  4805.5     242
  4824.9  240.99  4856.2  241.37  4929.5  236.05  4956.6  235.49  4974.3  233.68
  5007.1  233.31  5010.8  230.71  5011.1  230.21  5015.5  230.71  5023.6  231.73
  5034.1  234.62    5045  232.87    5055  232.99  5086.4  238.78  5105.2  239.43
  5117.8   246.3  5128.2  245.76    5138  248.52  5143.1  248.32  5200.4  251.03
#Mann= 10 ,-1 , 0
  3995.6     .05       0  4430.6     .07       0  4541.3     .12       0
  4560.7     .07       0  4661.9     .12       0  4730.8      .1       0
  4956.6     .12       0  5010.8     .05       0  5015.5     .12       0
  5143.1     .07       0
Bank Sta=5010.8,5015.5
XS Rating Curve= 0 ,0
Exp/Cntr=0.3,0.1

Type RM Length L Ch R = 1 ,799     ,539,539,539
BEGIN DESCRIPTION:
Mapping XS e3359005
END DESCRIPTION:
XS GIS Cut Line= 3
      2463589.33     13494505.05       2464384.5     13494116.15
      2464696.52     13493769.46
#Sta/Elev= 30
  4092.5  244.21  4509.4  243.86    4605  242.72  4627.5  240.42  4655.6  241.65
  4678.5  240.33  4740.1  238.62  4777.9  235.18  4785.1  233.31  4813.2   234.8
  4830.1  231.51  4844.6  236.67  4858.2   238.8  4880.7  237.72  4911.4  233.63
    4956  236.69  4970.8  233.66  4975.2  229.05  4981.8  229.05  4983.4  227.22
  4983.8  226.72  4988.4  227.22  5014.3  231.35  5056.9  233.01  5092.1  239.87
  5120.5  239.27  5130.6   240.2  5266.6  242.22  5286.4  242.47  5444.1  244.61
#Mann= 7 ,-1 , 0
  4092.5     .05       0  4678.5      .1       0  4983.4     .05       0
  4988.4      .1       0  5130.6     .12       0  5266.6     .07       0
  5286.4     .05       0
Bank Sta=4983.4,4988.4
XS Rating Curve= 0 ,0
Exp/Cntr=0.3,0.1

Type RM Length L Ch R = 1 ,260     ,0,0,0
BEGIN DESCRIPTION:
TRIB 10 TO EIGHTEENMILE CREEK 1.0
END DESCRIPTION:
XS GIS Cut Line= 3
      2463861.19     13494643.27      2464672.59     13494480.83
        2464775.     13494024.99
#Sta/Elev= 30
  4172.5  242.58  4338.2  243.46    4360  242.29  4392.2   242.5  4471.2  241.91
    4493  241.82  4524.1  241.36    4644  239.29  4665.9  236.64  4706.7  235.47
  4778.1  237.02  4850.8   236.5  4890.3  235.72  4931.1  231.34  4941.3  231.97
  4961.7  229.78  4992.3  228.63  4998.7  226.05  5003.4  222.81  5003.8  222.31
  5008.5  222.81  5016.2  224.39  5026.5  229.45  5032.7   233.8  5037.8  233.13
  5057.2  236.37  5070.9  235.94  5172.9  237.81  5264.6  237.38  5467.2  241.33
#Mann= 9 ,-1 , 0
  4172.5     .05       0  4392.2      .1       0  4471.2     .05       0
    4493      .1       0  4524.1     .07       0  4850.8      .1       0
  5003.4     .05       0  5008.5      .1       0  5070.9     .05       0
Bank Sta=5003.4,5008.5
XS Rating Curve= 0 ,0
Exp/Cntr=0.3,0.1

Chan Stop Cuts=-1
Use User Specified Reach Order=0
Composite Channel Slope=5