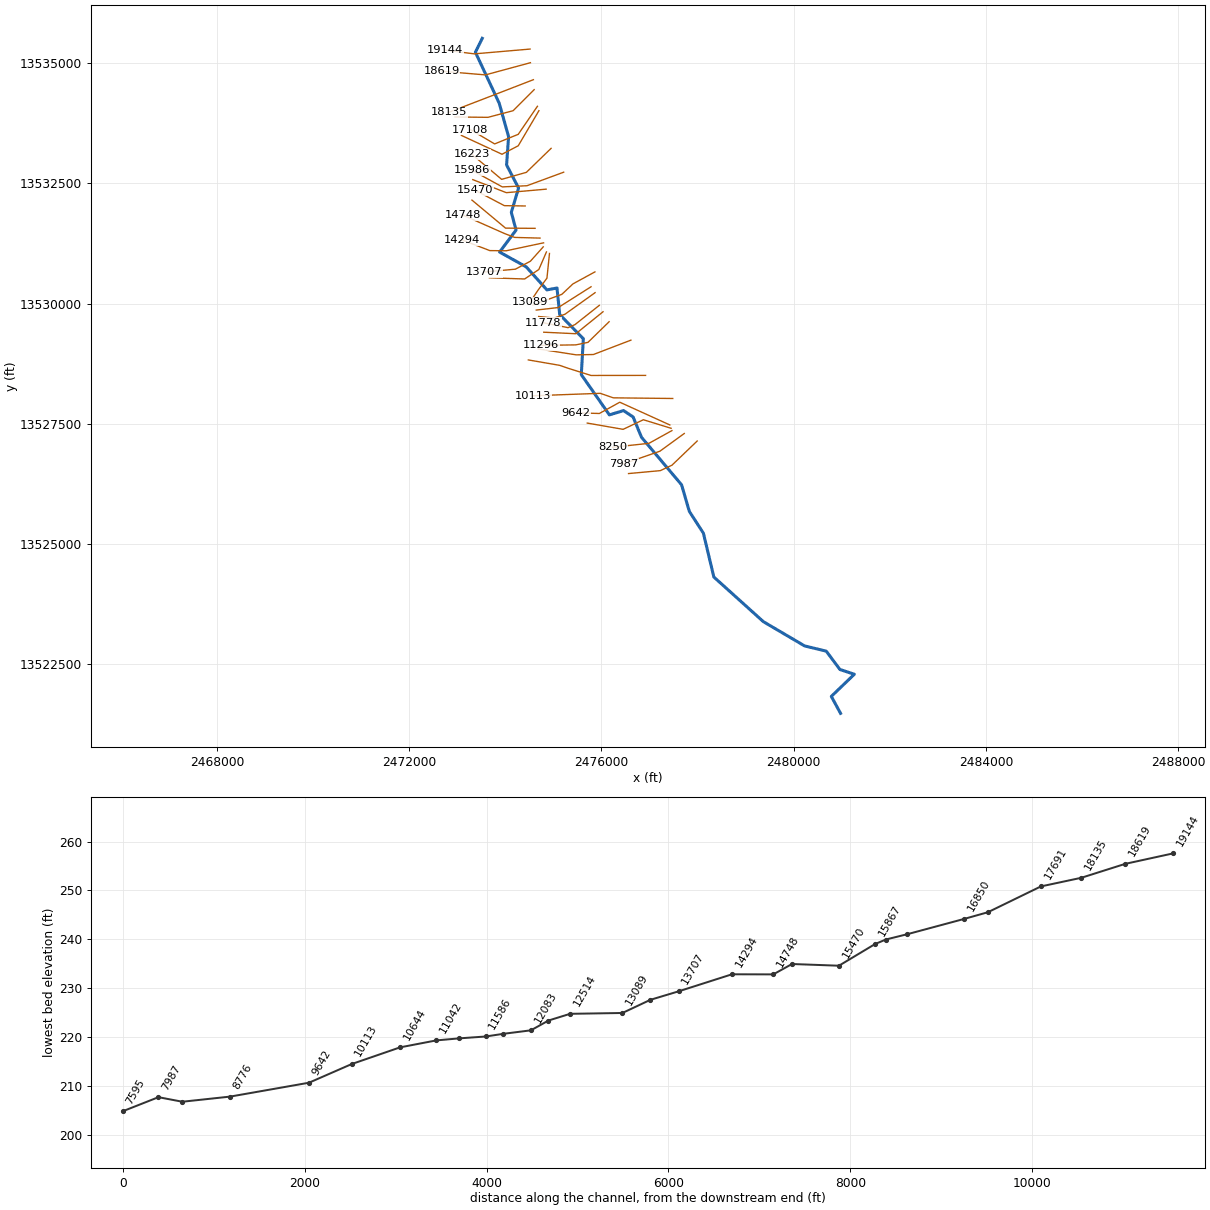
--- TRIB 10 TO FIFTEENMILE CREEK.prj (project) ---

Proj Title=TRIB 10 TO FIFTEENMILE CREEK Base Level Engineering
Current Plan=p01
Default Exp/Contr=0.3,0.1
English Units
Geom File=g01
Flow File=f01
Plan File=p01
BEGIN DESCRIPTION:
TRIB 10 TO FIFTEENMILE CREEK
END DESCRIPTION:

--- TRIB 10 TO FIFTEENMILE CREEK.p01 (plan) ---

Plan Title=Multiple Run
Short Identifier=Multiple
Geom File=g01
Flow File=f01
Subcritical Flow
K Sum by GR= 0
Std Step Tol= 0.01
Critical Tol= 0.01
Num of Std Step Trials= 20
Max Error Tol= 0.3
Flow Tol Ratio= 0.001
Split Flow NTrial= 30
Split Flow Tol= 0.02
Split Flow Ratio= 0.02
Log Output Level= 0
Friction Slope Method= 1
Unsteady Friction Slope Method= 2
Unsteady Bridges Friction Slope Method= 1
Parabolic Critical Depth
Global Vel Dist=  1 , 1 , 1
Global Log Level= 0
CheckData=True
Encroach Param= -1, 0, 0, 0
BEGIN DESCRIPTION:
Multiple Run
END DESCRIPTION:

--- TRIB 10 TO FIFTEENMILE CREEK.f01 (steady flow) ---

Flow Title=Multiple
Number of Profiles=7
Profile Names=10-year,25-year,50-year,1pct_min,100-year,1pct_plu,500-year
River Rch & RM= TRIB 10 TO FIFTE,Reach-1,19144
     638    1023    1367     884    1765    3521    2909
River Rch & RM= TRIB 10 TO FIFTE,Reach-1,14294
     734    1186    1594    1036    2066    4123    3439
River Rch & RM= TRIB 10 TO FIFTE,Reach-1,12514
    1166    1930    2636    1737    3466    6915    5937
River Rch & RM= TRIB 10 TO FIFTE,Reach-1,4990
    1834    3092    4275    2849    5685   11343    9958
Boundary for River Rch & Prof#=TRIB 10 TO FIFTE,Reach-1,1
Up Type=0
Dn Type=3
Dn Slope=0.005
Boundary for River Rch & Prof#=TRIB 10 TO FIFTE,Reach-1,2
Up Type=0
Dn Type=3
Dn Slope=0.005
Boundary for River Rch & Prof#=TRIB 10 TO FIFTE,Reach-1,3
Up Type=0
Dn Type=3
Dn Slope=0.005
Boundary for River Rch & Prof#=TRIB 10 TO FIFTE,Reach-1,4
Up Type=0
Dn Type=3
Dn Slope=0.005
Boundary for River Rch & Prof#=TRIB 10 TO FIFTE,Reach-1,5
Up Type=0
Dn Type=3
Dn Slope=0.005
Boundary for River Rch & Prof#=TRIB 10 TO FIFTE,Reach-1,6
Up Type=0
Dn Type=3
Dn Slope=0.005
Boundary for River Rch & Prof#=TRIB 10 TO FIFTE,Reach-1,7
Up Type=0
Dn Type=3
Dn Slope=0.005

--- TRIB 10 TO FIFTEENMILE CREEK.g01 (geometry) ---

Geom Title=Existing Conditions

River Reach=TRIB 10 TO FIFTE,Reach-1
Reach XY= 30
      2473519.72     13535519.72      2473376.63     13535231.04
      2473872.76     13534169.07      2474067.21     13533474.90
      2474026.08     13532885.54      2474275.10     13532404.90
      2474124.59     13531900.00      2474222.95     13531530.86
      2473880.39     13531072.56      2474434.81     13530764.49
      2474864.94     13530286.09      2475075.00     13530325.00
      2475130.83     13529772.70      2475623.02     13529269.33
      2475580.52     13528522.57      2476165.21     13527685.43
      2476459.61     13527774.93      2476658.38     13527641.71
      2476833.16     13527218.95      2477666.84     13526231.05
      2477828.75     13525676.55      2478121.38     13525223.50
      2478338.62     13524311.78      2479368.94     13523383.14
      2480226.58     13522878.82      2480677.43     13522769.48
      2480961.35     13522388.26      2481261.77     13522288.74
      2480782.84     13521828.23      2480975.00     13521475.00

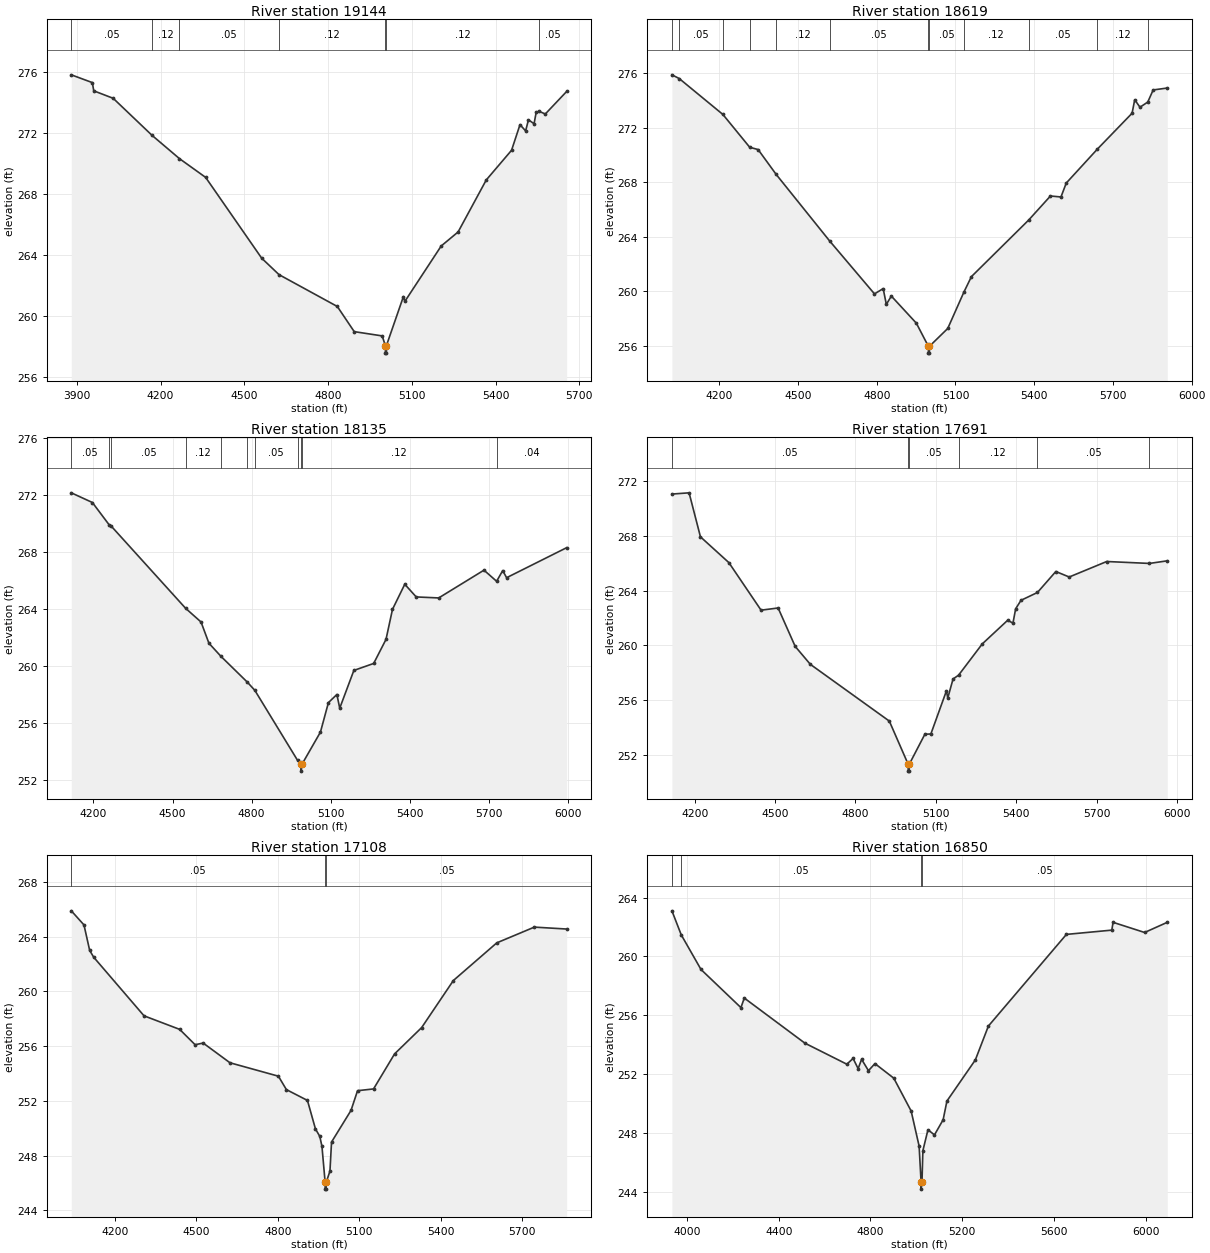
Type RM Length L Ch R = 1,19144,525,525,525
BEGIN DESCRIPTION:
Mapping XS bf536eb4
END DESCRIPTION:
XS GIS Cut Line= 3
      2474514.41     13535296.52      2473354.86     13535196.69
      2472749.14     13535273.36
#Sta/Elev= 30
  3880.3  275.83  3955.6  275.32  3960.7  274.78  4030.3  274.29  4169.4  271.86
  4267.8  270.33  4361.5  269.10  4562.2  263.80  4624.3  262.72  4833.2  260.63
  4893.7  258.98  4993.8  258.70  5005.2  258.07  5005.5  257.57  5009.0  257.57
  5009.2  258.07  5069.9  261.28  5074.9  260.96  5205.3  264.60  5265.8  265.52
  5366.6  268.93  5457.3  270.88  5487.5  272.56  5507.7  272.15  5517.8  272.88
  5537.9  272.62  5545.6  273.38  5556.6  273.43  5578.2  273.26  5654.7  274.74
#Mann=7,-1,0
  3880.3    0.05       0  4169.4    0.12       0  4267.8    0.05       0
  4624.3    0.12       0  5005.2    0.05       0  5009.2    0.12       0
  5556.6    0.05       0
Bank Sta=5005.2,5009.2
Exp/Cntr=0.3,0.1

Type RM Length L Ch R = 1,18619,484,484,484
BEGIN DESCRIPTION:
Mapping XS 9ae8746d
END DESCRIPTION:
XS GIS Cut Line= 3
      2474522.08     13535012.39      2473585.23     13534758.98
      2472671.37     13534835.77
#Sta/Elev= 30
  4019.5  275.88  4047.1  275.61  4213.7  272.97  4315.9  270.56  4348.0  270.39
  4417.0  268.56  4620.4  263.68  4791.4  259.79  4824.5  260.18  4836.5  259.02
  4855.6  259.63  4950.9  257.64  4996.7  255.94  4997.0  255.44  5000.5  255.44
  5000.7  255.94  5070.5  257.25  5131.8  259.91  5160.8  261.06  5378.7  265.21
  5461.9  266.98  5502.0  266.91  5522.1  267.93  5641.0  270.43  5773.0  273.06
  5783.0  274.05  5803.1  273.50  5832.7  273.88  5853.3  274.77  5907.1  274.91
#Mann=12,-1,0
  4019.5    0.12       0  4047.1    0.05       0  4213.7    0.12       0
  4315.9    0.05       0  4417.0    0.12       0  4620.4    0.05       0
  4996.7    0.05       0  5000.7    0.05       0  5131.8    0.12       0
  5378.7    0.05       0  5641.0    0.12       0  5832.7    0.05       0
Bank Sta=4996.7,5000.7
Exp/Cntr=0.3,0.1

Type RM Length L Ch R = 1,18135,444,444,444
BEGIN DESCRIPTION:
Mapping XS d24a9792
END DESCRIPTION:
XS GIS Cut Line= 3
      2474583.55     13534659.16      2473769.53     13534344.31
      2472832.64     13533983.37
#Sta/Elev= 30
  4116.6  272.13  4196.5  271.45  4260.1  269.88  4267.0  269.81  4549.8  264.02
  4608.1  263.06  4638.0  261.57  4683.5  260.65  4783.9  258.83  4812.0  258.26
  4973.7  253.35  4987.1  253.09  4987.4  252.59  4991.1  253.09  5060.5  255.33
  5090.7  257.40  5122.8  257.97  5133.6  257.01  5187.1  259.66  5262.2  260.15
  5308.9  261.84  5333.5  263.95  5380.0  265.71  5423.4  264.82  5508.6  264.75
  5680.1  266.70  5728.0  265.92  5751.1  266.67  5765.8  266.17  5993.4  268.28
#Mann=11,-1,0
  4116.6    0.05       0  4260.1    0.12       0  4267.0    0.05       0
  4549.8    0.12       0  4683.5    0.05       0  4783.9    0.12       0
  4812.0    0.05       0  4973.7    0.12       0  4987.1    0.05       0
  4991.1    0.12       0  5728.0    0.04       0
Bank Sta=4987.1,4991.1
Exp/Cntr=0.3,0.1

Type RM Length L Ch R = 1,17691,583,583,583
BEGIN DESCRIPTION:
Mapping XS 6cf76ee5
END DESCRIPTION:
XS GIS Cut Line= 4
      2474598.87     13534451.80      2474161.16     13534014.10
      2473638.98     13533875.88      2472948.90     13533883.55
#Sta/Elev= 30
  4114.8  271.04  4178.9  271.13  4221.3  267.92  4327.4  266.04  4447.6  262.57
  4511.3  262.73  4574.9  259.93  4631.5  258.62  4926.4  254.48  4996.8  251.33
  4997.0  250.83  5000.5  250.83  5000.8  251.33  5059.1  253.52  5081.5  253.54
  5139.5  256.68  5144.7  256.17  5164.3  257.55  5185.0  257.83  5273.4  260.11
  5368.0  261.83  5388.0  261.63  5398.0  262.67  5418.0  263.29  5479.3  263.86
  5548.0  265.39  5598.0  264.99  5738.0  266.12  5897.4  265.98  5964.1  266.17
#Mann=6,-1,0
  4114.8    0.05       0  4996.8    0.05       0  5000.8    0.05       0
  5185.0    0.12       0  5479.3    0.05       0  5897.4    0.04       0
Bank Sta=4996.8,5000.8
Exp/Cntr=0.3,0.1

Type RM Length L Ch R = 1,17108,258,258,258
BEGIN DESCRIPTION:
Mapping XS 2ea676fb
END DESCRIPTION:
XS GIS Cut Line= 4
      2474667.98     13534106.24      2474268.67     13533522.64
      2473777.21     13533322.98      2473270.39     13533622.47
#Sta/Elev= 30
  4038.6  265.89  4085.3  264.86  4106.3  263.00  4121.2  262.50  4306.7  258.22
  4438.1  257.23  4495.0  256.11  4524.8  256.23  4623.6  254.79  4802.1  253.81
  4831.6  252.83  4909.2  252.04  4938.7  249.96  4954.8  249.41  4962.7  248.68
  4974.4  246.06  4974.6  245.56  4978.1  245.56  4978.4  246.06  4992.2  246.88
  4998.0  249.00  5069.8  251.31  5093.9  252.75  5152.9  252.88  5230.5  255.44
  5330.2  257.36  5447.2  260.80  5607.2  263.55  5745.7  264.70  5864.9  264.56
#Mann=3,-1,0
  4038.6    0.05       0  4974.4    0.05       0  4978.4    0.05       0
Bank Sta=4974.4,4978.4
Exp/Cntr=0.3,0.1

Type RM Length L Ch R = 1,16850,627,627,627
BEGIN DESCRIPTION:
Mapping XS d8878047
END DESCRIPTION:
XS GIS Cut Line= 4
      2474698.73     13534014.14      2474268.67     13533284.59
      2473930.79     13533107.97      2473086.09     13533499.60
#Sta/Elev= 30
  3934.6  263.10  3975.2  261.47  4061.3  259.12  4235.4  256.53  4250.0  257.18
  4514.0  254.12  4697.0  252.69  4724.3  253.08  4746.2  252.39  4761.4  253.02
  4791.3  252.25  4819.5  252.73  4901.7  251.74  4977.4  249.51  5012.1  247.13
  5020.6  244.71  5020.8  244.21  5024.6  244.71  5028.5  246.82  5050.6  248.24
  5079.0  247.89  5116.8  248.92  5133.3  250.19  5257.2  252.98  5314.1  255.28
  5654.1  261.50  5852.0  261.79  5857.5  262.32  5995.0  261.63  6093.8  262.32
#Mann=4,-1,0
  3934.6    0.12       0  3975.2    0.05       0  5020.6    0.05       0
  5024.6    0.05       0
Bank Sta=5020.6,5024.6
Exp/Cntr=0.3,0.1

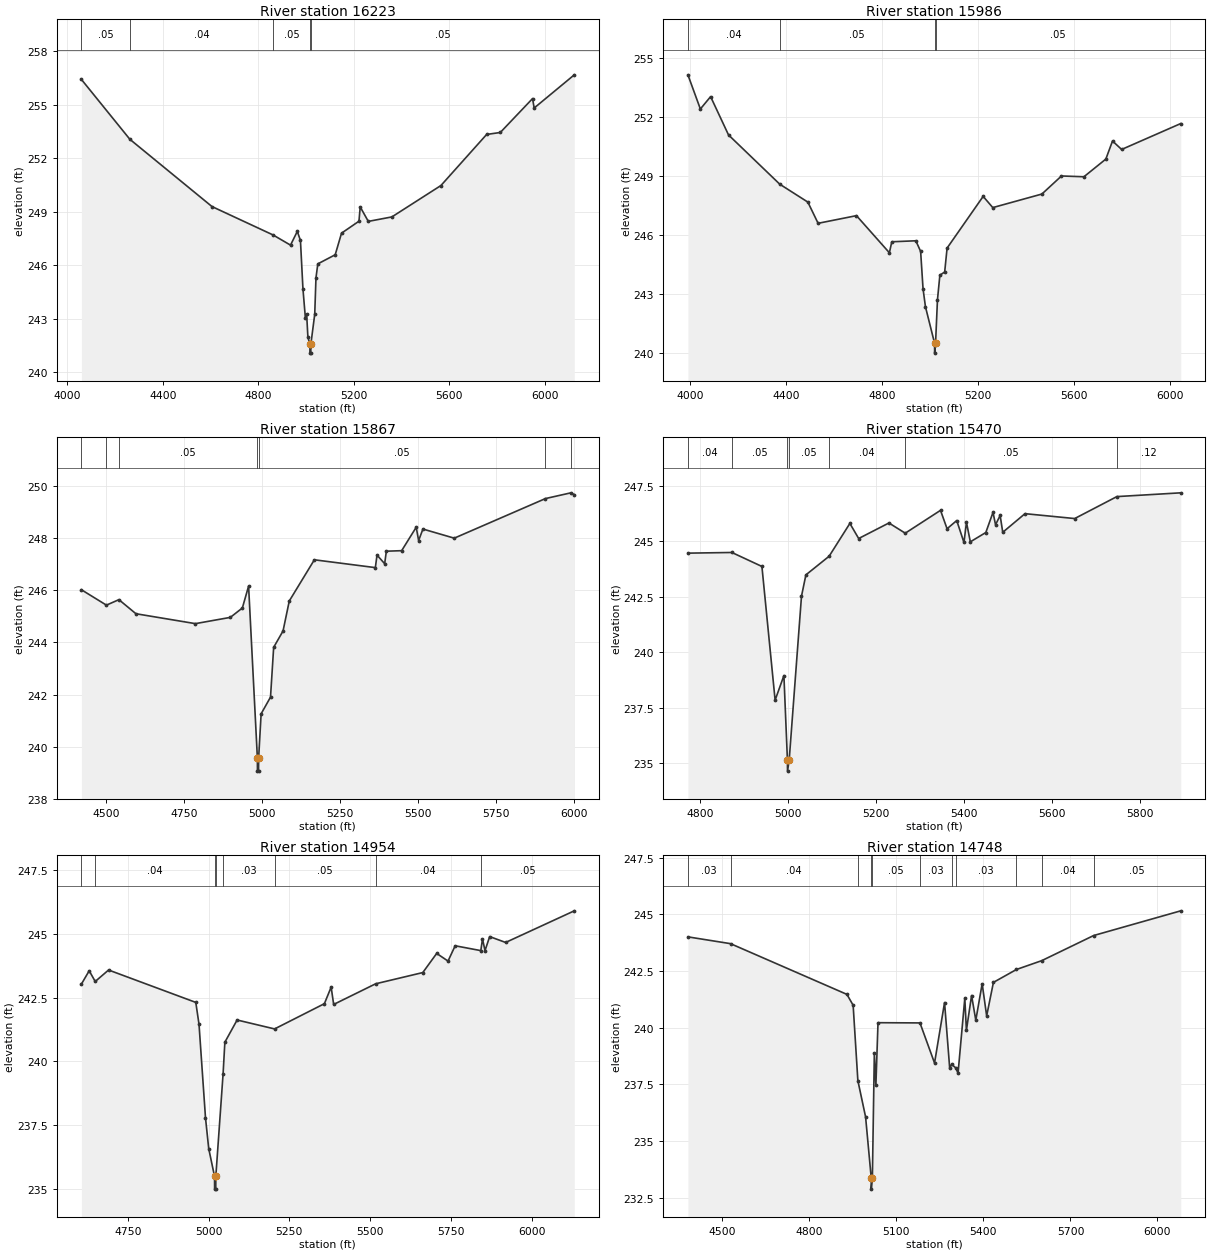
Type RM Length L Ch R = 1,16223,237,237,237
BEGIN DESCRIPTION:
Mapping XS 7e33b93b
END DESCRIPTION:
XS GIS Cut Line= 4
      2474952.14     13533230.85      2474437.61     13532731.69
      2473923.11     13532585.78      2473301.10     13533107.97
#Sta/Elev= 30
  4059.6  256.41  4262.3  253.06  4606.3  249.29  4862.0  247.70  4935.1  247.13
  4963.5  247.90  4976.7  247.39  4987.1  244.69  4997.4  243.04  5002.6  243.27
  5007.9  241.97  5016.3  241.58  5016.5  241.08  5020.0  241.08  5020.3  241.58
  5036.5  243.26  5041.7  245.30  5049.4  246.08  5122.2  246.59  5148.7  247.80
  5221.7  248.47  5226.9  249.27  5260.8  248.46  5359.5  248.71  5565.0  250.47
  5756.3  253.33  5813.5  253.44  5948.6  255.34  5955.3  254.81  6123.4  256.67
#Mann=5,-1,0
  4059.6    0.05       0  4262.3    0.04       0  4862.0    0.05       0
  5016.3    0.05       0  5020.3    0.05       0
Bank Sta=5016.3,5020.3
Exp/Cntr=0.3,0.1

Type RM Length L Ch R = 1,15986,119,119,119
BEGIN DESCRIPTION:
Mapping XS 8494c3c4
END DESCRIPTION:
XS GIS Cut Line= 4
      2475213.66     13532734.53      2474450.80     13532453.29
      2473937.57     13532428.69      2473301.30     13532776.70
#Sta/Elev= 30
  3991.8  254.16  4043.7  252.42  4086.3  253.05  4160.9  251.10  4374.4  248.59
  4491.2  247.68  4533.9  246.60  4693.6  246.99  4830.7  245.10  4840.7  245.66
  4940.8  245.71  4960.8  245.17  4970.8  243.27  4980.9  242.35  5018.9  240.49
  5019.1  239.99  5022.9  240.49  5030.9  242.71  5040.9  243.96  5060.9  244.12
  5071.0  245.34  5221.1  247.97  5261.2  247.40  5465.7  248.09  5547.3  249.01
  5640.7  248.97  5731.9  249.87  5759.7  250.79  5797.7  250.36  6043.9  251.68
#Mann=4,-1,0
  3991.8    0.04       0  4374.4    0.05       0  5018.9    0.05       0
  5022.9    0.05       0
Bank Sta=5018.9,5022.9
Exp/Cntr=0.3,0.1

Type RM Length L Ch R = 1,15867,397,397,397
BEGIN DESCRIPTION:
Mapping XS 6c3f3104
END DESCRIPTION:
XS GIS Cut Line= 3
      2474849.08     13532381.58      2474020.93     13532308.66
      2473322.37     13532579.85
#Sta/Elev= 30
  4421.7  246.02  4501.8  245.43  4541.9  245.64  4596.5  245.10  4787.2  244.72
  4899.2  244.96  4937.8  245.32  4957.8  246.16  4986.0  239.56  4986.2  239.06
  4989.7  239.06  4990.0  239.56  4998.0  241.26  5028.1  241.90  5038.2  243.81
  5068.3  244.44  5088.3  245.59  5168.7  247.17  5364.3  246.87  5369.7  247.35
  5394.2  247.02  5399.6  247.50  5448.7  247.52  5495.4  248.42  5503.1  247.91
  5516.9  248.35  5617.4  248.00  5909.9  249.52  5991.5  249.74  6002.4  249.67
#Mann=7,-1,0
  4421.7    0.05       0  4501.8    0.03       0  4541.9    0.05       0
  4986.0    0.05       0  4990.0    0.05       0  5909.9    0.12       0
  5991.5    0.05       0
Bank Sta=4986,4990
Exp/Cntr=0.3,0.1

Type RM Length L Ch R = 1,15470,516,516,516
BEGIN DESCRIPTION:
Mapping XS ef7e53f0
END DESCRIPTION:
XS GIS Cut Line= 3
      2474413.25     13532031.75      2473979.26     13532038.69
      2473371.57     13532358.40
#Sta/Elev= 30
  4773.1  244.47  4873.1  244.50  4941.4  243.87  4971.4  237.84  4991.4  238.95
  4999.4  235.14  4999.6  234.64  5003.4  235.14  5031.4  242.53  5041.4  243.49
  5094.2  244.33  5141.4  245.81  5161.4  245.13  5230.2  245.83  5267.3  245.37
  5347.5  246.40  5362.4  245.57  5384.4  245.94  5400.8  244.95  5406.5  245.86
  5415.3  244.98  5450.5  245.40  5466.9  246.31  5472.6  245.75  5483.1  246.17
  5489.0  245.41  5539.6  246.25  5652.6  246.03  5748.5  247.02  5893.8  247.19
#Mann=7,-1,0
  4773.1    0.04       0  4873.1    0.05       0  4999.4    0.05       0
  5003.4    0.05       0  5094.2    0.04       0  5267.3    0.05       0
  5748.5    0.12       0
Bank Sta=4999.4,5003.4
Exp/Cntr=0.3,0.1

Type RM Length L Ch R = 1,14954,206,206,206
BEGIN DESCRIPTION:
Mapping XS cb58593d
END DESCRIPTION:
XS GIS Cut Line= 3
      2474619.02     13531566.47      2474004.36     13531570.94
      2473304.78     13532154.51
#Sta/Elev= 30
  4606.5  243.03  4630.5  243.55  4649.2  243.13  4690.5  243.58  4960.5  242.31
  4970.5  241.45  4990.5  237.79  5000.5  236.58  5018.5  235.49  5018.8  234.99
  5022.3  234.99  5022.5  235.49  5045.0  239.51  5050.5  240.75  5088.4  241.62
  5204.4  241.27  5358.6  242.26  5379.5  242.91  5387.3  242.23  5517.3  243.04
  5663.2  243.48  5706.2  244.23  5741.3  243.93  5763.4  244.53  5842.8  244.34
  5848.0  244.80  5855.8  244.34  5870.2  244.89  5919.6  244.66  6132.2  245.90
#Mann=8,-1,0
  4606.5    0.03       0  4649.2    0.04       0  5018.5    0.04       0
  5022.5    0.04       0  5045.0    0.03       0  5204.4    0.05       0
  5517.3    0.04       0  5842.8    0.05       0
Bank Sta=5018.5,5022.5
Exp/Cntr=0.3,0.1

Type RM Length L Ch R = 1,14748,454,454,454
BEGIN DESCRIPTION:
Mapping XS bb519ea2
END DESCRIPTION:
XS GIS Cut Line= 4
      2474721.47     13531363.54      2474194.19     13531377.60
      2473983.26     13531458.45      2473119.24     13531841.30
#Sta/Elev= 30
  4381.8  244.01  4528.7  243.71  4929.8  241.47  4951.2  240.99  4967.5  237.66
  4994.1  236.06  5013.5  233.37  5013.7  232.87  5017.5  233.37  5024.3  238.89
  5029.6  237.46  5036.9  240.22  5181.5  240.21  5231.7  238.44  5266.2  241.11
  5284.0  238.20  5290.4  238.38  5304.3  238.23  5312.7  237.99  5336.0  241.30
  5341.5  239.88  5359.3  241.42  5373.9  240.33  5395.8  241.94  5411.3  240.52
  5434.6  242.00  5514.1  242.57  5601.2  242.96  5780.2  244.07  6080.2  245.16
#Mann=11,-1,0
  4381.8    0.03       0  4528.7    0.04       0  4967.5    0.05       0
  5013.5    0.05       0  5017.5    0.05       0  5181.5    0.03       0
  5290.4    0.05       0  5304.3    0.03       0  5514.1    0.05       0
  5601.2    0.04       0  5780.2    0.05       0
Bank Sta=5013.5,5017.5
Exp/Cntr=0.3,0.1

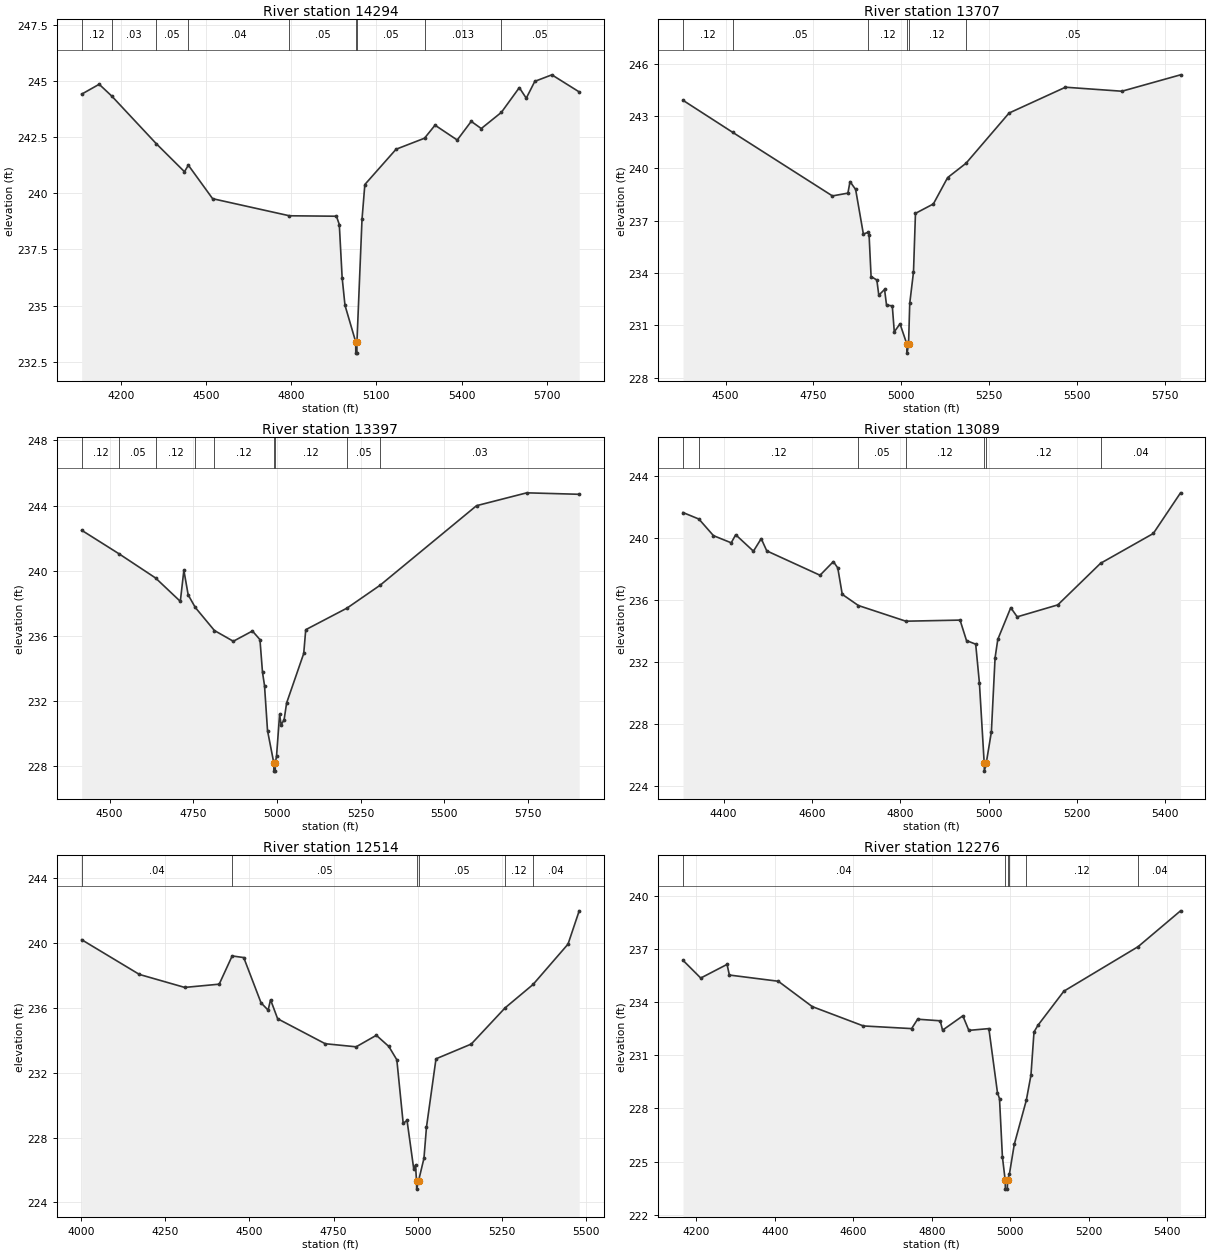
Type RM Length L Ch R = 1,14294,587,587,587
BEGIN DESCRIPTION:
Mapping XS 8b724ca3
END DESCRIPTION:
XS GIS Cut Line= 4
      2474795.35     13531265.12      2474018.42     13531099.89
      2473677.43     13531103.41      2473100.92     13531324.87
#Sta/Elev= 30
  4061.7  244.41  4123.4  244.85  4168.1  244.32  4324.3  242.21  4423.9  240.96
  4437.6  241.25  4523.1  239.76  4793.6  239.00  4959.4  238.98  4969.4  238.61
  4979.4  236.25  4989.4  235.02  5027.2  233.39  5027.5  232.89  5031.3  232.89
  5031.6  233.39  5049.4  238.84  5059.4  240.39  5169.4  241.96  5269.6  242.45
  5306.7  243.03  5384.9  242.37  5434.2  243.20  5469.6  242.88  5540.4  243.60
  5603.6  244.70  5628.1  244.23  5658.2  244.98  5718.3  245.27  5814.6  244.51
#Mann=9,-1,0
  4061.7    0.12       0  4168.1    0.03       0  4324.3    0.05       0
  4437.6    0.04       0  4793.6    0.05       0  5027.2    0.05       0
  5031.6    0.05       0  5269.6   0.013       0  5540.4    0.05       0
Bank Sta=5027.2,5031.6
Exp/Cntr=0.3,0.1

Type RM Length L Ch R = 1,13707,310,310,310
BEGIN DESCRIPTION:
Mapping XS de569fe1
END DESCRIPTION:
XS GIS Cut Line= 4
      2474788.26     13531180.73      2474521.11     13530881.94
      2474208.25     13530716.72      2473548.65     13530657.07
#Sta/Elev= 30
  4378.5  243.90  4519.5  242.07  4804.0  238.42  4848.1  238.58  4854.1  239.24
  4870.1  238.79  4892.1  236.24  4905.6  236.33  4908.4  236.19  4914.1  233.80
  4930.5  233.60  4936.1  232.73  4952.5  233.06  4958.1  232.16  4974.5  232.12
  4980.2  230.63  4996.5  231.09  5016.3  229.91  5016.6  229.41  5020.8  229.91
  5024.2  232.26  5034.9  234.06  5040.5  237.42  5091.5  237.96  5132.1  239.47
  5184.4  240.29  5307.1  243.17  5467.7  244.65  5628.4  244.42  5795.4  245.36
#Mann=6,-1,0
  4378.5    0.12       0  4519.5    0.05       0  4905.6    0.12       0
  5016.3    0.05       0  5020.8    0.12       0  5184.4    0.05       0
Bank Sta=5016.3,5020.8
Exp/Cntr=0.3,0.1

Type RM Length L Ch R = 1,13397,308,308,308
BEGIN DESCRIPTION:
Mapping XS 5fdede70
END DESCRIPTION:
XS GIS Cut Line= 4
      2474855.05     13531075.25      2474696.88     13530709.69
      2474401.59     13530512.83      2473668.41     13530537.39
#Sta/Elev= 30
  4416.6  242.48  4528.5  241.03  4637.3  239.55  4711.4  238.11  4722.0  240.02
  4734.9  238.51  4756.0  237.74  4813.3  236.32  4869.8  235.66  4926.9  236.29
  4949.4  235.76  4957.0  233.75  4963.0  232.94  4972.0  230.17  4990.8  228.18
  4991.1  227.68  4995.0  227.68  4995.3  228.18  4999.0  228.62  5008.1  231.16
  5012.7  230.53  5021.5  230.83  5029.1  231.87  5080.2  234.91  5086.2  236.37
  5209.8  237.70  5308.3  239.10  5596.6  243.99  5746.7  244.78  5903.4  244.69
#Mann=9,-1,0
  4416.6    0.12       0  4528.5    0.05       0  4637.3    0.12       0
  4756.0    0.05       0  4813.3    0.12       0  4990.8    0.05       0
  4995.3    0.12       0  5209.8    0.05       0  5308.3    0.03       0
Bank Sta=4990.8,4995.3
Exp/Cntr=0.3,0.1

Type RM Length L Ch R = 1,13089,575,575,575
BEGIN DESCRIPTION:
Mapping XS 191ae19a
END DESCRIPTION:
XS GIS Cut Line= 4
      2474918.35     13531043.67      2474865.61     13530530.41
      2474675.79     13530273.79      2474514.07     13530031.22
#Sta/Elev= 30
  4308.1  241.65  4344.1  241.23  4377.1  240.16  4417.3  239.70  4427.4  240.22
  4467.6  239.16  4485.2  239.97  4497.8  239.18  4618.4  237.61  4648.6  238.49
  4658.6  238.08  4668.7  236.38  4705.2  235.66  4812.7  234.65  4935.5  234.72
  4950.1  233.40  4970.9  233.17  4979.3  230.68  4990.2  225.49  4990.5  224.99
  4994.7  225.49  5006.4  227.51  5014.8  232.29  5021.0  233.48  5050.3  235.52
  5064.9  234.93  5156.8  235.70  5253.7  238.38  5373.1  240.30  5434.8  242.92
#Mann=7,-1,0
  4308.1    0.05       0  4344.1    0.12       0  4705.2    0.05       0
  4812.7    0.12       0  4990.2    0.05       0  4994.7    0.12       0
  5253.7    0.04       0
Bank Sta=4990.2,4994.7
Exp/Cntr=0.3,0.1

Type RM Length L Ch R = 1,12514,238,238,238
BEGIN DESCRIPTION:
Mapping XS adcad654
END DESCRIPTION:
XS GIS Cut Line= 4
      2475863.99     13530660.48      2475406.98     13530410.88
      2475174.96     13530192.93      2474573.82     13529971.46
#Sta/Elev= 30
  4000.9  240.19  4172.6  238.05  4307.4  237.25  4409.9  237.45  4448.5  239.19
  4482.9  239.09  4534.4  236.30  4555.4  235.85  4562.7  236.49  4583.7  235.32
  4725.3  233.78  4817.2  233.59  4877.3  234.30  4914.5  233.61  4938.2  232.79
  4957.1  228.88  4968.6  229.05  4988.4  226.08  4993.8  226.31  4996.8  225.32
  4997.3  224.82  5002.7  225.32  5018.9  226.72  5026.4  228.64  5054.7  232.85
  5159.6  233.76  5260.2  235.99  5343.3  237.43  5447.4  239.92  5480.6  241.97
#Mann=6,-1,0
  4000.9    0.04       0  4448.5    0.05       0  4996.8    0.05       0
  5002.7    0.05       0  5260.2    0.12       0  5343.3    0.04       0
Bank Sta=4996.8,5002.7
Exp/Cntr=0.3,0.1

Type RM Length L Ch R = 1,12276,193,193,193
BEGIN DESCRIPTION:
Mapping XS 162244f5
END DESCRIPTION:
XS GIS Cut Line= 3
      2475783.11     13530351.12      2475101.14     13529918.74
      2474644.16     13529866.01
#Sta/Elev= 30
  4166.1  236.35  4211.3  235.35  4278.3  236.12  4284.2  235.52  4408.8  235.17
  4495.4  233.74  4625.6  232.65  4748.5  232.50  4763.8  233.03  4821.4  232.94
  4827.3  232.41  4879.0  233.22  4894.3  232.40  4945.3  232.50  4967.2  228.89
  4972.4  228.55  4979.8  225.27  4986.9  223.95  4987.4  223.45  4992.3  223.45
  4992.8  223.95  4997.8  224.32  5010.0  225.97  5040.6  228.45  5052.5  229.87
  5060.3  232.31  5070.4  232.69  5136.4  234.61  5325.5  237.12  5433.6  239.14
#Mann=6,-1,0
  4166.1    0.04       0  4986.9    0.05       0  4992.8    0.04       0
  4997.8    0.05       0  5040.6    0.12       0  5325.5    0.04       0
Bank Sta=4986.9,4992.8
Exp/Cntr=0.3,0.1

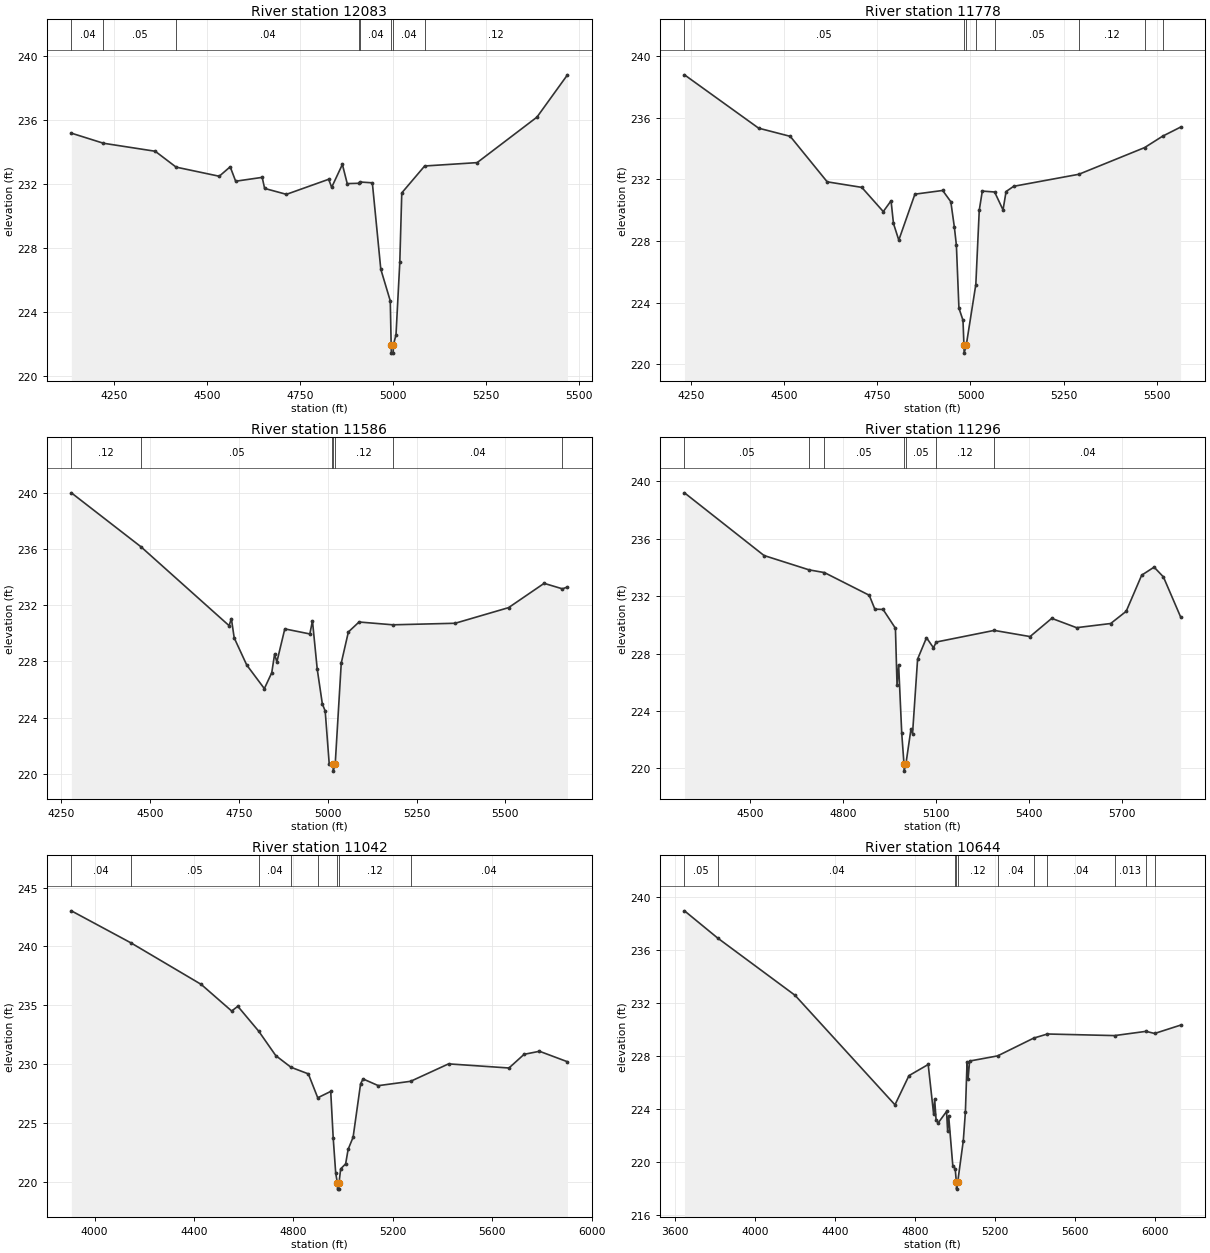
Type RM Length L Ch R = 1,12083,305,305,305
BEGIN DESCRIPTION:
Mapping XS 6f8df0ce
END DESCRIPTION:
XS GIS Cut Line= 4
      2475867.49     13530228.09      2475238.24     13529778.12
      2475020.29     13529700.79      2474693.36     13529732.42
#Sta/Elev= 30
  4134.9  235.18  4221.1  234.55  4360.3  234.05  4416.4  233.06  4532.3  232.49
  4561.8  233.08  4576.5  232.18  4647.8  232.42  4654.3  231.73  4712.9  231.36
  4826.4  232.30  4834.5  231.80  4863.3  233.23  4876.3  232.03  4907.1  232.05
  4910.7  232.13  4943.8  232.08  4966.5  226.69  4992.0  224.71  4994.4  221.95
  4994.9  221.45  4999.8  221.45  5000.3  221.95  5007.4  222.60  5017.6  227.12
  5022.9  231.45  5084.4  233.13  5225.4  233.34  5386.2  236.18  5468.2  238.82
#Mann=8,-1,0
  4134.9    0.04       0  4221.1    0.05       0  4416.4    0.04       0
  4907.1    0.05       0  4910.7    0.04       0  4994.4    0.04       0
  5000.3    0.04       0  5084.4    0.12       0
Bank Sta=4994.4,5000.3
Exp/Cntr=0.3,0.1

Type RM Length L Ch R = 1,11778,192,192,192
BEGIN DESCRIPTION:
Mapping XS 53920fdb
END DESCRIPTION:
XS GIS Cut Line= 4
      2475955.33     13529964.41      2475449.16     13529563.69
      2475305.03     13529500.41      2474784.73     13529602.36
#Sta/Elev= 30
  4231.5  238.78  4430.8  235.32  4515.7  234.79  4615.0  231.84  4708.0  231.48
  4765.7  229.91  4786.6  230.61  4793.1  229.14  4807.4  228.06  4850.7  231.04
  4925.3  231.28  4947.2  230.55  4956.8  228.89  4962.2  227.72  4969.0  223.65
  4979.9  222.86  4982.5  221.23  4983.0  220.73  4988.6  221.23  5014.4  225.18
  5023.6  229.99  5031.8  231.24  5064.9  231.18  5087.5  230.02  5095.7  231.21
  5116.1  231.55  5291.3  232.33  5467.9  234.06  5516.3  234.80  5564.7  235.39
#Mann=8,-1,0
  4231.5    0.05       0  4982.5    0.05       0  4988.6    0.05       0
  5014.4    0.04       0  5064.9    0.05       0  5291.3    0.12       0
  5467.9    0.05       0  5516.3    0.12       0
Bank Sta=4982.5,4988.6
Exp/Cntr=0.3,0.1

Type RM Length L Ch R = 1,11586,290,290,290
BEGIN DESCRIPTION:
Mapping XS a547d17e
END DESCRIPTION:
XS GIS Cut Line= 3
      2476032.67     13529830.82      2475466.74     13529373.86
      2474799.37     13529405.47
#Sta/Elev= 30
  4279.1  239.99  4474.5  236.16  4722.8  230.54  4729.2  231.04  4737.2  229.67
  4772.4  227.74  4822.0  226.06  4842.8  227.19  4850.8  228.51  4857.2  227.96
  4879.5  230.31  4949.9  229.95  4957.3  230.88  4970.7  227.45  4985.1  224.97
  4993.1  224.47  5004.4  220.72  5012.7  220.70  5015.2  220.69  5015.7  220.19
  5021.3  220.69  5038.3  227.88  5058.3  230.09  5088.3  230.80  5183.5  230.60
  5358.6  230.71  5508.8  231.82  5608.9  233.55  5660.4  233.16  5674.6  233.29
#Mann=7,-1,0
  4279.1    0.12       0  4474.5    0.05       0  5012.7    0.12       0
  5015.2    0.05       0  5021.3    0.12       0  5183.5    0.04       0
  5660.4    0.05       0
Bank Sta=5015.2,5021.3
Exp/Cntr=0.3,0.1

Type RM Length L Ch R = 1,11296,254,254,254
BEGIN DESCRIPTION:
Mapping XS 7380da58
END DESCRIPTION:
XS GIS Cut Line= 4
      2476159.23     13529623.42      2475719.84     13529194.58
      2475466.74     13529141.85      2474739.53     13529131.77
#Sta/Elev= 30
  4289.3  239.21  4545.8  234.84  4691.1  233.84  4740.6  233.65  4885.1  232.07
  4903.2  231.10  4929.7  231.08  4969.5  229.77  4974.7  225.80  4979.8  227.23
  4989.9  222.44  4997.1  220.31  4997.6  219.81  5003.3  220.31  5019.6  222.74
  5024.7  222.42  5041.0  227.62  5069.7  229.11  5092.1  228.41  5101.3  228.81
  5288.1  229.62  5403.6  229.19  5473.6  230.46  5553.6  229.81  5663.6  230.10
  5713.6  230.95  5763.6  233.47  5803.6  234.03  5833.6  233.35  5889.1  230.56
#Mann=7,-1,0
  4289.3    0.05       0  4691.1    0.04       0  4740.6    0.05       0
  4997.1    0.05       0  5003.3    0.05       0  5101.3    0.12       0
  5288.1    0.04       0
Bank Sta=4997.1,5003.3
Exp/Cntr=0.3,0.1

Type RM Length L Ch R = 1,11042,398,398,398
BEGIN DESCRIPTION:
Mapping XS 96a56ba9
END DESCRIPTION:
XS GIS Cut Line= 4
      2476612.72     13529240.27      2475832.33     13528941.47
      2475473.77     13528934.44      2474682.62     13529057.98
#Sta/Elev= 30
  3906.9  243.03  4146.4  240.31  4429.1  236.78  4551.6  234.52  4576.3  234.92
  4660.5  232.80  4729.0  230.73  4790.2  229.74  4859.9  229.18  4897.7  227.15
  4949.9  227.69  4959.9  223.73  4969.9  220.76  4976.8  219.89  4977.3  219.39
  4982.5  219.39  4983.0  219.89  4989.9  221.11  5009.9  221.54  5019.9  222.77
  5039.9  223.80  5069.9  228.33  5079.9  228.75  5141.3  228.18  5271.3  228.55
  5423.8  230.03  5666.7  229.68  5727.4  230.84  5789.3  231.10  5901.9  230.21
#Mann=8,-1,0
  3906.9    0.04       0  4146.4    0.05       0  4660.5    0.04       0
  4790.2    0.05       0  4897.7    0.12       0  4976.8    0.05       0
  4983.0    0.12       0  5271.3    0.04       0
Bank Sta=4976.8,4983
Exp/Cntr=0.3,0.1

Type RM Length L Ch R = 1,10644,531,531,531
BEGIN DESCRIPTION:
Mapping XS de89ee91
END DESCRIPTION:
XS GIS Cut Line= 5
      2476918.08     13528506.80      2475783.12     13528505.57
      2475301.52     13528656.73      2475129.26     13528716.49
      2474478.71     13528828.62
#Sta/Elev= 30
  3646.8  238.96  3812.6  236.91  4199.9  232.59  4699.9  224.33  4769.9  226.53
  4866.1  227.37  4893.3  223.63  4898.5  224.76  4905.6  223.18  4916.0  222.96
  4958.0  223.83  4963.4  222.33  4968.6  223.47  4989.4  219.71  5001.1  219.52
  5007.3  218.47  5007.8  217.97  5013.5  218.47  5041.8  221.63  5052.3  223.80
  5060.6  227.58  5065.9  226.31  5073.3  227.63  5213.6  228.02  5394.0  229.36
  5462.7  229.67  5798.5  229.55  5955.9  229.87  5999.0  229.71  6129.0  230.34
#Mann=11,-1,0
  3646.8    0.05       0  3812.6    0.04       0  5001.1    0.12       0
  5007.3    0.04       0  5013.5    0.12       0  5213.6    0.04       0
  5394.0    0.03       0  5462.7    0.04       0  5798.5   0.013       0
  5955.9    0.04       0  5999.0   0.013       0
Bank Sta=5007.3,5013.5
Exp/Cntr=0.3,0.1

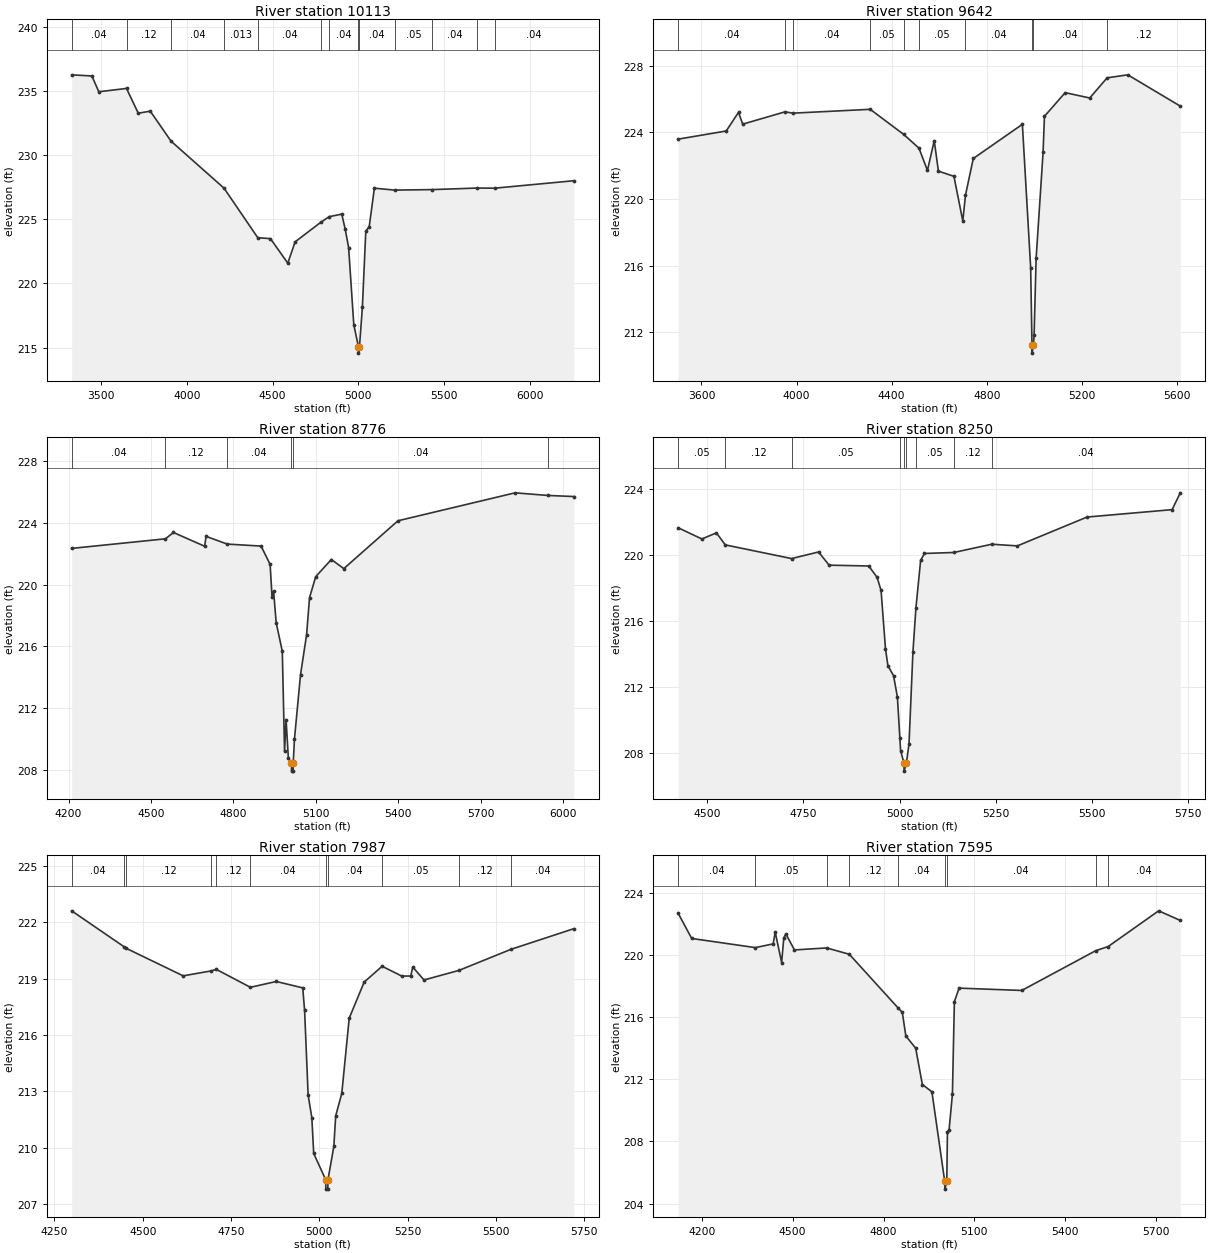
Type RM Length L Ch R = 1,10113,471,471,471
BEGIN DESCRIPTION:
Mapping XS f89772cb
END DESCRIPTION:
XS GIS Cut Line= 4
      2477483.05     13528026.60      2476246.90     13528040.06
      2475974.64     13528133.94      2474573.57     13528083.09
#Sta/Elev= 30
  3329.2  236.25  3447.3  236.16  3487.3  234.93  3648.9  235.19  3717.3  233.26
  3787.3  233.42  3908.5  231.08  4217.1  227.42  4413.8  223.56  4487.3  223.49
  4588.6  221.58  4631.4  223.24  4781.7  224.77  4830.2  225.20  4903.1  225.40
  4923.1  224.23  4943.1  222.79  4973.1  216.80  5000.0  215.07  5000.5  214.57
  5006.3  215.07  5023.2  218.13  5043.2  224.07  5063.2  224.43  5093.2  227.42
  5211.1  227.27  5431.6  227.31  5693.2  227.43  5794.5  227.42  6255.4  228.00
#Mann=13,-1,0
  3329.2    0.04       0  3648.9    0.12       0  3908.5    0.04       0
  4217.1   0.013       0  4413.8    0.04       0  4781.7   0.013       0
  4830.2    0.04       0  5000.0    0.04       0  5006.3    0.04       0
  5211.1    0.05       0  5431.6    0.04       0  5693.2    0.03       0
  5794.5    0.04       0
Bank Sta=5000,5006.3
Exp/Cntr=0.3,0.1

Type RM Length L Ch R = 1,9642,866,866,866
BEGIN DESCRIPTION:
Mapping XS 272d5a0f
END DESCRIPTION:
XS GIS Cut Line= 4
      2477423.12     13527475.82      2476381.45     13527948.91
      2475956.10     13527714.54      2475474.29     13527727.56
#Sta/Elev= 30
  3502.0  223.59  3704.3  224.08  3756.0  225.20  3773.6  224.49  3951.7  225.23
  3984.3  225.15  4309.8  225.38  4450.0  223.88  4514.8  223.05  4550.4  221.71
  4579.0  223.50  4596.5  221.67  4661.8  221.36  4699.1  218.68  4710.4  220.23
  4743.2  222.43  4949.6  224.48  4984.5  215.87  4990.0  211.25  4990.5  210.75
  4996.3  211.25  4998.9  211.83  5007.4  216.43  5036.7  222.80  5042.4  224.96
  5129.5  226.38  5232.9  226.06  5305.9  227.27  5392.9  227.45  5613.7  225.57
#Mann=10,-1,0
  3502.0    0.04       0  3951.7    0.12       0  3984.3    0.04       0
  4309.8    0.05       0  4450.0    0.04       0  4514.8    0.05       0
  4710.4    0.04       0  4990.0    0.04       0  4996.3    0.04       0
  5305.9    0.12       0
Bank Sta=4990,4996.3
Exp/Cntr=0.3,0.1

Type RM Length L Ch R = 1,8776,526,526,526
BEGIN DESCRIPTION:
Mapping XS 5b5c8bbd
END DESCRIPTION:
XS GIS Cut Line= 4
      2477449.19     13527406.37      2476871.90     13527584.33
      2476450.89     13527384.68      2475704.41     13527514.88
#Sta/Elev= 30
  4211.1  222.35  4552.2  222.97  4581.7  223.38  4695.1  222.49  4700.4  223.13
  4777.0  222.63  4900.6  222.50  4933.5  221.31  4940.5  219.18  4946.0  219.59
  4955.6  217.53  4977.8  215.68  4986.0  209.20  4991.5  211.26  4999.9  208.76
  5011.0  208.42  5011.5  207.92  5017.0  207.92  5017.5  208.42  5022.0  209.99
  5044.2  214.18  5066.3  216.76  5076.9  219.16  5099.5  220.52  5156.2  221.63
  5201.7  221.04  5398.8  224.14  5825.1  225.95  5943.9  225.78  6038.9  225.71
#Mann=6,-1,0
  4211.1    0.04       0  4552.2    0.12       0  4777.0    0.04       0
  5011.0    0.04       0  5017.5    0.04       0  5943.9    0.05       0
Bank Sta=5011,5017.5
Exp/Cntr=0.3,0.1

Type RM Length L Ch R = 1,8250,263,263,263
BEGIN DESCRIPTION:
Mapping XS 97b1aa85
END DESCRIPTION:
XS GIS Cut Line= 3
      2477466.48     13527358.62      2476989.09     13527093.88
      2476233.86     13527011.41
#Sta/Elev= 30
  4424.2  221.64  4486.0  220.96  4523.8  221.33  4546.9  220.60  4719.2  219.77
  4789.3  220.17  4816.8  219.37  4919.8  219.32  4941.5  218.63  4951.8  217.84
  4963.3  214.30  4969.6  213.27  4984.3  212.66  4994.3  211.37  5000.6  208.90
  5002.6  208.12  5011.2  207.37  5011.7  206.87  5017.7  207.37  5024.5  208.52
  5034.6  214.07  5042.4  216.76  5054.7  219.66  5064.7  220.08  5141.0  220.14
  5239.6  220.64  5306.2  220.54  5487.2  222.29  5708.5  222.74  5729.8  223.76
#Mann=9,-1,0
  4424.2    0.05       0  4546.9    0.12       0  4719.2    0.05       0
  5000.6    0.04       0  5011.2    0.05       0  5017.7    0.04       0
  5042.4    0.05       0  5141.0    0.12       0  5239.6    0.04       0
Bank Sta=5011.2,5017.7
Exp/Cntr=0.3,0.1

Type RM Length L Ch R = 1,7987,392,392,392
BEGIN DESCRIPTION:
Mapping XS 4458d22c
END DESCRIPTION:
XS GIS Cut Line= 3
      2477722.61     13527297.88      2477214.78     13526928.95
      2476463.95     13526668.54
#Sta/Elev= 30
  4298.7  222.61  4447.8  220.69  4452.7  220.62  4614.6  219.15  4692.9  219.41
  4708.9  219.49  4805.0  218.54  4878.2  218.85  4953.2  218.51  4958.5  217.31
  4968.5  212.81  4979.0  211.60  4984.3  209.70  5018.2  208.30  5018.7  207.80
  5024.2  207.80  5024.7  208.30  5041.3  210.07  5046.6  211.70  5063.8  212.89
  5084.9  216.90  5127.3  218.82  5178.1  219.66  5233.4  219.14  5259.2  219.14
  5264.9  219.62  5296.6  218.93  5395.7  219.44  5542.8  220.56  5721.1  221.66
#Mann=11,-1,0
  4298.7    0.04       0  4447.8    0.05       0  4452.7    0.12       0
  4692.9    0.04       0  4708.9    0.12       0  4805.0    0.04       0
  5018.2    0.04       0  5024.7    0.04       0  5178.1    0.05       0
  5395.7    0.12       0  5542.8    0.04       0
Bank Sta=5018.2,5024.7
Exp/Cntr=0.3,0.1

Type RM Length L Ch R = 1,7595,294,294,294
BEGIN DESCRIPTION:
Mapping XS ccc9b32b
END DESCRIPTION:
XS GIS Cut Line= 4
      2477991.70     13527141.63      2477466.52     13526638.15
      2477223.46     13526525.30      2476563.76     13526464.54
#Sta/Elev= 30
  4121.8  222.71  4166.6  221.08  4376.7  220.49  4435.5  220.73  4442.4  221.48
  4463.6  219.53  4470.7  221.12  4477.6  221.37  4505.9  220.34  4612.3  220.47
  4687.1  220.06  4848.2  216.60  4862.0  216.32  4873.6  214.80  4906.1  214.01
  4928.2  211.67  4959.7  211.20  5002.0  205.43  5002.5  204.93  5008.8  205.43
  5011.0  208.63  5016.5  208.76  5027.4  211.05  5033.9  217.01  5049.5  217.88
  5256.4  217.73  5500.3  220.29  5541.7  220.56  5708.3  222.86  5779.8  222.24
#Mann=9,-1,0
  4121.8    0.04       0  4376.7    0.05       0  4612.3    0.04       0
  4687.1    0.12       0  4848.2    0.04       0  5002.0    0.04       0
  5008.8    0.04       0  5500.3    0.05       0  5541.7    0.04       0
Bank Sta=5002,5008.8
Exp/Cntr=0.3,0.1