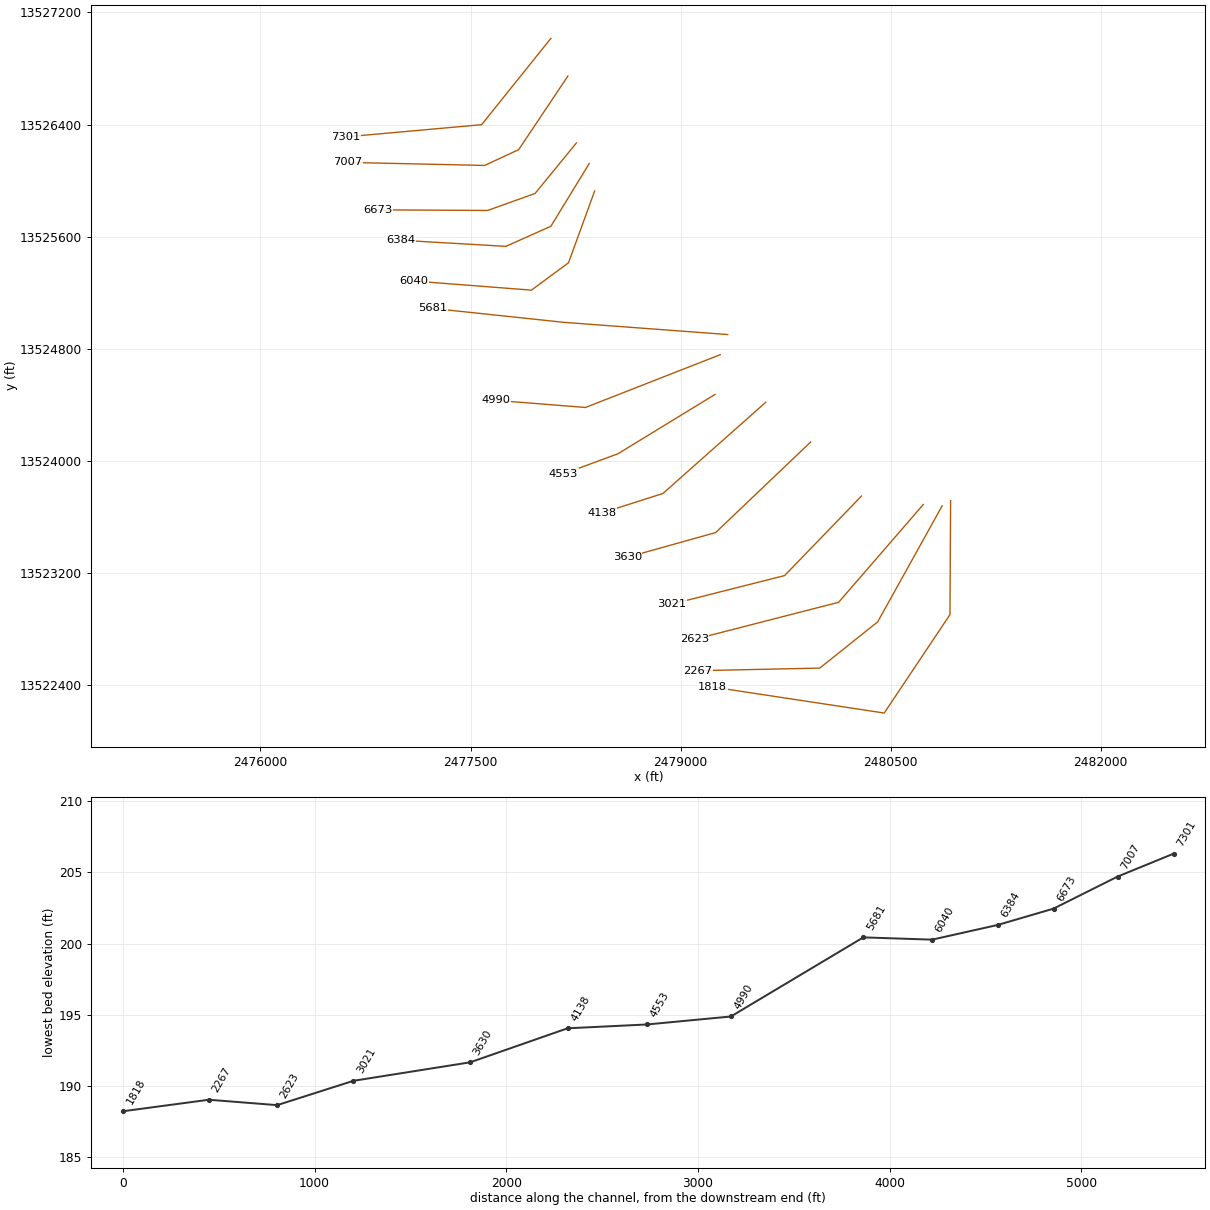
HEC-RAS study TRIB 10 TO FIFTEENMILE CREEK.prj: TRIB 10 TO FIFTEENMILE CREEK Base Level Engineering

--- TRIB 10 TO FIFTEENMILE CREEK.g01 (geometry) --- (continued)

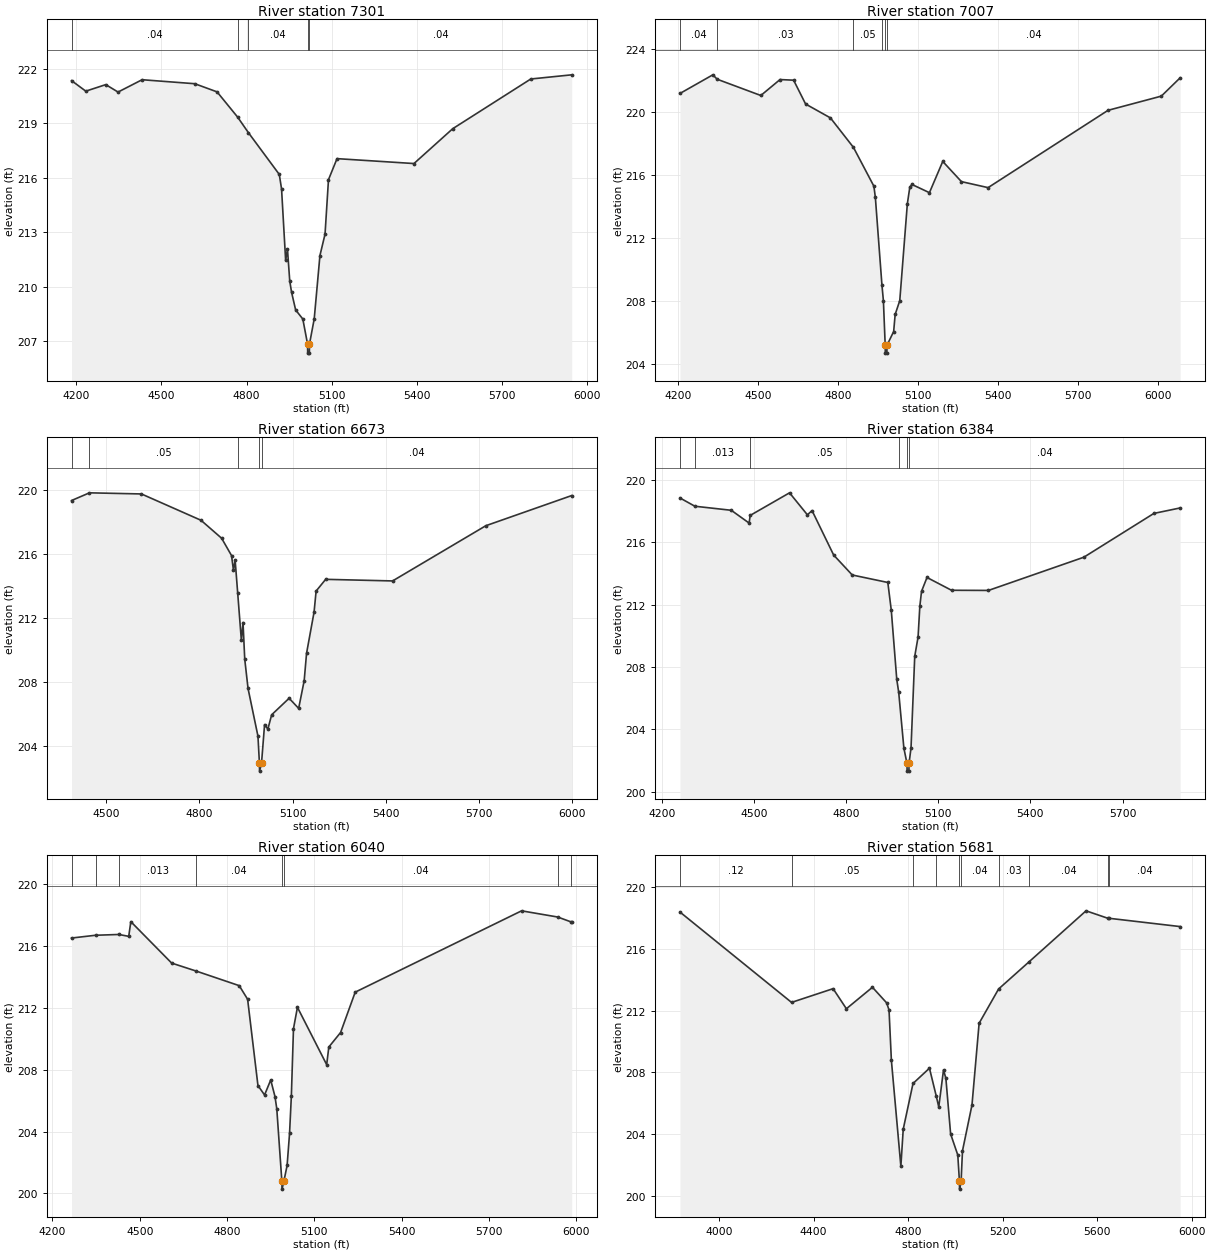
Type RM Length L Ch R = 1,7301,294,294,294
BEGIN DESCRIPTION:
Mapping XS 5110a6b8
END DESCRIPTION:
XS GIS Cut Line= 3
      2478074.16     13527015.75      2477579.36     13526399.44
      2476611.51     13526312.63
#Sta/Elev= 30
  4183.5  221.35  4233.7  220.77  4304.1  221.13  4347.3  220.72  4432.1  221.40
  4617.7  221.18  4696.2  220.73  4768.6  219.34  4806.7  218.48  4915.4  216.18
  4923.4  215.38  4937.8  211.44  4944.2  212.07  4952.2  210.31  4958.6  209.69
  4973.0  208.71  4998.3  208.21  5015.0  206.83  5015.5  206.33  5021.3  206.33
  5021.8  206.83  5038.5  208.22  5058.6  211.71  5076.6  212.89  5088.7  215.89
  5118.8  217.05  5389.9  216.78  5526.4  218.70  5801.5  221.44  5945.6  221.67
#Mann=5,-1,0
  4183.5    0.04       0  4768.6    0.05       0  4806.7    0.04       0
  5015.0    0.04       0  5021.8    0.04       0
Bank Sta=5015,5021.8
Exp/Cntr=0.3,0.1

Type RM Length L Ch R = 1,7007,334,334,334
BEGIN DESCRIPTION:
Mapping XS c5fb2fe7
END DESCRIPTION:
XS GIS Cut Line= 4
      2478195.68     13526746.65      2477844.12     13526221.48
      2477601.06     13526108.64      2476624.46     13526130.34
#Sta/Elev= 30
  4205.8  221.17  4329.0  222.35  4345.4  222.07  4509.1  221.04  4581.2  222.05
  4632.2  222.01  4677.1  220.50  4770.3  219.62  4856.7  217.75  4933.4  215.29
  4938.9  214.58  4963.7  209.00  4969.1  208.03  4975.8  205.21  4976.3  204.71
  4982.1  204.71  4982.6  205.21  5007.6  206.08  5013.2  207.16  5030.5  208.04
  5058.9  214.17  5068.3  215.24  5076.3  215.40  5141.8  214.88  5191.8  216.86
  5261.9  215.58  5361.9  215.20  5812.0  220.10  6012.0  221.00  6082.6  222.16
#Mann=6,-1,0
  4205.8    0.04       0  4345.4    0.03       0  4856.7    0.05       0
  4963.7    0.04       0  4975.8    0.04       0  4982.6    0.04       0
Bank Sta=4975.8,4982.6
Exp/Cntr=0.3,0.1

Type RM Length L Ch R = 1,6673,289,289,289
BEGIN DESCRIPTION:
Mapping XS b239f0d0
END DESCRIPTION:
XS GIS Cut Line= 4
      2478256.45     13526269.23      2477961.31     13525908.98
      2477622.77     13525787.46      2476838.58     13525791.79
#Sta/Elev= 30
  4388.9  219.32  4446.5  219.80  4613.8  219.73  4805.5  218.09  4871.9  216.97
  4903.8  215.89  4910.0  214.97  4915.3  215.62  4923.5  213.58  4935.4  210.61
  4940.7  211.72  4946.3  209.43  4956.9  207.61  4988.8  204.64  4993.5  202.96
  4994.0  202.46  5000.3  202.96  5010.1  205.36  5020.7  205.08  5032.9  205.97
  5089.1  207.00  5119.8  206.37  5137.6  208.10  5145.2  209.80  5169.4  212.37
  5176.0  213.68  5206.7  214.41  5422.1  214.31  5722.1  217.75  5998.5  219.63
#Mann=5,-1,0
  4388.9   0.013       0  4446.5    0.05       0  4923.5    0.04       0
  4993.5    0.04       0  5000.3    0.04       0
Bank Sta=4993.5,5000.3
Exp/Cntr=0.3,0.1

Type RM Length L Ch R = 1,6384,344,344,344
BEGIN DESCRIPTION:
Mapping XS 76c3e359
END DESCRIPTION:
XS GIS Cut Line= 4
      2478347.58     13526121.63      2478074.16     13525674.61
      2477752.97     13525531.38      2477002.11     13525574.78
#Sta/Elev= 30
  4259.6  218.84  4308.0  218.31  4426.5  218.05  4484.6  217.23  4488.0  217.72
  4616.1  219.17  4674.2  217.76  4689.4  218.03  4759.7  215.18  4820.2  213.90
  4936.0  213.42  4947.3  211.63  4965.1  207.20  4971.4  206.38  4988.3  202.79
  4998.3  201.82  4998.8  201.32  5004.6  201.32  5005.1  201.82  5011.5  202.81
  5023.6  208.68  5034.5  209.93  5040.2  211.90  5045.7  212.85  5063.5  213.74
  5143.3  212.92  5263.5  212.91  5574.0  215.04  5802.0  217.85  5887.4  218.20
#Mann=6,-1,0
  4259.6    0.04       0  4308.0   0.013       0  4488.0    0.05       0
  4971.4    0.04       0  4998.3    0.04       0  5005.1    0.04       0
Bank Sta=4998.3,5005.1
Exp/Cntr=0.3,0.1

Type RM Length L Ch R = 1,6040,359,359,359
BEGIN DESCRIPTION:
Mapping XS d4349aeb
END DESCRIPTION:
XS GIS Cut Line= 4
      2478386.66     13525926.35      2478200.02     13525414.19
      2477935.27     13525218.88      2477093.28     13525283.98
#Sta/Elev= 30
  4265.7  216.52  4348.2  216.70  4428.1  216.75  4462.2  216.63  4469.4  217.58
  4609.7  214.90  4694.5  214.38  4841.9  213.44  4870.7  212.56  4906.2  206.98
  4928.9  206.37  4950.1  207.34  4964.7  206.27  4970.9  205.48  4988.4  200.78
  4988.9  200.28  4995.2  200.78  5006.4  201.81  5014.8  203.88  5021.0  206.30
  5028.3  210.66  5041.9  212.04  5142.4  208.33  5149.7  209.47  5190.2  210.41
  5240.4  213.02  5812.1  218.28  5936.1  217.88  5982.6  217.56  5984.3  217.56
#Mann=8,-1,0
  4265.7    0.04       0  4348.2    0.05       0  4428.1   0.013       0
  4694.5    0.04       0  4988.4    0.04       0  4995.2    0.04       0
  5936.1    0.03       0  5982.6    0.04       0
Bank Sta=4988.4,4995.2
Exp/Cntr=0.3,0.1

Type RM Length L Ch R = 1,5681,691,691,691
BEGIN DESCRIPTION:
Mapping XS cd1ec42d
END DESCRIPTION:
XS GIS Cut Line= 3
      2479337.23     13524902.04      2478169.64     13524988.84
      2477228.92     13525088.55
#Sta/Elev= 30
  3834.7  218.38  4306.8  212.53  4482.7  213.42  4538.9  212.12  4649.2  213.51
  4709.3  212.50  4719.4  212.04  4729.4  208.77  4769.5  201.92  4779.5  204.32
  4820.9  207.28  4890.5  208.27  4919.7  206.44  4929.9  205.76  4950.0  208.16
  4960.0  207.61  4980.1  204.01  5010.4  202.65  5017.4  200.94  5017.9  200.44
  5024.4  200.94  5030.3  202.92  5070.5  205.89  5100.7  211.18  5183.2  213.40
  5312.2  215.16  5553.2  218.46  5647.1  217.97  5649.1  217.98  5951.5  217.44
#Mann=10,-1,0
  3834.7    0.12       0  4306.8    0.05       0  4820.9   0.013       0
  4919.7    0.04       0  5017.4    0.04       0  5024.4    0.04       0
  5183.2    0.03       0  5312.2    0.04       0  5647.1    0.03       0
  5649.1    0.04       0
Bank Sta=5017.4,5024.4
Exp/Cntr=0.3,0.1

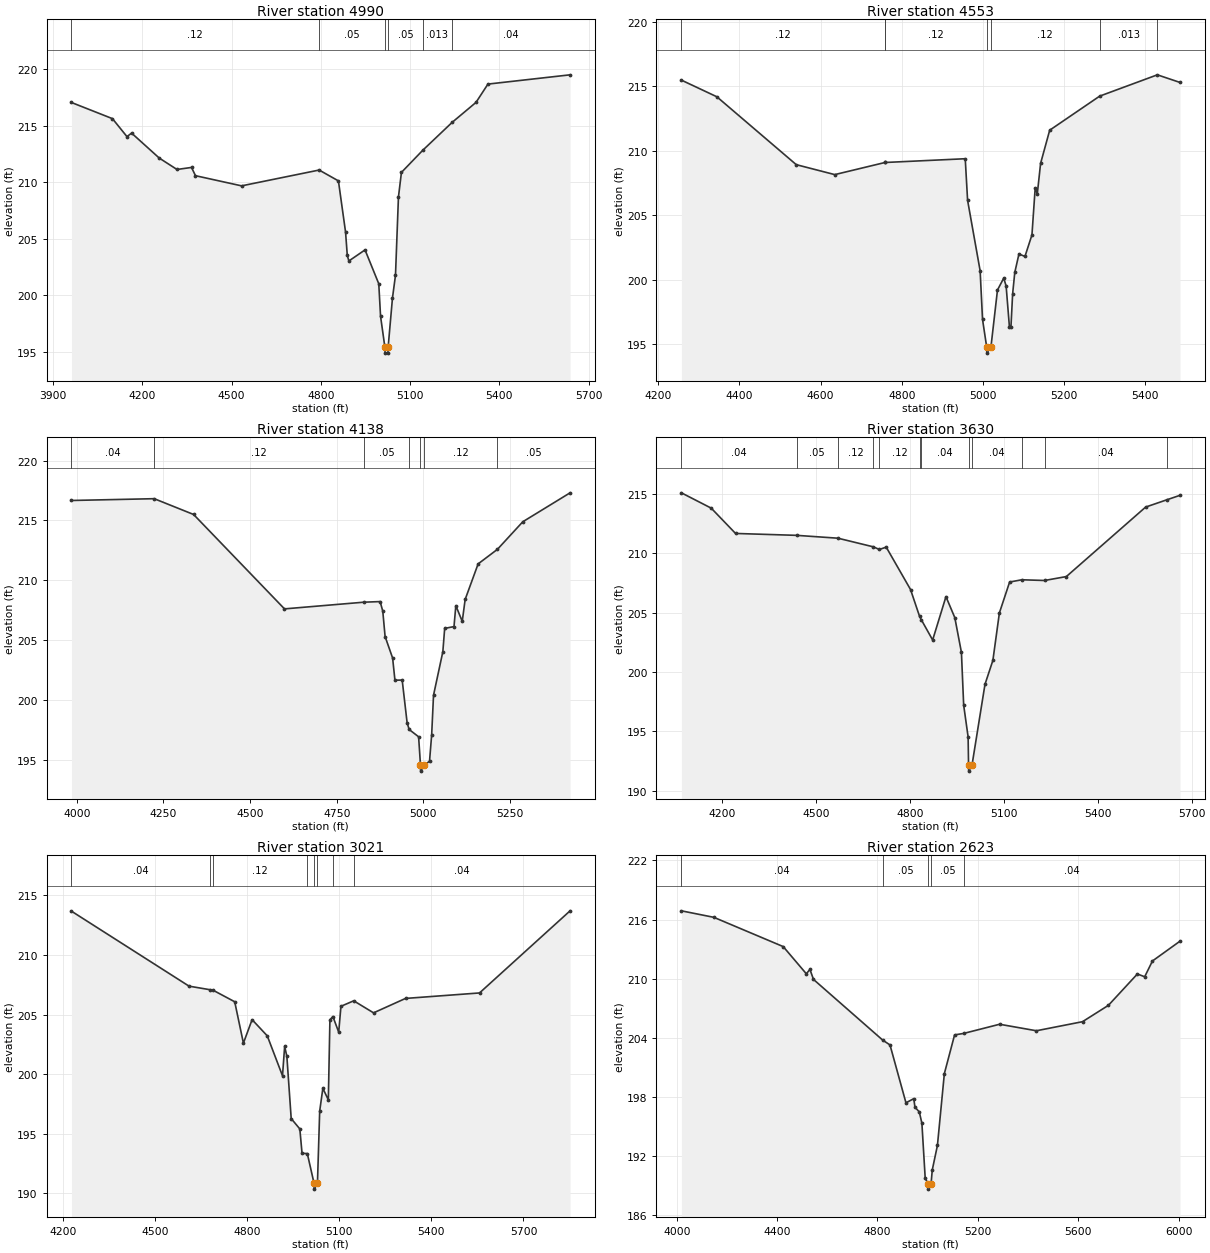
Type RM Length L Ch R = 1,4990,437,437,437
BEGIN DESCRIPTION:
Mapping XS 23e603b6
END DESCRIPTION:
XS GIS Cut Line= 3
      2479283.33     13524758.15      2478321.02     13524381.59
      2477679.72     13524432.71
#Sta/Elev= 30
  3961.3  217.07  4099.1  215.64  4147.9  214.05  4163.5  214.36  4256.5  212.15
  4316.1  211.14  4365.0  211.32  4378.3  210.59  4533.3  209.69  4794.2  211.09
  4859.0  210.13  4883.0  205.60  4888.8  203.53  4894.2  203.04  4948.5  204.02
  4994.7  201.02  5000.7  198.14  5015.4  195.38  5015.9  194.88  5025.6  194.88
  5026.1  195.38  5040.8  199.77  5050.9  201.77  5060.9  208.71  5070.9  210.88
  5142.6  212.84  5241.4  215.31  5321.7  217.08  5361.8  218.70  5638.0  219.52
#Mann=6,-1,0
  3961.3    0.12       0  4794.2    0.05       0  5015.4    0.05       0
  5026.1    0.05       0  5142.6   0.013       0  5241.4    0.04       0
Bank Sta=5015.4,5026.1
Exp/Cntr=0.3,0.1

Type RM Length L Ch R = 1,4553,415,415,415
BEGIN DESCRIPTION:
Mapping XS 3f6300db
END DESCRIPTION:
XS GIS Cut Line= 3
      2479246.13     13524474.56      2478553.46     13524051.52
      2478162.94     13523907.40
#Sta/Elev= 30
  4257.4  215.47  4344.7  214.18  4540.3  208.92  4635.1  208.15  4759.0  209.09
  4759.7  209.09  4956.4  209.38  4962.2  206.16  4993.1  200.70  4999.0  196.93
  5009.1  194.82  5009.6  194.32  5019.8  194.82  5035.8  199.21  5051.2  200.13
  5057.1  199.52  5065.2  196.36  5069.0  196.36  5073.1  198.90  5078.4  200.57
  5088.7  202.00  5103.5  201.81  5120.7  203.48  5128.6  207.08  5133.9  206.67
  5142.0  209.02  5164.4  211.59  5287.5  214.23  5429.5  215.88  5485.3  215.29
#Mann=7,-1,0
  4257.4    0.12       0  4759.0    0.05       0  4759.7    0.12       0
  5009.1    0.05       0  5019.8    0.12       0  5287.5   0.013       0
  5429.5    0.04       0
Bank Sta=5009.1,5019.8
Exp/Cntr=0.3,0.1

Type RM Length L Ch R = 1,4138,508,508,508
BEGIN DESCRIPTION:
Mapping XS ef6d8173
END DESCRIPTION:
XS GIS Cut Line= 3
      2479608.75     13524418.77      2478874.24     13523767.93
      2478438.65     13523628.92
#Sta/Elev= 30
  3984.7  216.67  4223.4  216.82  4337.1  215.50  4599.3  207.61  4828.3  208.17
  4875.3  208.22  4882.9  207.42  4889.6  205.30  4911.3  203.50  4918.0  201.65
  4938.9  201.66  4953.1  198.10  4959.0  197.53  4986.3  196.92  4991.7  194.55
  4992.2  194.05  5002.4  194.55  5017.8  194.88  5024.0  197.10  5029.3  200.39
  5056.2  204.03  5061.5  205.98  5088.4  206.13  5093.7  207.88  5112.2  206.57
  5120.6  208.40  5158.0  211.37  5213.8  212.59  5286.8  214.89  5423.3  217.31
#Mann=7,-1,0
  3984.7    0.04       0  4223.4    0.12       0  4828.3    0.05       0
  4959.0    0.12       0  4991.7    0.05       0  5002.4    0.12       0
  5213.8    0.05       0
Bank Sta=4991.7,5002.4
Exp/Cntr=0.3,0.1

Type RM Length L Ch R = 1,3630,609,609,609
BEGIN DESCRIPTION:
Mapping XS e73efd45
END DESCRIPTION:
XS GIS Cut Line= 3
      2479929.58     13524135.23      2479250.80     13523489.00
      2478619.29     13523312.55
#Sta/Elev= 30
  4070.0  215.09  4165.3  213.80  4243.0  211.67  4438.1  211.51  4570.2  211.27
  4683.6  210.54  4702.4  210.32  4724.3  210.52  4802.0  206.95  4831.0  204.68
  4836.8  204.39  4872.7  202.70  4915.2  206.35  4943.5  204.58  4964.6  201.66
  4971.8  197.21  4986.0  194.54  4987.4  192.16  4987.9  191.66  4998.4  192.16
  5039.9  198.97  5065.1  200.98  5085.9  204.98  5118.6  207.58  5157.7  207.77
  5230.1  207.71  5299.8  208.04  5553.1  213.89  5621.6  214.51  5662.9  214.88
#Mann=12,-1,0
  4070.0    0.04       0  4438.1    0.05       0  4570.2    0.12       0
  4683.6    0.05       0  4702.4    0.12       0  4831.0    0.05       0
  4836.8    0.04       0  4987.4    0.04       0  4998.4    0.04       0
  5157.7    0.05       0  5230.1    0.04       0  5621.6    0.05       0
Bank Sta=4987.4,4998.4
Exp/Cntr=0.3,0.1

Type RM Length L Ch R = 1,3021,398,398,398
BEGIN DESCRIPTION:
Mapping XS 5480c0fb
END DESCRIPTION:
XS GIS Cut Line= 3
      2480292.15     13523749.33      2479743.59     13523182.17
      2478934.69     13522977.62
#Sta/Elev= 30
  4228.4  213.68  4611.2  207.39  4679.6  207.09  4690.1  207.04  4759.9  206.08
  4788.2  202.61  4816.5  204.58  4865.9  203.22  4915.5  199.87  4922.5  202.34
  4929.7  201.50  4943.8  196.28  4971.9  195.41  4979.1  193.37  4996.3  193.34
  5018.1  190.86  5018.6  190.36  5029.3  190.86  5036.6  196.91  5046.9  198.82
  5064.7  197.85  5069.9  204.57  5079.6  204.84  5098.5  203.53  5105.8  205.70
  5147.4  206.16  5212.0  205.15  5316.0  206.36  5557.0  206.82  5851.8  213.71
#Mann=8,-1,0
  4228.4    0.04       0  4679.6    0.05       0  4690.1    0.12       0
  4996.3    0.04       0  5018.1    0.04       0  5029.3    0.04       0
  5079.6    0.12       0  5147.4    0.04       0
Bank Sta=5018.1,5029.3
Exp/Cntr=0.3,0.1

Type RM Length L Ch R = 1,2623,356,356,356
BEGIN DESCRIPTION:
Mapping XS 57c96659
END DESCRIPTION:
XS GIS Cut Line= 3
      2480733.82     13523688.92      2480129.45     13522991.56
      2479098.69     13522726.91
#Sta/Elev= 30
  4018.6  216.89  4148.0  216.23  4424.4  213.26  4516.5  210.50  4530.8  210.95
  4545.0  209.93  4820.9  203.77  4849.9  203.28  4913.5  197.41  4944.6  197.83
  4949.4  196.96  4966.6  196.49  4977.0  195.34  4990.2  189.76  5002.3  189.15
  5002.8  188.65  5013.5  189.15  5018.3  190.59  5038.9  193.08  5066.5  200.37
  5107.3  204.30  5143.6  204.45  5286.7  205.38  5433.3  204.72  5617.1  205.64
  5720.3  207.30  5835.7  210.48  5864.9  210.20  5895.8  211.80  6005.6  213.81
#Mann=5,-1,0
  4018.6    0.04       0  4820.9    0.05       0  5002.3    0.05       0
  5013.5    0.05       0  5143.6    0.04       0
Bank Sta=5002.3,5013.5
Exp/Cntr=0.3,0.1

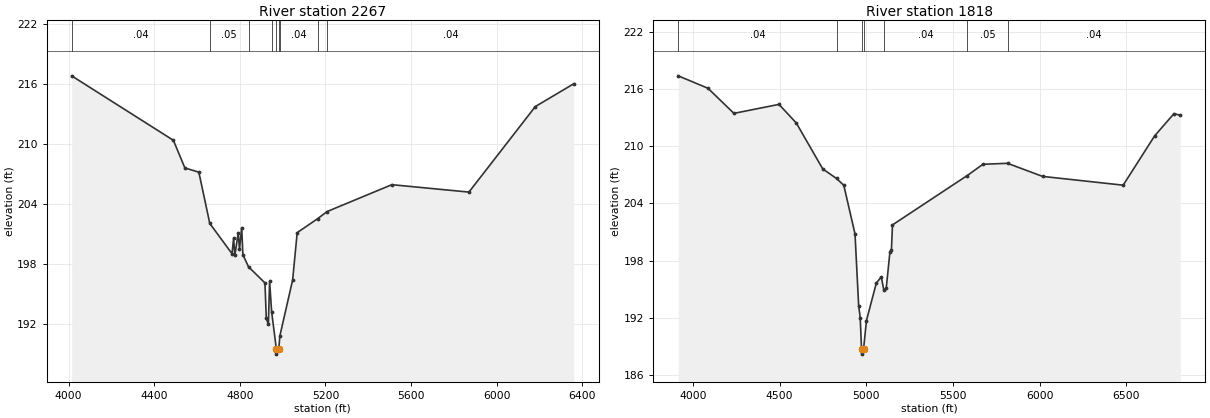
Type RM Length L Ch R = 1,2267,449,449,449
BEGIN DESCRIPTION:
Mapping XS be2776e4
END DESCRIPTION:
XS GIS Cut Line= 4
      2480868.64     13523679.63      2480408.38     13522852.10
      2479994.63     13522522.02      2479125.32     13522503.43
#Sta/Elev= 30
  4014.7  216.82  4490.0  210.38  4543.7  207.62  4608.9  207.20  4660.0  202.08
  4763.8  199.06  4771.3  200.61  4777.0  198.90  4793.0  201.13  4798.8  199.51
  4809.0  201.65  4814.8  198.95  4840.9  197.75  4917.7  196.14  4924.0  192.59
  4933.7  192.00  4939.4  196.30  4949.0  193.25  4971.0  189.53  4971.5  189.03
  4982.3  189.53  4987.4  190.85  5047.1  196.44  5068.3  201.16  5163.6  202.55
  5208.3  203.27  5510.5  205.95  5870.6  205.21  6180.7  213.75  6360.4  216.03
#Mann=9,-1,0
  4014.7    0.04       0  4660.0    0.05       0  4840.9    0.04       0
  4949.0    0.05       0  4971.0    0.04       0  4982.3    0.05       0
  4987.4    0.04       0  5163.6    0.05       0  5208.3    0.04       0
Bank Sta=4971,4982.3
Exp/Cntr=0.3,0.1

Type RM Length L Ch R = 1,1818,0,0,0
BEGIN DESCRIPTION:
Mapping XS 389f35b1
END DESCRIPTION:
XS GIS Cut Line= 4
      2480929.06     13523716.83      2480924.41     13522903.24
      2480454.87     13522201.25      2479228.81     13522387.01
#Sta/Elev= 30
  3914.4  217.36  4086.2  216.06  4236.2  213.43  4496.2  214.37  4596.2  212.42
  4748.9  207.61  4828.4  206.61  4870.3  205.90  4935.1  200.80  4956.1  193.30
  4965.1  192.02  4972.8  188.72  4973.3  188.22  4984.2  188.72  5001.2  191.74
  5058.2  195.67  5086.8  196.30  5101.3  194.92  5115.3  195.13  5136.3  198.87
  5145.3  199.14  5151.3  201.75  5582.8  206.92  5673.6  208.10  5815.4  208.20
  6017.4  206.83  6482.7  205.91  6664.7  211.08  6776.0  213.40  6812.6  213.23
#Mann=7,-1,0
  3914.4    0.04       0  4828.4    0.05       0  4972.8    0.05       0
  4984.2    0.05       0  5101.3    0.04       0  5582.8    0.05       0
  5815.4    0.04       0
Bank Sta=4972.8,4984.2
Exp/Cntr=0.3,0.1

Chan Stop Cuts=-1