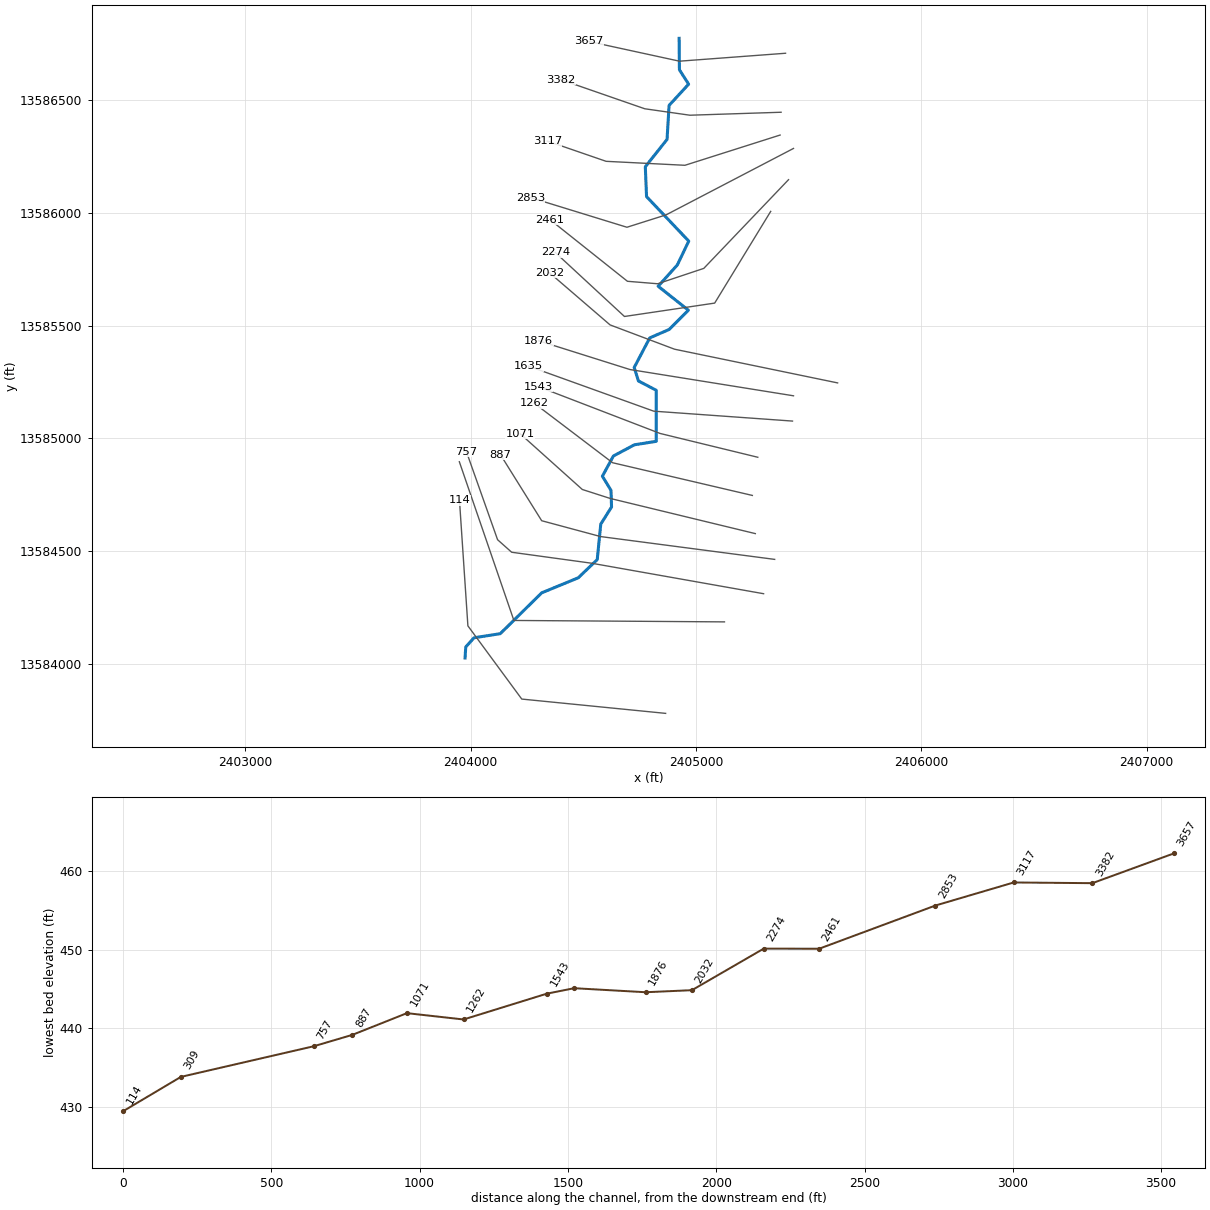
--- TRIB 10 TO SALT CREEK.prj (project) ---

Proj Title=TRIB 10 TO SALT CREEK Base Level Engineering
Current Plan=p01
Default Exp/Contr=0.3,0.1
English Units
Geom File=g01
Flow File=f01
Plan File=p01
BEGIN DESCRIPTION:
TRIB 10 TO SALT CREEK
END DESCRIPTION:

--- TRIB 10 TO SALT CREEK.p01 (plan) ---

Plan Title=Multiple Run
Short Identifier=Multiple
Geom File=g01
Flow File=f01
Subcritical Flow
K Sum by GR= 0
Std Step Tol= 0.01
Critical Tol= 0.01
Num of Std Step Trials= 20
Max Error Tol= 0.3
Flow Tol Ratio= 0.001
Split Flow NTrial= 30
Split Flow Tol= 0.02
Split Flow Ratio= 0.02
Log Output Level= 0
Friction Slope Method= 1
Unsteady Friction Slope Method= 2
Unsteady Bridges Friction Slope Method= 1
Parabolic Critical Depth
Global Vel Dist=  1 , 1 , 1
Global Log Level= 0
CheckData=True
Encroach Param= -1, 0, 0, 0
BEGIN DESCRIPTION:
Multiple Run
END DESCRIPTION:

--- TRIB 10 TO SALT CREEK.f01 (steady flow) ---

Flow Title=Multiple
Number of Profiles=7
Profile Names=10-year,25-year,50-year,1pct_min,100-year,1pct_plu,500-year
River Rch & RM= TRIB 10 TO SALT ,Reach-1,3657
     525     853    1153     757    1510    3014    2564
Boundary for River Rch & Prof#=TRIB 10 TO SALT ,Reach-1,1
Up Type=0
Dn Type=3
Dn Slope=0.005
Boundary for River Rch & Prof#=TRIB 10 TO SALT ,Reach-1,2
Up Type=0
Dn Type=3
Dn Slope=0.005
Boundary for River Rch & Prof#=TRIB 10 TO SALT ,Reach-1,3
Up Type=0
Dn Type=3
Dn Slope=0.005
Boundary for River Rch & Prof#=TRIB 10 TO SALT ,Reach-1,4
Up Type=0
Dn Type=3
Dn Slope=0.005
Boundary for River Rch & Prof#=TRIB 10 TO SALT ,Reach-1,5
Up Type=0
Dn Type=3
Dn Slope=0.005
Boundary for River Rch & Prof#=TRIB 10 TO SALT ,Reach-1,6
Up Type=0
Dn Type=3
Dn Slope=0.005
Boundary for River Rch & Prof#=TRIB 10 TO SALT ,Reach-1,7
Up Type=0
Dn Type=3
Dn Slope=0.005

--- TRIB 10 TO SALT CREEK.g01 (geometry) ---

Geom Title=Existing Conditions

River Reach=TRIB 10 TO SALT ,Reach-1
Reach XY= 30
      2404925.00     13586775.00      2404926.35     13586635.41
      2404967.20     13586571.59      2404880.50     13586477.45
      2404871.44     13586326.47      2404774.94     13586205.01
      2404780.45     13586072.55      2404967.72     13585875.09
      2404916.84     13585768.95      2404832.00     13585674.78
      2404966.12     13585568.47      2404881.07     13585483.17
      2404794.62     13585445.47      2404725.68     13585314.25
      2404744.37     13585254.57      2404823.35     13585213.17
      2404823.50     13584986.53      2404726.64     13584971.15
      2404633.43     13584921.49      2404584.40     13584831.67
      2404622.63     13584769.11      2404625.09     13584695.10
      2404577.27     13584619.06      2404561.64     13584461.66
      2404477.31     13584380.83      2404315.32     13584314.24
      2404131.17     13584132.86      2404014.90     13584114.74
      2403978.12     13584074.01      2403975.00     13584025.00

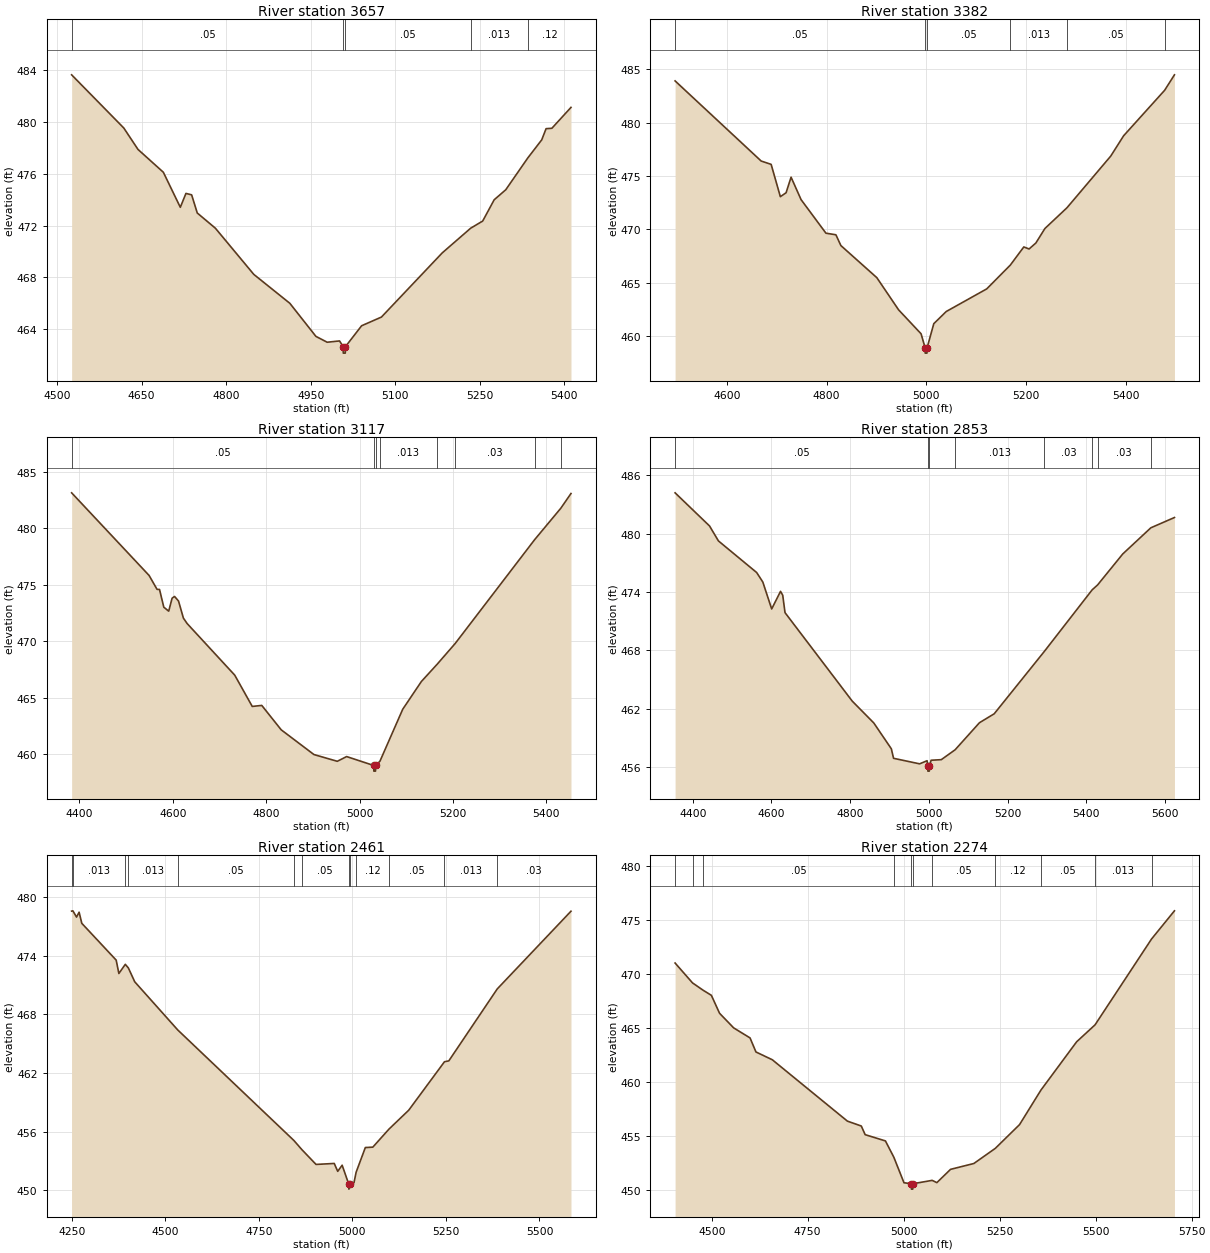
Type RM Length L Ch R = 1,3657,275,275,275
BEGIN DESCRIPTION:
Mapping XS 092d4aaa
END DESCRIPTION:
XS GIS Cut Line= 3
      2405397.38     13586708.80      2404926.63     13586673.60
      2404521.85     13586761.60
#Sta/Elev= 30
  4525.8  483.62  4618.4  479.52  4643.6  477.87  4688.6  476.11  4718.7  473.41
  4728.7  474.48  4738.8  474.37  4748.8  472.97  4780.9  471.80  4849.1  468.24
  4913.1  466.01  4959.4  463.46  4979.4  463.01  5001.3  463.11  5007.8  462.67
  5008.0  462.17  5011.5  462.17  5011.8  462.67  5040.5  464.28  5075.7  464.95
  5183.7  469.90  5234.1  471.80  5255.4  472.35  5275.8  473.99  5296.3  474.76
  5335.4  477.21  5360.2  478.61  5367.9  479.47  5378.2  479.50  5412.1  481.11
#Mann=5,-1,0
  4525.8    0.05       0  5007.8    0.05       0  5011.8    0.05       0
  5234.1   0.013       0  5335.4    0.12       0
Bank Sta=5007.8,5011.8
Exp/Cntr=0.3,0.1

Type RM Length L Ch R = 1,3382,265,265,265
BEGIN DESCRIPTION:
Mapping XS 7c3595f1
END DESCRIPTION:
XS GIS Cut Line= 4
      2405377.66     13586447.00      2404972.83     13586433.80
      2404772.63     13586462.40      2404399.35     13586591.95
#Sta/Elev= 30
  4495.8  483.91  4668.6  476.40  4688.6  476.09  4707.1  473.06  4718.6  473.43
  4728.6  474.89  4748.6  472.79  4798.6  469.64  4818.6  469.49  4828.6  468.48
  4900.8  465.47  4944.4  462.46  4989.6  460.21  4997.7  458.90  4997.9  458.40
  5001.4  458.40  5001.7  458.90  5015.1  461.16  5040.1  462.30  5121.4  464.42
  5168.7  466.65  5195.8  468.35  5206.4  468.16  5220.0  468.72  5238.2  470.08
  5282.4  472.02  5370.4  476.87  5396.2  478.77  5478.5  483.03  5498.2  484.48
#Mann=6,-1,0
  4495.8    0.05       0  4997.7    0.05       0  5001.7    0.05       0
  5168.7   0.013       0  5282.4    0.05       0  5478.5    0.12       0
Bank Sta=4997.7,5001.7
Exp/Cntr=0.3,0.1

Type RM Length L Ch R = 1,3117,264,264,264
BEGIN DESCRIPTION:
Mapping XS fafa1c9e
END DESCRIPTION:
XS GIS Cut Line= 4
      2405373.23     13586345.80      2404950.83     13586211.60
      2404601.03     13586229.20      2404339.66     13586319.25
#Sta/Elev= 30
  4383.2  483.14  4549.2  475.82  4566.2  474.59  4571.5  474.58  4580.7  473.01
  4591.2  472.66  4598.5  473.81  4603.7  473.96  4612.2  473.56  4622.7  472.04
  4630.7  471.56  4732.7  466.99  4770.2  464.22  4790.6  464.31  4832.2  462.15
  4902.3  459.96  4952.4  459.36  4972.4  459.78  5030.5  458.99  5030.7  458.49
  5034.2  458.49  5034.5  458.99  5043.8  459.37  5092.6  463.97  5132.6  466.43
  5166.0  467.94  5204.9  469.79  5375.4  479.00  5431.4  481.78  5453.1  483.08
#Mann=8,-1,0
  4383.2    0.05       0  5030.5    0.05       0  5034.5    0.05       0
  5043.8   0.013       0  5166.0    0.05       0  5204.9    0.03       0
  5375.4    0.12       0  5431.4    0.05       0
Bank Sta=5030.5,5034.5
Exp/Cntr=0.3,0.1

Type RM Length L Ch R = 1,2853,392,392,392
BEGIN DESCRIPTION:
Mapping XS 592379cd
END DESCRIPTION:
XS GIS Cut Line= 4
      2405432.62     13586286.39      2404867.23     13585991.60
      2404693.43     13585936.60      2404264.40     13586068.61
#Sta/Elev= 30
  4355.3  484.21  4442.8  480.80  4465.4  479.26  4562.5  476.01  4578.2  475.03
  4600.7  472.26  4623.2  474.07  4628.8  473.67  4634.6  471.88  4805.5  462.77
  4860.1  460.53  4904.7  457.87  4910.4  456.89  4976.6  456.32  4995.6  456.64
  4997.4  456.07  4997.6  455.57  5001.1  455.57  5001.4  456.07  5005.8  456.69
  5031.7  456.75  5066.9  457.77  5128.6  460.55  5166.1  461.47  5293.9  467.91
  5415.1  474.23  5428.8  474.73  5492.8  477.92  5564.1  480.61  5624.1  481.67
#Mann=8,-1,0
  4355.3    0.05       0  4997.4    0.05       0  5001.4    0.05       0
  5066.9   0.013       0  5293.9    0.03       0  5415.1    0.05       0
  5428.8    0.03       0  5564.1    0.05       0
Bank Sta=4997.4,5001.4
Exp/Cntr=0.3,0.1

Type RM Length L Ch R = 1,2461,187,187,187
BEGIN DESCRIPTION:
Mapping XS 3cfa8e45
END DESCRIPTION:
XS GIS Cut Line= 5
      2405410.61     13586147.78      2405034.43     13585754.00
      2404829.83     13585685.80      2404695.63     13585696.80
      2404351.34     13585970.92
#Sta/Elev= 30
  4249.3  478.58  4252.6  478.61  4262.4  477.97  4269.3  478.47  4276.5  477.33
  4368.4  473.56  4375.6  472.19  4392.8  473.13  4401.1  472.75  4418.0  471.34
  4532.9  466.41  4843.6  455.08  4864.5  454.16  4902.7  452.63  4951.4  452.73
  4960.7  451.92  4972.5  452.55  4990.3  450.60  4990.5  450.10  4994.3  450.60
  5004.1  450.75  5009.9  451.83  5034.5  454.36  5054.5  454.40  5097.5  456.24
  5150.4  458.18  5246.1  463.15  5257.7  463.24  5387.2  470.61  5584.3  478.57
#Mann=13,-1,0
  4249.3    0.05       0  4252.6   0.013       0  4392.8    0.05       0
  4401.1   0.013       0  4532.9    0.05       0  4843.6    0.12       0
  4864.5    0.05       0  4990.3    0.05       0  4994.3    0.05       0
  5009.9    0.12       0  5097.5    0.05       0  5246.1   0.013       0
  5387.2    0.03       0
Bank Sta=4990.3,4994.3
Exp/Cntr=0.3,0.1

Type RM Length L Ch R = 1,2274,242,242,242
BEGIN DESCRIPTION:
TRIB 10 TO SALT CREEK 5.0
END DESCRIPTION:
XS GIS Cut Line= 4
      2405331.44     13586007.02      2405082.83     13585600.00
      2404682.43     13585540.60      2404375.02     13585824.98
#Sta/Elev= 30
  4404.7  471.03  4450.1  469.19  4477.4  468.52  4499.2  468.04  4520.5  466.38
  4557.2  465.03  4599.9  464.10  4615.3  462.80  4657.9  462.08  4853.5  456.40
  4889.6  455.95  4899.7  455.15  4952.5  454.57  4974.4  453.06  5000.8  450.70
  5020.0  450.61  5020.2  450.11  5023.7  450.11  5024.0  450.61  5074.2  450.92
  5086.4  450.71  5122.1  451.94  5182.7  452.48  5238.6  453.88  5301.8  456.08
  5357.6  459.28  5450.4  463.74  5498.4  465.31  5645.5  473.25  5705.2  475.86
#Mann=11,-1,0
  4404.7    0.05       0  4450.1   0.013       0  4477.4    0.05       0
  4974.4    0.12       0  5020.0    0.05       0  5024.0    0.12       0
  5074.2    0.05       0  5238.6    0.12       0  5357.6    0.05       0
  5498.4   0.013       0  5645.5    0.03       0
Bank Sta=5020,5024
Exp/Cntr=0.3,0.1

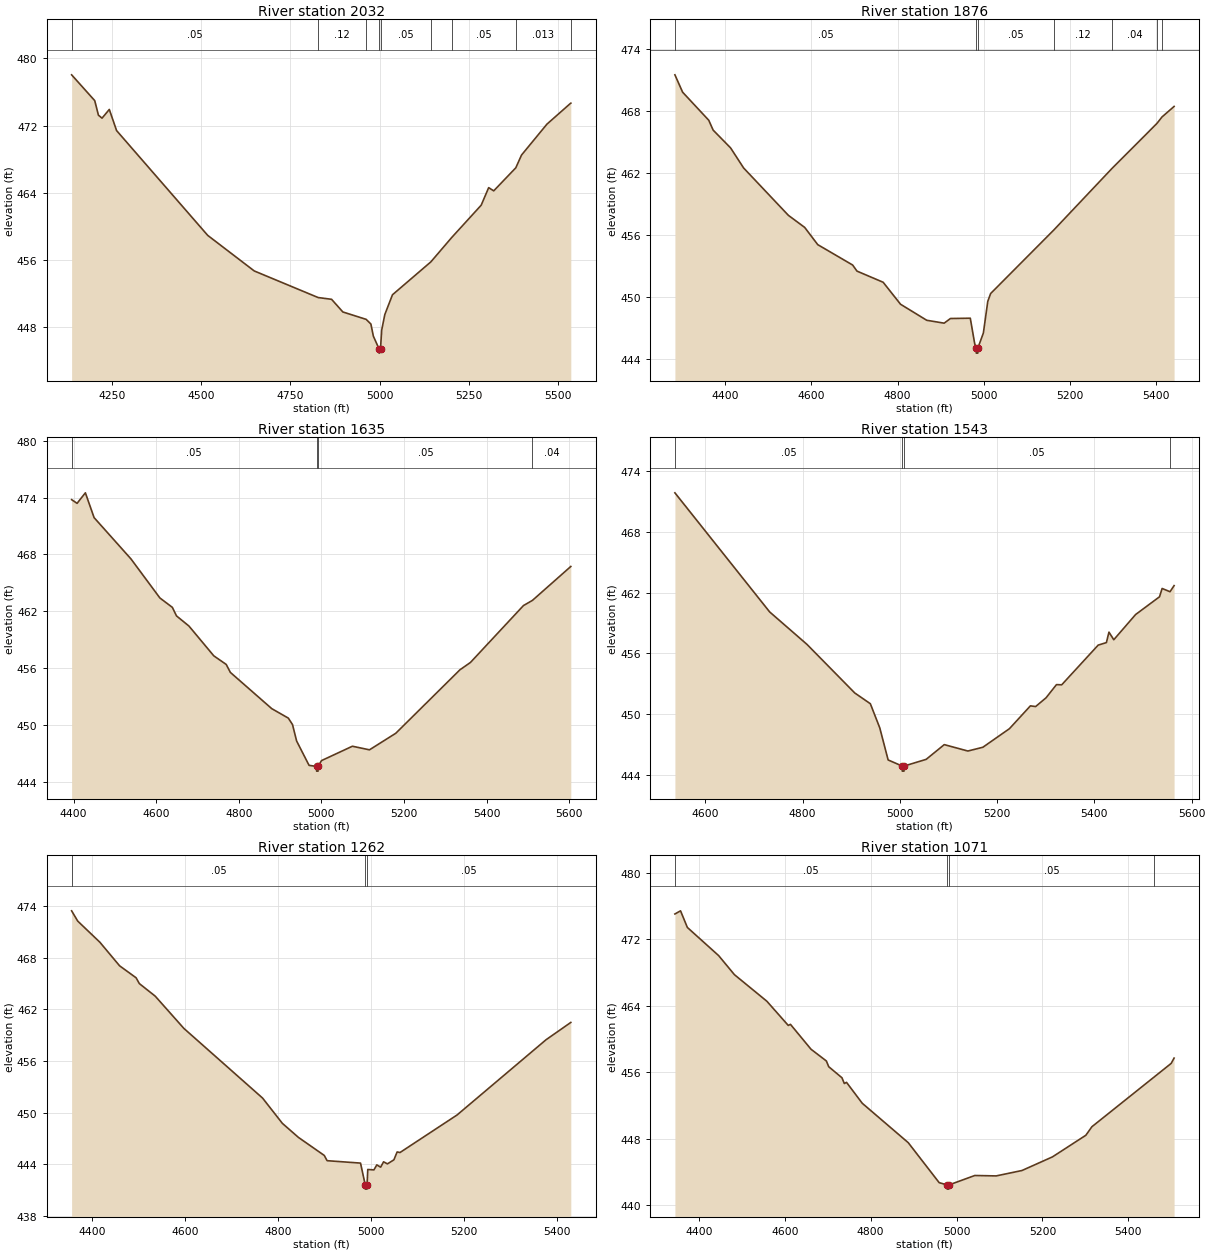
Type RM Length L Ch R = 1,2032,156,156,156
BEGIN DESCRIPTION:
Mapping XS 2023b58c
END DESCRIPTION:
XS GIS Cut Line= 4
      2405628.43     13585245.80      2404904.63     13585395.40
      2404618.63     13585503.20      2404350.20     13585734.23
#Sta/Elev= 30
  4137.2  478.05  4202.0  474.97  4212.3  473.24  4222.4  472.88  4242.8  473.92
  4263.2  471.40  4518.5  458.90  4649.1  454.65  4828.1  451.48  4865.7  451.27
  4897.3  449.76  4962.5  448.88  4975.9  448.32  4982.8  446.87  4998.8  445.35
  4999.0  444.85  5002.8  445.35  5006.1  447.59  5014.8  449.44  5036.3  451.81
  5144.0  455.74  5202.1  458.63  5285.0  462.50  5305.9  464.59  5320.1  464.21
  5382.0  466.96  5398.0  468.48  5469.3  472.17  5535.9  474.67  5536.1  474.67
#Mann=9,-1,0
  4137.2    0.05       0  4828.1    0.12       0  4962.5    0.05       0
  4998.8    0.05       0  5002.8    0.05       0  5144.0    0.12       0
  5202.1    0.05       0  5382.0   0.013       0  5535.9    0.03       0
Bank Sta=4998.8,5002.8
Exp/Cntr=0.3,0.1

Type RM Length L Ch R = 1,1876,241,241,241
BEGIN DESCRIPTION:
Mapping XS e797241d
END DESCRIPTION:
XS GIS Cut Line= 3
      2405432.66     13585188.59      2404706.63     13585305.20
      2404301.80     13585432.81
#Sta/Elev= 30
  4282.8  471.53  4300.7  469.85  4361.5  467.13  4371.6  466.18  4412.1  464.46
  4442.5  462.51  4546.4  457.93  4584.3  456.76  4614.7  455.09  4695.7  453.12
  4705.8  452.53  4766.6  451.45  4807.1  449.32  4867.9  447.77  4908.4  447.49
  4922.9  447.94  4969.1  447.97  4979.3  445.51  4982.8  445.09  4983.1  444.59
  4986.6  444.59  4986.8  445.09  4999.5  446.54  5009.7  449.60  5016.4  450.36
  5163.4  456.52  5298.6  462.48  5402.6  466.82  5414.5  467.45  5442.6  468.47
#Mann=7,-1,0
  4282.8    0.05       0  4982.8    0.05       0  4986.8    0.05       0
  5163.4    0.12       0  5298.6    0.04       0  5402.6    0.05       0
  5414.5   0.013       0
Bank Sta=4982.8,4986.8
Exp/Cntr=0.3,0.1

Type RM Length L Ch R = 1,1635,92,92,92
BEGIN DESCRIPTION:
Mapping XS 7bbd2d50
END DESCRIPTION:
XS GIS Cut Line= 3
      2405428.20     13585076.40      2404812.23     13585120.40
      2404256.43     13585320.31
#Sta/Elev= 30
  4395.4  473.78  4408.6  473.39  4428.7  474.50  4449.8  471.88  4539.0  467.52
  4609.1  463.39  4639.2  462.40  4649.2  461.50  4679.3  460.43  4739.5  457.28
  4769.6  456.37  4779.6  455.53  4879.8  451.70  4919.9  450.70  4930.0  450.02
  4940.0  448.28  4970.1  445.71  4988.1  445.60  4988.4  445.10  4991.9  445.10
  4992.1  445.60  5000.1  446.21  5075.0  447.73  5116.3  447.35  5180.0  449.10
  5335.4  455.81  5360.7  456.58  5489.0  462.59  5510.8  463.14  5603.6  466.72
#Mann=4,-1,0
  4395.4    0.05       0  4988.1    0.05       0  4992.1    0.05       0
  5510.8    0.04       0
Bank Sta=4988.1,4992.1
Exp/Cntr=0.3,0.1

Type RM Length L Ch R = 1,1543,281,281,281
BEGIN DESCRIPTION:
Mapping XS e3b16b40
END DESCRIPTION:
XS GIS Cut Line= 3
      2405274.22     13584915.80      2404840.83     13585021.40
      2404299.27     13585229.69
#Sta/Elev= 30
  4537.6  471.82  4732.4  460.09  4809.2  456.89  4907.3  452.11  4939.4  451.05
  4958.8  448.67  4976.0  445.51  5004.8  444.91  5005.1  444.41  5008.6  444.41
  5008.8  444.91  5054.2  445.57  5091.4  447.02  5139.9  446.39  5170.7  446.76
  5225.4  448.59  5268.5  450.84  5279.2  450.77  5300.6  451.63  5322.1  452.93
  5332.8  452.91  5407.8  456.82  5424.7  457.07  5430.0  458.10  5439.9  457.35
  5484.7  459.83  5533.9  461.58  5539.3  462.40  5555.5  462.08  5563.9  462.68
#Mann=4,-1,0
  4537.6    0.05       0  5004.8    0.05       0  5008.8    0.05       0
  5555.5    0.04       0
Bank Sta=5004.8,5008.8
Exp/Cntr=0.3,0.1

Type RM Length L Ch R = 1,1262,191,191,191
BEGIN DESCRIPTION:
Mapping XS c0636952
END DESCRIPTION:
XS GIS Cut Line= 3
      2405250.05     13584746.40      2404629.63     13584891.60
      2404282.01     13585155.62
#Sta/Elev= 30
  4356.1  473.43  4369.2  472.24  4416.8  469.79  4459.3  467.05  4494.8  465.66
  4501.7  464.99  4535.9  463.53  4597.5  459.79  4766.9  451.70  4809.4  448.77
  4844.0  447.14  4899.5  445.05  4905.6  444.44  4977.5  444.16  4987.6  441.64
  4987.8  441.14  4991.3  441.14  4991.6  441.64  4993.1  443.42  5006.3  443.37
  5012.5  443.95  5020.8  443.69  5027.1  444.31  5035.4  444.07  5049.3  444.54
  5056.2  445.45  5062.5  445.39  5185.1  449.74  5376.5  458.47  5429.8  460.48
#Mann=3,-1,0
  4356.1    0.05       0  4987.6    0.05       0  4991.6    0.05       0
Bank Sta=4987.6,4991.6
Exp/Cntr=0.3,0.1

Type RM Length L Ch R = 1,1071,184,184,184
BEGIN DESCRIPTION:
Mapping XS 325e4e42
END DESCRIPTION:
XS GIS Cut Line= 4
      2405263.19     13584577.01      2404618.63     13584733.20
      2404495.43     13584772.80      2404219.92     13585019.89
#Sta/Elev= 30
  4344.1  475.05  4357.2  475.43  4373.1  473.43  4446.0  470.04  4482.7  467.75
  4558.3  464.55  4608.1  461.64  4613.2  461.77  4661.2  458.77  4696.9  457.36
  4702.4  456.67  4733.2  455.34  4738.7  454.65  4743.8  454.79  4780.5  452.27
  4887.6  447.53  4959.6  442.72  4978.2  442.44  4978.4  441.94  4981.9  441.94
  4982.2  442.44  5042.6  443.58  5092.4  443.53  5152.5  444.18  5223.5  445.82
  5301.2  448.42  5315.4  449.45  5461.0  455.46  5500.0  457.07  5506.8  457.71
#Mann=4,-1,0
  4344.1    0.05       0  4978.2    0.05       0  4982.2    0.05       0
  5461.0    0.04       0
Bank Sta=4978.2,4982.2
Exp/Cntr=0.3,0.1

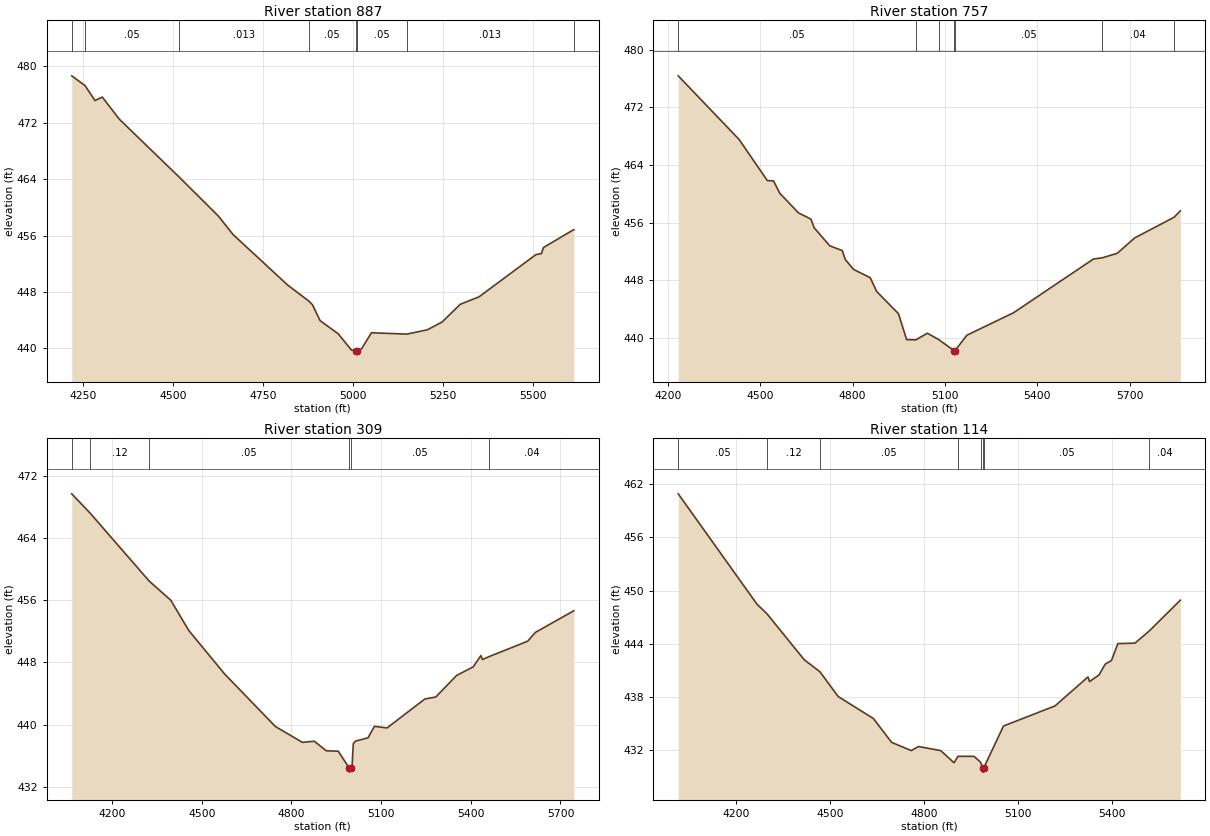
Type RM Length L Ch R = 1,887,130,130,130
BEGIN DESCRIPTION:
Mapping XS ce1b46b7
END DESCRIPTION:
XS GIS Cut Line= 4
      2405349.06     13584462.60      2404576.83     13584563.80
      2404315.03     13584634.20      2404132.45     13584926.77
#Sta/Elev= 30
  4219.1  478.66  4256.0  477.27  4283.7  475.15  4303.9  475.65  4351.2  472.51
  4515.7  464.39  4626.6  458.76  4667.0  456.16  4819.0  448.98  4877.3  446.73
  4887.8  446.19  4909.0  443.94  4959.4  442.07  4996.3  439.75  5008.2  439.69
  5008.4  439.19  5011.9  439.19  5012.2  439.69  5023.8  439.92  5051.6  442.22
  5149.8  442.03  5206.9  442.64  5248.0  443.75  5298.4  446.26  5350.3  447.31
  5508.4  453.30  5523.7  453.45  5529.6  454.31  5613.0  456.83  5613.9  456.83
#Mann=8,-1,0
  4219.1   0.013       0  4256.0    0.05       0  4515.7   0.013       0
  4877.3    0.05       0  5008.2    0.05       0  5012.2    0.05       0
  5149.8   0.013       0  5613.0    0.04       0
Bank Sta=5008.2,5012.2
Exp/Cntr=0.3,0.1

Type RM Length L Ch R = 1,757,448,448,448
BEGIN DESCRIPTION:
Mapping XS 1bee37ef
END DESCRIPTION:
XS GIS Cut Line= 5
      2405299.90     13584310.26      2404536.04     13584445.67
      2404181.88     13584494.28      2404119.38     13584549.83
      2403980.88     13584941.07
#Sta/Elev= 30
  4233.2  476.39  4431.1  467.55  4522.9  461.84  4542.9  461.80  4563.2  460.09
  4624.1  457.36  4664.7  456.49  4674.9  455.30  4725.7  452.79  4766.3  452.13
  4776.4  450.87  4803.2  449.51  4857.3  448.36  4878.0  446.46  4949.1  443.36
  4975.5  439.77  5005.4  439.73  5043.1  440.65  5079.5  439.78  5129.1  438.25
  5129.4  437.75  5133.1  438.25  5171.5  440.38  5322.9  443.49  5582.9  450.96
  5611.3  451.12  5660.2  451.75  5716.7  453.88  5844.7  456.75  5865.1  457.64
#Mann=7,-1,0
  4233.2    0.05       0  5005.4   0.013       0  5079.5    0.05       0
  5129.1    0.05       0  5133.1    0.05       0  5611.3    0.04       0
  5844.7   0.013       0
Bank Sta=5129.1,5133.1
Exp/Cntr=0.3,0.1

Type RM Length L Ch R = 1,309,195,195,195
BEGIN DESCRIPTION:
TRIB 10 TO SALT CREEK 1.0
END DESCRIPTION:
XS GIS Cut Line= 3
      2405126.29     13584185.25      2404191.71     13584191.57
      2403949.62     13584895.93
#Sta/Elev= 30
  4065.4  469.72  4127.6  467.20  4324.4  458.48  4396.7  456.01  4456.7  452.12
  4576.7  446.51  4746.7  439.74  4836.7  437.71  4876.7  437.85  4916.7  436.62
  4956.7  436.57  4993.9  434.37  4994.1  433.87  4997.9  434.37  5002.6  434.37
  5007.1  437.53  5014.2  437.86  5056.5  438.29  5077.6  439.77  5119.9  439.56
  5246.5  443.29  5283.0  443.55  5352.6  446.32  5408.0  447.43  5433.9  448.88
  5439.2  448.37  5461.2  448.75  5590.2  450.73  5616.1  451.87  5744.8  454.66
#Mann=6,-1,0
  4065.4    0.05       0  4127.6    0.12       0  4324.4    0.05       0
  4993.9    0.05       0  4997.9    0.05       0  5461.2    0.04       0
Bank Sta=4993.9,4997.9
Exp/Cntr=0.3,0.1

Type RM Length L Ch R = 1,114,0,0,0
BEGIN DESCRIPTION:
TRIB 10 TO SALT CREEK 0.5
END DESCRIPTION:
XS GIS Cut Line= 4
      2404865.20     13583779.20      2404226.63     13583842.69
      2403987.61     13584167.59      2403950.27     13584724.07
#Sta/Elev= 30
  4014.2  460.92  4265.6  448.47  4297.9  447.37  4416.4  442.20  4466.5  440.85
  4524.8  438.05  4637.5  435.56  4695.3  432.88  4758.1  431.95  4781.0  432.41
  4852.0  431.95  4894.7  430.58  4907.3  431.30  4958.5  431.30  4979.2  430.65
  4985.8  430.02  4986.0  429.52  4989.5  429.52  4989.8  430.02  5052.5  434.72
  5217.0  436.99  5322.3  440.26  5327.3  439.74  5357.3  440.48  5377.4  441.71
  5397.4  442.12  5417.5  444.02  5472.1  444.07  5518.0  445.45  5617.0  448.92
#Mann=8,-1,0
  4014.2    0.05       0  4297.9    0.12       0  4466.5    0.05       0
  4907.3     0.1       0  4979.2    0.05       0  4985.8    0.05       0
  4989.8    0.05       0  5518.0    0.04       0
Bank Sta=4985.8,4989.8
Exp/Cntr=0.3,0.1

Chan Stop Cuts=-1