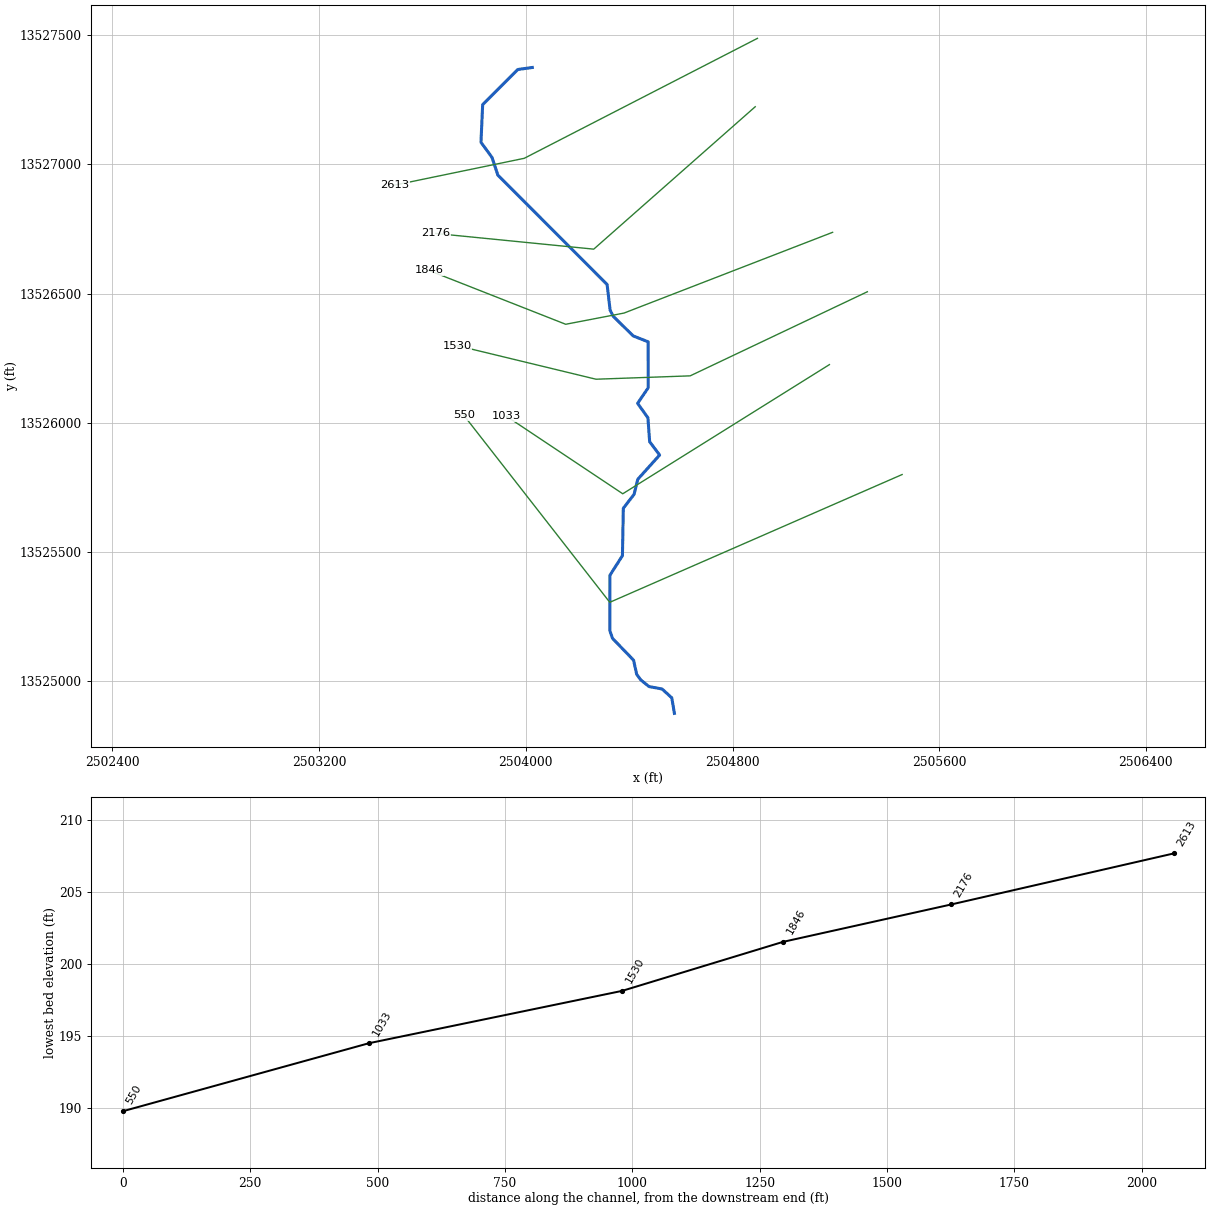
--- TRIB 10 TO TWELVEMILE CREEK.prj (project) ---

Proj Title=TRIB 10 TO TWELVEMILE CREEK Base Level Engineering
Current Plan=p01
Default Exp/Contr=0.3,0.1
English Units
Geom File=g01
Flow File=f01
Plan File=p01
BEGIN DESCRIPTION:
TRIB 10 TO TWELVEMILE CREEK
END DESCRIPTION:

--- TRIB 10 TO TWELVEMILE CREEK.p01 (plan) ---

Plan Title=Multiple Run
Short Identifier=Multiple
Geom File=g01
Flow File=f01
Subcritical Flow
K Sum by GR= 0
Std Step Tol= 0.01
Critical Tol= 0.01
Num of Std Step Trials= 20
Max Error Tol= 0.3
Flow Tol Ratio= 0.001
Split Flow NTrial= 30
Split Flow Tol= 0.02
Split Flow Ratio= 0.02
Log Output Level= 0
Friction Slope Method= 1
Unsteady Friction Slope Method= 2
Unsteady Bridges Friction Slope Method= 1
Parabolic Critical Depth
Global Vel Dist=  1 , 1 , 1
Global Log Level= 0
CheckData=True
Encroach Param= -1, 0, 0, 0
BEGIN DESCRIPTION:
Multiple Run
END DESCRIPTION:

--- TRIB 10 TO TWELVEMILE CREEK.f01 (steady flow) ---

Flow Title=Multiple
Number of Profiles=7
Profile Names=10-year,25-year,50-year,1pct_min,100-year,1pct_plu,500-year
River Rch & RM= TRIB 10 TO TWELV,Reach-1,2613
     283     432     560     353     704    1406    1098
Boundary for River Rch & Prof#=TRIB 10 TO TWELV,Reach-1,1
Up Type=0
Dn Type=3
Dn Slope=0.005
Boundary for River Rch & Prof#=TRIB 10 TO TWELV,Reach-1,2
Up Type=0
Dn Type=3
Dn Slope=0.005
Boundary for River Rch & Prof#=TRIB 10 TO TWELV,Reach-1,3
Up Type=0
Dn Type=3
Dn Slope=0.005
Boundary for River Rch & Prof#=TRIB 10 TO TWELV,Reach-1,4
Up Type=0
Dn Type=3
Dn Slope=0.005
Boundary for River Rch & Prof#=TRIB 10 TO TWELV,Reach-1,5
Up Type=0
Dn Type=3
Dn Slope=0.005
Boundary for River Rch & Prof#=TRIB 10 TO TWELV,Reach-1,6
Up Type=0
Dn Type=3
Dn Slope=0.005
Boundary for River Rch & Prof#=TRIB 10 TO TWELV,Reach-1,7
Up Type=0
Dn Type=3
Dn Slope=0.005

--- TRIB 10 TO TWELVEMILE CREEK.g01 (geometry) ---

Geom Title=Existing Conditions

River Reach=TRIB 10 TO TWELV,Reach-1
Reach XY= 30
      2504025.00     13527375.00      2503968.79     13527367.24
      2503832.80     13527231.19      2503826.19     13527085.50
      2503868.86     13527027.17      2503891.64     13526958.32
      2504314.48     13526534.79      2504326.16     13526435.48
      2504338.40     13526411.67      2504415.60     13526335.90
      2504473.38     13526313.17      2504473.62     13526135.44
      2504432.56     13526075.00      2504472.45     13526019.10
      2504479.10     13525926.50      2504517.68     13525874.90
      2504433.18     13525781.06      2504418.86     13525722.83
      2504377.24     13525669.07      2504373.78     13525485.51
      2504325.52     13525409.78      2504324.96     13525194.98
      2504335.50     13525165.21      2504416.81     13525081.02
      2504428.89     13525026.43      2504444.63     13525004.53
      2504476.44     13524978.87      2504527.48     13524969.28
      2504564.67     13524935.25      2504575.00     13524875.00

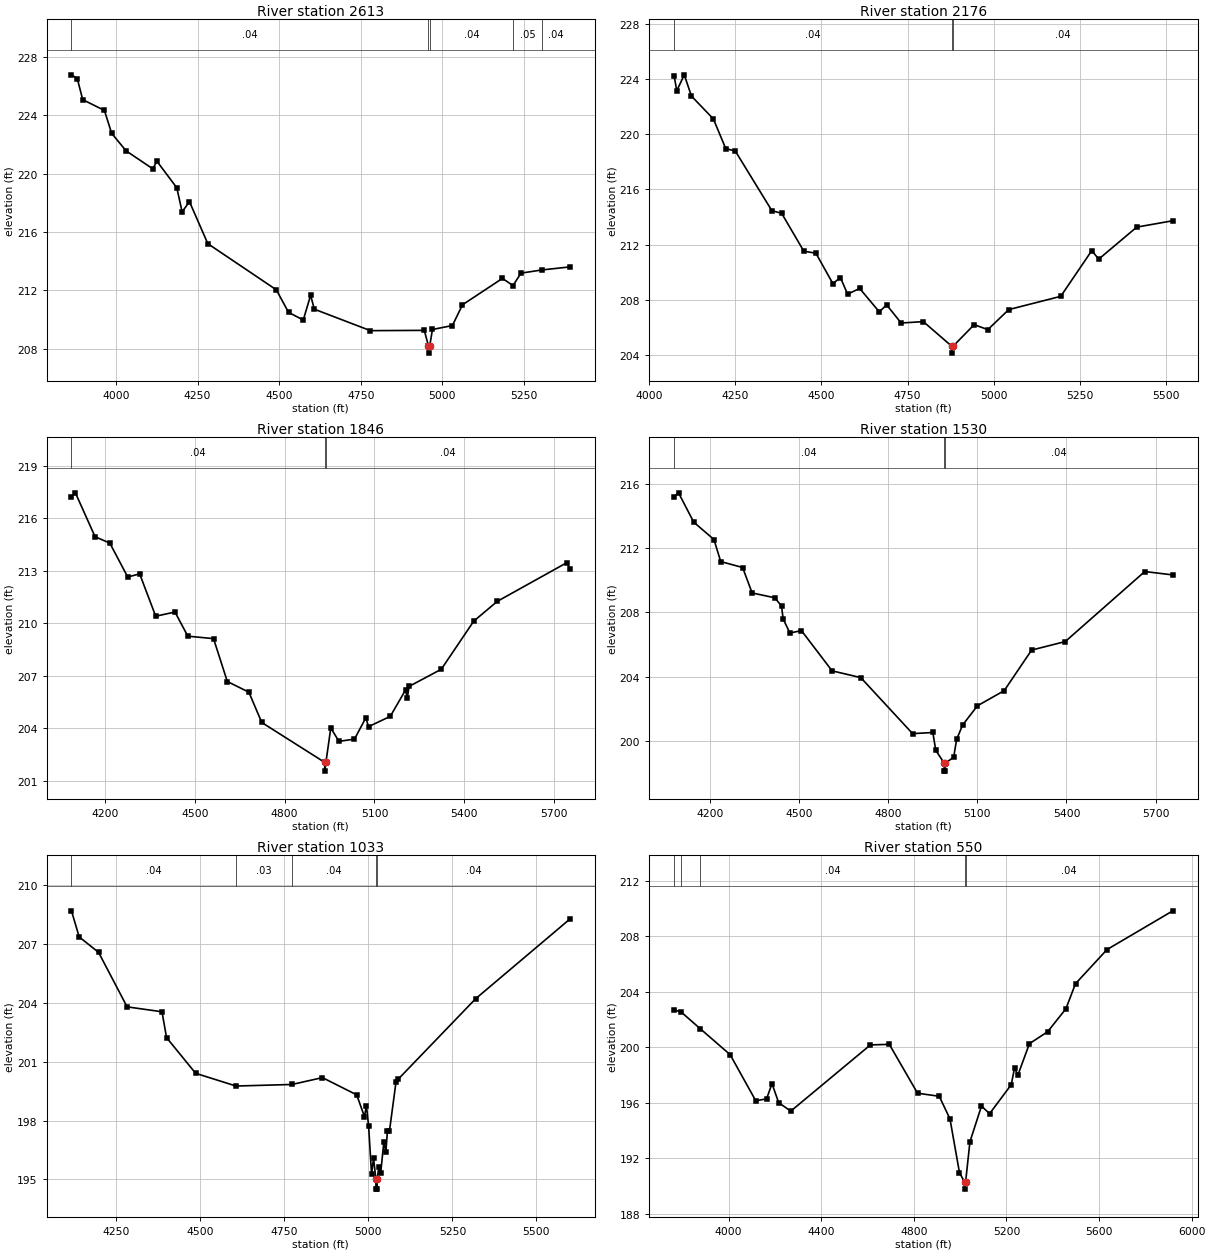
Type RM Length L Ch R = 1,2613,437,437,437
BEGIN DESCRIPTION:
TRIB 10 TO TWELVEMILE CREEK 4.0
END DESCRIPTION:
XS GIS Cut Line= 3
      2504896.43     13527487.84      2503993.66     13527023.44
      2503491.91     13526919.63
#Sta/Elev= 30
  3863.6  226.77  3881.4  226.51  3898.0  225.07  3964.5  224.33  3986.7  222.76
  4031.0  221.56  4112.6  220.33  4125.3  220.85  4186.3  219.03  4202.6  217.38
  4225.0  218.08  4281.3  215.20  4491.1  212.04  4528.7  210.49  4573.7  209.97
  4596.2  211.66  4607.6  210.71  4779.4  209.24  4944.5  209.26  4957.1  208.20
  4957.4  207.70  4961.1  208.20  4969.4  209.32  5030.6  209.59  5061.3  211.01
  5183.8  212.82  5216.2  212.33  5240.6  213.18  5304.7  213.40  5391.2  213.61
#Mann=5,-1,0
  3863.6    0.04       0  4957.1    0.04       0  4961.1    0.04       0
  5216.2    0.05       0  5304.7    0.04       0
Bank Sta=4957.1,4961.1
Exp/Cntr=0.3,0.1

Type RM Length L Ch R = 1,2176,330,330,330
BEGIN DESCRIPTION:
Mapping XS 3ce256b1
END DESCRIPTION:
XS GIS Cut Line= 3
      2504887.79     13527223.12      2504262.76     13526671.88
      2503650.76     13526732.64
#Sta/Elev= 30
  4072.2  224.19  4079.8  223.14  4101.5  224.29  4122.4  222.75  4186.0  221.10
  4222.0  218.95  4249.6  218.78  4355.9  214.46  4384.3  214.27  4448.7  211.53
  4483.9  211.38  4533.2  209.18  4555.0  209.62  4575.9  208.42  4611.0  208.83
  4667.9  207.14  4689.3  207.64  4731.5  206.33  4795.9  206.43  4878.4  204.65
  4878.6  204.15  4882.4  204.65  4943.5  206.21  4983.3  205.85  5044.0  207.30
  5195.0  208.26  5285.2  211.57  5305.3  210.95  5415.8  213.27  5520.6  213.73
#Mann=3,-1,0
  4072.2    0.04       0  4878.4    0.04       0  4882.4    0.04       0
Bank Sta=4878.4,4882.4
Exp/Cntr=0.3,0.1

Type RM Length L Ch R = 1,1846,316,316,316
BEGIN DESCRIPTION:
Mapping XS 888342bb
END DESCRIPTION:
XS GIS Cut Line= 4
      2505187.24     13526736.98      2504379.95     13526424.48
      2504154.25     13526381.08      2503624.76     13526589.40
#Sta/Elev= 30
  4088.6  217.20  4101.7  217.45  4167.4  214.94  4216.5  214.58  4276.4  212.64
  4316.2  212.82  4369.8  210.40  4434.1  210.64  4477.0  209.26  4562.8  209.12
  4608.8  206.67  4680.8  206.06  4723.7  204.33  4933.9  202.05  4934.1  201.55
  4937.9  202.05  4954.2  204.02  4981.4  203.25  5033.3  203.38  5071.3  204.60
  5080.1  204.09  5152.8  204.68  5203.9  206.19  5209.3  205.70  5215.5  206.39
  5323.0  207.37  5431.4  210.12  5510.0  211.25  5742.1  213.46  5753.1  213.08
#Mann=3,-1,0
  4088.6    0.04       0  4933.9    0.04       0  4937.9    0.04       0
Bank Sta=4933.9,4937.9
Exp/Cntr=0.3,0.1

Type RM Length L Ch R = 1,1530,497,497,497
BEGIN DESCRIPTION:
Mapping XS ebdaab69
END DESCRIPTION:
XS GIS Cut Line= 4
      2505321.83     13526506.96      2504636.02     13526181.42
      2504271.44     13526168.40      2503733.23     13526298.61
#Sta/Elev= 30
  4080.1  215.20  4094.8  215.43  4145.8  213.61  4213.9  212.53  4236.7  211.16
  4310.4  210.79  4342.3  209.21  4418.5  208.91  4441.2  208.40  4446.8  207.59
  4469.5  206.72  4508.3  206.87  4611.4  204.37  4707.9  203.95  4882.2  200.47
  4950.3  200.54  4960.3  199.43  4988.4  198.64  4988.6  198.14  4992.1  198.14
  4992.4  198.64  5020.4  199.00  5030.4  200.11  5050.4  201.00  5100.4  202.20
  5190.5  203.14  5282.7  205.66  5395.9  206.19  5663.4  210.54  5757.8  210.33
#Mann=3,-1,0
  4080.1    0.04       0  4988.4    0.04       0  4992.4    0.04       0
Bank Sta=4988.4,4992.4
Exp/Cntr=0.3,0.1

Type RM Length L Ch R = 1,1033,483,483,483
BEGIN DESCRIPTION:
TRIB 10 TO TWELVEMILE CREEK 2.0
END DESCRIPTION:
XS GIS Cut Line= 3
      2505174.96     13526224.97      2504375.00     13525725.00
      2503924.99     13526025.01
#Sta/Elev= 30
  4116.2  208.70  4139.1  207.37  4196.9  206.58  4281.8  203.80  4385.6  203.55
  4399.2  202.23  4485.8  200.41  4605.9  199.76  4772.4  199.84  4863.2  200.19
  4965.2  199.31  4988.2  198.20  4994.1  198.76  5000.6  197.72  5009.4  195.25
  5015.3  196.09  5022.2  195.00  5022.4  194.50  5025.9  194.50  5026.2  195.00
  5030.7  195.61  5036.6  195.34  5046.0  196.91  5051.9  196.38  5056.6  197.46
  5062.6  197.46  5082.1  199.96  5088.1  200.10  5319.5  204.22  5600.4  208.29
#Mann=5,-1,0
  4116.2    0.04       0  4605.9    0.03       0  4772.4    0.04       0
  5022.2    0.04       0  5026.2    0.04       0
Bank Sta=5022.2,5026.2
Exp/Cntr=0.3,0.1

Type RM Length L Ch R = 1,550,0,0,0
BEGIN DESCRIPTION:
TRIB 10 TO TWELVEMILE CREEK 1.0
END DESCRIPTION:
XS GIS Cut Line= 3
      2505456.31     13525799.47      2504324.80     13525304.94
      2503759.65     13526029.05
#Sta/Elev= 30
  3765.3  202.66  3793.4  202.56  3878.3  201.32  4006.8  199.46  4117.5  196.14
  4164.3  196.27  4187.7  197.37  4216.5  196.00  4268.8  195.39  4612.7  200.16
  4694.4  200.20  4816.3  196.68  4909.9  196.46  4956.3  194.83  4997.3  190.96
  5019.7  190.27  5020.0  189.77  5023.7  190.27  5042.5  193.18  5092.3  195.75
  5127.6  195.21  5220.7  197.29  5235.2  198.49  5249.7  197.99  5299.4  200.25
  5378.1  201.11  5456.8  202.76  5498.4  204.57  5634.5  207.03  5918.7  209.82
#Mann=5,-1,0
  3765.3    0.04       0  3793.4    0.05       0  3878.3    0.04       0
  5019.7    0.04       0  5023.7    0.04       0
Bank Sta=5019.7,5023.7
Exp/Cntr=0.3,0.1

Chan Stop Cuts=-1