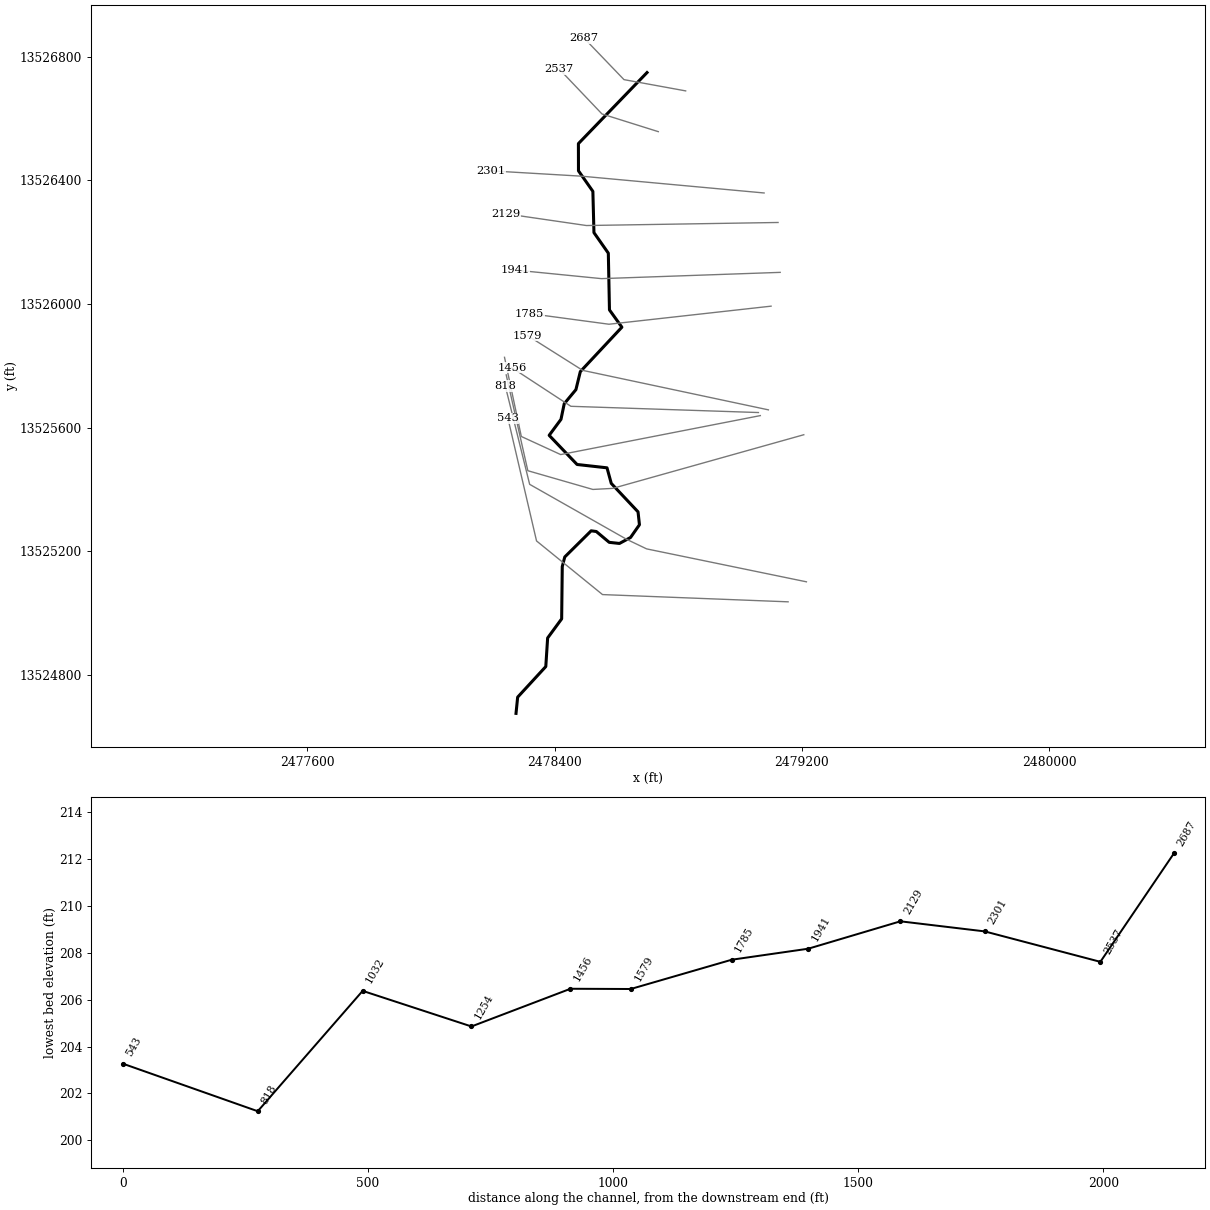
--- TRIB 10_1 TO FIFTEENMILE CREEK.prj (project) ---

Proj Title=TRIB 10_1 TO FIFTEENMILE CREEK Base Level Engineering
Current Plan=p01
Default Exp/Contr=0.3,0.1
English Units
Geom File=g01
Flow File=f01
Plan File=p01
BEGIN DESCRIPTION:
TRIB 10_1 TO FIFTEENMILE CREEK
END DESCRIPTION:

--- TRIB 10_1 TO FIFTEENMILE CREEK.p01 (plan) ---

Plan Title=Multiple Run
Short Identifier=Multiple
Geom File=g01
Flow File=f01
Subcritical Flow
K Sum by GR= 0
Std Step Tol= 0.01
Critical Tol= 0.01
Num of Std Step Trials= 20
Max Error Tol= 0.3
Flow Tol Ratio= 0.001
Split Flow NTrial= 30
Split Flow Tol= 0.02
Split Flow Ratio= 0.02
Log Output Level= 0
Friction Slope Method= 1
Unsteady Friction Slope Method= 2
Unsteady Bridges Friction Slope Method= 1
Parabolic Critical Depth
Global Vel Dist=  1 , 1 , 1
Global Log Level= 0
CheckData=True
Encroach Param= -1, 0, 0, 0
BEGIN DESCRIPTION:
Multiple Run
END DESCRIPTION:

--- TRIB 10_1 TO FIFTEENMILE CREEK.f01 (steady flow) ---

Flow Title=Multiple
Number of Profiles=7
Profile Names=10-year,25-year,50-year,1pct_min,100-year,1pct_plu,500-year
River Rch & RM= TRIB 10_1 TO FIF,Reach-1,2687
     546     871    1160     748    1492    2977    2444
River Rch & RM= TRIB 10_1 TO FIF,Reach-1,1579
     918    1501    2035    1333    2660    5307    4499
Boundary for River Rch & Prof#=TRIB 10_1 TO FIF,Reach-1,1
Up Type=0
Dn Type=3
Dn Slope=0.005
Boundary for River Rch & Prof#=TRIB 10_1 TO FIF,Reach-1,2
Up Type=0
Dn Type=3
Dn Slope=0.005
Boundary for River Rch & Prof#=TRIB 10_1 TO FIF,Reach-1,3
Up Type=0
Dn Type=3
Dn Slope=0.005
Boundary for River Rch & Prof#=TRIB 10_1 TO FIF,Reach-1,4
Up Type=0
Dn Type=3
Dn Slope=0.005
Boundary for River Rch & Prof#=TRIB 10_1 TO FIF,Reach-1,5
Up Type=0
Dn Type=3
Dn Slope=0.005
Boundary for River Rch & Prof#=TRIB 10_1 TO FIF,Reach-1,6
Up Type=0
Dn Type=3
Dn Slope=0.005
Boundary for River Rch & Prof#=TRIB 10_1 TO FIF,Reach-1,7
Up Type=0
Dn Type=3
Dn Slope=0.005

--- TRIB 10_1 TO FIFTEENMILE CREEK.g01 (geometry) ---

Geom Title=Existing Conditions

River Reach=TRIB 10_1 TO FIF,Reach-1
Reach XY= 30
      2478699.04     13526749.04      2478476.96     13526519.11
      2478477.16     13526430.98      2478523.77     13526364.49
      2478527.27     13526230.94      2478573.78     13526164.49
      2478577.47     13525980.85      2478617.68     13525924.90
      2478483.14     13525781.06      2478468.89     13525722.81
      2478431.05     13525677.19      2478420.56     13525626.63
      2478382.28     13525574.90      2478472.60     13525480.55
      2478569.53     13525469.74      2478583.32     13525419.30
      2478669.93     13525327.26      2478674.51     13525285.45
      2478645.69     13525244.27      2478609.80     13525224.96
      2478576.68     13525228.57      2478534.86     13525263.61
      2478518.25     13525265.86      2478432.81     13525181.23
      2478424.71     13525150.13      2478422.74     13524980.94
      2478377.36     13524919.02      2478371.39     13524826.50
      2478280.33     13524727.51      2478275.00     13524675.00

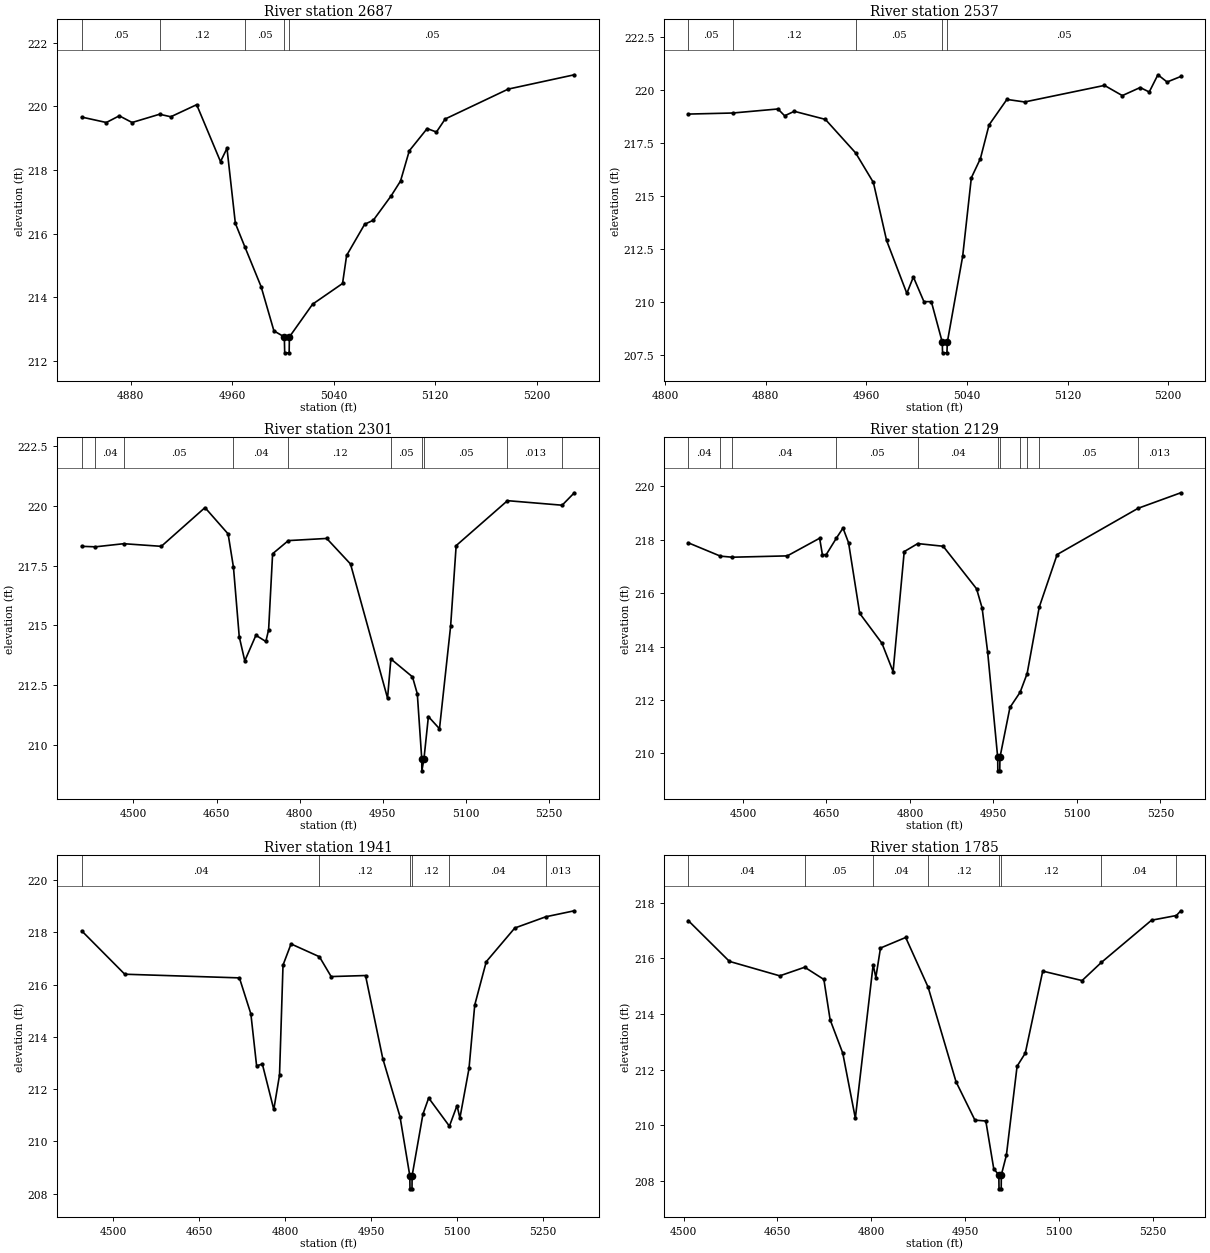
Type RM Length L Ch R = 1,2687,150,150,150
BEGIN DESCRIPTION:
Mapping XS faae2e0a
END DESCRIPTION:
XS GIS Cut Line= 3
      2478824.08     13526689.70      2478624.45     13526726.15
      2478496.01     13526859.80
#Sta/Elev= 30
  4841.5  219.66  4860.9  219.49  4871.1  219.70  4881.2  219.49  4902.9  219.75
  4911.7  219.67  4932.1  220.05  4950.9  218.26  4956.0  218.68  4962.6  216.32
  4970.0  215.59  4982.9  214.33  4993.0  212.94  5001.2  212.75  5001.5  212.25
  5005.0  212.25  5005.2  212.75  5023.5  213.78  5047.1  214.43  5050.3  215.31
  5064.5  216.29  5071.4  216.42  5085.5  217.19  5092.8  217.65  5099.7  218.60
  5113.8  219.30  5121.1  219.19  5128.0  219.60  5177.7  220.54  5229.8  220.99
#Mann=5,-1,0
  4841.5    0.05       0  4902.9    0.12       0  4970.0    0.05       0
  5001.2    0.05       0  5005.2    0.05       0
Bank Sta=5001.2,5005.2
Exp/Cntr=0.3,0.1

Type RM Length L Ch R = 1,2537,236,236,236
BEGIN DESCRIPTION:
Mapping XS 714c9a07
END DESCRIPTION:
XS GIS Cut Line= 3
      2478735.53     13526557.76      2478553.27     13526615.04
      2478414.82     13526760.41
#Sta/Elev= 30
  4818.3  218.86  4853.7  218.91  4889.7  219.10  4895.0  218.78  4902.7  218.99
  4927.4  218.61  4951.5  217.03  4965.6  215.64  4976.1  212.91  4992.2  210.42
  4997.4  211.19  5005.8  210.03  5011.7  210.03  5020.4  208.12  5020.6  207.62
  5024.1  207.62  5024.4  208.12  5036.6  212.16  5043.5  215.86  5050.7  216.76
  5057.6  218.35  5071.8  219.55  5085.9  219.43  5149.4  220.21  5163.6  219.73
  5177.8  220.11  5185.0  219.90  5191.9  220.71  5199.2  220.37  5210.1  220.63
#Mann=5,-1,0
  4818.3    0.05       0  4853.7    0.12       0  4951.5    0.05       0
  5020.4    0.05       0  5024.4    0.05       0
Bank Sta=5020.4,5024.4
Exp/Cntr=0.3,0.1

Type RM Length L Ch R = 1,2301,172,172,172
BEGIN DESCRIPTION:
Mapping XS 7cb8d4b1
END DESCRIPTION:
XS GIS Cut Line= 3
      2479077.96     13526359.30      2478487.30     13526413.65
      2478192.17     13526431.01
#Sta/Elev= 30
  4406.8  218.31  4431.5  218.29  4482.6  218.42  4550.4  218.31  4629.2  219.93
  4670.9  218.83  4680.6  217.43  4691.0  214.53  4701.0  213.52  4721.1  214.59
  4739.0  214.33  4744.0  214.82  4751.2  218.00  4779.6  218.55  4848.8  218.64
  4891.8  217.57  4958.6  211.96  4964.6  213.60  5003.6  212.85  5012.3  212.14
  5020.3  209.42  5020.5  208.92  5024.3  209.42  5032.3  211.19  5052.3  210.68
  5072.4  214.97  5082.4  218.34  5175.0  220.22  5273.6  220.03  5295.6  220.55
#Mann=10,-1,0
  4406.8    0.05       0  4431.5    0.04       0  4482.6    0.05       0
  4680.6    0.04       0  4779.6    0.12       0  4964.6    0.05       0
  5020.3    0.05       0  5024.3    0.05       0  5175.0   0.013       0
  5273.6    0.03       0
Bank Sta=5020.3,5024.3
Exp/Cntr=0.3,0.1

Type RM Length L Ch R = 1,2129,188,188,188
BEGIN DESCRIPTION:
Mapping XS a25bef2b
END DESCRIPTION:
XS GIS Cut Line= 3
      2479123.12     13526263.81      2478502.92     13526253.93
      2478240.76     13526292.12
#Sta/Elev= 30
  4401.5  217.88  4459.4  217.38  4480.7  217.34  4579.6  217.39  4637.7  218.05
  4642.7  217.43  4649.6  217.44  4668.0  218.06  4679.7  218.43  4689.7  217.88
  4709.7  215.24  4749.7  214.12  4769.7  213.06  4789.7  217.55  4814.0  217.85
  4859.7  217.75  4919.7  216.16  4929.7  215.44  4939.7  213.78  4957.7  209.85
  4957.9  209.35  4961.4  209.35  4961.7  209.85  4979.7  211.72  4998.0  212.29
  5010.6  212.99  5032.3  215.47  5064.5  217.44  5210.0  219.17  5286.7  219.75
#Mann=11,-1,0
  4401.5    0.04       0  4459.4    0.05       0  4480.7    0.04       0
  4668.0    0.05       0  4814.0    0.04       0  4957.7    0.05       0
  4961.7    0.04       0  4998.0    0.12       0  5010.6    0.04       0
  5032.3    0.05       0  5210.0   0.013       0
Bank Sta=4957.7,4961.7
Exp/Cntr=0.3,0.1

Type RM Length L Ch R = 1,1941,156,156,156
BEGIN DESCRIPTION:
Mapping XS e1ade0fb
END DESCRIPTION:
XS GIS Cut Line= 3
      2479130.03     13526102.35      2478551.53     13526082.05
      2478272.07     13526109.83
#Sta/Elev= 30
  4444.7  218.06  4519.8  216.40  4719.9  216.26  4739.9  214.88  4749.9  212.89
  4759.9  212.96  4779.9  211.22  4789.9  212.54  4796.0  216.75  4810.0  217.56
  4859.5  217.07  4880.0  216.31  4940.0  216.35  4970.1  213.17  5000.1  210.95
  5017.3  208.68  5017.6  208.18  5021.1  208.18  5021.3  208.68  5040.2  211.04
  5050.2  211.66  5086.4  210.58  5099.7  211.37  5104.7  210.89  5120.6  212.79
  5130.6  215.22  5150.7  216.88  5200.5  218.17  5254.6  218.60  5304.4  218.83
#Mann=6,-1,0
  4444.7    0.04       0  4859.5    0.12       0  5017.3    0.05       0
  5021.3    0.12       0  5086.4    0.04       0  5254.6   0.013       0
Bank Sta=5017.3,5021.3
Exp/Cntr=0.3,0.1

Type RM Length L Ch R = 1,1785,206,206,206
BEGIN DESCRIPTION:
Mapping XS aeb3d923
END DESCRIPTION:
XS GIS Cut Line= 3
      2479100.53     13525992.98      2478575.84     13525934.48
      2478318.59     13525969.01
#Sta/Elev= 30
  4507.4  217.36  4573.3  215.89  4653.8  215.37  4693.7  215.68  4724.3  215.24
  4734.3  213.79  4754.5  212.59  4774.6  210.25  4803.1  215.77  4807.4  215.31
  4814.8  216.37  4855.1  216.75  4891.0  214.96  4935.6  211.56  4965.8  210.18
  4983.2  210.15  4995.9  208.43  5004.0  208.21  5004.3  207.71  5007.8  207.71
  5008.0  208.21  5016.1  208.92  5033.2  212.12  5046.3  212.59  5074.2  215.54
  5137.1  215.20  5167.8  215.85  5248.1  217.37  5287.9  217.54  5294.9  217.71
#Mann=8,-1,0
  4507.4    0.04       0  4693.7    0.05       0  4803.1    0.04       0
  4891.0    0.12       0  5004.0    0.05       0  5008.0    0.12       0
  5167.8    0.04       0  5287.9   0.013       0
Bank Sta=5004,5008
Exp/Cntr=0.3,0.1

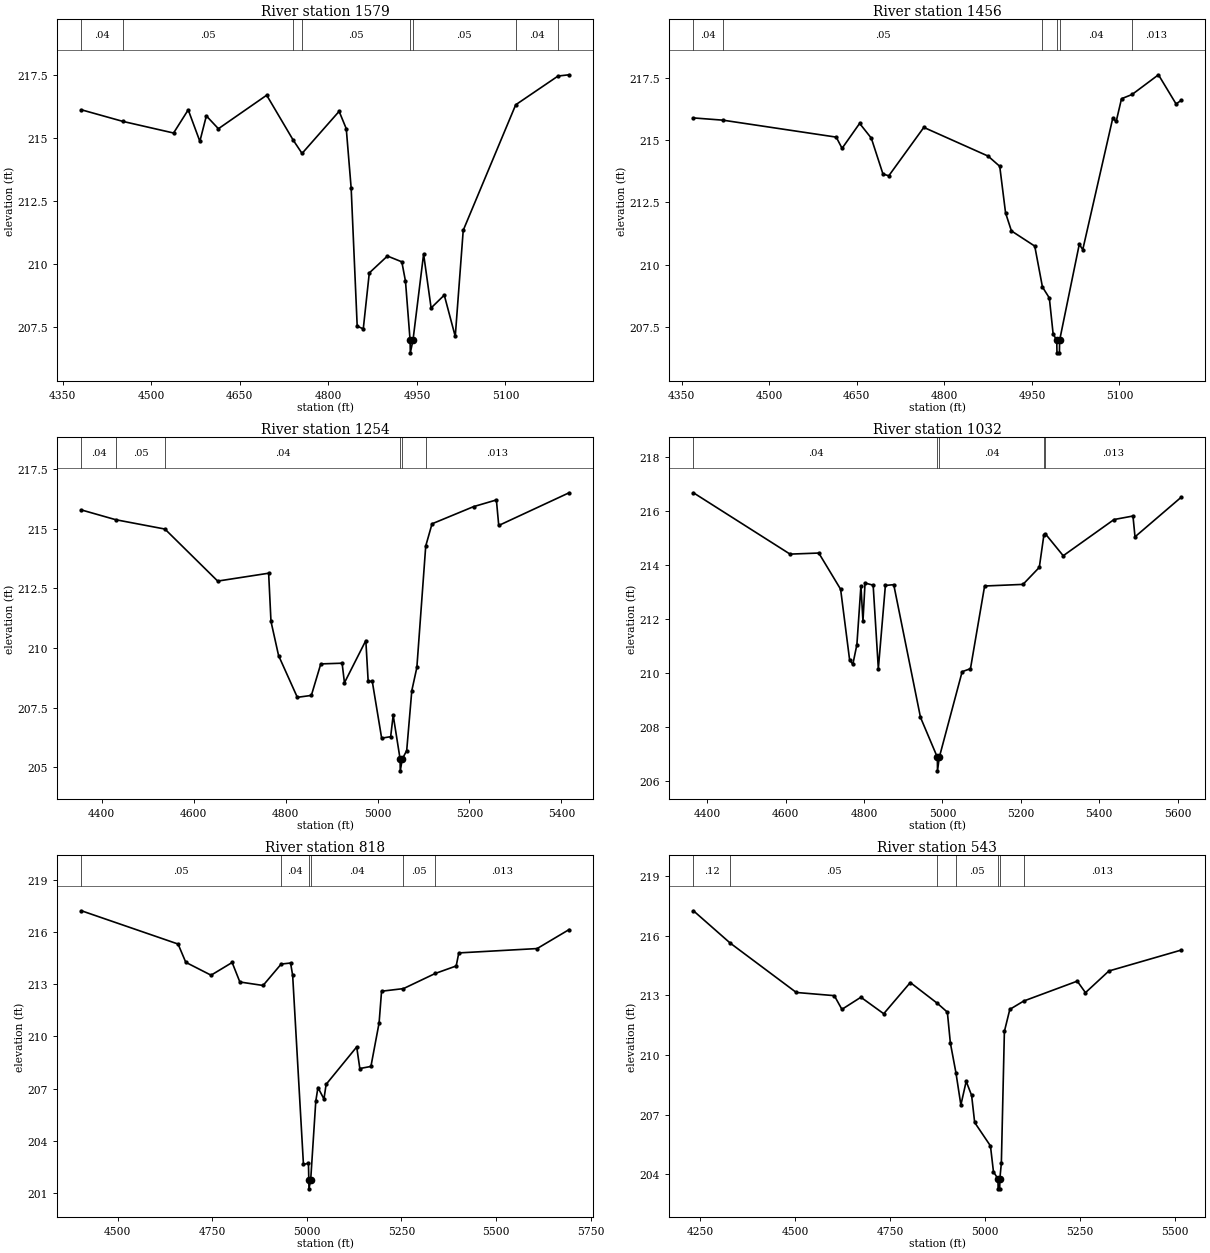
Type RM Length L Ch R = 1,1579,123,123,123
BEGIN DESCRIPTION:
Mapping XS 8ce5126c
END DESCRIPTION:
XS GIS Cut Line= 3
      2479091.83     13525657.38      2478490.77     13525785.18
      2478311.99     13525898.00
#Sta/Elev= 30
  4381.9  216.10  4452.1  215.64  4537.9  215.18  4562.7  216.10  4582.4  214.85
  4593.4  215.86  4613.8  215.35  4695.6  216.68  4740.2  214.91  4755.5  214.37
  4818.3  216.04  4830.4  215.35  4838.7  212.99  4848.9  207.52  4859.2  207.41
  4869.4  209.63  4900.1  210.30  4924.5  210.07  4930.7  209.30  4938.5  206.96
  4938.9  206.46  4943.4  206.96  4961.4  210.38  4974.1  208.24  4996.4  208.75
  5015.0  207.11  5028.5  211.32  5117.4  216.30  5189.1  217.44  5207.8  217.49
#Mann=8,-1,0
  4381.9    0.04       0  4452.1    0.05       0  4740.2    0.04       0
  4755.5    0.05       0  4938.5    0.05       0  4943.4    0.05       0
  5117.4    0.04       0  5189.1   0.013       0
Bank Sta=4938.5,4943.4
Exp/Cntr=0.3,0.1

Type RM Length L Ch R = 1,1456,202,202,202
BEGIN DESCRIPTION:
Mapping XS ab5d5708
END DESCRIPTION:
XS GIS Cut Line= 3
      2479059.61     13525648.69      2478452.58     13525668.86
      2478261.61     13525793.85
#Sta/Elev= 30
  4370.0  215.89  4420.5  215.80  4614.7  215.12  4624.7  214.67  4654.8  215.67
  4674.8  215.08  4694.8  213.64  4704.8  213.57  4764.8  215.51  4874.9  214.36
  4894.9  213.95  4904.9  212.08  4914.9  211.36  4954.9  210.75  4968.1  209.11
  4979.9  208.67  4986.4  207.23  4992.6  206.97  4993.0  206.47  4997.2  206.47
  4997.5  206.97  5031.2  210.82  5037.2  210.61  5088.5  215.87  5094.5  215.75
  5103.6  216.66  5121.7  216.83  5166.9  217.62  5197.1  216.45  5205.6  216.59
#Mann=6,-1,0
  4370.0    0.04       0  4420.5    0.05       0  4968.1    0.04       0
  4992.6    0.04       0  4997.5    0.04       0  5121.7   0.013       0
Bank Sta=4992.6,4997.5
Exp/Cntr=0.3,0.1

Type RM Length L Ch R = 1,1254,222,222,222
BEGIN DESCRIPTION:
Mapping XS 32dccbb8
END DESCRIPTION:
XS GIS Cut Line= 4
      2479065.76     13525638.75      2478419.59     13525512.61
      2478292.16     13525571.19      2478237.78     13525827.46
#Sta/Elev= 30
  4356.1  215.79  4430.9  215.38  4537.6  214.99  4652.4  212.81  4763.2  213.14
  4768.3  211.12  4784.8  209.69  4825.6  207.94  4856.1  208.02  4876.6  209.34
  4923.0  209.37  4928.1  208.55  4974.6  210.32  4979.7  208.61  4988.6  208.61
  5009.0  206.23  5028.6  206.29  5034.1  207.19  5049.1  205.36  5049.5  204.86
  5054.0  205.36  5063.5  205.71  5074.6  208.22  5085.6  209.19  5104.9  214.28
  5118.6  215.21  5209.0  215.93  5258.6  216.21  5263.7  215.14  5416.7  216.51
#Mann=6,-1,0
  4356.1    0.04       0  4430.9    0.05       0  4537.6    0.04       0
  5049.1    0.04       0  5054.0    0.04       0  5104.9   0.013       0
Bank Sta=5049.1,5054
Exp/Cntr=0.3,0.1

Type RM Length L Ch R = 1,1032,214,214,214
BEGIN DESCRIPTION:
Mapping XS 0cc9c668
END DESCRIPTION:
XS GIS Cut Line= 5
      2479206.39     13525576.82      2478587.99     13525403.23
      2478523.76     13525399.76      2478313.28     13525460.39
      2478243.26     13525770.62
#Sta/Elev= 30
  4364.9  216.67  4611.3  214.40  4684.6  214.44  4740.3  213.10  4763.2  210.49
  4771.4  210.32  4781.8  211.05  4792.1  213.22  4797.3  211.92  4802.6  213.33
  4823.3  213.25  4836.5  210.16  4854.5  213.24  4875.8  213.27  4944.0  208.36
  4987.1  206.88  4987.4  206.38  4992.0  206.88  5050.3  210.05  5071.5  210.16
  5107.6  213.22  5205.5  213.28  5247.1  213.91  5258.7  215.10  5262.6  215.15
  5308.1  214.34  5437.7  215.68  5486.0  215.81  5491.2  215.04  5608.6  216.50
#Mann=5,-1,0
  4364.9    0.04       0  4987.1    0.04       0  4992.0    0.04       0
  5258.7    0.05       0  5262.6   0.013       0
Bank Sta=4987.1,4992
Exp/Cntr=0.3,0.1

Type RM Length L Ch R = 1,818,275,275,275
BEGIN DESCRIPTION:
Mapping XS cd4a8e17
END DESCRIPTION:
XS GIS Cut Line= 5
      2479214.91     13525100.81      2478697.74     13525207.40
      2478633.13     13525238.30      2478319.18     13525416.28
      2478240.33     13525734.51
#Sta/Elev= 30
  4404.5  217.21  4659.7  215.30  4680.1  214.25  4746.9  213.51  4802.6  214.24
  4823.0  213.12  4884.3  212.92  4932.2  214.15  4957.0  214.21  4962.5  213.50
  4991.0  202.64  5004.2  202.71  5005.2  201.74  5005.6  201.24  5010.1  201.74
  5023.6  206.27  5029.3  207.06  5045.2  206.40  5050.9  207.24  5131.7  209.39
  5140.0  208.15  5169.3  208.27  5190.9  210.77  5197.4  212.59  5255.3  212.74
  5339.3  213.61  5394.6  214.04  5401.5  214.79  5608.5  215.04  5692.9  216.13
#Mann=6,-1,0
  4404.5    0.05       0  4932.2    0.04       0  5005.2    0.04       0
  5010.1    0.04       0  5255.3    0.05       0  5339.3   0.013       0
Bank Sta=5005.2,5010.1
Exp/Cntr=0.3,0.1

Type RM Length L Ch R = 1,543,0,0,0
BEGIN DESCRIPTION:
Mapping XS 2b8d293b
END DESCRIPTION:
XS GIS Cut Line= 4
      2479155.71     13525036.04      2478555.01     13525059.48
      2478341.46     13525233.10      2478248.81     13525630.16
#Sta/Elev= 30
  4232.6  217.26  4329.7  215.63  4503.5  213.15  4603.6  212.99  4623.6  212.30
  4673.6  212.91  4733.7  212.08  4803.7  213.65  4875.2  212.60  4901.3  212.16
  4909.2  210.61  4923.9  209.11  4936.9  207.49  4950.9  208.68  4965.2  207.97
  4973.2  206.61  5014.8  205.43  5022.7  204.13  5034.6  203.77  5035.0  203.27
  5039.2  203.27  5039.5  203.77  5043.5  204.56  5051.5  211.19  5065.8  212.30
  5102.5  212.72  5243.4  213.72  5265.0  213.14  5326.6  214.23  5516.7  215.28
#Mann=7,-1,0
  4232.6    0.12       0  4329.7    0.05       0  4875.2    0.04       0
  4923.9    0.05       0  5034.6    0.05       0  5039.5    0.05       0
  5102.5   0.013       0
Bank Sta=5034.6,5039.5
Exp/Cntr=0.3,0.1

Chan Stop Cuts=-1