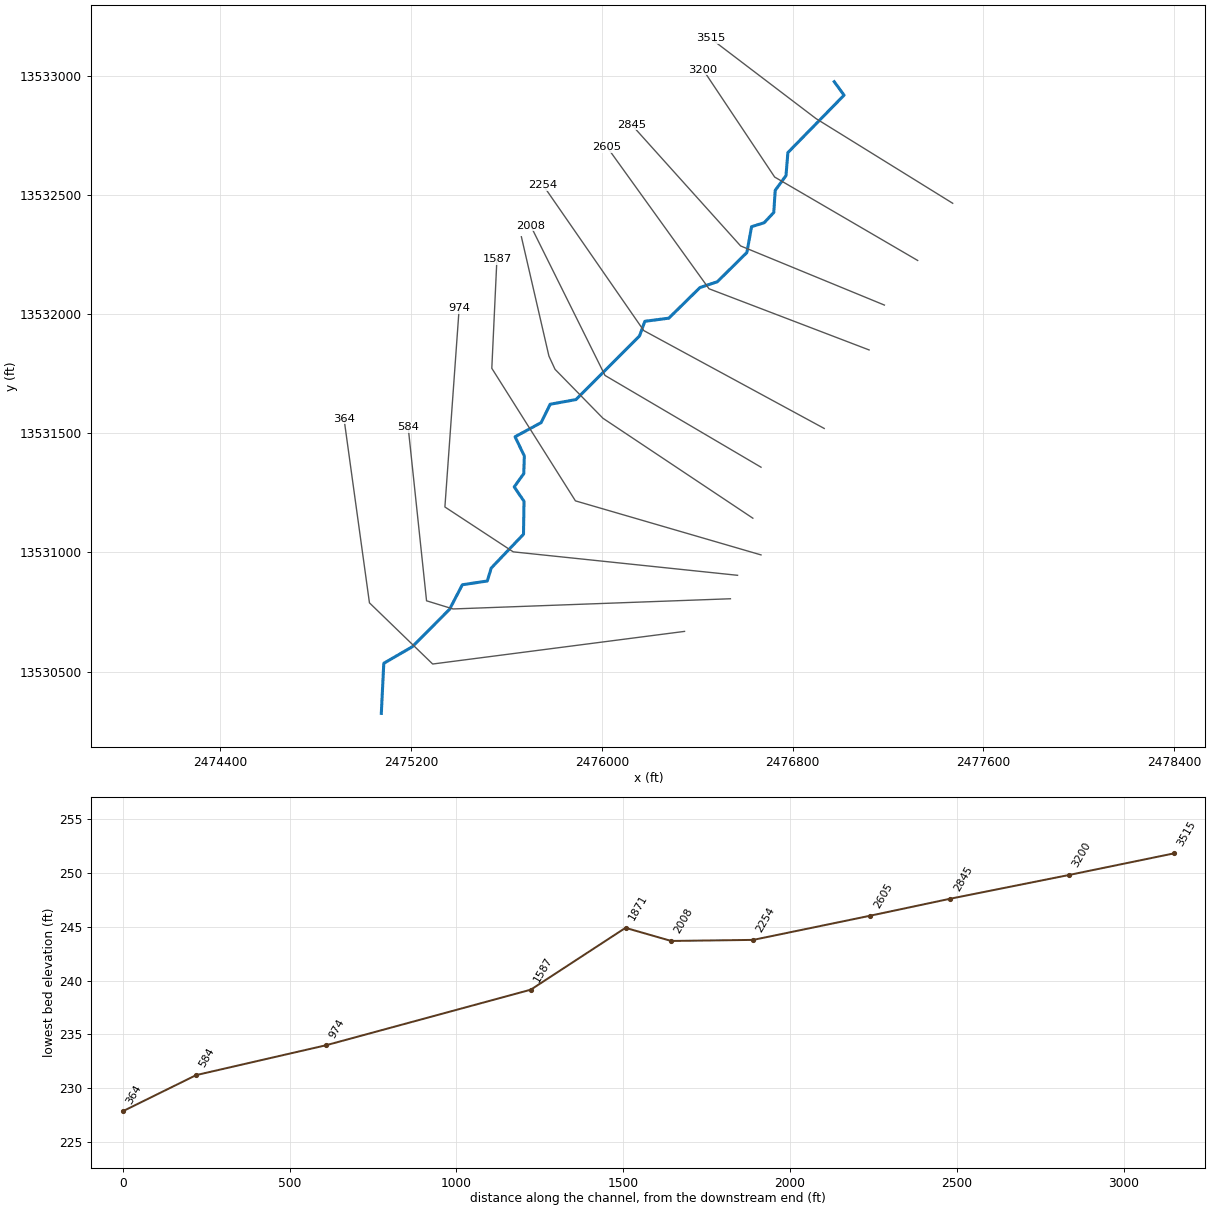
--- TRIB 10_2 TO FIFTEENMILE CREEK.prj (project) ---

Proj Title=TRIB 10_2 TO FIFTEENMILE CREEK Base Level Engineering
Current Plan=p01
Default Exp/Contr=0.3,0.1
English Units
Geom File=g01
Flow File=f01
Plan File=p01
BEGIN DESCRIPTION:
TRIB 10_2 TO FIFTEENMILE CREEK
END DESCRIPTION:

--- TRIB 10_2 TO FIFTEENMILE CREEK.p01 (plan) ---

Plan Title=Multiple Run
Short Identifier=Multiple
Geom File=g01
Flow File=f01
Subcritical Flow
K Sum by GR= 0
Std Step Tol= 0.01
Critical Tol= 0.01
Num of Std Step Trials= 20
Max Error Tol= 0.3
Flow Tol Ratio= 0.001
Split Flow NTrial= 30
Split Flow Tol= 0.02
Split Flow Ratio= 0.02
Log Output Level= 0
Friction Slope Method= 1
Unsteady Friction Slope Method= 2
Unsteady Bridges Friction Slope Method= 1
Parabolic Critical Depth
Global Vel Dist=  1 , 1 , 1
Global Log Level= 0
CheckData=True
Encroach Param= -1, 0, 0, 0
BEGIN DESCRIPTION:
Multiple Run
END DESCRIPTION:

--- TRIB 10_2 TO FIFTEENMILE CREEK.f01 (steady flow) ---

Flow Title=Multiple
Number of Profiles=7
Profile Names=10-year,25-year,50-year,1pct_min,100-year,1pct_plu,500-year
River Rch & RM= TRIB 10_2 TO FIF,Reach-1,3515
     346     532     693     437     872    1739    1363
River Rch & RM= TRIB 10_2 TO FIF,Reach-1,974
     460     723     954     610    1216    2426    1956
Boundary for River Rch & Prof#=TRIB 10_2 TO FIF,Reach-1,1
Up Type=0
Dn Type=3
Dn Slope=0.005
Boundary for River Rch & Prof#=TRIB 10_2 TO FIF,Reach-1,2
Up Type=0
Dn Type=3
Dn Slope=0.005
Boundary for River Rch & Prof#=TRIB 10_2 TO FIF,Reach-1,3
Up Type=0
Dn Type=3
Dn Slope=0.005
Boundary for River Rch & Prof#=TRIB 10_2 TO FIF,Reach-1,4
Up Type=0
Dn Type=3
Dn Slope=0.005
Boundary for River Rch & Prof#=TRIB 10_2 TO FIF,Reach-1,5
Up Type=0
Dn Type=3
Dn Slope=0.005
Boundary for River Rch & Prof#=TRIB 10_2 TO FIF,Reach-1,6
Up Type=0
Dn Type=3
Dn Slope=0.005
Boundary for River Rch & Prof#=TRIB 10_2 TO FIF,Reach-1,7
Up Type=0
Dn Type=3
Dn Slope=0.005

--- TRIB 10_2 TO FIFTEENMILE CREEK.g01 (geometry) ---

Geom Title=Existing Conditions

River Reach=TRIB 10_2 TO FIF,Reach-1
Reach XY= 30
      2476975.00     13532975.00      2477016.23     13532918.33
      2476780.52     13532677.43      2476772.64     13532580.98
      2476727.36     13532519.02      2476721.45     13532426.30
      2476681.03     13532383.17      2476628.19     13532366.65
      2476608.53     13532258.27      2476484.68     13532135.78
      2476411.79     13532111.37      2476281.12     13531982.88
      2476180.47     13531969.74      2476158.26     13531908.55
      2475891.73     13531641.47      2475783.35     13531621.81
      2475745.41     13531544.74      2475635.97     13531485.38
      2475674.97     13531404.95      2475672.63     13531330.90
      2475632.56     13531275.00      2475673.63     13531214.56
      2475671.47     13531076.47      2475535.90     13530934.38
      2475519.52     13530880.26      2475414.94     13530864.60
      2475361.36     13530761.80      2475205.16     13530604.62
      2475085.34     13530535.12      2475075.00     13530325.00

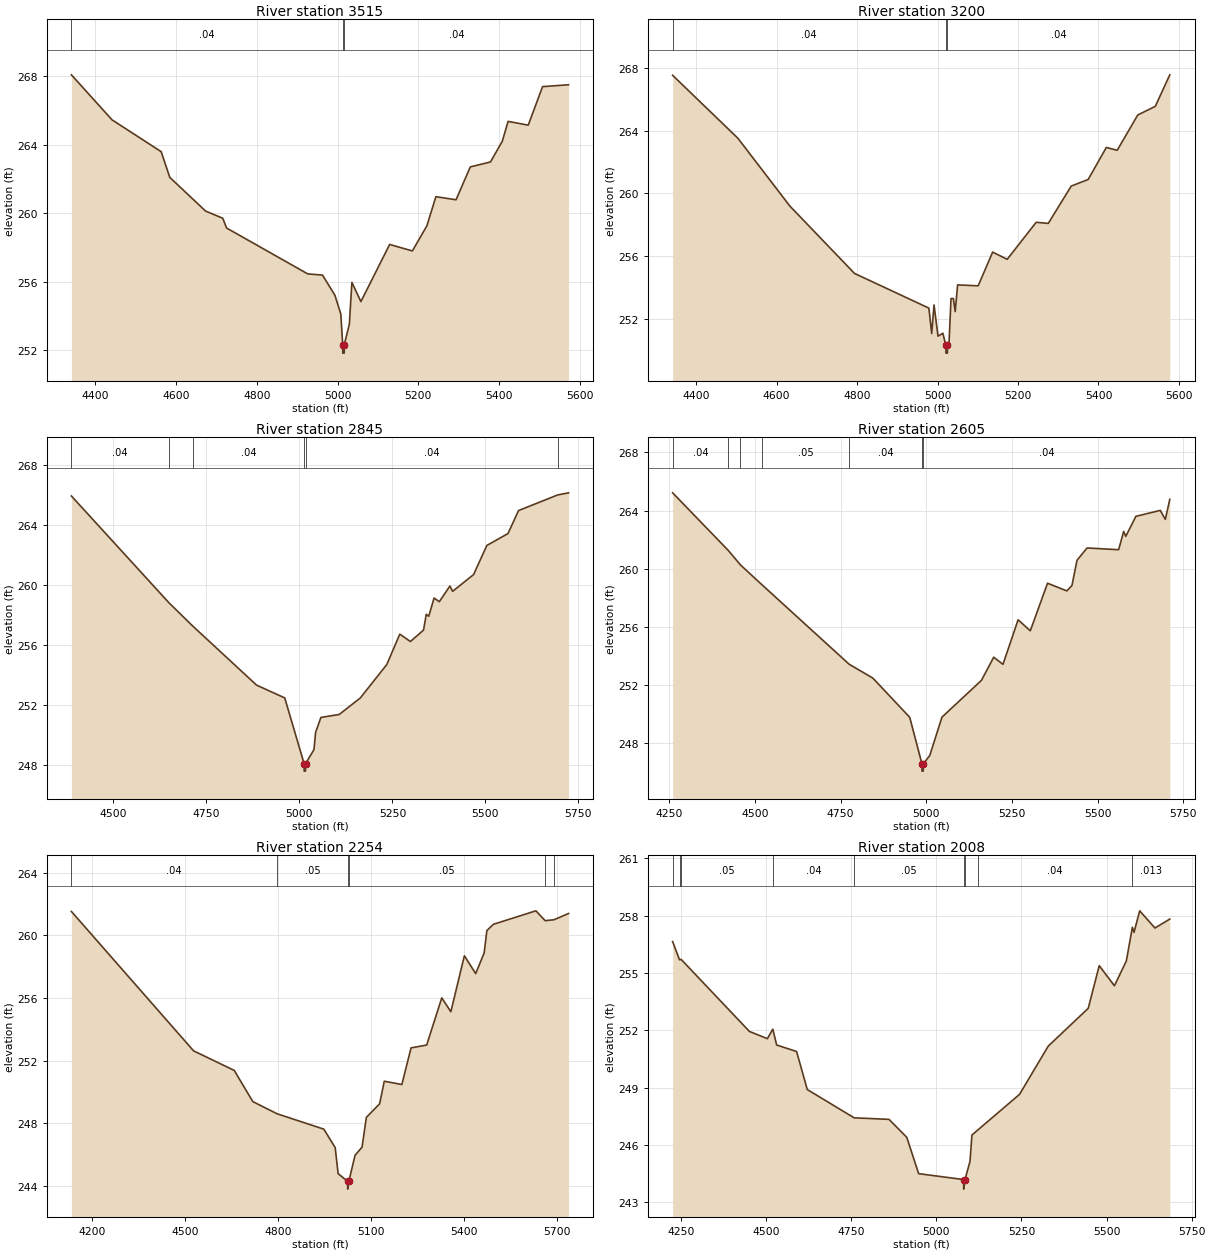
Type RM Length L Ch R = 1,3515,315,315,315
BEGIN DESCRIPTION:
TRIB 10_2 TO FIFTEENMILE CREEK 7.0
END DESCRIPTION:
XS GIS Cut Line= 3
      2477472.01     13532464.84      2476898.46     13532820.19
      2476455.84     13533156.83
#Sta/Elev= 30
  4341.1  268.09  4441.7  265.46  4563.4  263.60  4584.6  262.10  4673.3  260.13
  4715.8  259.71  4725.3  259.14  4926.1  256.46  4962.7  256.39  4993.5  255.21
  5008.1  254.11  5012.7  252.33  5013.0  251.83  5016.5  251.83  5016.7  252.33
  5029.2  253.52  5035.5  255.96  5057.8  254.84  5129.0  258.18  5185.2  257.80
  5221.2  259.27  5243.4  260.97  5293.3  260.79  5328.7  262.71  5378.6  263.00
  5407.7  264.20  5422.2  265.37  5472.1  265.15  5507.5  267.40  5571.9  267.51
#Mann=3,-1,0
  4341.1    0.04       0  5012.7    0.04       0  5016.7    0.04       0
Bank Sta=5012.7,5016.7
Exp/Cntr=0.3,0.1

Type RM Length L Ch R = 1,3200,355,355,355
BEGIN DESCRIPTION:
TRIB 10_2 TO FIFTEENMILE CREEK 6.0
END DESCRIPTION:
XS GIS Cut Line= 3
      2477325.03     13532224.98      2476725.00     13532575.00
      2476425.00     13533025.01
#Sta/Elev= 30
  4341.7  267.53  4503.8  263.52  4633.2  259.19  4793.7  254.90  4978.5  252.69
  4985.5  251.07  4991.3  252.89  5001.2  250.90  5013.2  251.09  5020.7  250.32
  5021.0  249.82  5024.5  249.82  5024.7  250.32  5028.5  250.42  5033.5  253.30
  5039.4  253.30  5043.9  252.47  5049.9  254.17  5101.0  254.11  5137.0  256.26
  5173.1  255.80  5245.2  258.16  5275.2  258.09  5332.3  260.47  5374.4  260.89
  5419.4  262.93  5446.5  262.75  5497.6  265.00  5541.1  265.55  5577.2  267.56
#Mann=3,-1,0
  4341.7    0.04       0  5020.7    0.04       0  5024.7    0.04       0
Bank Sta=5020.7,5024.7
Exp/Cntr=0.3,0.1

Type RM Length L Ch R = 1,2845,240,240,240
BEGIN DESCRIPTION:
Mapping XS 0205bf4e
END DESCRIPTION:
XS GIS Cut Line= 3
      2477185.48     13532037.83      2476582.30     13532285.94
      2476124.58     13532795.00
#Sta/Elev= 30
  4386.9  265.92  4649.1  258.82  4712.7  257.28  4884.8  253.34  4960.5  252.49
  5012.6  248.12  5012.8  247.62  5016.3  247.62  5016.6  248.12  5039.1  249.05
  5043.6  250.20  5057.8  251.19  5107.1  251.39  5163.9  252.49  5234.9  254.71
  5270.0  256.73  5298.4  256.24  5333.7  257.00  5341.1  258.05  5347.8  257.92
  5362.0  259.13  5376.2  258.89  5404.6  259.93  5412.1  259.58  5468.2  260.69
  5504.0  262.63  5560.8  263.42  5589.2  264.95  5694.4  265.99  5723.7  266.13
#Mann=6,-1,0
  4386.9    0.04       0  4649.1    0.05       0  4712.7    0.04       0
  5012.6    0.04       0  5016.6    0.04       0  5694.4    0.03       0
Bank Sta=5012.6,5016.6
Exp/Cntr=0.3,0.1

Type RM Length L Ch R = 1,2605,351,351,351
BEGIN DESCRIPTION:
Mapping XS e049dc18
END DESCRIPTION:
XS GIS Cut Line= 3
      2477121.29     13531849.62      2476449.69     13532106.28
      2476022.25     13532700.42
#Sta/Elev= 30
  4259.6  265.22  4421.6  261.26  4457.6  260.25  4520.5  258.88  4774.6  253.41
  4844.0  252.45  4951.5  249.75  4987.2  246.54  4987.4  246.04  4990.9  246.04
  4991.2  246.54  5010.0  247.12  5045.6  249.76  5161.0  252.30  5196.6  253.89
  5223.7  253.40  5267.8  256.47  5303.4  255.71  5353.7  258.99  5410.2  258.46
  5424.9  258.83  5439.7  260.57  5469.1  261.42  5561.2  261.30  5575.9  262.56
  5582.1  262.22  5611.5  263.60  5682.7  264.01  5697.4  263.39  5710.5  264.77
#Mann=7,-1,0
  4259.6    0.04       0  4421.6    0.05       0  4457.6    0.04       0
  4520.5    0.05       0  4774.6    0.04       0  4987.2    0.04       0
  4991.2    0.04       0
Bank Sta=4987.2,4991.2
Exp/Cntr=0.3,0.1

Type RM Length L Ch R = 1,2254,246,246,246
BEGIN DESCRIPTION:
Mapping XS 1b5ff195
END DESCRIPTION:
XS GIS Cut Line= 3
      2476933.04     13531520.24      2476175.91     13531930.89
      2475753.29     13532541.35
#Sta/Elev= 30
  4133.6  261.52  4527.7  252.62  4658.9  251.37  4718.8  249.38  4797.3  248.60
  4947.9  247.62  4984.6  246.44  4994.0  244.78  5024.6  244.29  5024.9  243.79
  5028.6  244.29  5048.6  245.95  5071.2  246.47  5085.1  248.37  5128.0  249.24
  5142.8  250.68  5199.6  250.47  5229.3  252.81  5279.7  252.99  5328.3  256.00
  5357.7  255.12  5401.3  258.69  5437.8  257.55  5465.1  258.87  5473.9  260.30
  5494.9  260.70  5632.0  261.56  5661.9  260.93  5690.4  260.99  5737.4  261.39
#Mann=6,-1,0
  4133.6    0.04       0  4797.3    0.05       0  5024.6    0.05       0
  5028.6    0.05       0  5661.9   0.013       0  5690.4    0.04       0
Bank Sta=5024.6,5028.6
Exp/Cntr=0.3,0.1

Type RM Length L Ch R = 1,2008,137,137,137
BEGIN DESCRIPTION:
Mapping XS 588ca208
END DESCRIPTION:
XS GIS Cut Line= 3
      2476667.89     13531357.65      2476013.36     13531742.67
      2475701.47     13532370.71
#Sta/Elev= 30
  4225.2  256.64  4245.4  255.69  4250.2  255.71  4450.8  251.94  4503.6  251.56
  4519.5  252.06  4530.8  251.23  4589.4  250.89  4620.8  248.90  4758.6  247.42
  4860.9  247.34  4913.1  246.40  4947.9  244.50  5080.1  244.19  5080.3  243.69
  5084.1  244.19  5098.8  245.14  5104.5  246.52  5122.2  246.79  5244.5  248.65
  5328.6  251.17  5446.2  253.15  5478.5  255.38  5523.1  254.33  5558.2  255.63
  5575.8  257.39  5580.6  257.12  5597.4  258.25  5642.2  257.35  5685.8  257.82
#Mann=9,-1,0
  4225.2    0.05       0  4245.4    0.04       0  4250.2    0.05       0
  4519.5    0.04       0  4758.6    0.05       0  5080.1    0.05       0
  5084.1    0.05       0  5122.2    0.04       0  5575.8   0.013       0
Bank Sta=5080.1,5084.1
Exp/Cntr=0.3,0.1

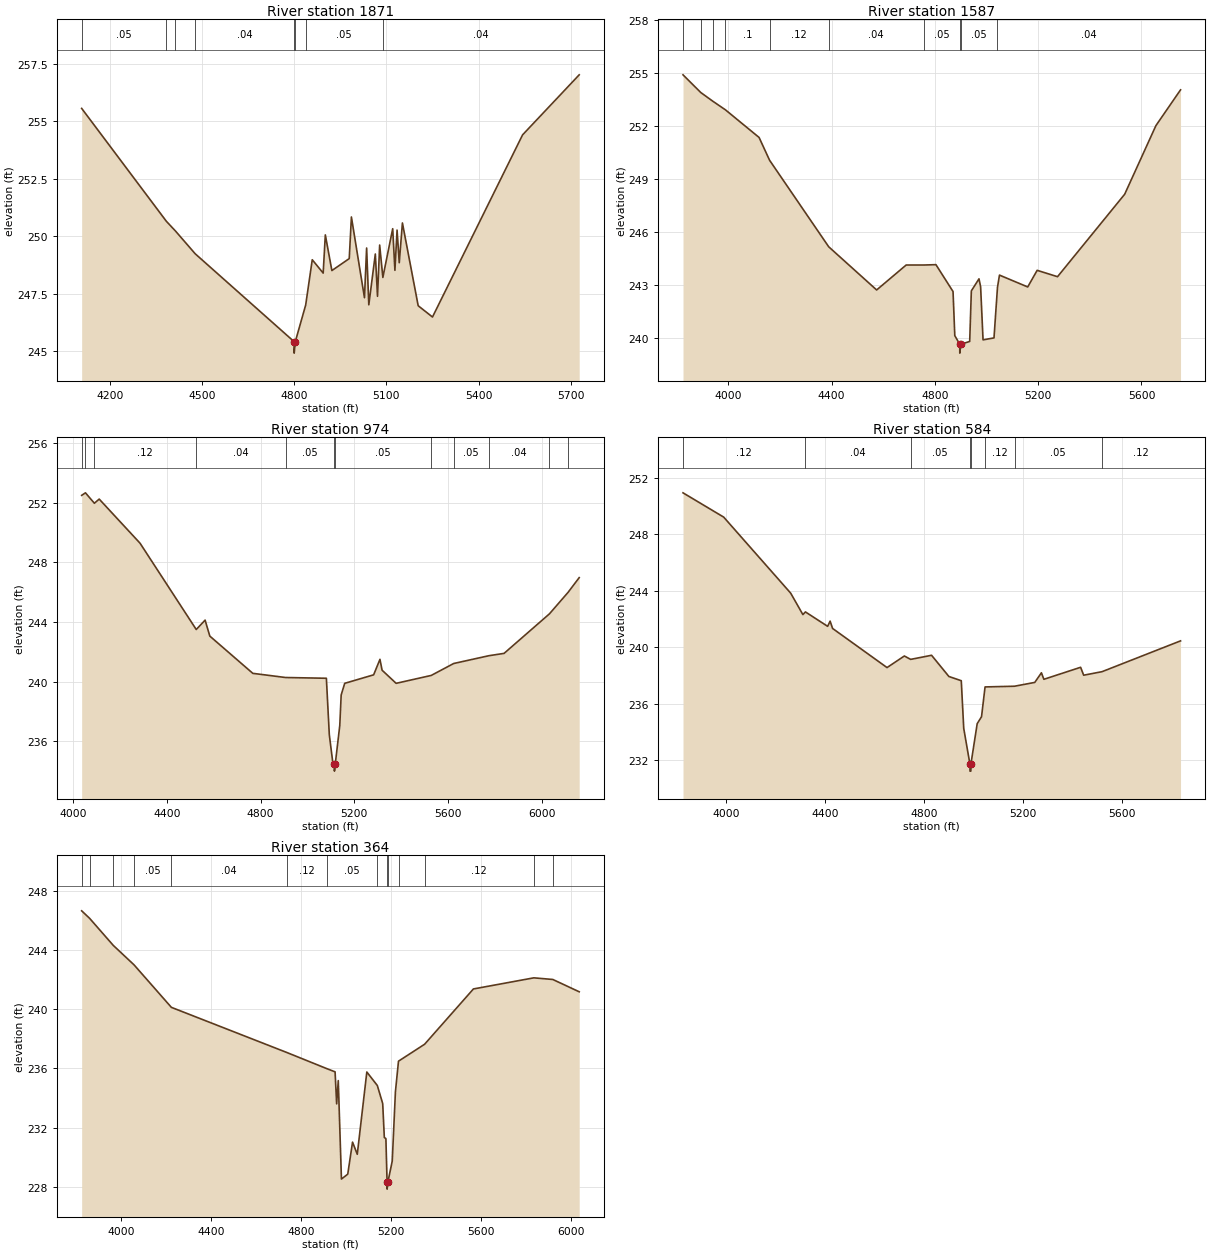
Type RM Length L Ch R = 1,1871,284,284,284
BEGIN DESCRIPTION:
Mapping XS 3bc6abb0
END DESCRIPTION:
XS GIS Cut Line= 5
      2476633.63     13531143.78      2476004.80     13531563.00
      2475803.75     13531768.33      2475778.08     13531823.94
      2475662.59     13532324.41
#Sta/Elev= 30
  4109.0  255.55  4384.6  250.64  4414.0  250.22  4478.2  249.23  4799.8  245.41
  4800.1  244.91  4803.8  245.41  4837.5  247.00  4858.9  248.97  4894.4  248.39
  4901.4  250.05  4922.7  248.50  4979.2  249.02  4986.2  250.83  5028.7  247.32
  5035.7  249.48  5042.8  247.01  5064.0  249.22  5071.1  247.38  5078.1  249.61
  5088.5  248.20  5120.5  250.32  5127.7  248.51  5134.7  250.26  5141.8  248.84
  5152.1  250.57  5203.4  246.97  5249.9  246.48  5542.9  254.40  5727.0  257.01
#Mann=8,-1,0
  4109.0    0.05       0  4384.6    0.12       0  4414.0    0.05       0
  4478.2    0.04       0  4799.8    0.05       0  4803.8    0.04       0
  4837.5    0.05       0  5088.5    0.04       0
Bank Sta=4799.8,4803.8
Exp/Cntr=0.3,0.1

Type RM Length L Ch R = 1,1587,613,613,613
BEGIN DESCRIPTION:
Mapping XS 140b2917
END DESCRIPTION:
XS GIS Cut Line= 4
      2476667.86     13530989.78      2475889.30     13531216.50
      2475538.52     13531772.61      2475559.91     13532230.22
#Sta/Elev= 30
  3824.9  254.89  3893.7  253.89  3941.1  253.39  3989.3  252.91  4119.5  251.35
  4160.2  250.06  4389.1  245.17  4574.7  242.73  4689.0  244.14  4756.7  244.14
  4804.3  244.16  4870.5  242.64  4877.3  240.15  4896.5  239.66  4896.7  239.16
  4900.5  239.66  4935.0  239.82  4941.4  242.68  4971.0  243.36  4977.3  242.91
  4986.7  239.91  5029.1  240.02  5042.6  242.88  5050.3  243.57  5159.7  242.90
  5196.2  243.84  5275.1  243.48  5535.1  248.14  5656.1  252.02  5751.4  254.04
#Mann=10,-1,0
  3824.9    0.12       0  3893.7     0.1       0  3941.1    0.05       0
  3989.3     0.1       0  4160.2    0.12       0  4389.1    0.04       0
  4756.7    0.05       0  4896.5    0.05       0  4900.5    0.05       0
  5042.6    0.04       0
Bank Sta=4896.5,4900.5
Exp/Cntr=0.3,0.1

Type RM Length L Ch R = 1,974,390,390,390
BEGIN DESCRIPTION:
Mapping XS e7c77561
END DESCRIPTION:
XS GIS Cut Line= 4
      2476569.45     13530904.22      2475628.36     13531002.61
      2475341.75     13531190.83      2475401.63     13532024.97
#Sta/Elev= 30
  4035.3  252.50  4051.5  252.67  4089.6  251.97  4110.2  252.25  4284.7  249.29
  4524.8  243.50  4562.6  244.13  4582.7  243.06  4766.4  240.56  4906.3  240.28
  5080.7  240.23  5093.2  236.44  5107.7  234.63  5114.8  234.50  5115.1  234.00
  5118.8  234.50  5137.9  237.06  5143.9  239.11  5159.0  239.89  5282.6  240.46
  5309.6  241.50  5318.7  240.77  5378.7  239.89  5528.7  240.42  5624.6  241.22
  5774.1  241.74  5839.9  241.90  6033.5  244.55  6113.0  245.99  6160.7  246.98
#Mann=12,-1,0
  4035.3    0.12       0  4051.5     0.1       0  4089.6    0.12       0
  4524.8    0.04       0  4906.3    0.05       0  5114.8    0.05       0
  5118.8    0.05       0  5528.7    0.12       0  5624.6    0.05       0
  5774.1    0.04       0  6033.5    0.03       0  6113.0    0.04       0
Bank Sta=5114.8,5118.8
Exp/Cntr=0.3,0.1

Type RM Length L Ch R = 1,584,220,220,220
BEGIN DESCRIPTION:
Mapping XS ff195d9e
END DESCRIPTION:
XS GIS Cut Line= 4
      2476539.51     13530805.83      2475375.97     13530763.06
      2475264.75     13530797.28      2475187.74     13531524.52
#Sta/Elev= 30
  3824.2  250.92  3988.8  249.20  4259.6  243.82  4309.0  242.30  4319.2  242.49
  4409.1  241.47  4419.1  241.84  4429.1  241.32  4649.3  238.55  4719.3  239.37
  4744.8  239.13  4829.4  239.42  4899.4  237.92  4949.5  237.62  4959.5  234.24
  4984.5  231.72  4984.8  231.22  4988.3  231.22  4988.5  231.72  5013.9  234.58
  5031.4  235.07  5045.7  237.18  5164.8  237.23  5246.7  237.50  5273.6  238.18
  5283.6  237.72  5432.1  238.57  5444.5  238.01  5518.9  238.26  5836.2  240.44
#Mann=8,-1,0
  3824.2    0.12       0  4319.2    0.04       0  4744.8    0.05       0
  4984.5    0.05       0  4988.5    0.05       0  5045.7    0.12       0
  5164.8    0.05       0  5518.9    0.12       0
Bank Sta=4984.5,4988.5
Exp/Cntr=0.3,0.1

Type RM Length L Ch R = 1,364,0,0,0
BEGIN DESCRIPTION:
Mapping XS c59ddb89
END DESCRIPTION:
XS GIS Cut Line= 4
      2476347.03     13530668.95      2475290.41     13530532.06
      2475025.19     13530788.72      2474918.46     13531561.45
#Sta/Elev= 30
  3822.9  246.63  3858.5  246.12  3963.5  244.30  4055.8  242.99  4222.2  240.12
  4735.3  237.08  4913.5  235.99  4950.9  235.77  4957.9  233.61  4965.1  235.18
  4979.2  228.54  5007.3  228.87  5028.6  231.03  5049.7  230.21  5092.2  235.76
  5138.9  234.85  5162.9  233.63  5170.1  231.34  5177.1  231.27  5182.3  228.36
  5182.5  227.86  5186.3  228.36  5205.4  229.76  5219.5  234.43  5233.2  236.49
  5349.3  237.63  5566.6  241.36  5835.6  242.11  5920.1  242.00  6037.5  241.17
#Mann=14,-1,0
  3822.9    0.12       0  3858.5    0.05       0  3963.5    0.12       0
  4055.8    0.05       0  4222.2    0.04       0  4735.3    0.12       0
  4913.5    0.05       0  5138.9    0.12       0  5182.3    0.05       0
  5186.3    0.12       0  5233.2    0.05       0  5349.3    0.12       0
  5835.6    0.05       0  5920.1    0.03       0
Bank Sta=5182.3,5186.3
Exp/Cntr=0.3,0.1

Chan Stop Cuts=-1