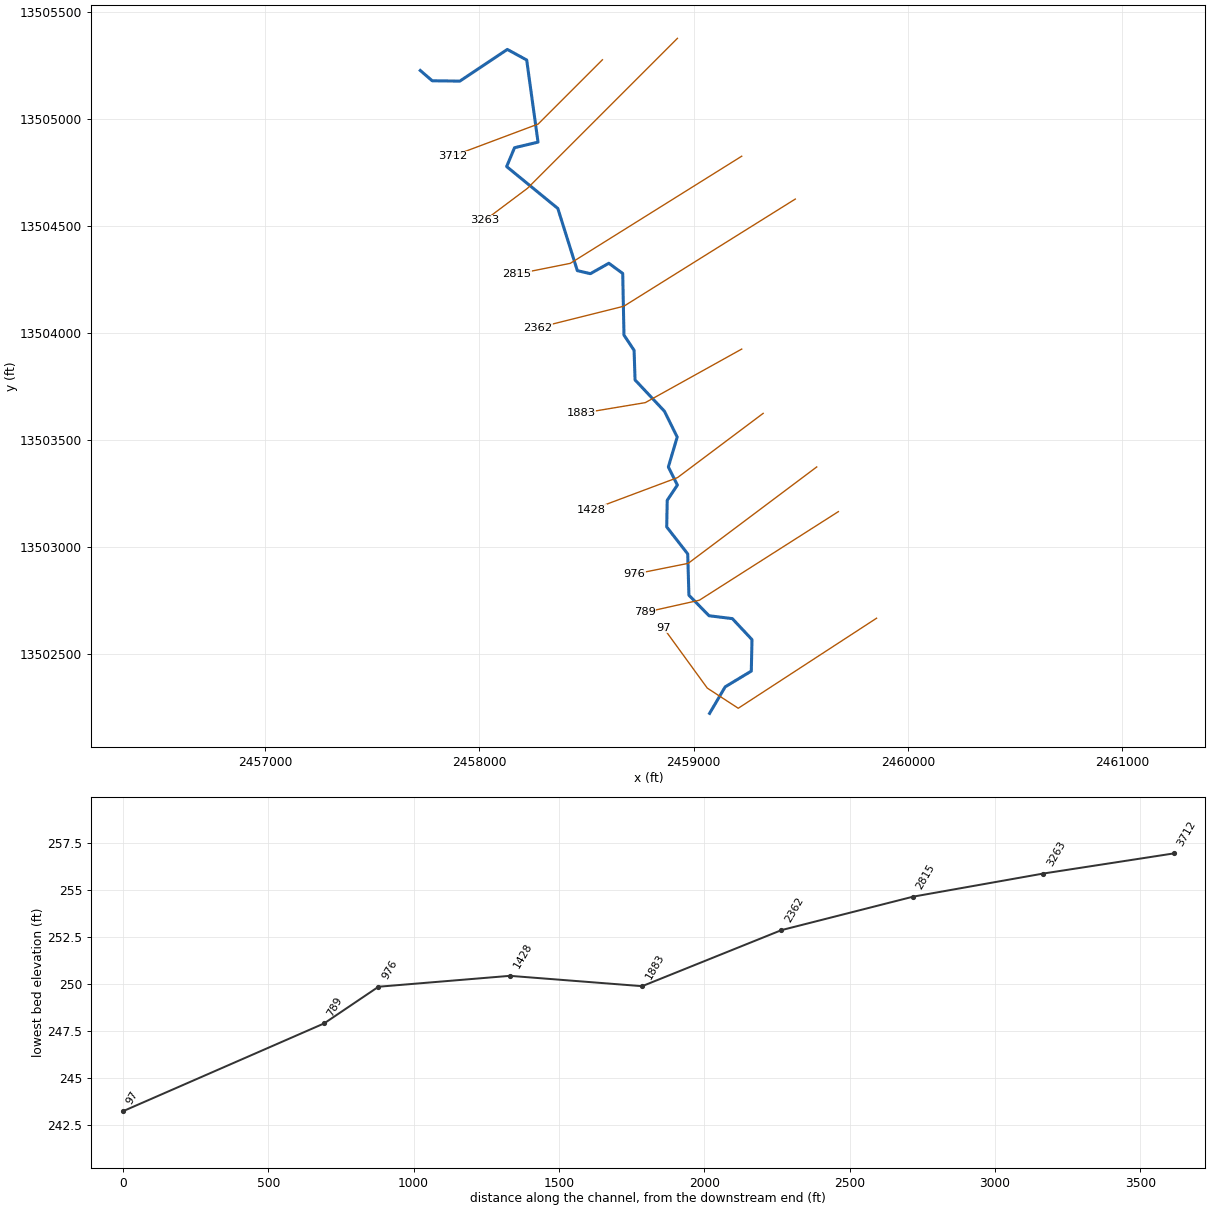
--- TRIB 11 TO EIGHTEENMILE CREEK.prj (project) ---

Proj Title=TRIB 11 TO EIGHTEENMILE CREEK Base Level Engineering
Current Plan=p01
Default Exp/Contr=0.3,0.1
English Units
Geom File=g01
Flow File=f01
Plan File=p01
Y Axis Title=Elevation
X Axis Title(PF)=Main Channel Distance
X Axis Title(XS)=Station
BEGIN DESCRIPTION:
TRIB 11 TO EIGHTEENMILE CREEK
END DESCRIPTION:
DSS Export Rating Curves= 0
DSS Export Rating Curve Sorted= 0
DSS Export Volume Flow Curves= 0
DXF OffsetX= 0
DXF OffsetY= 0
DXF ScaleX= 1
DXF ScaleY= 10

--- TRIB 11 TO EIGHTEENMILE CREEK.p01 (plan) ---

Plan Title=Multiple Run
Short Identifier=Multiple
Geom File=g01
Flow File=f01
Subcritical Flow
K Sum by GR= 0
Std Step Tol= 0.01
Critical Tol= 0.01
Num of Std Step Trials= 20
Max Error Tol= 0.3
Flow Tol Ratio= 0.001
Split Flow NTrial= 30
Split Flow Tol= 0.02
Split Flow Ratio= 0.02
Log Output Level= 0
Friction Slope Method= 1
Unsteady Friction Slope Method= 2
Unsteady Bridges Friction Slope Method= 1
Parabolic Critical Depth
Global Vel Dist=  1 , 1 , 1
Global Log Level= 0
CheckData=True
Encroach Param= -1, 0, 0, 0
BEGIN DESCRIPTION:
Multiple Run
END DESCRIPTION:

--- TRIB 11 TO EIGHTEENMILE CREEK.f01 (steady flow) ---

Flow Title=Multiple
Number of Profiles=7
Profile Names=10-year,25-year,50-year,1pct_min,100-year,1pct_plu,500-year
River Rch & RM= TRIB 11 TO EIGHT,Reach-1,3712
    1245    2085    2870    1908    3807    7597    6637
Boundary for River Rch & Prof#=TRIB 11 TO EIGHT,Reach-1,1
Up Type=0
Dn Type=3
Dn Slope=0.005
Boundary for River Rch & Prof#=TRIB 11 TO EIGHT,Reach-1,2
Up Type=0
Dn Type=3
Dn Slope=0.005
Boundary for River Rch & Prof#=TRIB 11 TO EIGHT,Reach-1,3
Up Type=0
Dn Type=3
Dn Slope=0.005
Boundary for River Rch & Prof#=TRIB 11 TO EIGHT,Reach-1,4
Up Type=0
Dn Type=3
Dn Slope=0.005
Boundary for River Rch & Prof#=TRIB 11 TO EIGHT,Reach-1,5
Up Type=0
Dn Type=3
Dn Slope=0.005
Boundary for River Rch & Prof#=TRIB 11 TO EIGHT,Reach-1,6
Up Type=0
Dn Type=3
Dn Slope=0.005
Boundary for River Rch & Prof#=TRIB 11 TO EIGHT,Reach-1,7
Up Type=0
Dn Type=3
Dn Slope=0.005

--- TRIB 11 TO EIGHTEENMILE CREEK.g01 (geometry) ---

Geom Title=Existing Conditions
Program Version=4.10

River Reach=TRIB 11 TO EIGHT,Reach-1
Reach XY= 30
        2457725.       13505225.      2457780.79     13505176.88
      2457909.84     13505175.37      2458131.16     13505323.26
      2458221.55     13505273.81      2458274.44     13504890.58
      2458164.82      13504864.6      2458128.08     13504776.67
      2458366.87     13504581.07      2458457.86     13504291.03
      2458518.84     13504276.79      2458604.98     13504325.44
      2458669.64     13504277.78      2458675.52     13503990.22
      2458722.73     13503919.06      2458727.24     13503780.91
      2458864.32     13503634.98      2458923.91     13503514.45
       2458882.6     13503374.99      2458924.85     13503290.42
      2458877.28     13503219.07      2458874.94     13503094.99
      2458972.93     13502969.14      2458978.53     13502776.45
      2459072.56     13502680.52      2459181.19     13502667.14
      2459272.96     13502569.15      2459269.65      13502422.3
      2459147.84     13502348.86        2459075.       13502225.

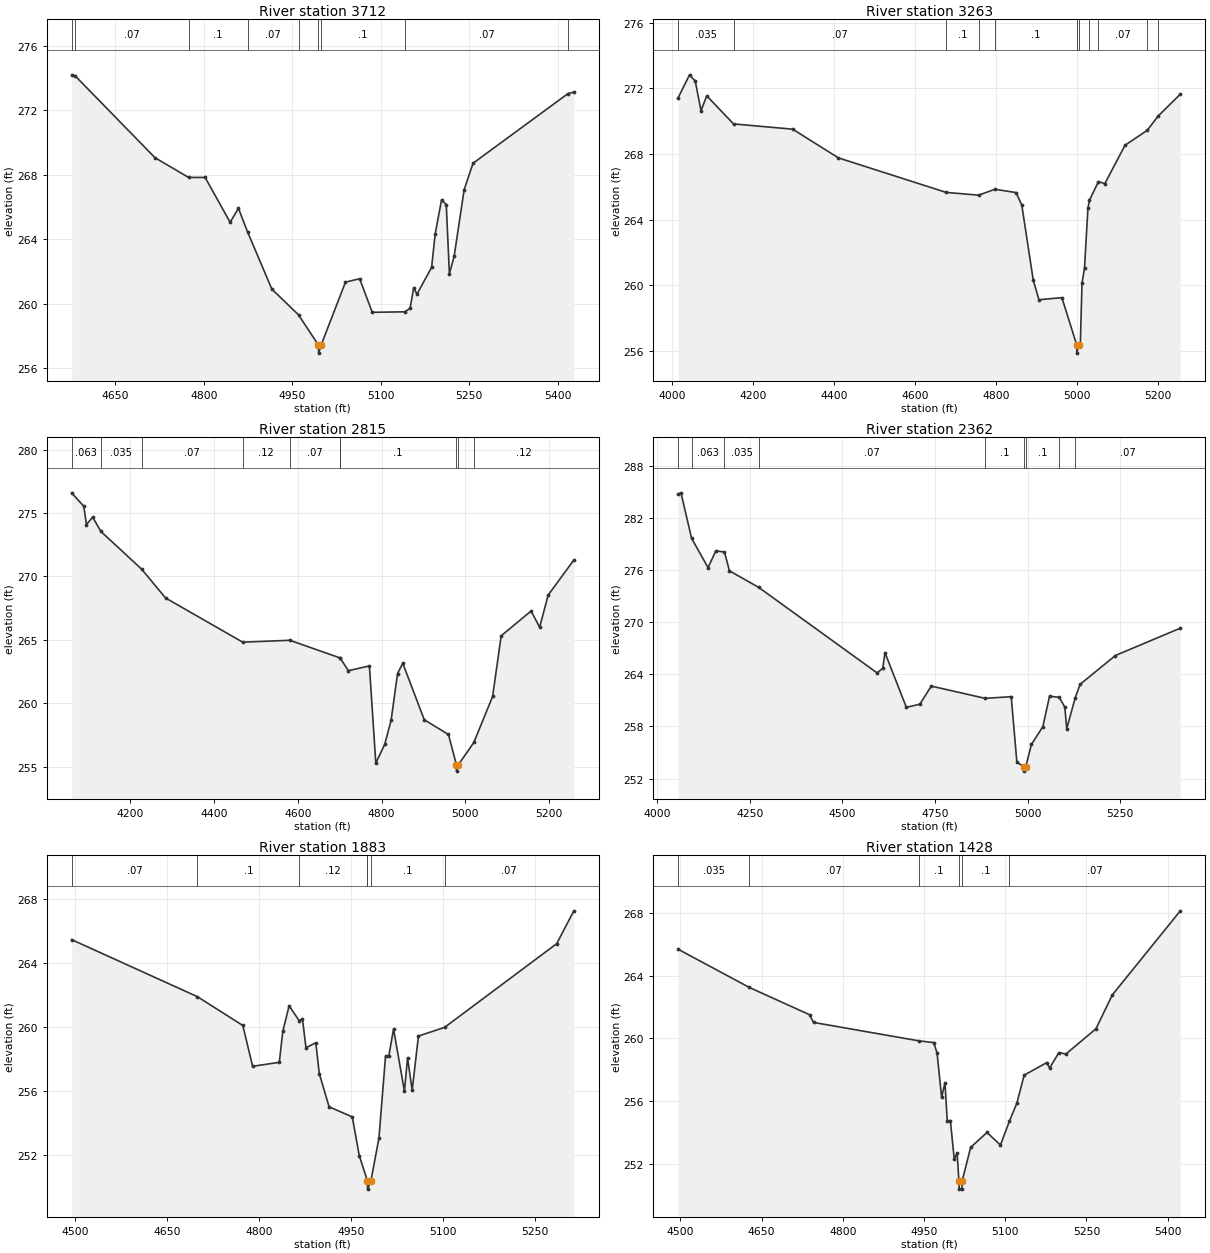
Type RM Length L Ch R = 1 ,3712    ,449,449,449
BEGIN DESCRIPTION:
TRIB 11 TO EIGHTEENMILE CREEK 8.0
END DESCRIPTION:
XS GIS Cut Line= 3
        2458575.       13505275.        2458275.       13504975.
      2457874.97     13504824.99
#Sta/Elev= 30
    4576  274.19  4581.8  274.13  4717.4  269.05  4774.3  267.83  4802.3  267.83
  4844.7  265.05  4858.8  265.92  4874.2  264.46  4915.4  260.91  4960.7  259.31
  4994.4  257.44  4994.8  256.94    4999  257.44  5040.3  261.34  5064.3  261.55
  5085.7  259.47  5140.5   259.5  5149.8  259.71    5156     261  5161.4  260.59
  5186.3  262.25  5192.5  264.35  5203.2  266.44  5211.2  266.14  5216.5  261.86
  5224.5  262.93  5241.5  267.07  5256.6  268.71  5417.7  273.03  5427.5  273.12
#Mann= 9 ,-1 , 0
    4576     .05       0  4581.8     .07       0  4774.3      .1       0
  4874.2     .07       0  4960.7      .1       0  4994.4     .05       0
    4999      .1       0  5140.5     .07       0  5417.7     .05       0
Bank Sta=4994.4,4999
XS Rating Curve= 0 ,0
Exp/Cntr=0.3,0.1

Type RM Length L Ch R = 1 ,3263    ,448,448,448
BEGIN DESCRIPTION:
TRIB 11 TO EIGHTEENMILE CREEK 7.0
END DESCRIPTION:
XS GIS Cut Line= 3
      2458924.97     13505374.97        2458225.       13504675.
        2458025.       13504525.
#Sta/Elev= 30
  4014.9  271.42  4043.1  272.82  4057.3  272.43  4071.4  270.64  4085.6  271.54
  4151.7  269.83  4297.7  269.51  4410.8  267.76  4676.6  265.66  4756.7  265.49
  4797.2  265.85  4849.2  265.65  4863.4  264.89  4891.7  260.32  4905.8  259.12
  4962.4  259.25    4999  256.37  4999.3  255.87  5003.6  256.37  5007.9  256.37
  5012.1  260.13  5018.3  261.06  5026.7  264.68  5030.5  265.18  5052.8  266.32
  5068.3  266.19  5118.3  268.53  5173.1  269.44  5200.5  270.32  5254.8  271.64
#Mann= 11 ,-1 , 0
  4014.9    .035       0  4151.7     .07       0  4676.6      .1       0
  4756.7     .07       0  4797.2      .1       0    4999     .05       0
  5003.6      .1       0  5030.5     .12       0  5052.8     .07       0
  5173.1     .05       0  5200.5     .07       0
Bank Sta=4999,5003.6
XS Rating Curve= 0 ,0
Exp/Cntr=0.3,0.1

Type RM Length L Ch R = 1 ,2815    ,453,453,453
BEGIN DESCRIPTION:
TRIB 11 TO EIGHTEENMILE CREEK 6.0
END DESCRIPTION:
XS GIS Cut Line= 3
      2459224.97     13504824.98        2458425.       13504325.
      2458175.01       13504275.
#Sta/Elev= 30
  4060.4  276.59  4089.3  275.53  4095.7  274.09  4110.5  274.67  4130.3  273.54
  4227.4  270.57  4284.4   268.3  4468.6  264.81  4581.1  264.96  4699.8  263.58
  4700.7  263.58  4720.7  262.56  4770.9  262.94  4786.2  255.27  4807.4  256.75
  4822.7  258.65  4838.1  262.34  4850.5  263.15  4901.8  258.69  4959.5  257.53
  4978.5  255.14  4978.8  254.64  4983.1  255.14  5020.1   256.9  5064.9  260.53
  5085.3  265.31  5156.7  267.27  5177.1  265.99  5197.5  268.53  5258.7  271.29
#Mann= 10 ,-1 , 0
  4060.4    .063       0  4130.3    .035       0  4227.4     .07       0
  4468.6     .12       0  4581.1     .07       0  4699.8     .12       0
  4700.7      .1       0  4978.5     .05       0  4983.1      .1       0
  5020.1     .12       0
Bank Sta=4978.5,4983.1
XS Rating Curve= 0 ,0
Exp/Cntr=0.3,0.1

Type RM Length L Ch R = 1 ,2362    ,479,479,479
BEGIN DESCRIPTION:
TRIB 11 TO EIGHTEENMILE CREEK 5.0
END DESCRIPTION:
XS GIS Cut Line= 3
        2459475.       13504625.        2458675.       13504125.
      2458275.01       13504025.
#Sta/Elev= 30
  4056.6  284.78  4064.3   284.9    4093  279.66  4137.4  276.29  4158.6  278.23
  4181.8  278.08  4195.2  275.92  4274.3  274.01  4593.7  264.17  4609.1   264.7
    4615   266.5  4672.8   260.2  4709.3  260.57    4740  262.65  4885.4  261.24
  4955.8  261.43  4971.1  253.91  4989.5  253.36    4990  252.86  4995.1  253.36
  5010.3  255.93  5041.2  257.98  5059.3  261.48  5085.5  261.36  5100.5  260.23
  5105.7  257.75  5128.7  261.32  5141.7  262.85  5237.1  266.17  5412.3  269.32
#Mann= 9 ,-1 , 0
  4056.6     .07       0    4093    .063       0  4181.8    .035       0
  4274.3     .07       0  4885.4      .1       0  4989.5     .05       0
  4995.1      .1       0  5085.5     .12       0  5128.7     .07       0
Bank Sta=4989.5,4995.1
XS Rating Curve= 0 ,0
Exp/Cntr=0.3,0.1

Type RM Length L Ch R = 1 ,1883    ,455,455,455
BEGIN DESCRIPTION:
TRIB 11 TO EIGHTEENMILE CREEK 4.0
END DESCRIPTION:
XS GIS Cut Line= 3
        2459225.       13503925.        2458775.       13503675.
      2458475.02       13503625.
#Sta/Elev= 30
  4493.9  265.46  4698.9   261.9    4773   260.1    4789  257.55  4832.5   257.8
  4838.2  259.73  4848.5  261.33  4865.1  260.39  4870.3  260.51    4876  258.71
    4892  259.02  4897.7   257.1  4913.7  255.02  4951.5  254.39  4962.9  251.97
  4975.8  250.45  4976.1  250.38  4976.5  249.88  4981.8  250.38    4995  253.07
  5005.8  258.21  5011.2  258.21  5018.8  259.88  5036.6  255.99  5041.6  258.07
  5049.2  256.06  5059.4  259.44    5102  259.98  5284.9  265.21  5312.8  267.26
#Mann= 7 ,-1 , 0
  4493.9     .07       0  4698.9      .1       0  4865.1     .12       0
  4975.8      .1       0  4976.1     .05       0  4981.8      .1       0
    5102     .07       0
Bank Sta=4976.1,4981.8
XS Rating Curve= 0 ,0
Exp/Cntr=0.3,0.1

Type RM Length L Ch R = 1 ,1428    ,452,452,452
BEGIN DESCRIPTION:
TRIB 11 TO EIGHTEENMILE CREEK 3.0
END DESCRIPTION:
XS GIS Cut Line= 3
      2459325.01     13503625.01        2458925.       13503325.
      2458525.02     13503175.01
#Sta/Elev= 30
    4496  265.67  4627.6  263.24  4738.7  261.51    4746  261.02  4940.6  259.85
  4967.9  259.74  4974.1  259.08  4982.5  256.26  4988.7  257.19  4992.9  254.78
  4998.7  254.78  5005.8  252.33  5011.1  252.73  5014.5  250.93  5014.9  250.43
  5019.8  250.43  5020.3  250.93  5036.1  253.08  5066.3  254.03  5091.2  253.23
  5107.8  254.76  5121.5   255.9  5134.9  257.67  5176.7  258.47    5182  258.12
  5198.9   259.1  5212.3  259.02  5267.5  260.62  5297.7  262.77  5423.2  268.11
#Mann= 6 ,-1 , 0
    4496    .035       0  4627.6     .07       0  4940.6      .1       0
  5014.5     .05       0  5020.3      .1       0  5107.8     .07       0
Bank Sta=5014.5,5020.3
XS Rating Curve= 0 ,0
Exp/Cntr=0.3,0.1

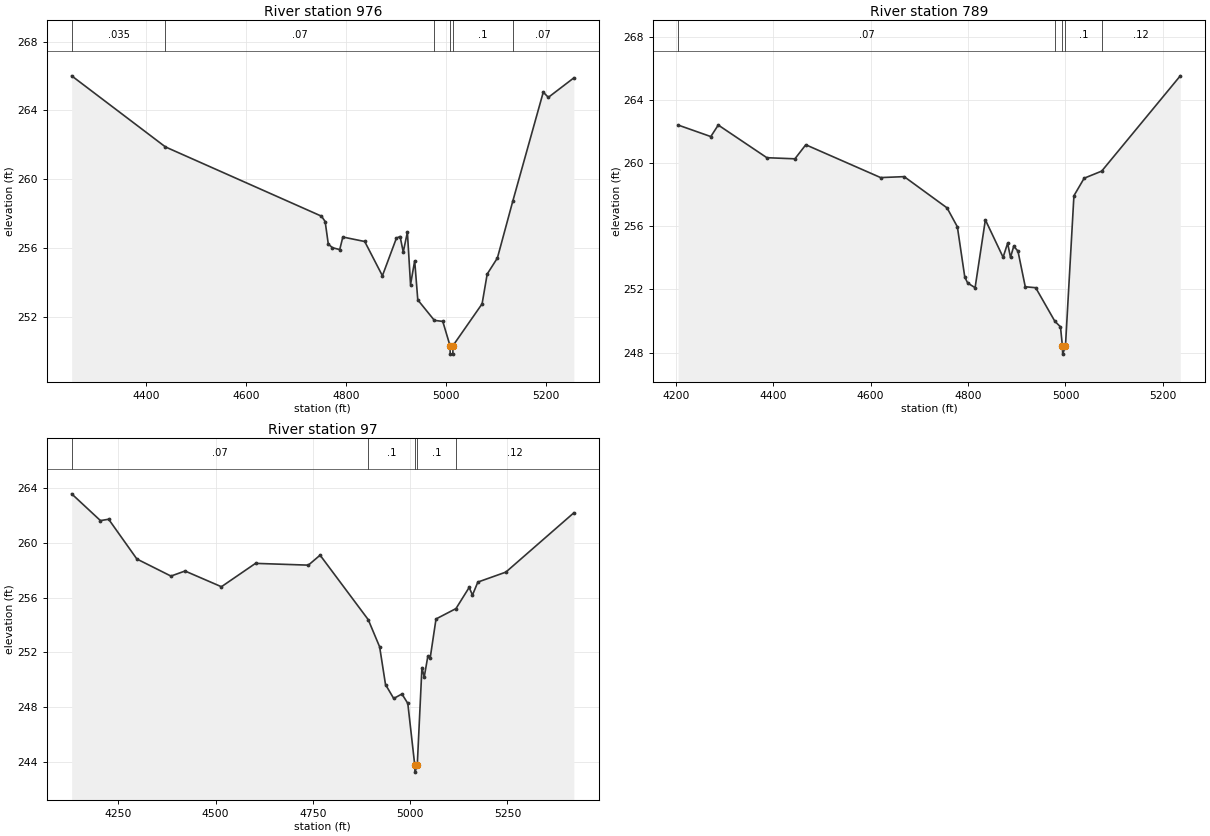
Type RM Length L Ch R = 1 ,976     ,187,187,187
BEGIN DESCRIPTION:
TRIB 11 TO EIGHTEENMILE CREEK 2.0
END DESCRIPTION:
XS GIS Cut Line= 3
      2459575.03     13503375.02        2458975.       13502925.
      2458724.99       13502875.
#Sta/Elev= 30
  4250.5  266.01  4438.3  261.88  4750.5  257.86  4757.8  257.55  4764.1  256.24
  4772.4  256.03    4787  255.92  4793.2  256.65    4837  256.39  4872.4   254.4
  4900.5  256.59  4907.8  256.68  4914.1  255.78  4922.4  256.93  4928.7  253.89
    4937  255.27  4943.2     253  4976.4  251.81  4993.2  251.75  5007.6  250.35
  5008.1  249.85  5013.3  249.85  5013.8  250.35  5071.9  252.77  5082.1   254.5
  5102.5  255.43  5133.2  258.72  5194.3  265.06  5204.5  264.76  5255.5  265.89
#Mann= 6 ,-1 , 0
  4250.5    .035       0  4438.3     .07       0  4976.4      .1       0
  5007.6     .05       0  5013.8      .1       0  5133.2     .07       0
Bank Sta=5007.6,5013.8
XS Rating Curve= 0 ,0
Exp/Cntr=0.3,0.1

Type RM Length L Ch R = 1 ,789     ,692,692,692
BEGIN DESCRIPTION:
Mapping XS 61b464a4
END DESCRIPTION:
XS GIS Cut Line= 3
        2459676.     13503166.45      2459027.29     13502753.03
      2458771.86     13502695.89
#Sta/Elev= 30
  4204.7  262.42  4271.8  261.69  4287.1  262.42  4386.9  260.35  4444.5  260.28
  4466.8  261.17  4620.5  259.09  4668.8  259.15  4756.8  257.17    4778  255.97
  4793.2  252.79  4799.1  252.41  4814.4  252.11  4835.5  256.41  4871.9  254.04
  4881.2  254.93  4887.1  254.03  4893.7  254.74  4902.4  254.43  4917.4  252.17
  4938.8  252.11  4978.2  249.98  4989.7  249.63  4993.7   248.4  4994.2   247.9
  4999.9   248.4  5017.3  257.94  5038.3  259.05  5074.3   259.5  5235.7  265.54
#Mann= 5 ,-1 , 0
  4204.7     .07       0  4978.2      .1       0  4993.7     .05       0
  4999.9      .1       0  5074.3     .12       0
Bank Sta=4993.7,4999.9
XS Rating Curve= 0 ,0
Exp/Cntr=0.3,0.1

Type RM Length L Ch R = 1 ,97      ,0,0,0
BEGIN DESCRIPTION:
TRIB 11 TO EIGHTEENMILE CREEK 1.0
END DESCRIPTION:
XS GIS Cut Line= 4
      2459854.14     13502669.01      2459208.79     13502248.86
      2459064.26     13502342.97       2458859.6      13502624.5
#Sta/Elev= 30
  4129.9   263.6  4203.9  261.64    4225  261.74  4297.5  258.83  4385.1  257.58
  4421.3  257.95  4514.8   256.8  4602.4  258.51  4738.2  258.38  4768.4  259.11
  4892.1  254.39  4921.4   252.4  4936.5  249.64  4957.6  248.62  4978.7  248.95
  4993.8  248.26  5011.7  243.73  5012.2  243.23  5018.1  243.73  5030.1  250.88
    5036  250.19  5045.2   251.7  5051.2  251.56  5066.3  254.44  5117.6   255.2
  5151.5  256.75    5160  256.19  5173.8  257.14  5245.8  257.87  5420.5  262.21
#Mann= 5 ,-1 , 0
  4129.9     .07       0  4892.1      .1       0  5011.7     .05       0
  5018.1      .1       0  5117.6     .12       0
Bank Sta=5011.7,5018.1
XS Rating Curve= 0 ,0
Exp/Cntr=0.3,0.1

Chan Stop Cuts=-1
Use User Specified Reach Order=0
Composite Channel Slope=5