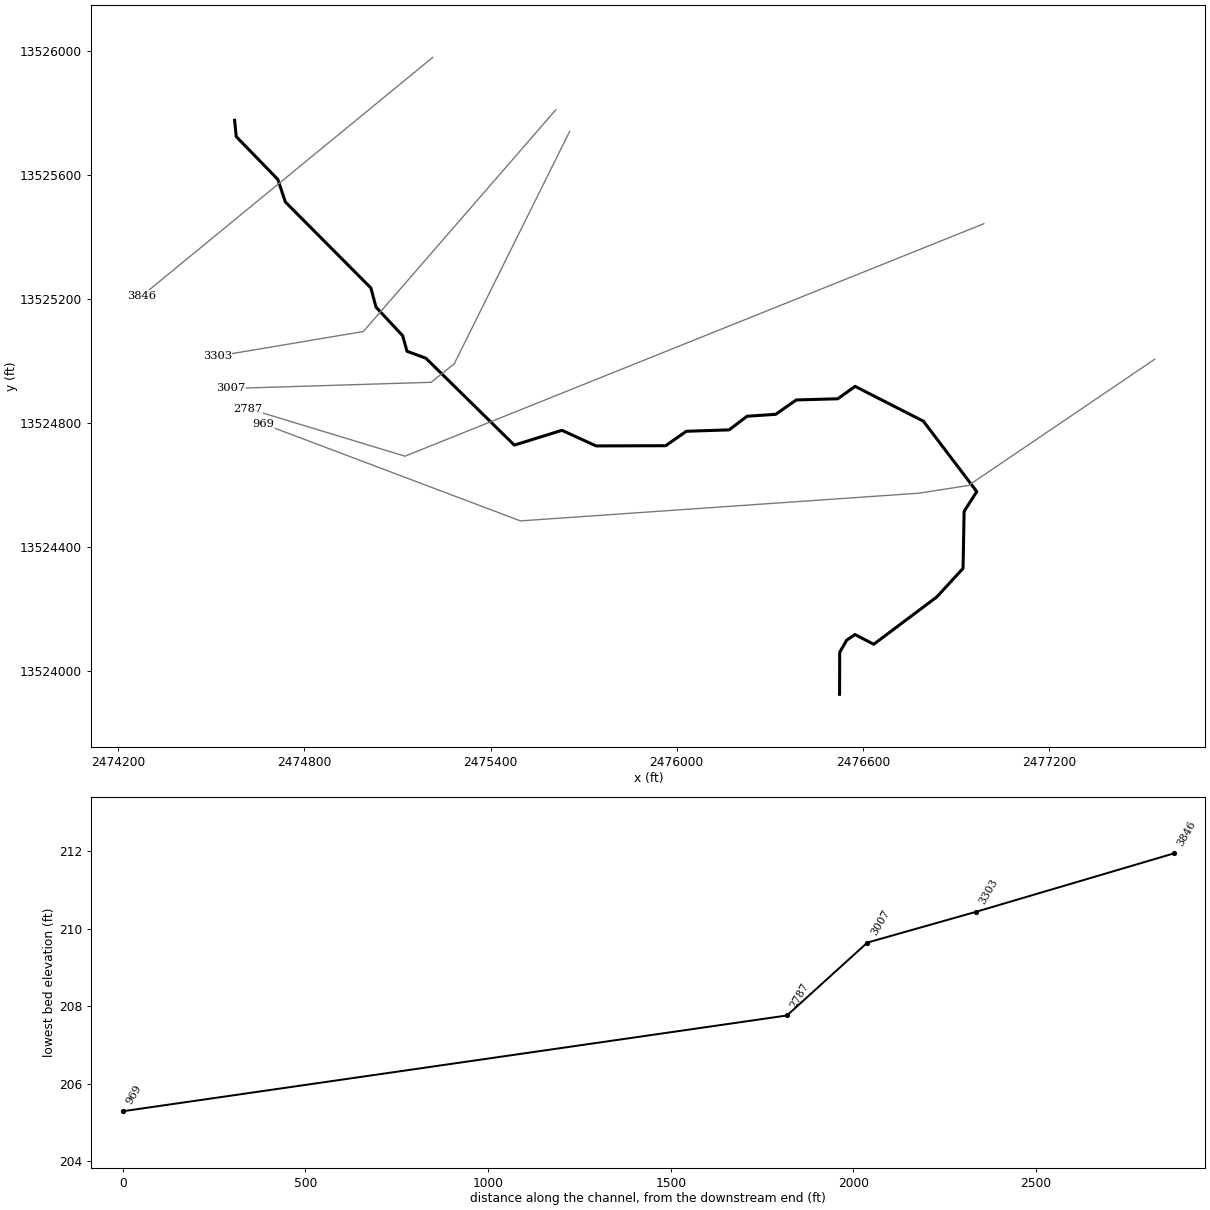
--- TRIB 11 TO FIFTEENMILE CREEK.prj (project) ---

Proj Title=TRIB 11 TO FIFTEENMILE CREEK Base Level Engineering
Current Plan=p01
Default Exp/Contr=0.3,0.1
English Units
Geom File=g01
Flow File=f01
Plan File=p01
BEGIN DESCRIPTION:
TRIB 11 TO FIFTEENMILE CREEK
END DESCRIPTION:

--- TRIB 11 TO FIFTEENMILE CREEK.p01 (plan) ---

Plan Title=Multiple Run
Short Identifier=Multiple
Geom File=g01
Flow File=f01
Subcritical Flow
K Sum by GR= 0
Std Step Tol= 0.01
Critical Tol= 0.01
Num of Std Step Trials= 20
Max Error Tol= 0.3
Flow Tol Ratio= 0.001
Split Flow NTrial= 30
Split Flow Tol= 0.02
Split Flow Ratio= 0.02
Log Output Level= 0
Friction Slope Method= 1
Unsteady Friction Slope Method= 2
Unsteady Bridges Friction Slope Method= 1
Parabolic Critical Depth
Global Vel Dist=  1 , 1 , 1
Global Log Level= 0
CheckData=True
Encroach Param= -1, 0, 0, 0
BEGIN DESCRIPTION:
Multiple Run
END DESCRIPTION:

--- TRIB 11 TO FIFTEENMILE CREEK.f01 (steady flow) ---

Flow Title=Multiple
Number of Profiles=7
Profile Names=10-year,25-year,50-year,1pct_min,100-year,1pct_plu,500-year
River Rch & RM= TRIB 11 TO FIFTE,Reach-1,3846
     357     551     719     454     906    1807    1422
Boundary for River Rch & Prof#=TRIB 11 TO FIFTE,Reach-1,1
Up Type=0
Dn Type=3
Dn Slope=0.005
Boundary for River Rch & Prof#=TRIB 11 TO FIFTE,Reach-1,2
Up Type=0
Dn Type=3
Dn Slope=0.005
Boundary for River Rch & Prof#=TRIB 11 TO FIFTE,Reach-1,3
Up Type=0
Dn Type=3
Dn Slope=0.005
Boundary for River Rch & Prof#=TRIB 11 TO FIFTE,Reach-1,4
Up Type=0
Dn Type=3
Dn Slope=0.005
Boundary for River Rch & Prof#=TRIB 11 TO FIFTE,Reach-1,5
Up Type=0
Dn Type=3
Dn Slope=0.005
Boundary for River Rch & Prof#=TRIB 11 TO FIFTE,Reach-1,6
Up Type=0
Dn Type=3
Dn Slope=0.005
Boundary for River Rch & Prof#=TRIB 11 TO FIFTE,Reach-1,7
Up Type=0
Dn Type=3
Dn Slope=0.005

--- TRIB 11 TO FIFTEENMILE CREEK.g01 (geometry) ---

Geom Title=Existing Conditions

River Reach=TRIB 11 TO FIFTE,Reach-1
Reach XY= 30
      2474575.00     13525775.00      2474580.31     13525722.48
      2474714.22     13525584.68      2474738.63     13525511.79
      2475014.22     13525234.68      2475030.87     13525172.72
      2475116.70     13525080.74      2475130.62     13525030.62
      2475191.48     13525008.27      2475476.63     13524728.13
      2475630.03     13524775.80      2475740.22     13524725.52
      2475964.50     13524726.22      2476030.94     13524772.73
      2476169.06     13524777.27      2476226.60     13524821.14
      2476319.02     13524827.36      2476385.51     13524873.77
      2476519.14     13524877.47      2476575.01     13524917.47
      2476795.13     13524805.23      2476967.19     13524578.41
      2476926.39     13524514.57      2476922.95     13524330.84
      2476838.24     13524238.62      2476634.99     13524086.25
      2476574.76     13524117.54      2476547.86     13524099.44
      2476525.31     13524060.16      2476525.00     13523925.00

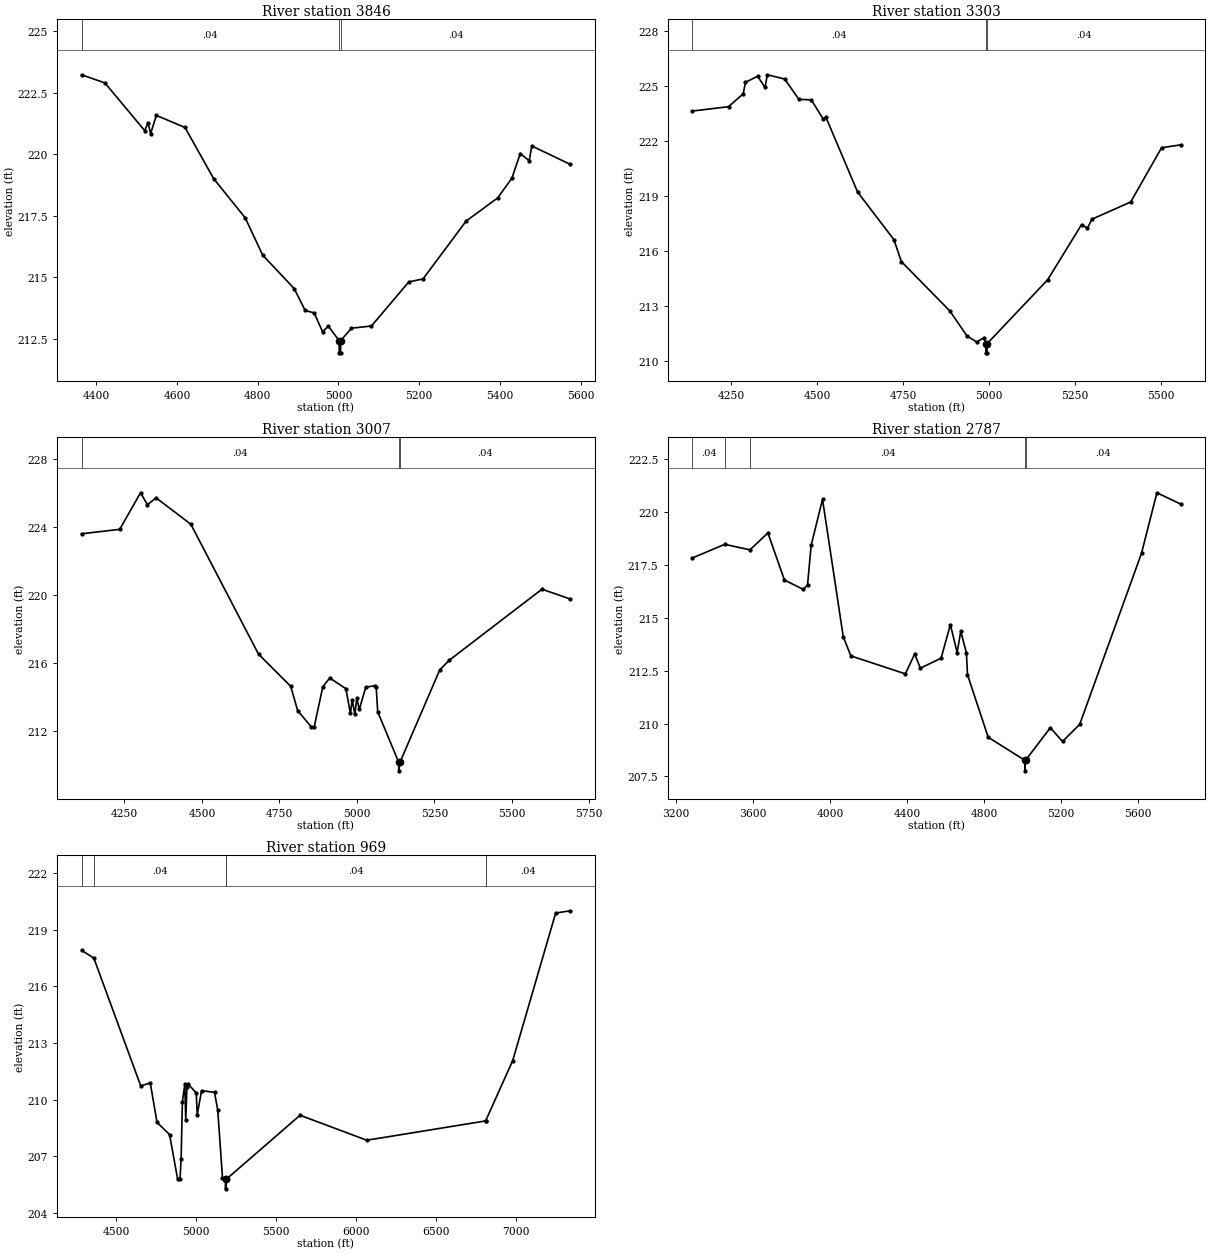
Type RM Length L Ch R = 1,3846,543,543,543
BEGIN DESCRIPTION:
LGII4600
END DESCRIPTION:
XS GIS Cut Line= 2
      2475213.36     13525977.73      2474276.29     13525209.22
#Sta/Elev= 30
  4363.0  223.23  4420.8  222.90  4519.8  220.96  4527.7  221.29  4534.2  220.84
  4548.5  221.58  4619.5  221.09  4690.6  219.01  4768.8  217.42  4811.9  215.91
  4890.1  214.55  4917.4  213.66  4939.6  213.56  4960.5  212.80  4974.8  213.02
  5001.5  212.44  5001.8  211.94  5005.3  211.94  5005.5  212.44  5032.2  212.94
  5081.7  213.03  5174.3  214.82  5209.5  214.94  5316.4  217.29  5394.6  218.23
  5429.8  219.03  5450.6  220.03  5472.8  219.74  5479.3  220.34  5574.9  219.59
#Mann=3,-1,0
  4363.0    0.04       0  5001.5    0.04       0  5005.5    0.04       0
Bank Sta=5001.5,5005.5
Exp/Cntr=0.3,0.1

Type RM Length L Ch R = 1,3303,296,296,296
BEGIN DESCRIPTION:
LGII4599
END DESCRIPTION:
XS GIS Cut Line= 3
      2475610.40     13525809.00      2474990.05     13525094.35
      2474519.32     13525015.07
#Sta/Elev= 30
  4135.5  223.62  4241.5  223.86  4284.2  224.56  4290.9  225.19  4326.2  225.52
  4347.9  224.91  4354.5  225.60  4404.9  225.37  4446.6  224.26  4482.7  224.23
  4517.8  223.17  4524.8  223.30  4617.5  219.20  4723.4  216.60  4744.8  215.41
  4886.3  212.71  4935.7  211.36  4964.1  211.02  4986.0  211.26  4990.6  210.93
  4990.9  210.43  4994.4  210.43  4994.6  210.93  5170.7  214.41  5269.5  217.42
  5286.7  217.23  5299.9  217.72  5412.8  218.66  5502.7  221.62  5559.2  221.78
#Mann=3,-1,0
  4135.5    0.04       0  4990.6    0.04       0  4994.6    0.04       0
Bank Sta=4990.6,4994.6
Exp/Cntr=0.3,0.1

Type RM Length L Ch R = 1,3007,220,220,220
BEGIN DESCRIPTION:
LGII4598
END DESCRIPTION:
XS GIS Cut Line= 4
      2475655.10     13525739.56      2475282.86     13524990.13
      2475208.42     13524930.58      2474563.24     13524910.73
#Sta/Elev= 30
  4111.4  223.58  4234.5  223.84  4301.7  225.99  4324.1  225.29  4352.1  225.69
  4464.1  224.14  4682.6  216.50  4786.4  214.61  4808.8  213.18  4853.4  212.21
  4861.9  212.20  4889.8  214.57  4912.2  215.10  4964.5  214.47  4978.9  213.03
  4985.3  213.80  4993.3  212.96  4999.7  213.90  5007.7  213.25  5028.6  214.56
  5056.9  214.64  5062.2  214.57  5067.2  213.11  5135.0  210.14  5135.2  209.64
  5139.0  210.14  5267.0  215.56  5297.1  216.13  5597.2  220.32  5689.0  219.74
#Mann=3,-1,0
  4111.4    0.04       0  5135.0    0.04       0  5139.0    0.04       0
Bank Sta=5135,5139
Exp/Cntr=0.3,0.1

Type RM Length L Ch R = 1,2787,1818,1818,1818
BEGIN DESCRIPTION:
LGII4597
END DESCRIPTION:
XS GIS Cut Line= 3
      2476990.06     13525441.74      2475124.05     13524692.36
      2474618.93     13524845.88
#Sta/Elev= 30
  3284.0  217.83  3453.5  218.48  3584.5  218.22  3677.4  219.02  3763.6  216.79
  3860.6  216.35  3883.3  216.55  3902.1  218.43  3961.2  220.61  4068.8  214.11
  4108.4  213.20  4391.4  212.35  4439.8  213.29  4469.4  212.62  4577.0  213.09
  4625.3  214.68  4660.3  213.36  4679.1  214.36  4708.7  213.34  4714.1  212.31
  4821.6  209.35  5011.7  208.26  5011.9  207.76  5015.7  208.26  5144.3  209.80
  5207.6  209.15  5297.0  209.96  5617.9  218.06  5697.8  220.92  5822.8  220.38
#Mann=5,-1,0
  3284.0    0.04       0  3453.5    0.03       0  3584.5    0.04       0
  5011.7    0.04       0  5015.7    0.04       0
Bank Sta=5011.7,5015.7
Exp/Cntr=0.3,0.1

Type RM Length L Ch R = 1,969,0,0,0
BEGIN DESCRIPTION:
LGII4596
END DESCRIPTION:
XS GIS Cut Line= 5
      2477540.93     13525005.01      2476940.45     13524598.07
      2476781.64     13524573.25      2475496.26     13524483.92
      2474668.78     13524796.09
#Sta/Elev= 30
  4283.5  217.90  4360.3  217.49  4654.0  210.73  4713.5  210.89  4755.8  208.80
  4834.3  208.16  4884.6  205.81  4899.6  205.82  4906.7  206.88  4914.5  209.89
  4929.5  210.81  4935.5  208.91  4943.0  210.70  4950.5  210.83  5001.4  210.36
  5007.2  209.20  5034.6  210.48  5115.6  210.39  5135.9  209.44  5165.4  205.88
  5184.3  205.79  5184.5  205.29  5188.3  205.79  5650.8  209.18  6068.4  207.86
  6812.2  208.88  6812.5  208.89  6981.5  212.07  7250.3  219.87  7342.5  219.99
#Mann=6,-1,0
  4283.5    0.03       0  4360.3    0.04       0  5184.3    0.04       0
  5188.3    0.04       0  6812.2    0.12       0  6812.5    0.04       0
Bank Sta=5184.3,5188.3
Exp/Cntr=0.3,0.1

Chan Stop Cuts=-1