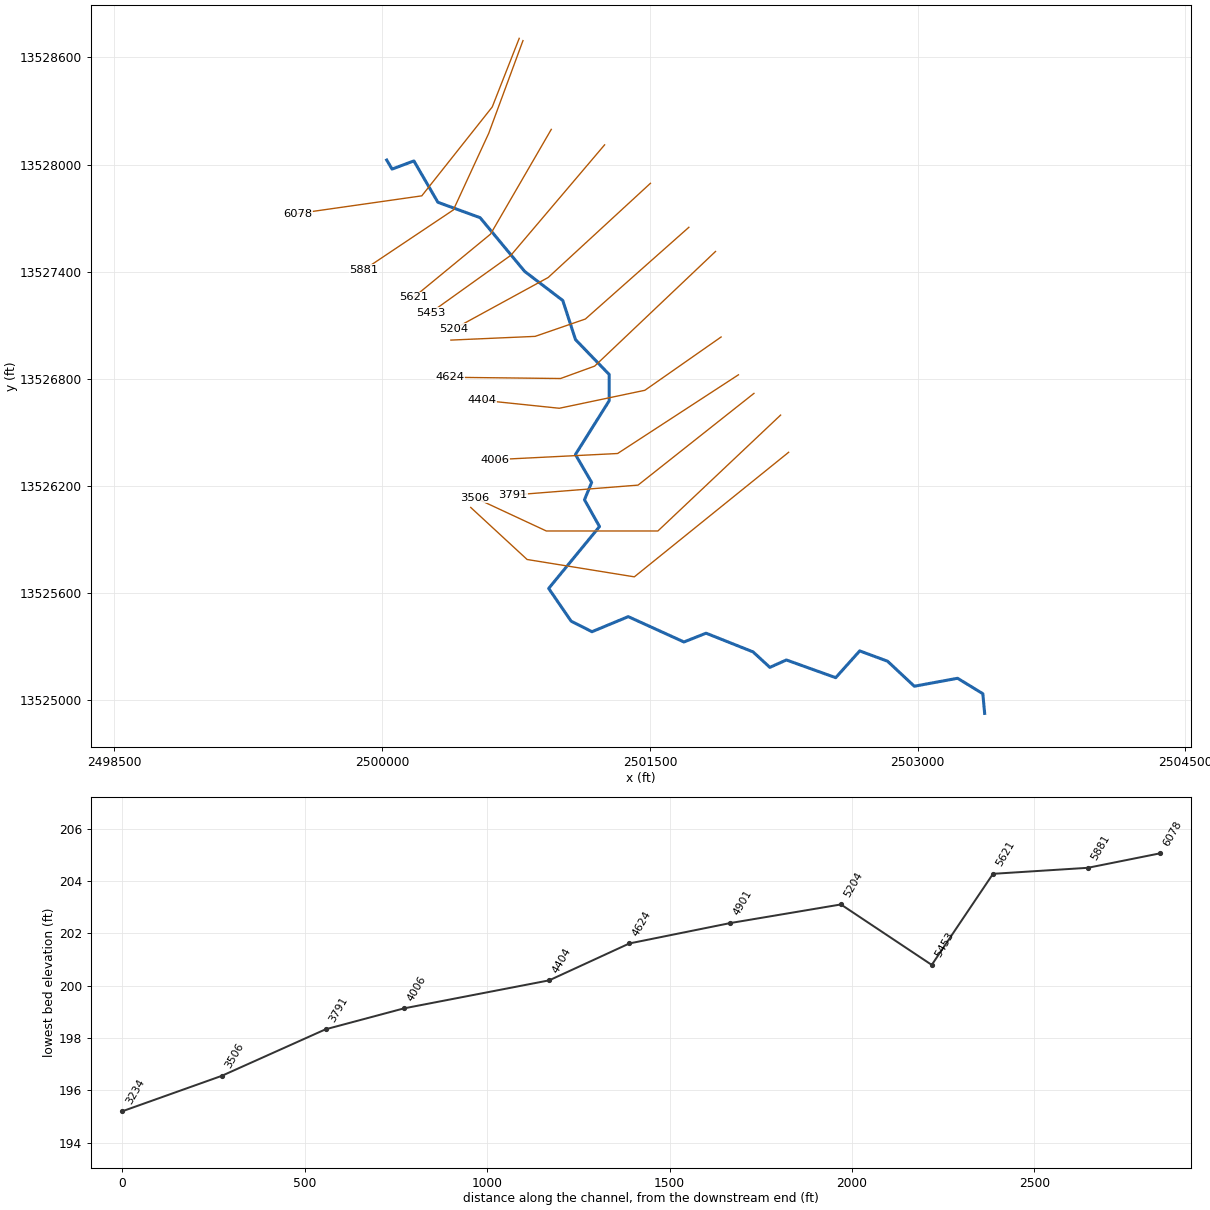
--- TRIB 11 TO TWELVEMILE CREEK.prj (project) ---

Proj Title=TRIB 11 TO TWELVEMILE CREEK Base Level Engineering
Current Plan=p01
Default Exp/Contr=0.3,0.1
English Units
Geom File=g01
Flow File=f01
Plan File=p01
BEGIN DESCRIPTION:
TRIB 11 TO TWELVEMILE CREEK
END DESCRIPTION:

--- TRIB 11 TO TWELVEMILE CREEK.p01 (plan) ---

Plan Title=Multiple Run
Short Identifier=Multiple
Geom File=g01
Flow File=f01
Subcritical Flow
K Sum by GR= 0
Std Step Tol= 0.01
Critical Tol= 0.01
Num of Std Step Trials= 20
Max Error Tol= 0.3
Flow Tol Ratio= 0.001
Split Flow NTrial= 30
Split Flow Tol= 0.02
Split Flow Ratio= 0.02
Log Output Level= 0
Friction Slope Method= 1
Unsteady Friction Slope Method= 2
Unsteady Bridges Friction Slope Method= 1
Parabolic Critical Depth
Global Vel Dist=  1 , 1 , 1
Global Log Level= 0
CheckData=True
Encroach Param= -1, 0, 0, 0
BEGIN DESCRIPTION:
Multiple Run
END DESCRIPTION:

--- TRIB 11 TO TWELVEMILE CREEK.f01 (steady flow) ---

Flow Title=Multiple
Number of Profiles=7
Profile Names=10-year,25-year,50-year,1pct_min,100-year,1pct_plu,500-year
River Rch & RM= TRIB 11 TO TWELV,Reach-1,6078
     565     901    1201     775    1547    3086    2537
River Rch & RM= TRIB 11 TO TWELV,Reach-1,5453
     612     977    1303     841    1677    3347    2750
Boundary for River Rch & Prof#=TRIB 11 TO TWELV,Reach-1,1
Up Type=0
Dn Type=3
Dn Slope=0.005
Boundary for River Rch & Prof#=TRIB 11 TO TWELV,Reach-1,2
Up Type=0
Dn Type=3
Dn Slope=0.005
Boundary for River Rch & Prof#=TRIB 11 TO TWELV,Reach-1,3
Up Type=0
Dn Type=3
Dn Slope=0.005
Boundary for River Rch & Prof#=TRIB 11 TO TWELV,Reach-1,4
Up Type=0
Dn Type=3
Dn Slope=0.005
Boundary for River Rch & Prof#=TRIB 11 TO TWELV,Reach-1,5
Up Type=0
Dn Type=3
Dn Slope=0.005
Boundary for River Rch & Prof#=TRIB 11 TO TWELV,Reach-1,6
Up Type=0
Dn Type=3
Dn Slope=0.005
Boundary for River Rch & Prof#=TRIB 11 TO TWELV,Reach-1,7
Up Type=0
Dn Type=3
Dn Slope=0.005

--- TRIB 11 TO TWELVEMILE CREEK.g01 (geometry) ---

Geom Title=Existing Conditions

River Reach=TRIB 11 TO TWELV,Reach-1
Reach XY= 30
      2500025.00     13528025.00      2500055.04     13527974.25
      2500177.27     13528020.13      2500311.67     13527788.39
      2500548.47     13527701.99      2500797.86     13527401.16
      2501011.38     13527238.22      2501082.86     13527018.83
      2501271.47     13526823.53      2501271.46     13526676.47
      2501082.30     13526375.08      2501173.16     13526218.88
      2501133.07     13526121.69      2501217.23     13525971.59
      2500932.50     13525625.00      2501058.29     13525441.62
      2501174.99     13525382.53      2501378.30     13525466.92
      2501690.39     13525325.08      2501814.31     13525374.25
      2502077.43     13525269.45      2502171.60     13525182.83
      2502264.29     13525224.18      2502540.47     13525125.01
      2502675.00     13525275.00      2502831.18     13525217.15
      2502980.86     13525077.05      2503223.28     13525121.66
      2503364.72     13525035.18      2503375.00     13524925.00

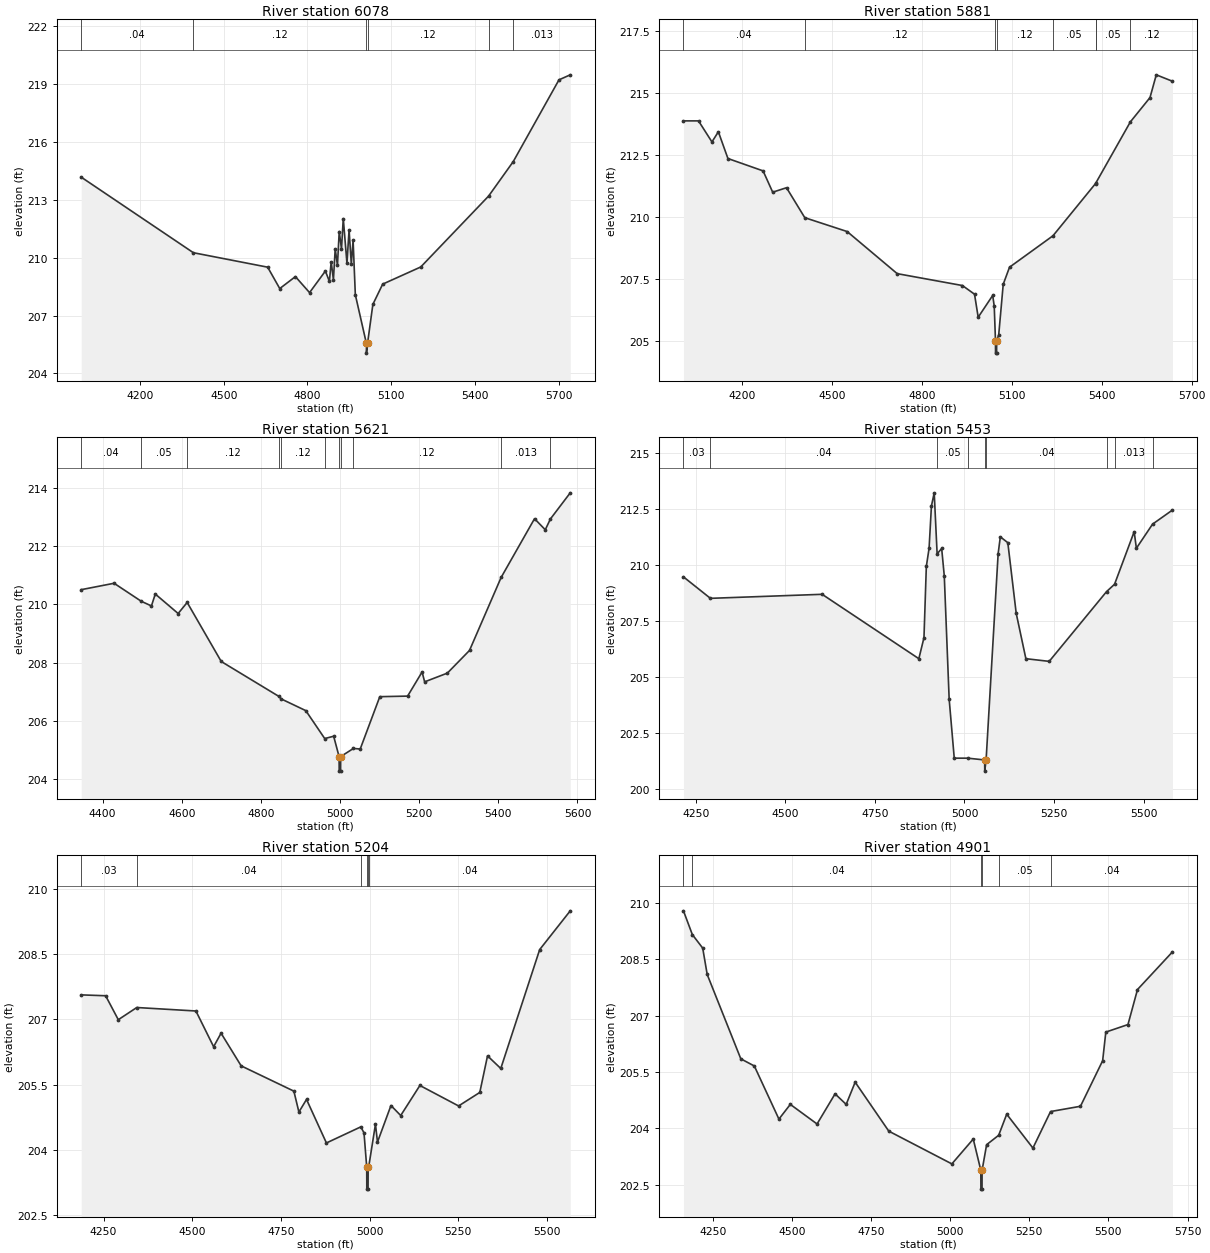
Type RM Length L Ch R = 1,6078,197,197,197
BEGIN DESCRIPTION:
TRIB 11_1 TO TWELVEMILE CREEK 4.0
END DESCRIPTION:
XS GIS Cut Line= 4
      2500767.47     13528706.84      2500616.32     13528322.41
      2500221.56     13527824.41      2499524.97     13527725.00
#Sta/Elev= 30
  3989.5  214.18  4391.3  210.26  4657.5  209.51  4700.8  208.40  4756.9  209.02
  4807.6  208.19  4864.3  209.31  4878.7  208.77  4885.1  209.79  4893.1  208.86
  4899.5  210.46  4907.5  209.61  4913.9  211.36  4922.0  210.46  4928.4  212.03
  4941.6  209.71  4949.2  211.45  4957.2  209.67  4963.6  210.90  4971.6  208.08
  5011.3  205.55  5011.5  205.05  5015.3  205.55  5034.5  207.58  5069.6  208.63
  5206.0  209.52  5449.2  213.20  5537.5  214.99  5701.3  219.23  5741.7  219.49
#Mann=6,-1,0
  3989.5    0.04       0  4391.3    0.12       0  5011.3    0.05       0
  5015.3    0.12       0  5449.2    0.05       0  5537.5   0.013       0
Bank Sta=5011.3,5015.3
Exp/Cntr=0.3,0.1

Type RM Length L Ch R = 1,5881,260,260,260
BEGIN DESCRIPTION:
Mapping XS ceb054c3
END DESCRIPTION:
XS GIS Cut Line= 4
      2500788.49     13528694.14      2500596.72     13528175.07
      2500398.44     13527745.46      2499896.02     13527409.36
#Sta/Elev= 30
  4005.0  213.88  4055.2  213.88  4100.0  213.03  4121.4  213.44  4153.3  212.36
  4270.6  211.86  4302.6  211.00  4348.7  211.18  4409.7  209.97  4551.0  209.41
  4717.9  207.71  4935.4  207.23  4975.8  206.88  4988.0  205.95  5036.4  206.83
  5041.5  206.40  5045.7  205.00  5045.9  204.50  5049.4  204.50  5049.7  205.00
  5056.5  205.24  5071.5  207.28  5092.5  207.97  5237.5  209.24  5379.5  211.35
  5381.3  211.39  5495.6  213.84  5561.0  214.82  5582.0  215.74  5636.0  215.48
#Mann=8,-1,0
  4005.0    0.04       0  4409.7    0.12       0  5045.7    0.05       0
  5049.7    0.12       0  5237.5    0.05       0  5379.5   0.013       0
  5381.3    0.05       0  5495.6    0.12       0
Bank Sta=5045.7,5049.7
Exp/Cntr=0.3,0.1

Type RM Length L Ch R = 1,5621,168,168,168
BEGIN DESCRIPTION:
Mapping XS 6ddb657e
END DESCRIPTION:
XS GIS Cut Line= 3
      2500947.05     13528196.84      2500606.78     13527610.05
      2500176.24     13527255.89
#Sta/Elev= 30
  4346.0  210.51  4429.0  210.73  4497.8  210.11  4523.4  209.95  4533.1  210.36
  4590.9  209.69  4613.7  210.07  4699.8  208.04  4845.4  206.84  4851.8  206.75
  4913.5  206.35  4961.3  205.39  4983.9  205.47  4997.6  204.77  4997.9  204.27
  5001.4  204.27  5001.6  204.77  5033.9  205.05  5051.0  205.03  5100.5  206.83
  5170.8  206.85  5207.4  207.68  5213.8  207.34  5271.2  207.64  5327.2  208.42
  5407.1  210.93  5491.5  212.95  5518.7  212.57  5531.6  212.94  5581.8  213.84
#Mann=11,-1,0
  4346.0    0.04       0  4497.8    0.05       0  4613.7    0.12       0
  4845.4    0.05       0  4851.8    0.12       0  4961.3    0.05       0
  4997.6    0.05       0  5001.6    0.05       0  5033.9    0.12       0
  5407.1   0.013       0  5531.6    0.12       0
Bank Sta=4997.6,5001.6
Exp/Cntr=0.3,0.1

Type RM Length L Ch R = 1,5453,249,249,249
BEGIN DESCRIPTION:
Mapping XS dacb3384
END DESCRIPTION:
XS GIS Cut Line= 3
      2501245.69     13528110.08      2500721.36     13527491.99
      2500270.65     13527169.56
#Sta/Elev= 30
  4215.8  209.48  4291.0  208.52  4602.8  208.70  4872.7  205.82  4887.0  206.76
  4893.6  209.95  4901.3  210.76  4907.8  212.65  4915.6  213.24  4923.7  210.51
  4936.4  210.75  4943.7  209.52  4957.3  204.01  4971.5  201.37  5009.0  201.37
  5056.4  201.29  5056.6  200.79  5060.4  201.29  5094.0  210.52  5100.1  211.27
  5121.0  211.01  5144.4  207.85  5171.4  205.82  5236.5  205.70  5396.5  208.82
  5418.9  209.15  5473.6  211.50  5479.8  210.76  5525.0  211.84  5580.5  212.47
#Mann=9,-1,0
  4215.8    0.03       0  4291.0    0.04       0  4923.7    0.05       0
  5009.0    0.04       0  5056.4    0.05       0  5060.4    0.04       0
  5396.5    0.12       0  5418.9   0.013       0  5525.0    0.12       0
Bank Sta=5056.4,5060.4
Exp/Cntr=0.3,0.1

Type RM Length L Ch R = 1,5204,303,303,303
BEGIN DESCRIPTION:
Mapping XS dbf113fc
END DESCRIPTION:
XS GIS Cut Line= 3
      2501502.59     13527894.75      2500929.69     13527366.99
      2500403.03     13527079.41
#Sta/Elev= 30
  4187.0  207.56  4255.8  207.54  4291.5  206.99  4343.6  207.27  4510.4  207.19
  4560.3  206.37  4581.3  206.68  4638.0  205.93  4786.6  205.35  4800.8  204.87
  4822.3  205.16  4878.4  204.16  4975.5  204.53  4984.4  204.39  4992.1  203.60
  4992.3  203.10  4995.8  203.10  4996.1  203.60  4998.0  203.63  5016.7  204.59
  5022.4  204.18  5060.4  205.02  5087.9  204.79  5142.0  205.48  5251.1  205.01
  5310.9  205.32  5332.7  206.16  5370.1  205.87  5479.8  208.60  5566.0  209.49
#Mann=6,-1,0
  4187.0    0.03       0  4343.6    0.04       0  4975.5    0.05       0
  4992.1    0.04       0  4996.1    0.05       0  4998.0    0.04       0
Bank Sta=4992.1,4996.1
Exp/Cntr=0.3,0.1

Type RM Length L Ch R = 1,4901,277,277,277
BEGIN DESCRIPTION:
Mapping XS e3d1ecdf
END DESCRIPTION:
XS GIS Cut Line= 4
      2501717.85     13527648.21      2501138.03     13527134.35
      2500856.78     13527037.13      2500384.57     13527016.30
#Sta/Elev= 30
  4157.5  209.78  4185.5  209.15  4218.3  208.79  4232.5  208.09  4338.7  205.85
  4381.4  205.66  4459.1  204.25  4495.1  204.64  4579.6  204.12  4636.5  204.92
  4671.6  204.64  4700.0  205.23  4806.2  203.93  5005.5  203.06  5073.1  203.72
  5097.0  202.89  5097.3  202.39  5100.8  202.39  5101.0  202.89  5115.3  203.57
  5153.4  203.82  5178.8  204.38  5261.6  203.48  5317.3  204.45  5411.8  204.59
  5481.9  205.80  5491.9  206.56  5561.9  206.76  5592.0  207.69  5702.5  208.69
#Mann=6,-1,0
  4157.5    0.03       0  4185.5    0.04       0  5097.0    0.04       0
  5101.0    0.04       0  5153.4    0.05       0  5317.3    0.04       0
Bank Sta=5097,5101
Exp/Cntr=0.3,0.1

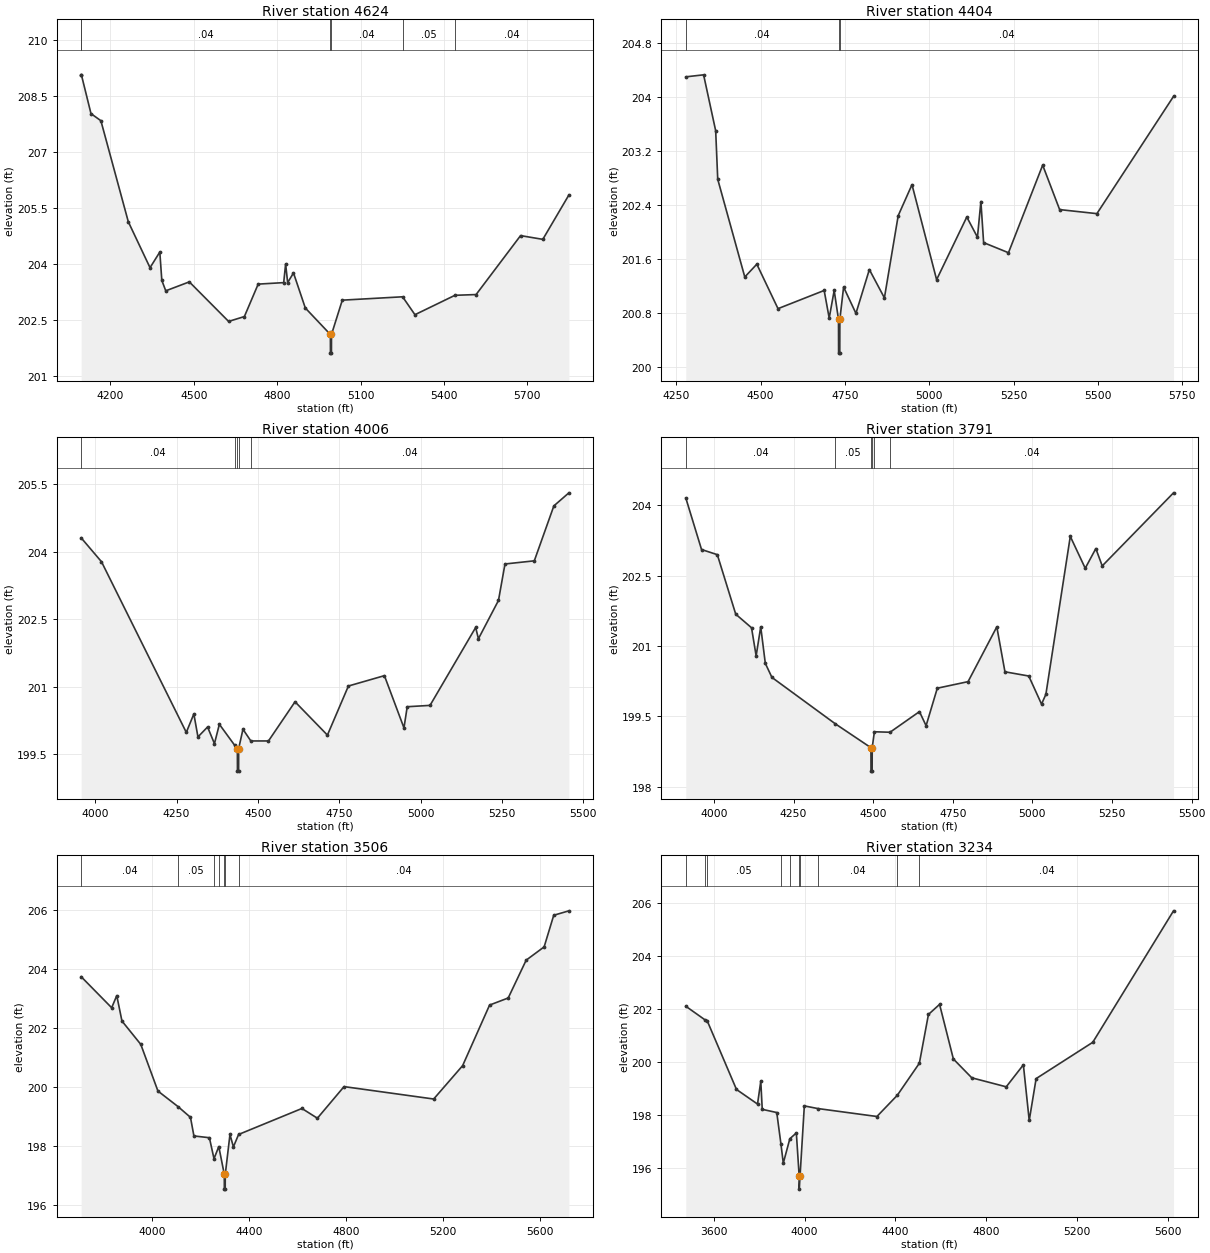
Type RM Length L Ch R = 1,4624,220,220,220
BEGIN DESCRIPTION:
Mapping XS bdbdc9b3
END DESCRIPTION:
XS GIS Cut Line= 4
      2501867.19     13527512.82      2501190.11     13526870.46
      2500999.14     13526801.02      2500381.09     13526807.96
#Sta/Elev= 30
  4094.7  209.07  4095.5  209.07  4130.0  208.03  4165.6  207.84  4264.3  205.13
  4342.4  203.90  4377.6  204.32  4384.8  203.56  4399.0  203.28  4483.7  203.52
  4625.1  202.46  4681.8  202.59  4731.5  203.46  4823.3  203.50  4830.2  204.00
  4837.5  203.50  4858.5  203.76  4901.0  202.82  4991.2  202.11  4991.5  201.61
  4995.0  201.61  4995.2  202.11  5034.1  203.03  5251.0  203.12  5295.4  202.64
  5439.3  203.16  5515.4  203.18  5675.4  204.76  5755.4  204.66  5849.3  205.85
#Mann=6,-1,0
  4094.7    0.03       0  4095.5    0.04       0  4991.2    0.04       0
  4995.2    0.04       0  5251.0    0.05       0  5439.3    0.04       0
Bank Sta=4991.2,4995.2
Exp/Cntr=0.3,0.1

Type RM Length L Ch R = 1,4404,398,398,398
BEGIN DESCRIPTION:
Mapping XS cea90300
END DESCRIPTION:
XS GIS Cut Line= 4
      2501898.42     13527033.64      2501471.36     13526735.05
      2500992.19     13526634.35      2500559.06     13526679.40
#Sta/Elev= 30
  4278.2  204.30  4331.0  204.33  4366.8  203.50  4372.9  202.78  4453.1  201.33
  4488.8  201.52  4551.6  200.86  4688.5  201.13  4703.4  200.72  4718.2  201.13
  4731.0  200.70  4731.3  200.20  4734.8  200.20  4735.0  200.70  4746.1  201.18
  4782.7  200.79  4822.5  201.44  4867.1  201.02  4908.0  202.24  4948.9  202.70
  5021.9  201.29  5111.4  202.22  5143.0  201.92  5153.2  202.45  5161.3  201.84
  5235.0  201.69  5336.4  202.99  5386.7  202.33  5497.2  202.27  5724.4  204.01
#Mann=3,-1,0
  4278.2    0.04       0  4731.0    0.04       0  4735.0    0.04       0
Bank Sta=4731,4735
Exp/Cntr=0.3,0.1

Type RM Length L Ch R = 1,4006,215,215,215
BEGIN DESCRIPTION:
Mapping XS b399e87f
END DESCRIPTION:
XS GIS Cut Line= 3
      2501995.65     13526821.84      2501318.58     13526380.88
      2500628.85     13526346.22
#Sta/Elev= 30
  3957.1  204.31  4019.5  203.78  4280.1  199.99  4303.3  200.40  4315.9  199.89
  4345.5  200.11  4366.6  199.74  4381.7  200.17  4429.1  199.70  4437.0  199.63
  4437.3  199.13  4440.8  199.13  4441.0  199.63  4454.2  200.06  4478.4  199.80
  4532.6  199.80  4614.2  200.67  4713.7  199.93  4778.2  201.02  4888.8  201.25
  4948.9  200.09  4958.9  200.56  5029.0  200.59  5169.2  202.32  5177.7  202.07
  5239.3  202.92  5259.3  203.73  5349.4  203.80  5409.5  205.02  5455.7  205.31
#Mann=5,-1,0
  3957.1    0.04       0  4429.1    0.05       0  4437.0    0.04       0
  4441.0    0.05       0  4478.4    0.04       0
Bank Sta=4437,4441
Exp/Cntr=0.3,0.1

Type RM Length L Ch R = 1,3791,285,285,285
BEGIN DESCRIPTION:
Mapping XS 9fb7c9a0
END DESCRIPTION:
XS GIS Cut Line= 3
      2502082.44     13526717.66      2501433.16     13526203.80
      2500731.79     13526148.24
#Sta/Elev= 30
  3911.5  204.16  3960.9  203.06  4010.5  202.95  4068.3  201.68  4117.9  201.39
  4132.4  200.79  4146.8  201.41  4161.2  200.63  4182.0  200.33  4381.0  199.34
  4492.9  198.83  4493.1  198.33  4496.6  198.33  4496.9  198.83  4503.7  199.17
  4552.9  199.16  4645.2  199.60  4666.1  199.30  4701.3  200.10  4797.9  200.24
  4888.2  201.41  4913.7  200.45  4988.5  200.36  5028.6  199.76  5042.3  199.97
  5118.9  203.34  5165.8  202.66  5199.1  203.08  5219.2  202.71  5443.1  204.27
#Mann=6,-1,0
  3911.5    0.04       0  4381.0    0.05       0  4492.9    0.04       0
  4496.9    0.05       0  4503.7     0.1       0  4552.9    0.04       0
Bank Sta=4492.9,4496.9
Exp/Cntr=0.3,0.1

Type RM Length L Ch R = 1,3506,272,272,272
BEGIN DESCRIPTION:
Mapping XS 013d47da
END DESCRIPTION:
XS GIS Cut Line= 4
      2502231.76     13526596.14      2501544.28     13525946.85
      2500919.28     13525946.85      2500518.23     13526133.55
#Sta/Elev= 30
  3707.9  203.74  3833.7  202.69  3854.8  203.10  3876.2  202.24  3953.9  201.45
  4024.7  199.87  4108.1  199.34  4159.0  198.98  4173.2  198.35  4237.1  198.29
  4256.1  197.58  4275.9  197.99  4298.6  197.05  4298.8  196.55  4302.3  196.55
  4302.6  197.05  4322.0  198.40  4336.2  197.98  4357.6  198.40  4619.0  199.28
  4682.8  198.95  4792.8  200.02  5162.8  199.60  5282.3  200.73  5393.5  202.78
  5470.4  203.02  5544.5  204.30  5618.7  204.75  5658.3  205.82  5720.9  205.97
#Mann=7,-1,0
  3707.9    0.04       0  4108.1    0.05       0  4256.1    0.12       0
  4275.9     0.1       0  4298.6    0.04       0  4302.6     0.1       0
  4357.6    0.04       0
Bank Sta=4298.6,4302.6
Exp/Cntr=0.3,0.1

Type RM Length L Ch R = 1,3234,0,0,0
BEGIN DESCRIPTION:
Mapping XS 7fa4de58
END DESCRIPTION:
XS GIS Cut Line= 4
      2502276.91     13526387.82      2501412.33     13525689.91
      2500811.64     13525787.13      2500495.69     13526078.77
#Sta/Elev= 30
  3476.5  202.10  3560.6  201.59  3570.4  201.56  3699.9  198.96  3792.6  198.41
  3807.0  199.27  3813.4  198.21  3877.4  198.09  3895.7  196.91  3906.2  196.18
  3935.0  197.10  3963.7  197.32  3976.1  195.70  3976.4  195.20  3980.1  195.70
  3998.9  198.34  4058.5  198.24  4318.8  197.94  4408.6  198.74  4505.9  199.95
  4545.9  201.79  4595.0  202.17  4655.8  200.11  4736.9  199.40  4888.8  199.06
  4964.3  199.89  4990.1  197.79  5020.5  199.37  5270.2  200.74  5626.1  205.70
#Mann=10,-1,0
  3476.5    0.05       0  3560.6    0.04       0  3570.4    0.05       0
  3895.7    0.12       0  3935.0    0.05       0  3976.1    0.04       0
  3980.1    0.05       0  4058.5    0.04       0  4408.6    0.05       0
  4505.9    0.04       0
Bank Sta=3976.1,3980.1
Exp/Cntr=0.3,0.1

Chan Stop Cuts=-1