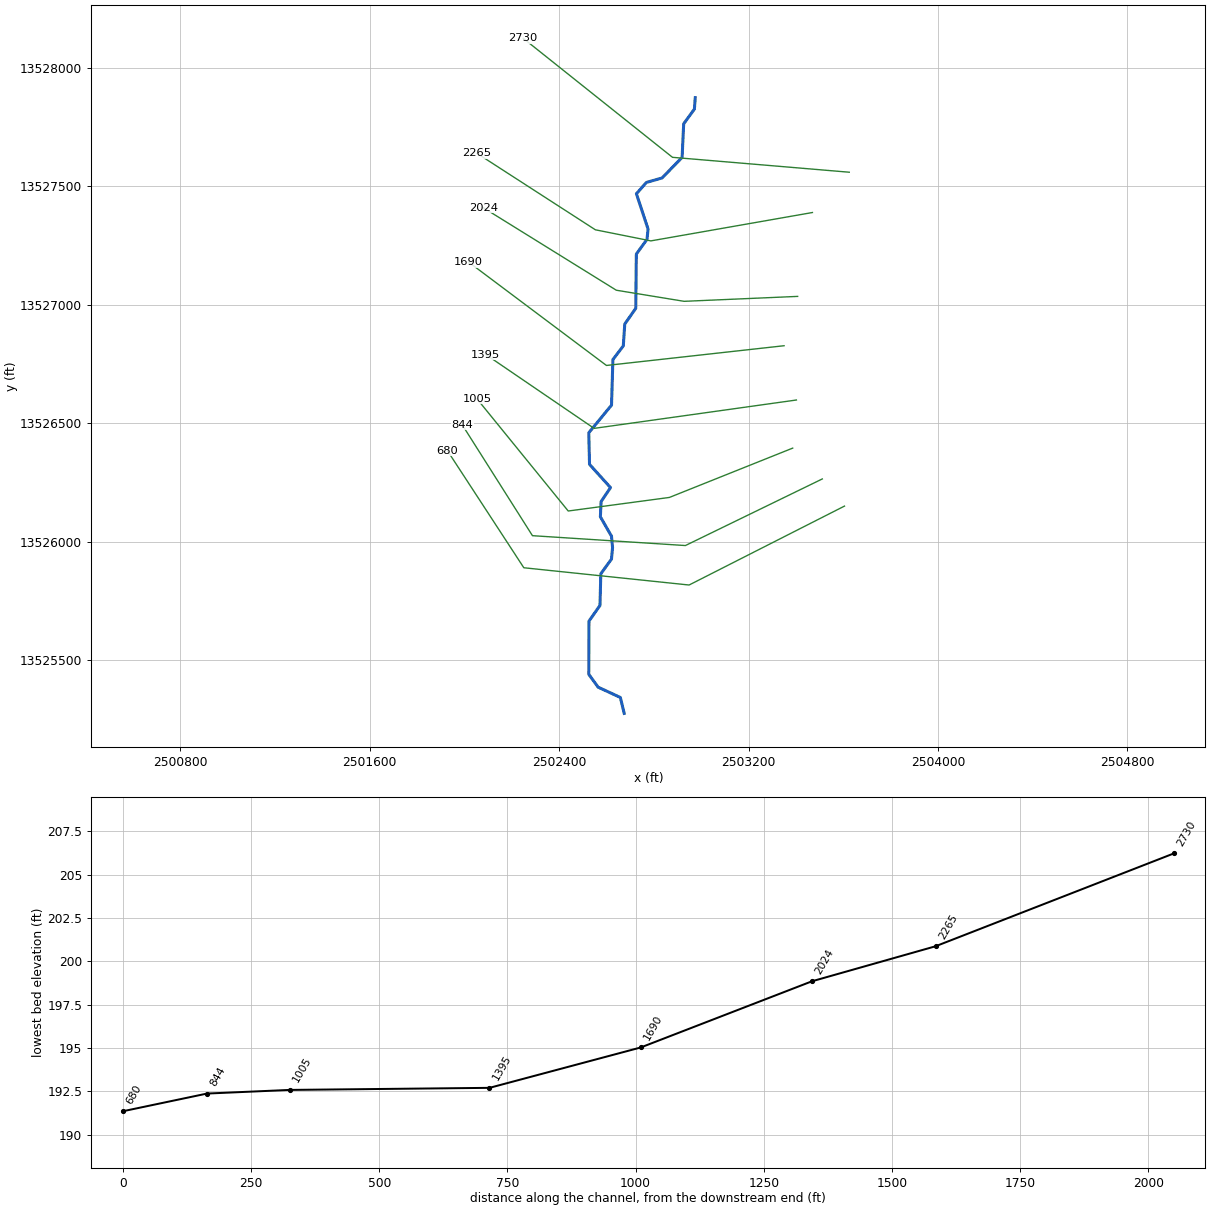
--- TRIB 11_1 TO TWELVEMILE CREEK.prj (project) ---

Proj Title=TRIB 11_1 TO TWELVEMILE CREEK Base Level Engineering
Current Plan=p01
Default Exp/Contr=0.3,0.1
English Units
Geom File=g01
Flow File=f01
Plan File=p01
BEGIN DESCRIPTION:
TRIB 11_1 TO TWELVEMILE CREEK
END DESCRIPTION:

--- TRIB 11_1 TO TWELVEMILE CREEK.p01 (plan) ---

Plan Title=Multiple Run
Short Identifier=Multiple
Geom File=g01
Flow File=f01
Subcritical Flow
K Sum by GR= 0
Std Step Tol= 0.01
Critical Tol= 0.01
Num of Std Step Trials= 20
Max Error Tol= 0.3
Flow Tol Ratio= 0.001
Split Flow NTrial= 30
Split Flow Tol= 0.02
Split Flow Ratio= 0.02
Log Output Level= 0
Friction Slope Method= 1
Unsteady Friction Slope Method= 2
Unsteady Bridges Friction Slope Method= 1
Parabolic Critical Depth
Global Vel Dist=  1 , 1 , 1
Global Log Level= 0
CheckData=True
Encroach Param= -1, 0, 0, 0
BEGIN DESCRIPTION:
Multiple Run
END DESCRIPTION:

--- TRIB 11_1 TO TWELVEMILE CREEK.f01 (steady flow) ---

Flow Title=Multiple
Number of Profiles=7
Profile Names=10-year,25-year,50-year,1pct_min,100-year,1pct_plu,500-year
River Rch & RM= TRIB 11_1 TO TWE,Reach-1,2730
     505     801    1063     684    1364    2722    2222
River Rch & RM= TRIB 11_1 TO TWE,Reach-1,1690
     624    1002    1341     869    1735    3461    2871
Boundary for River Rch & Prof#=TRIB 11_1 TO TWE,Reach-1,1
Up Type=0
Dn Type=3
Dn Slope=0.005
Boundary for River Rch & Prof#=TRIB 11_1 TO TWE,Reach-1,2
Up Type=0
Dn Type=3
Dn Slope=0.005
Boundary for River Rch & Prof#=TRIB 11_1 TO TWE,Reach-1,3
Up Type=0
Dn Type=3
Dn Slope=0.005
Boundary for River Rch & Prof#=TRIB 11_1 TO TWE,Reach-1,4
Up Type=0
Dn Type=3
Dn Slope=0.005
Boundary for River Rch & Prof#=TRIB 11_1 TO TWE,Reach-1,5
Up Type=0
Dn Type=3
Dn Slope=0.005
Boundary for River Rch & Prof#=TRIB 11_1 TO TWE,Reach-1,6
Up Type=0
Dn Type=3
Dn Slope=0.005
Boundary for River Rch & Prof#=TRIB 11_1 TO TWE,Reach-1,7
Up Type=0
Dn Type=3
Dn Slope=0.005

--- TRIB 11_1 TO TWELVEMILE CREEK.g01 (geometry) ---

Geom Title=Existing Conditions

River Reach=TRIB 11_1 TO TWE,Reach-1
Reach XY= 30
      2502975.00     13527875.00      2502971.35     13527826.51
      2502926.13     13527764.53      2502919.54     13527622.54
      2502834.68     13527535.78      2502768.57     13527516.96
      2502726.54     13527469.15      2502775.80     13527319.97
      2502771.29     13527276.60      2502726.22     13527214.50
      2502723.78     13526985.50      2502677.36     13526919.02
      2502671.14     13526826.60      2502627.26     13526769.06
      2502621.45     13526576.47      2502525.37     13526459.83
      2502528.55     13526326.47      2502617.19     13526228.41
      2502577.37     13526169.11      2502574.42     13526104.96
      2502621.29     13526023.40      2502625.82     13525975.00
      2502621.30     13525926.60      2502576.23     13525864.49
      2502572.73     13525730.94      2502526.22     13525664.50
      2502525.33     13525440.03      2502564.95     13525385.61
      2502658.64     13525342.23      2502675.00     13525275.00

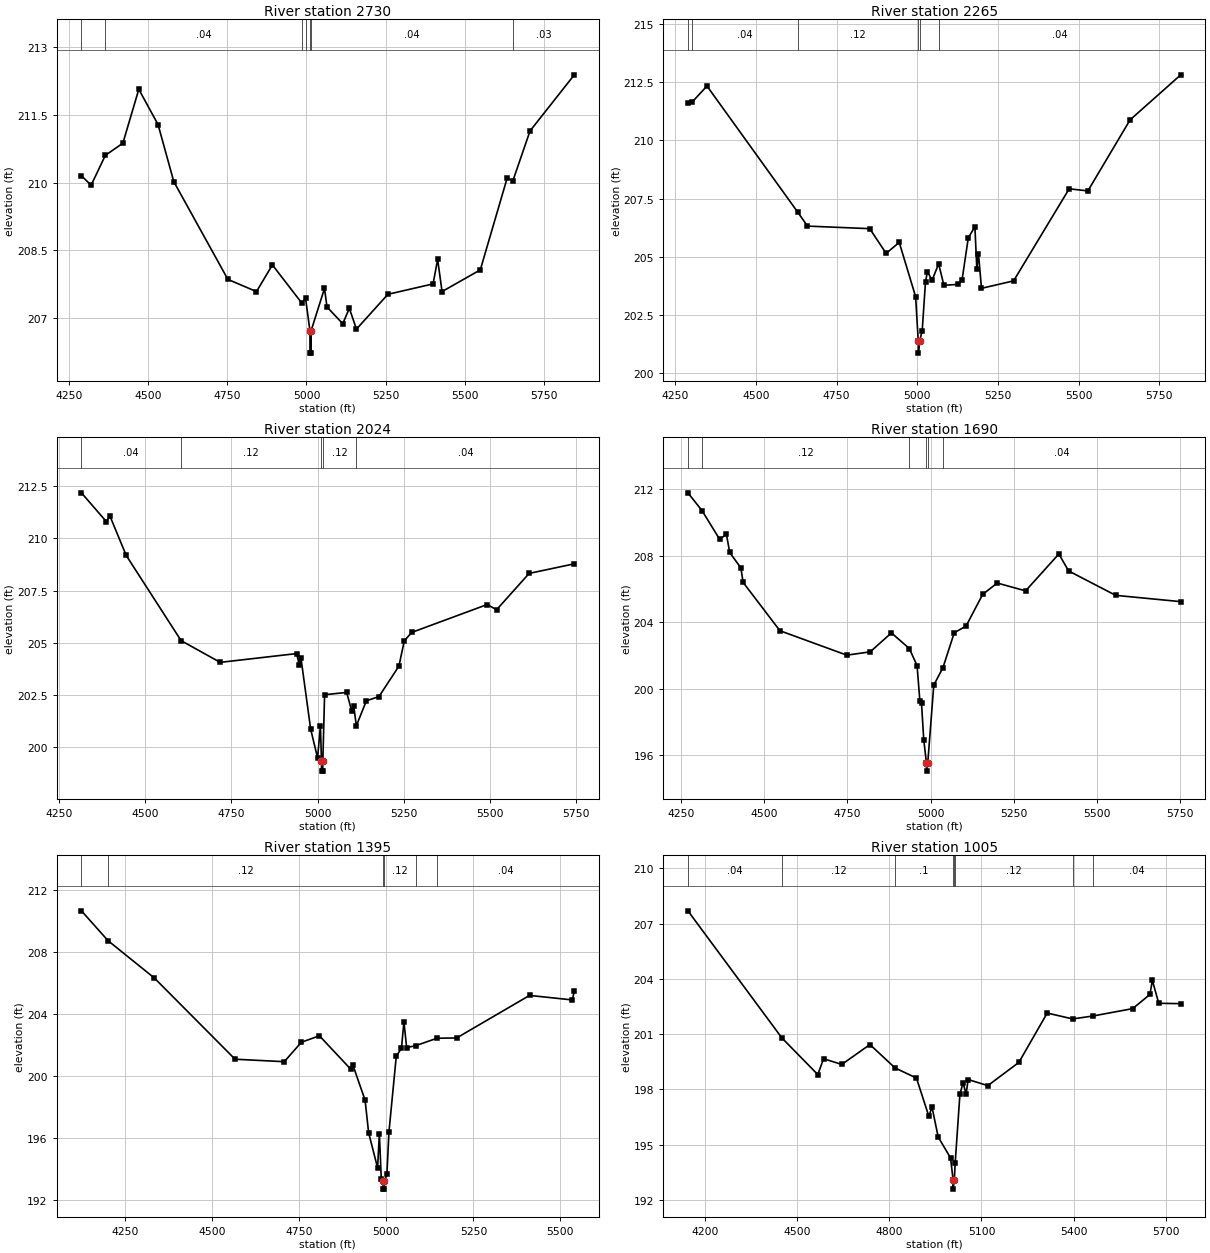
Type RM Length L Ch R = 1,2730,465,465,465
BEGIN DESCRIPTION:
Mapping XS f15a61ba
END DESCRIPTION:
XS GIS Cut Line= 3
      2503625.36     13527560.07      2502878.88     13527623.00
      2502248.68     13528125.43
#Sta/Elev= 30
  4289.9  210.15  4320.4  209.94  4365.3  210.60  4420.7  210.87  4470.9  212.06
  4531.7  211.28  4581.3  210.02  4751.9  207.86  4842.2  207.59  4892.4  208.18
  4984.8  207.34  4997.1  207.44  5010.8  206.73  5011.1  206.23  5014.6  206.23
  5014.8  206.73  5056.8  207.66  5064.7  207.25  5114.4  206.88  5135.2  207.22
  5157.6  206.76  5256.9  207.53  5399.4  207.76  5413.8  208.30  5427.7  207.59
  5548.4  208.07  5633.2  210.10  5651.3  210.04  5705.3  211.14  5845.0  212.38
#Mann=7,-1,0
  4289.9    0.03       0  4365.3    0.04       0  4984.8    0.12       0
  4997.1    0.04       0  5010.8    0.04       0  5014.8    0.04       0
  5651.3    0.03       0
Bank Sta=5010.8,5014.8
Exp/Cntr=0.3,0.1

Type RM Length L Ch R = 1,2265,241,241,241
BEGIN DESCRIPTION:
Mapping XS f824e702
END DESCRIPTION:
XS GIS Cut Line= 4
      2503469.83     13527389.92      2502787.56     13527270.13
      2502553.18     13527317.01      2502053.21     13527639.91
#Sta/Elev= 30
  4289.2  211.62  4302.2  211.64  4348.3  212.33  4629.9  206.91  4659.6  206.32
  4852.5  206.21  4903.3  205.15  4943.9  205.62  4994.7  203.29  5002.9  201.37
  5003.2  200.87  5006.9  201.37  5015.1  201.84  5025.3  203.94  5031.3  204.36
  5045.7  204.00  5066.0  204.70  5082.3  203.78  5127.3  203.82  5138.4  204.00
  5157.9  205.82  5178.3  206.29  5184.3  204.49  5189.4  205.13  5198.7  203.65
  5298.2  203.97  5470.4  207.92  5528.3  207.83  5659.2  210.88  5816.1  212.81
#Mann=6,-1,0
  4289.2    0.03       0  4302.2    0.04       0  4629.9    0.12       0
  5002.9    0.05       0  5006.9    0.12       0  5066.0    0.04       0
Bank Sta=5002.9,5006.9
Exp/Cntr=0.3,0.1

Type RM Length L Ch R = 1,2024,334,334,334
BEGIN DESCRIPTION:
Mapping XS 235ce3a0
END DESCRIPTION:
XS GIS Cut Line= 4
      2503407.37     13527035.76      2502928.18     13527014.93
      2502641.72     13527061.80      2502080.21     13527410.15
#Sta/Elev= 30
  4314.7  212.18  4387.1  210.80  4397.1  211.08  4444.7  209.18  4604.0  205.10
  4717.5  204.06  4939.4  204.48  4947.1  203.93  4952.1  204.25  4980.0  200.87
  5000.2  199.48  5008.4  201.02  5011.5  199.35  5011.7  198.85  5015.2  198.85
  5015.5  199.35  5020.5  202.51  5084.6  202.62  5099.3  201.73  5105.2  201.96
  5112.7  201.02  5141.8  202.22  5178.4  202.42  5236.3  203.88  5251.7  205.08
  5272.9  205.49  5492.6  206.83  5519.8  206.58  5614.3  208.32  5745.4  208.78
#Mann=5,-1,0
  4314.7    0.04       0  4604.0    0.12       0  5011.5    0.05       0
  5015.5    0.12       0  5112.7    0.04       0
Bank Sta=5011.5,5015.5
Exp/Cntr=0.3,0.1

Type RM Length L Ch R = 1,1690,295,295,295
BEGIN DESCRIPTION:
Mapping XS 44697a2f
END DESCRIPTION:
XS GIS Cut Line= 3
      2503350.06     13526827.43      2502600.06     13526744.09
      2502017.75     13527180.82
#Sta/Elev= 30
  4270.2  211.78  4312.7  210.71  4365.8  208.98  4386.0  209.29  4396.0  208.19
  4429.6  207.26  4436.3  206.39  4547.0  203.48  4748.2  202.01  4818.6  202.21
  4882.4  203.35  4936.1  202.41  4959.5  201.38  4967.9  199.26  4972.9  199.11
  4979.6  196.92  4987.7  195.53  4987.9  195.03  4991.7  195.53  5009.8  200.21
  5037.4  201.26  5071.4  203.36  5106.9  203.76  5156.9  205.67  5200.6  206.35
  5286.0  205.88  5386.0  208.10  5415.2  207.08  5556.9  205.61  5752.7  205.23
#Mann=6,-1,0
  4270.2    0.04       0  4312.7    0.12       0  4936.1    0.05       0
  4987.7    0.05       0  4991.7    0.05       0  5037.4    0.04       0
Bank Sta=4987.7,4991.7
Exp/Cntr=0.3,0.1

Type RM Length L Ch R = 1,1395,390,390,390
BEGIN DESCRIPTION:
Mapping XS 72540807
END DESCRIPTION:
XS GIS Cut Line= 3
      2503402.11     13526598.25      2502547.97     13526478.47
      2502090.57     13526790.33
#Sta/Elev= 30
  4123.8  210.63  4200.6  208.70  4332.9  206.31  4565.2  201.07  4706.6  200.91
  4755.6  202.16  4807.5  202.58  4898.3  200.41  4903.4  200.71  4938.8  198.43
  4948.9  196.34  4974.7  194.07  4979.8  196.28  4985.3  193.36  4990.5  193.20
  4990.7  192.70  4994.2  192.70  4994.5  193.20  5001.4  193.65  5007.4  196.40
  5028.4  201.26  5043.3  201.78  5050.4  203.48  5058.2  201.82  5083.9  201.94
  5145.2  202.42  5201.9  202.44  5411.3  205.18  5533.9  204.89  5539.9  205.44
#Mann=6,-1,0
  4123.8    0.04       0  4200.6    0.12       0  4990.5    0.05       0
  4994.5    0.12       0  5083.9    0.05       0  5145.2    0.04       0
Bank Sta=4990.5,4994.5
Exp/Cntr=0.3,0.1

Type RM Length L Ch R = 1,1005,161,161,161
BEGIN DESCRIPTION:
Mapping XS c6172570
END DESCRIPTION:
XS GIS Cut Line= 4
      2503386.49     13526395.12      2502865.68     13526186.80
      2502438.60     13526129.51      2502053.19     13526603.45
#Sta/Elev= 30
  4145.4  207.69  4451.0  200.79  4567.8  198.80  4586.6  199.66  4645.8  199.35
  4737.3  200.43  4819.0  199.16  4888.6  198.61  4929.0  196.53  4939.1  197.04
  4959.3  195.41  4999.6  194.27  5007.7  193.08  5007.9  192.58  5011.7  193.08
  5014.5  193.99  5029.9  197.73  5040.0  198.35  5050.1  197.75  5056.7  198.53
  5120.7  198.20  5221.6  199.46  5313.8  202.14  5396.7  201.82  5462.4  201.98
  5591.8  202.38  5647.8  203.15  5655.7  203.91  5676.6  202.67  5748.1  202.65
#Mann=8,-1,0
  4145.4    0.04       0  4451.0    0.12       0  4819.0     0.1       0
  5007.7    0.05       0  5011.7     0.1       0  5014.5    0.12       0
  5396.7    0.05       0  5462.4    0.04       0
Bank Sta=5007.7,5011.7
Exp/Cntr=0.3,0.1

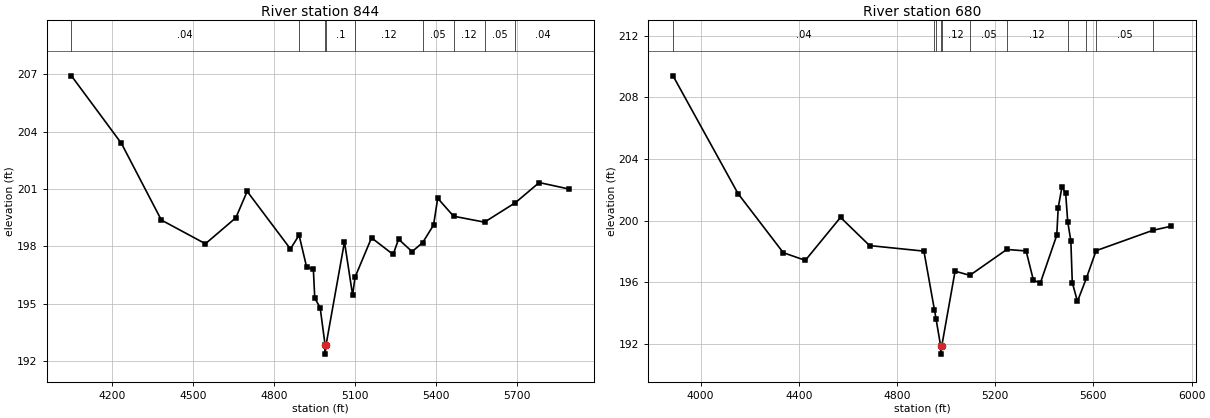
Type RM Length L Ch R = 1,844,164,164,164
BEGIN DESCRIPTION:
Mapping XS 33596b4a
END DESCRIPTION:
XS GIS Cut Line= 4
      2503511.55     13526264.94      2502933.39     13525983.68
      2502287.56     13526025.34      2501990.67     13526494.11
#Sta/Elev= 30
  4048.2  206.92  4233.4  203.39  4381.5  199.38  4544.9  198.14  4657.7  199.50
  4699.6  200.88  4859.9  197.87  4892.0  198.59  4920.0  196.92  4944.9  196.82
  4950.1  195.30  4970.1  194.80  4988.2  192.87  4988.4  192.37  4992.2  192.87
  5060.3  198.24  5090.4  195.46  5099.4  196.39  5160.5  198.45  5240.7  197.58
  5260.7  198.38  5310.8  197.73  5350.1  198.20  5390.5  199.12  5405.8  200.52
  5464.7  199.58  5579.3  199.27  5694.0  200.29  5782.1  201.34  5893.2  201.00
#Mann=9,-1,0
  4048.2    0.04       0  4892.0     0.1       0  4988.2    0.05       0
  4992.2     0.1       0  5099.4    0.12       0  5350.1    0.05       0
  5464.7    0.12       0  5579.3    0.05       0  5694.0    0.04       0
Bank Sta=4988.2,4992.2
Exp/Cntr=0.3,0.1

Type RM Length L Ch R = 1,680,0,0,0
BEGIN DESCRIPTION:
Mapping XS 2ed680dc
END DESCRIPTION:
XS GIS Cut Line= 4
      2503605.26     13526150.34      2502949.02     13525817.01
      2502251.10     13525889.93      2501929.11     13526383.29
#Sta/Elev= 30
  3888.1  209.40  4152.9  201.76  4337.0  197.93  4426.8  197.43  4570.2  200.22
  4688.5  198.39  4909.7  198.03  4952.8  194.20  4959.5  193.60  4978.1  191.85
  4978.3  191.35  4982.1  191.85  5036.6  196.73  5096.8  196.46  5247.4  198.14
  5325.9  198.04  5355.8  196.13  5384.2  195.98  5450.7  199.06  5456.6  200.85
  5471.7  202.18  5486.9  201.79  5495.3  199.94  5508.0  198.70  5513.9  195.99
  5535.0  194.77  5571.4  196.28  5610.9  198.06  5842.0  199.38  5915.0  199.64
#Mann=11,-1,0
  3888.1    0.04       0  4952.8     0.1       0  4959.5    0.12       0
  4978.1    0.05       0  4982.1    0.12       0  5096.8    0.05       0
  5247.4    0.12       0  5495.3    0.05       0  5571.4    0.12       0
  5610.9    0.05       0  5842.0    0.04       0
Bank Sta=4978.1,4982.1
Exp/Cntr=0.3,0.1

Chan Stop Cuts=-1