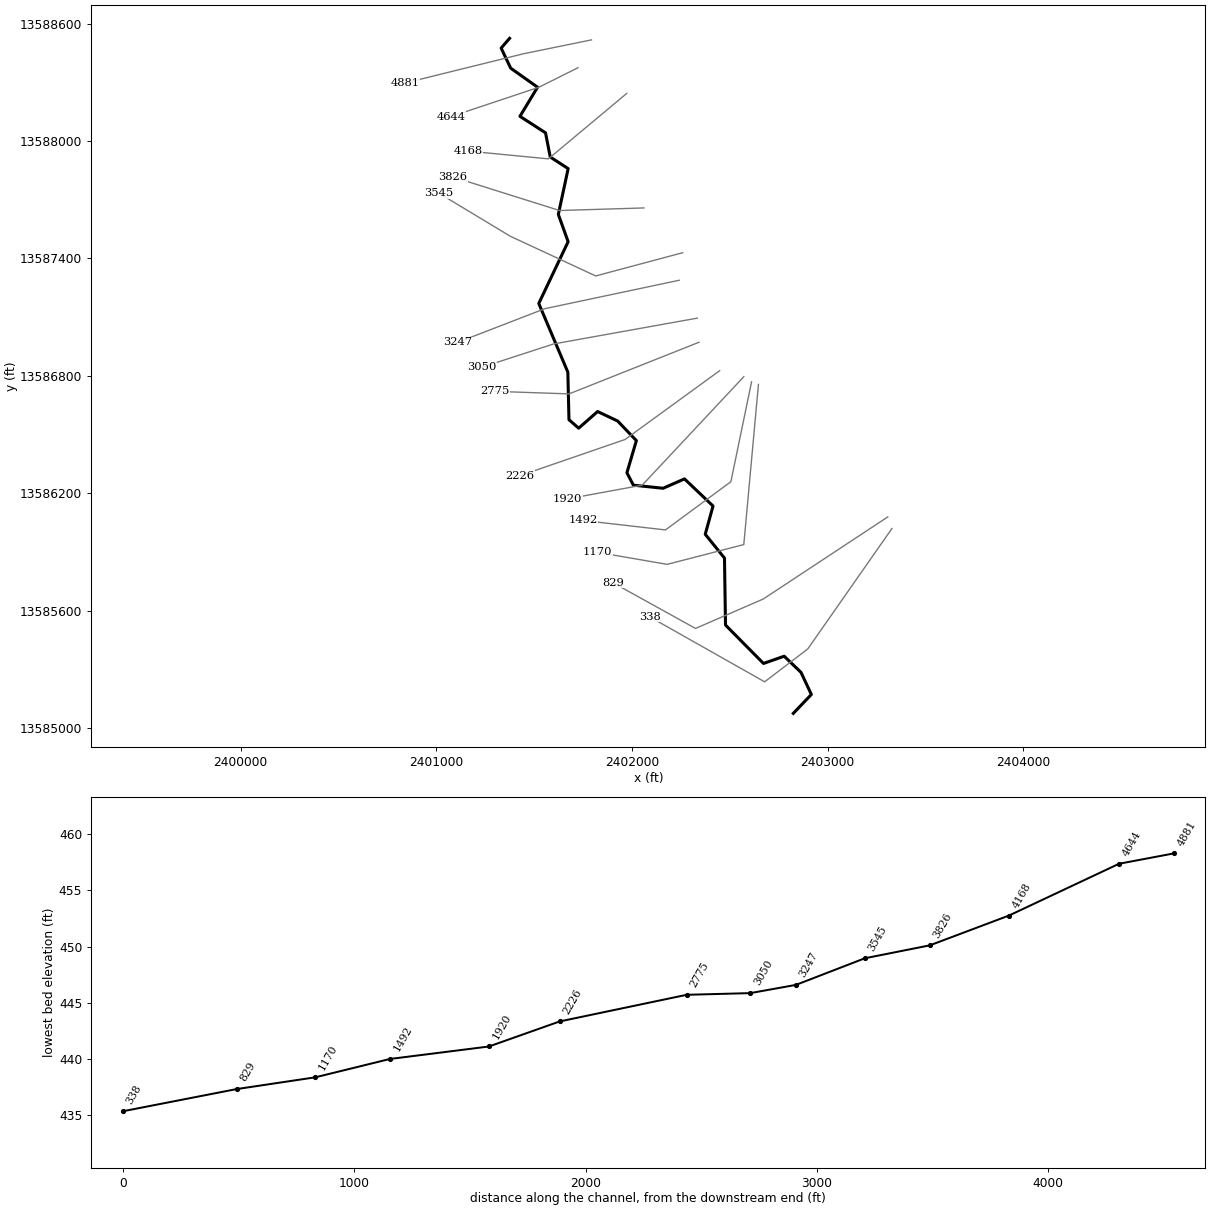
--- TRIB 12 TO SALT CREEK.prj (project) ---

Proj Title=TRIB 12 TO SALT CREEK Base Level Engineering
Current Plan=p01
Default Exp/Contr=0.3,0.1
English Units
Geom File=g01
Flow File=f01
Plan File=p01
Y Axis Title=Elevation
X Axis Title(PF)=Main Channel Distance
X Axis Title(XS)=Station
BEGIN DESCRIPTION:
TRIB 12 TO SALT CREEK
END DESCRIPTION:
DSS Export Rating Curves= 0
DSS Export Rating Curve Sorted= 0
DSS Export Volume Flow Curves= 0
DXF OffsetX= 0
DXF OffsetY= 0
DXF ScaleX= 1
DXF ScaleY= 10

--- TRIB 12 TO SALT CREEK.p01 (plan) ---

Plan Title=Multiple Run
Short Identifier=Multiple
Geom File=g01
Flow File=f01
Subcritical Flow
K Sum by GR= 0
Std Step Tol= 0.01
Critical Tol= 0.01
Num of Std Step Trials= 20
Max Error Tol= 0.3
Flow Tol Ratio= 0.001
Split Flow NTrial= 30
Split Flow Tol= 0.02
Split Flow Ratio= 0.02
Log Output Level= 0
Friction Slope Method= 1
Unsteady Friction Slope Method= 2
Unsteady Bridges Friction Slope Method= 1
Parabolic Critical Depth
Global Vel Dist=  1 , 1 , 1
Global Log Level= 0
CheckData=True
Encroach Param= -1, 0, 0, 0
BEGIN DESCRIPTION:
Multiple Run
END DESCRIPTION:

--- TRIB 12 TO SALT CREEK.f01 (steady flow) ---

Flow Title=Multiple
Number of Profiles=7
Profile Names=10-year,25-year,50-year,1pct_min,100-year,1pct_plu,500-year
River Rch & RM= TRIB 12 TO SALT ,Reach-1,4881
     424     679     907     589    1176    2347    1955
River Rch & RM= TRIB 12 TO SALT ,Reach-1,829
     542     880    1188     779    1554    3100    2630
Boundary for River Rch & Prof#=TRIB 12 TO SALT ,Reach-1,1
Up Type=0
Dn Type=3
Dn Slope=0.005
Boundary for River Rch & Prof#=TRIB 12 TO SALT ,Reach-1,2
Up Type=0
Dn Type=3
Dn Slope=0.005
Boundary for River Rch & Prof#=TRIB 12 TO SALT ,Reach-1,3
Up Type=0
Dn Type=3
Dn Slope=0.005
Boundary for River Rch & Prof#=TRIB 12 TO SALT ,Reach-1,4
Up Type=0
Dn Type=3
Dn Slope=0.005
Boundary for River Rch & Prof#=TRIB 12 TO SALT ,Reach-1,5
Up Type=0
Dn Type=3
Dn Slope=0.005
Boundary for River Rch & Prof#=TRIB 12 TO SALT ,Reach-1,6
Up Type=0
Dn Type=3
Dn Slope=0.005
Boundary for River Rch & Prof#=TRIB 12 TO SALT ,Reach-1,7
Up Type=0
Dn Type=3
Dn Slope=0.005

--- TRIB 12 TO SALT CREEK.g01 (geometry) ---

Geom Title=Existing Conditions

River Reach=TRIB 12 TO SALT ,Reach-1
Reach XY= 30
      2401375.00     13588525.00      2401331.87     13588475.12
      2401380.70     13588372.46      2401518.00     13588275.22
      2401428.01     13588126.43      2401558.69     13588042.13
      2401582.79     13587918.57      2401674.34     13587859.15
      2401624.19     13587625.00      2401674.25     13587485.68
      2401524.19     13587169.97      2401672.74     13586819.06
      2401678.54     13586575.97      2401728.13     13586532.53
      2401824.91     13586617.69      2401927.30     13586569.20
      2402023.04     13586469.12      2401974.61     13586304.71
      2402007.69     13586241.27      2402159.78     13586225.52
      2402268.97     13586273.38      2402414.81     13586134.68
      2402374.96     13585990.34      2402473.31     13585868.85
      2402478.54     13585526.46      2402672.71     13585330.12
      2402778.42     13585367.19      2402864.25     13585284.72
      2402917.35     13585171.59      2402825.00     13585075.00

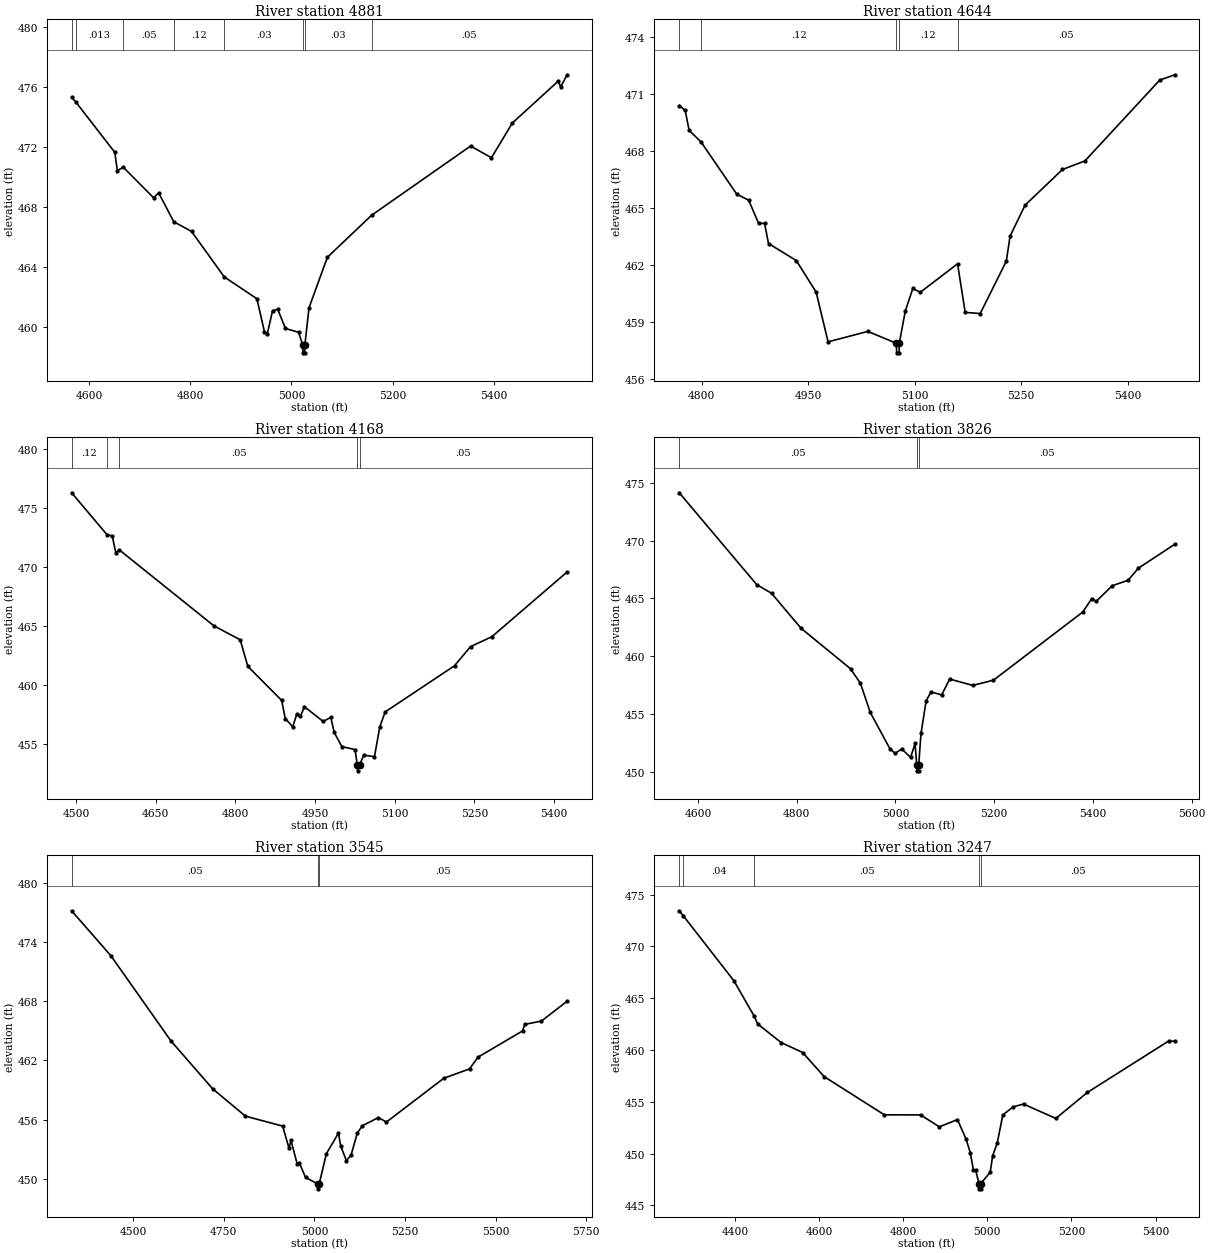
Type RM Length L Ch R = 1,4881,237,237,237
BEGIN DESCRIPTION:
TRIB 12 TO SALT CREEK 10.0
END DESCRIPTION:
XS GIS Cut Line= 3
      2401793.61     13588517.06      2401444.87     13588445.88
      2400839.99     13588296.44
#Sta/Elev= 30
  4565.7  475.29  4573.9  474.98  4651.0  471.63  4656.1  470.41  4667.7  470.64
  4727.6  468.61  4737.8  468.93  4767.5  467.01  4802.6  466.37  4867.3  463.34
  4931.8  461.89  4946.7  459.69  4952.4  459.56  4962.7  461.09  4973.0  461.18
  4988.2  459.91  5014.2  459.66  5022.5  458.79  5022.7  458.29  5026.2  458.29
  5026.5  458.79  5034.8  461.29  5071.1  464.65  5158.3  467.44  5354.1  472.05
  5395.3  471.27  5436.5  473.58  5527.0  476.36  5532.1  475.99  5544.7  476.79
#Mann=8,-1,0
  4565.7    0.12       0  4573.9   0.013       0  4667.7    0.05       0
  4767.5    0.12       0  4867.3    0.03       0  5022.5    0.03       0
  5026.5    0.03       0  5158.3    0.05       0
Bank Sta=5022.5,5026.5
Exp/Cntr=0.3,0.1

Type RM Length L Ch R = 1,4644,476,476,476
BEGIN DESCRIPTION:
TRIB 12 TO SALT CREEK 9.0
END DESCRIPTION:
XS GIS Cut Line= 3
      2401724.97     13588374.99      2401525.00     13588275.00
      2401075.02     13588125.01
#Sta/Elev= 30
  4768.6  470.40  4777.0  470.14  4782.5  469.09  4799.3  468.48  4849.6  465.73
  4866.4  465.41  4880.4  464.19  4888.8  464.19  4894.3  463.13  4933.5  462.23
  4961.4  460.57  4978.2  457.95  5034.3  458.50  5074.5  457.87  5074.8  457.37
  5078.3  457.37  5078.5  457.87  5087.0  459.57  5097.6  460.76  5108.1  460.56
  5160.6  462.06  5171.4  459.50  5192.5  459.44  5229.3  462.20  5234.6  463.52
  5255.7  465.15  5308.4  467.03  5340.0  467.48  5445.4  471.74  5466.5  472.02
#Mann=5,-1,0
  4768.6   0.013       0  4799.3    0.12       0  5074.5    0.05       0
  5078.5    0.12       0  5160.6    0.05       0
Bank Sta=5074.5,5078.5
Exp/Cntr=0.3,0.1

Type RM Length L Ch R = 1,4168,342,342,342
BEGIN DESCRIPTION:
Mapping XS cda2befb
END DESCRIPTION:
XS GIS Cut Line= 3
      2401973.66     13588243.39      2401573.28     13587909.00
      2401164.04     13587948.60
#Sta/Elev= 30
  4491.7  476.31  4558.5  472.75  4568.1  472.66  4574.8  471.25  4581.6  471.47
  4759.6  465.04  4809.1  463.86  4823.4  461.61  4887.2  458.72  4893.9  457.19
  4908.0  456.49  4915.8  457.59  4922.3  457.37  4930.1  458.19  4965.3  456.94
  4979.6  457.29  4986.1  456.01  5000.4  454.82  5025.2  454.56  5029.7  453.26
  5030.0  452.76  5033.7  453.26  5041.8  454.09  5061.9  453.96  5071.9  456.49
  5082.0  457.75  5212.6  461.66  5242.7  463.28  5282.9  464.12  5424.5  469.60
#Mann=5,-1,0
  4491.7    0.12       0  4558.5   0.013       0  4581.6    0.05       0
  5029.7    0.05       0  5033.7    0.05       0
Bank Sta=5029.7,5033.7
Exp/Cntr=0.3,0.1

Type RM Length L Ch R = 1,3826,281,281,281
BEGIN DESCRIPTION:
Mapping XS f356b6f8
END DESCRIPTION:
XS GIS Cut Line= 3
      2402061.69     13587658.20      2401630.48     13587645.00
      2401084.84     13587816.61
#Sta/Elev= 30
  4562.3  474.13  4719.1  466.20  4749.1  465.45  4809.1  462.42  4909.1  458.93
  4929.2  457.67  4949.2  455.15  4988.9  452.02  4999.5  451.62  5012.8  452.00
  5030.9  451.27  5039.9  452.48  5043.2  450.61  5043.4  450.11  5046.9  450.11
  5047.2  450.61  5051.9  453.35  5062.4  456.18  5072.3  456.92  5093.8  456.67
  5109.9  458.04  5156.7  457.49  5198.6  457.94  5379.5  463.83  5397.8  464.99
  5406.7  464.75  5439.1  466.10  5471.2  466.57  5492.2  467.62  5565.7  469.68
#Mann=3,-1,0
  4562.3    0.05       0  5043.2    0.05       0  5047.2    0.05       0
Bank Sta=5043.2,5047.2
Exp/Cntr=0.3,0.1

Type RM Length L Ch R = 1,3545,298,298,298
BEGIN DESCRIPTION:
Mapping XS 22464f40
END DESCRIPTION:
XS GIS Cut Line= 4
      2402259.69     13587429.40      2401815.28     13587310.60
      2401379.68     13587513.00      2401014.47     13587733.01
#Sta/Elev= 30
  4330.1  477.20  4438.5  472.63  4604.1  463.98  4719.1  459.12  4809.7  456.34
  4912.3  455.33  4929.7  453.09  4935.2  453.88  4952.6  451.45  4958.1  451.60
  4975.4  450.12  5009.0  449.46  5009.2  448.96  5013.0  449.46  5033.0  452.54
  5066.1  454.61  5072.5  453.30  5088.1  451.82  5100.9  452.38  5118.3  454.64
  5132.2  455.37  5176.4  456.20  5198.4  455.74  5356.7  460.19  5427.7  461.14
  5451.0  462.33  5574.1  465.00  5580.0  465.66  5626.1  466.00  5696.8  468.01
#Mann=3,-1,0
  4330.1    0.05       0  5009.0    0.05       0  5013.0    0.05       0
Bank Sta=5009,5013
Exp/Cntr=0.3,0.1

Type RM Length L Ch R = 1,3247,197,197,197
BEGIN DESCRIPTION:
Mapping XS 4585c086
END DESCRIPTION:
XS GIS Cut Line= 3
      2402242.08     13587288.60      2401555.68     13587143.40
      2401111.25     13586971.79
#Sta/Elev= 30
  4267.5  473.45  4277.4  472.95  4397.4  466.69  4445.9  463.25  4453.8  462.52
  4509.8  460.72  4560.9  459.76  4612.0  457.43  4755.1  453.74  4841.3  453.73
  4885.9  452.58  4928.9  453.28  4949.3  451.41  4959.6  450.06  4966.9  448.39
  4972.1  448.39  4980.2  447.09  4980.5  446.59  4984.0  446.59  4984.2  447.09
  5006.8  448.19  5012.7  449.80  5023.4  450.99  5036.8  453.73  5061.4  454.51
  5086.0  454.78  5162.8  453.39  5237.8  455.90  5430.8  460.86  5445.5  460.85
#Mann=5,-1,0
  4267.5    0.03       0  4277.4    0.04       0  4445.9    0.05       0
  4980.2    0.05       0  4984.2    0.05       0
Bank Sta=4980.2,4984.2
Exp/Cntr=0.3,0.1

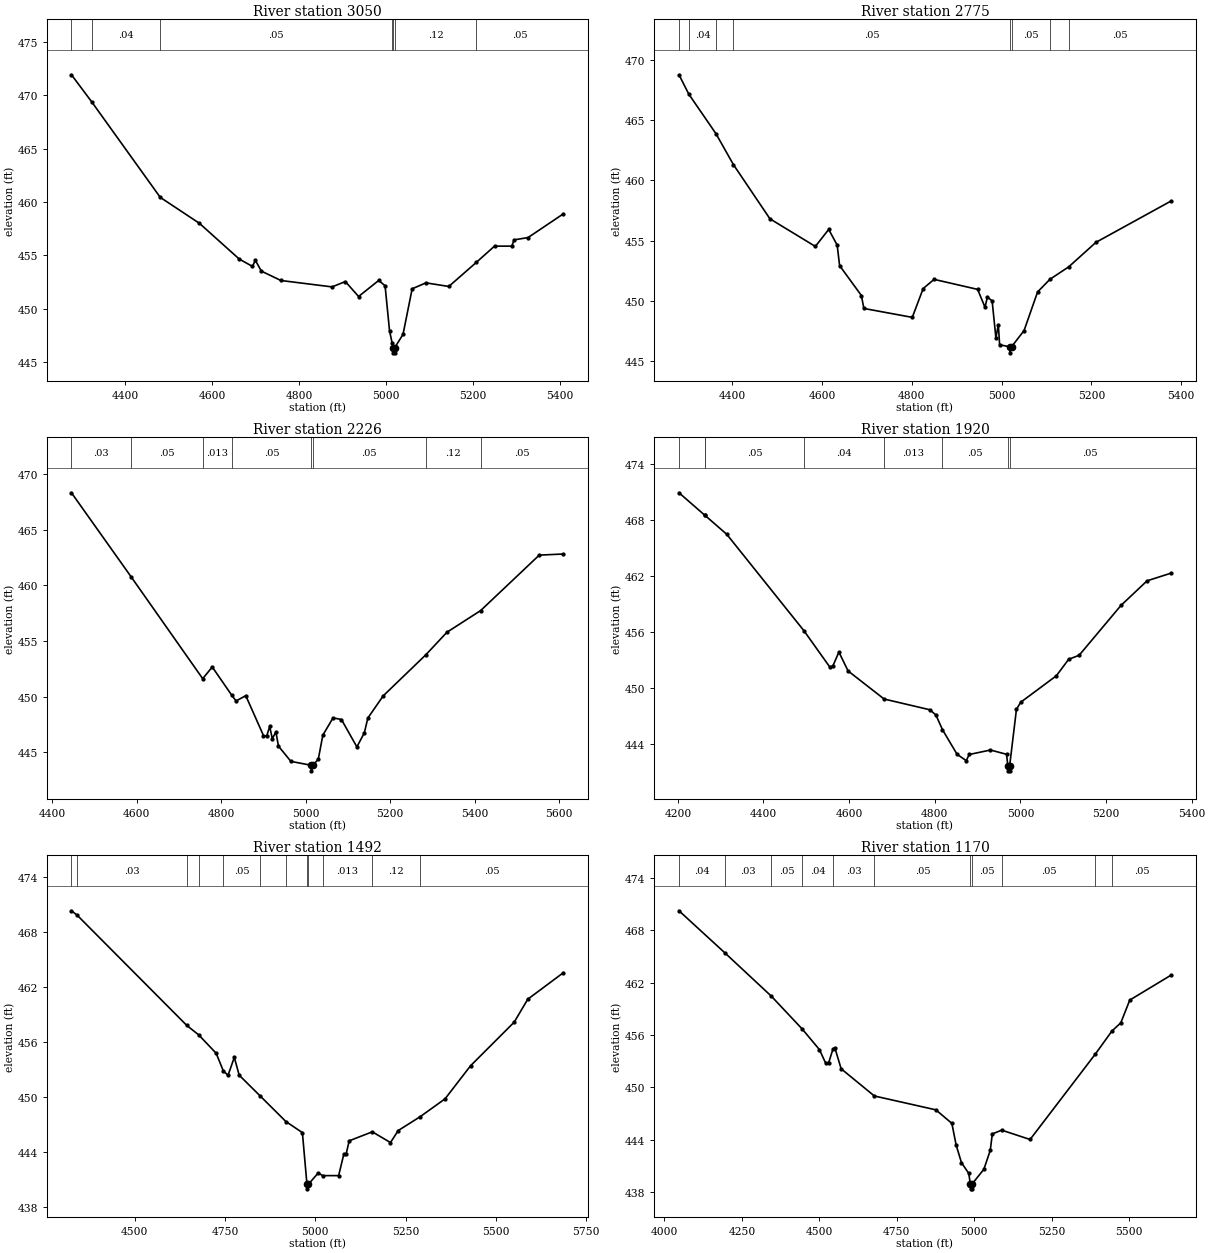
Type RM Length L Ch R = 1,3050,275,275,275
BEGIN DESCRIPTION:
Mapping XS f7c2db0c
END DESCRIPTION:
XS GIS Cut Line= 3
      2402334.49     13587095.00      2401599.68     13586963.00
      2401234.49     13586844.20
#Sta/Elev= 30
  4277.2  471.92  4324.0  469.37  4481.3  460.43  4571.3  458.00  4662.8  454.65
  4693.2  453.96  4699.9  454.53  4713.6  453.52  4758.6  452.64  4876.1  452.04
  4906.6  452.54  4937.1  451.14  4983.5  452.65  4998.0  452.14  5008.2  447.93
  5014.1  446.80  5016.4  446.36  5016.6  445.86  5020.1  445.86  5020.4  446.36
  5039.2  447.59  5060.2  451.86  5091.8  452.42  5144.4  452.08  5208.0  454.35
  5249.5  455.86  5289.2  455.86  5294.5  456.45  5326.4  456.66  5407.8  458.89
#Mann=7,-1,0
  4277.2    0.03       0  4324.0    0.04       0  4481.3    0.05       0
  5014.1    0.12       0  5016.4    0.05       0  5020.4    0.12       0
  5208.0    0.05       0
Bank Sta=5016.4,5020.4
Exp/Cntr=0.3,0.1

Type RM Length L Ch R = 1,2775,549,549,549
BEGIN DESCRIPTION:
Mapping XS 27ec7b53
END DESCRIPTION:
XS GIS Cut Line= 3
      2402343.29     13586971.80      2401678.88     13586707.80
      2401298.04     13586720.93
#Sta/Elev= 30
  4281.2  468.76  4303.1  467.15  4363.5  463.88  4402.3  461.32  4483.8  456.82
  4585.0  454.53  4614.7  455.94  4633.6  454.64  4639.0  452.94  4687.6  450.46
  4693.0  449.39  4800.9  448.65  4825.2  451.04  4849.5  451.80  4946.5  450.97
  4962.9  449.49  4968.3  450.33  4978.8  450.02  4987.2  446.95  4992.6  448.05
  4995.5  446.38  5018.0  446.21  5018.3  445.71  5022.0  446.21  5050.0  447.56
  5080.1  450.76  5107.7  451.81  5149.5  452.84  5210.1  454.87  5377.2  458.29
#Mann=8,-1,0
  4281.2    0.03       0  4303.1    0.04       0  4363.5    0.03       0
  4402.3    0.05       0  5018.0    0.05       0  5022.0    0.05       0
  5107.7    0.12       0  5149.5    0.05       0
Bank Sta=5018,5022
Exp/Cntr=0.3,0.1

Type RM Length L Ch R = 1,2226,306,306,306
BEGIN DESCRIPTION:
Mapping XS d7b0522b
END DESCRIPTION:
XS GIS Cut Line= 3
      2402448.89     13586826.60      2401964.88     13586474.60
      2401429.30     13586290.22
#Sta/Elev= 30
  4445.4  468.32  4586.9  460.76  4756.2  451.62  4778.8  452.67  4825.2  450.12
  4835.2  449.62  4858.2  450.09  4900.1  446.51  4907.7  446.46  4914.8  447.33
  4921.0  446.23  4929.5  446.83  4935.6  445.56  4965.0  444.19  5013.2  443.84
  5013.5  443.34  5017.2  443.84  5029.9  444.39  5040.7  446.55  5064.9  448.10
  5084.7  447.95  5121.3  445.49  5138.9  446.75  5147.2  448.08  5183.7  450.08
  5284.4  453.76  5334.5  455.79  5414.4  457.74  5553.1  462.72  5610.3  462.82
#Mann=8,-1,0
  4445.4    0.03       0  4586.9    0.05       0  4756.2   0.013       0
  4825.2    0.05       0  5013.2    0.05       0  5017.2    0.05       0
  5284.4    0.12       0  5414.4    0.05       0
Bank Sta=5013.2,5017.2
Exp/Cntr=0.3,0.1

Type RM Length L Ch R = 1,1920,428,428,428
BEGIN DESCRIPTION:
Mapping XS 6ce50cf3
END DESCRIPTION:
XS GIS Cut Line= 3
      2402572.12     13586795.84      2402052.88     13586241.40
      2401670.11     13586171.00
#Sta/Elev= 30
  4202.7  470.89  4262.8  468.49  4262.9  468.49  4314.3  466.44  4494.7  456.10
  4555.1  452.21  4561.9  452.33  4576.1  453.83  4597.5  451.81  4681.7  448.80
  4788.5  447.65  4802.7  447.09  4817.9  445.52  4852.1  442.88  4873.5  442.20
  4880.4  442.86  4930.0  443.34  4967.6  442.88  4970.7  441.61  4971.0  441.11
  4974.5  441.11  4974.7  441.61  4990.7  447.70  5000.8  448.46  5083.9  451.29
  5112.7  453.06  5137.0  453.48  5234.7  458.82  5295.7  461.46  5351.5  462.28
#Mann=8,-1,0
  4202.7    0.04       0  4262.8    0.03       0  4262.9    0.05       0
  4494.7    0.04       0  4681.7   0.013       0  4817.9    0.05       0
  4970.7    0.05       0  4974.7    0.05       0
Bank Sta=4970.7,4974.7
Exp/Cntr=0.3,0.1

Type RM Length L Ch R = 1,1492,322,322,322
BEGIN DESCRIPTION:
Mapping XS 101d0a0f
END DESCRIPTION:
XS GIS Cut Line= 4
      2402611.69     13586769.45      2402506.08     13586259.00
      2402171.68     13586012.60      2401749.68     13586060.95
#Sta/Elev= 30
  4325.3  470.28  4340.8  469.81  4644.6  457.79  4677.3  456.77  4725.8  454.76
  4745.8  452.82  4758.7  452.37  4776.0  454.32  4789.4  452.38  4847.4  450.12
  4918.7  447.33  4964.4  446.12  4977.0  440.50  4977.3  440.00  4981.0  440.50
  5008.3  441.73  5020.3  441.44  5064.7  441.44  5079.3  443.82  5085.5  443.80
  5093.9  445.23  5157.9  446.21  5208.1  445.04  5229.7  446.35  5290.1  447.85
  5359.2  449.80  5429.7  453.40  5550.5  458.15  5588.1  460.65  5686.7  463.54
#Mann=12,-1,0
  4325.3    0.04       0  4340.8    0.03       0  4644.6    0.05       0
  4677.3    0.04       0  4745.8    0.05       0  4847.4    0.03       0
  4918.7    0.05       0  4977.0    0.05       0  4981.0    0.05       0
  5020.3   0.013       0  5157.9    0.12       0  5290.1    0.05       0
Bank Sta=4977,4981
Exp/Cntr=0.3,0.1

Type RM Length L Ch R = 1,1170,341,341,341
BEGIN DESCRIPTION:
Mapping XS a7591a2f
END DESCRIPTION:
XS GIS Cut Line= 4
      2402646.88     13586756.21      2402572.08     13585937.80
      2402180.48     13585836.60      2401824.05     13585898.21
#Sta/Elev= 30
  4047.2  470.26  4195.1  465.44  4345.7  460.45  4444.9  456.70  4500.3  454.35
  4520.4  452.80  4530.4  452.84  4544.2  454.41  4550.5  454.52  4570.6  452.14
  4677.8  449.02  4876.3  447.43  4928.0  445.88  4941.8  443.39  4959.0  441.37
  4982.5  440.14  4987.9  438.87  4988.2  438.37  4991.7  438.37  4991.9  438.87
  5031.3  440.61  5051.9  442.78  5058.6  444.67  5088.8  445.10  5180.5  444.03
  5391.4  453.84  5444.5  456.46  5473.3  457.41  5502.3  460.02  5635.2  462.87
#Mann=11,-1,0
  4047.2    0.04       0  4195.1    0.03       0  4345.7    0.05       0
  4444.9    0.04       0  4544.2    0.03       0  4677.8    0.05       0
  4987.9    0.03       0  4991.9    0.05       0  5088.8    0.05       0
  5391.4    0.12       0  5444.5    0.05       0
Bank Sta=4987.9,4991.9
Exp/Cntr=0.3,0.1

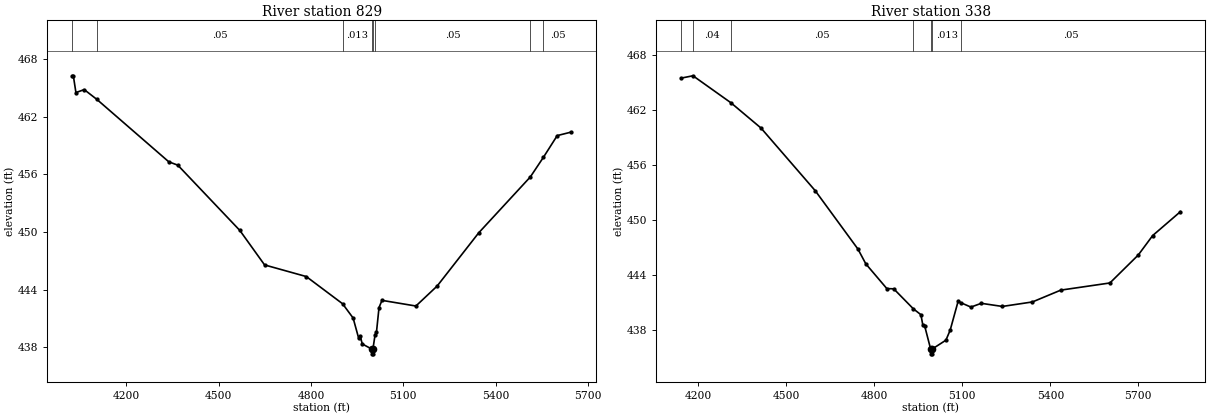
Type RM Length L Ch R = 1,829,491,491,491
BEGIN DESCRIPTION:
Mapping XS a7591a2faaa
END DESCRIPTION:
XS GIS Cut Line= 4
      2403308.15     13586079.23      2402671.56     13585659.50
      2402325.29     13585509.10      2401902.08     13585743.44
#Sta/Elev= 30
  4022.7  466.28  4027.6  466.28  4036.0  464.53  4063.0  464.84  4104.1  463.82
  4337.9  457.32  4367.2  456.97  4568.9  450.17  4649.3  446.58  4784.8  445.37
  4902.7  442.54  4937.1  441.05  4955.1  438.95  4960.5  439.13  4966.8  438.35
  4997.5  437.82  4997.8  437.32  5001.3  437.32  5001.5  437.82  5008.6  439.33
  5012.9  439.55  5021.3  442.14  5030.9  442.89  5141.2  442.30  5210.2  444.38
  5345.3  449.92  5513.3  455.75  5555.9  457.80  5600.6  460.05  5646.5  460.42
#Mann=8,-1,0
  4022.7   0.013       0  4104.1    0.05       0  4902.7   0.013       0
  4997.5    0.03       0  5001.5   0.013       0  5008.6    0.05       0
  5513.3    0.12       0  5555.9    0.05       0
Bank Sta=4997.5,5001.5
Exp/Cntr=0.3,0.1

Type RM Length L Ch R = 1,338,0,0,0
BEGIN DESCRIPTION:
Mapping XS a7591a2faa
END DESCRIPTION:
XS GIS Cut Line= 4
      2403329.13     13586019.77      2402898.91     13585404.17
      2402678.55     13585236.28      2402090.95     13585568.56
#Sta/Elev= 30
  4140.4  465.42  4181.5  465.68  4310.7  462.74  4413.4  459.98  4598.2  453.15
  4743.9  446.78  4770.9  445.16  4842.4  442.47  4866.0  442.44  4933.2  440.25
  4958.6  439.62  4964.9  438.54  4971.8  438.35  4992.0  435.85  4992.2  435.35
  4995.7  435.35  4996.0  435.85  5043.9  436.84  5058.4  437.93  5085.5  441.08
  5096.7  440.90  5129.1  440.45  5164.5  440.86  5236.3  440.52  5338.8  441.01
  5435.6  442.30  5603.0  443.08  5699.7  446.13  5748.8  448.25  5843.5  450.86
#Mann=7,-1,0
  4140.4   0.013       0  4181.5    0.04       0  4310.7    0.05       0
  4933.2   0.013       0  4992.0    0.03       0  4996.0   0.013       0
  5096.7    0.05       0
Bank Sta=4992,4996
Exp/Cntr=0.3,0.1

Chan Stop Cuts=-1