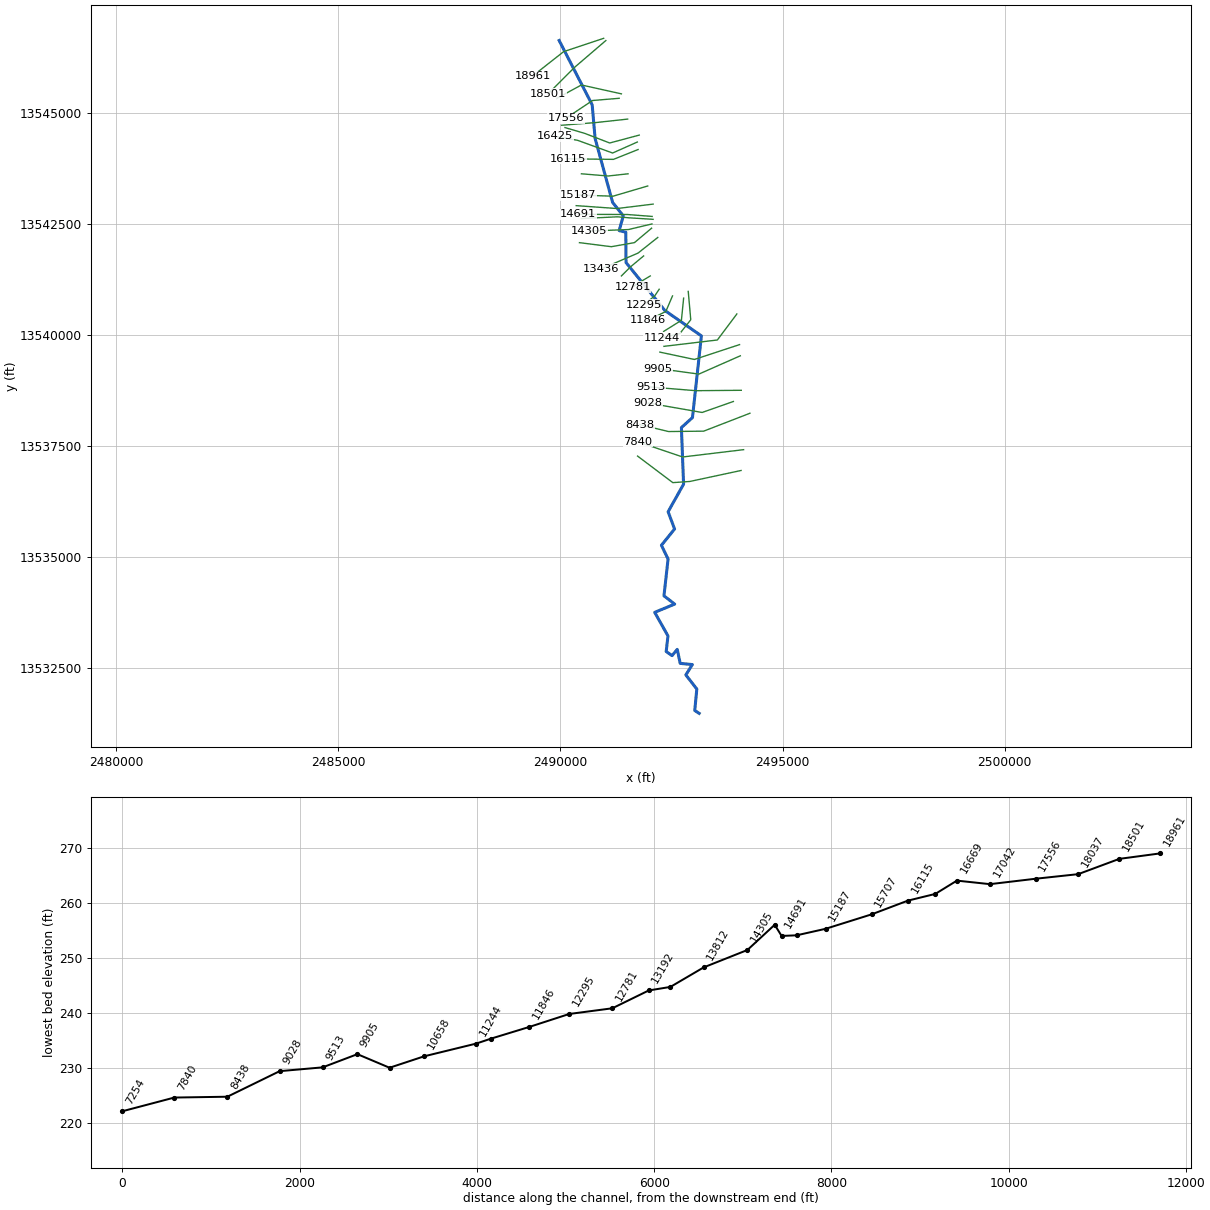
--- TRIB 12 TO TWELVEMILE CREEK.prj (project) ---

Proj Title=TRIB 12 TO TWELVEMILE CREEK Base Level Engineering
Current Plan=p01
Default Exp/Contr=0.3,0.1
English Units
Geom File=g01
Flow File=f01
Plan File=p01
Y Axis Title=Elevation
X Axis Title(PF)=Main Channel Distance
X Axis Title(XS)=Station
BEGIN DESCRIPTION:
TRIB 12 TO TWELVEMILE CREEK
END DESCRIPTION:
DSS Export Rating Curves= 0
DSS Export Rating Curve Sorted= 0
DSS Export Volume Flow Curves= 0
DXF OffsetX= 0
DXF OffsetY= 0
DXF ScaleX= 1
DXF ScaleY= 10

--- TRIB 12 TO TWELVEMILE CREEK.p01 (plan) ---

Plan Title=Multiple Run
Short Identifier=Multiple
Geom File=g01
Flow File=f01
Subcritical Flow
K Sum by GR= 0
Std Step Tol= 0.01
Critical Tol= 0.01
Num of Std Step Trials= 20
Max Error Tol= 0.3
Flow Tol Ratio= 0.001
Split Flow NTrial= 30
Split Flow Tol= 0.02
Split Flow Ratio= 0.02
Log Output Level= 0
Friction Slope Method= 1
Unsteady Friction Slope Method= 2
Unsteady Bridges Friction Slope Method= 1
Parabolic Critical Depth
Global Vel Dist=  1 , 1 , 1
Global Log Level= 0
CheckData=True
Encroach Param= -1, 0, 0, 0
BEGIN DESCRIPTION:
Multiple Run
END DESCRIPTION:

--- TRIB 12 TO TWELVEMILE CREEK.f01 (steady flow) ---

Flow Title=Multiple
Number of Profiles=7
Profile Names=10-year,25-year,50-year,1pct_min,100-year,1pct_plu,500-year
River Rch & RM= TRIB 12 TO TWELV,Reach-1,18961
     636    1013    1348     868    1731    3454    2825
River Rch & RM= TRIB 12 TO TWELV,Reach-1,13436
     709    1137    1519     982    1959    3909    3223
River Rch & RM= TRIB 12 TO TWELV,Reach-1,10658
    1325    2194    2996    1973    3938    7856    6737
River Rch & RM= TRIB 12 TO TWELV,Reach-1,3479
    1483    2467    3382    2235    4459    8897    7679
Boundary for River Rch & Prof#=TRIB 12 TO TWELV,Reach-1,1
Up Type=0
Dn Type=3
Dn Slope=0.005
Boundary for River Rch & Prof#=TRIB 12 TO TWELV,Reach-1,2
Up Type=0
Dn Type=3
Dn Slope=0.005
Boundary for River Rch & Prof#=TRIB 12 TO TWELV,Reach-1,3
Up Type=0
Dn Type=3
Dn Slope=0.005
Boundary for River Rch & Prof#=TRIB 12 TO TWELV,Reach-1,4
Up Type=0
Dn Type=3
Dn Slope=0.005
Boundary for River Rch & Prof#=TRIB 12 TO TWELV,Reach-1,5
Up Type=0
Dn Type=3
Dn Slope=0.005
Boundary for River Rch & Prof#=TRIB 12 TO TWELV,Reach-1,6
Up Type=0
Dn Type=3
Dn Slope=0.005
Boundary for River Rch & Prof#=TRIB 12 TO TWELV,Reach-1,7
Up Type=0
Dn Type=3
Dn Slope=0.005

--- TRIB 12 TO TWELVEMILE CREEK.g01 (geometry) ---

Geom Title=Existing Conditions

River Reach=TRIB 12 TO TWELV,Reach-1
Reach XY= 30
      2489975.00     13546625.00      2490717.21     13545178.43
      2490783.08     13544421.70      2491177.06     13542980.85
      2491416.96     13542678.32      2491324.94     13542344.76
      2491474.34     13542309.73      2491478.82     13541626.59
      2492350.99     13540547.67      2493175.00     13539975.00
      2492973.95     13538135.43      2492725.19     13537909.91
      2492773.80     13536635.50      2492426.04     13536014.56
      2492571.54     13535626.50      2492275.24     13535259.78
      2492425.21     13534950.09      2492332.69     13534121.33
      2492574.47     13533935.35      2492124.41     13533750.00
      2492422.95     13533219.14      2492382.80     13532868.79
      2492514.51     13532775.49      2492631.84     13532916.25
      2492697.70     13532600.84      2492971.64     13532573.75
      2492824.99     13532340.47      2493071.87     13532023.37
      2493025.32     13531540.05      2493125.00     13531475.00

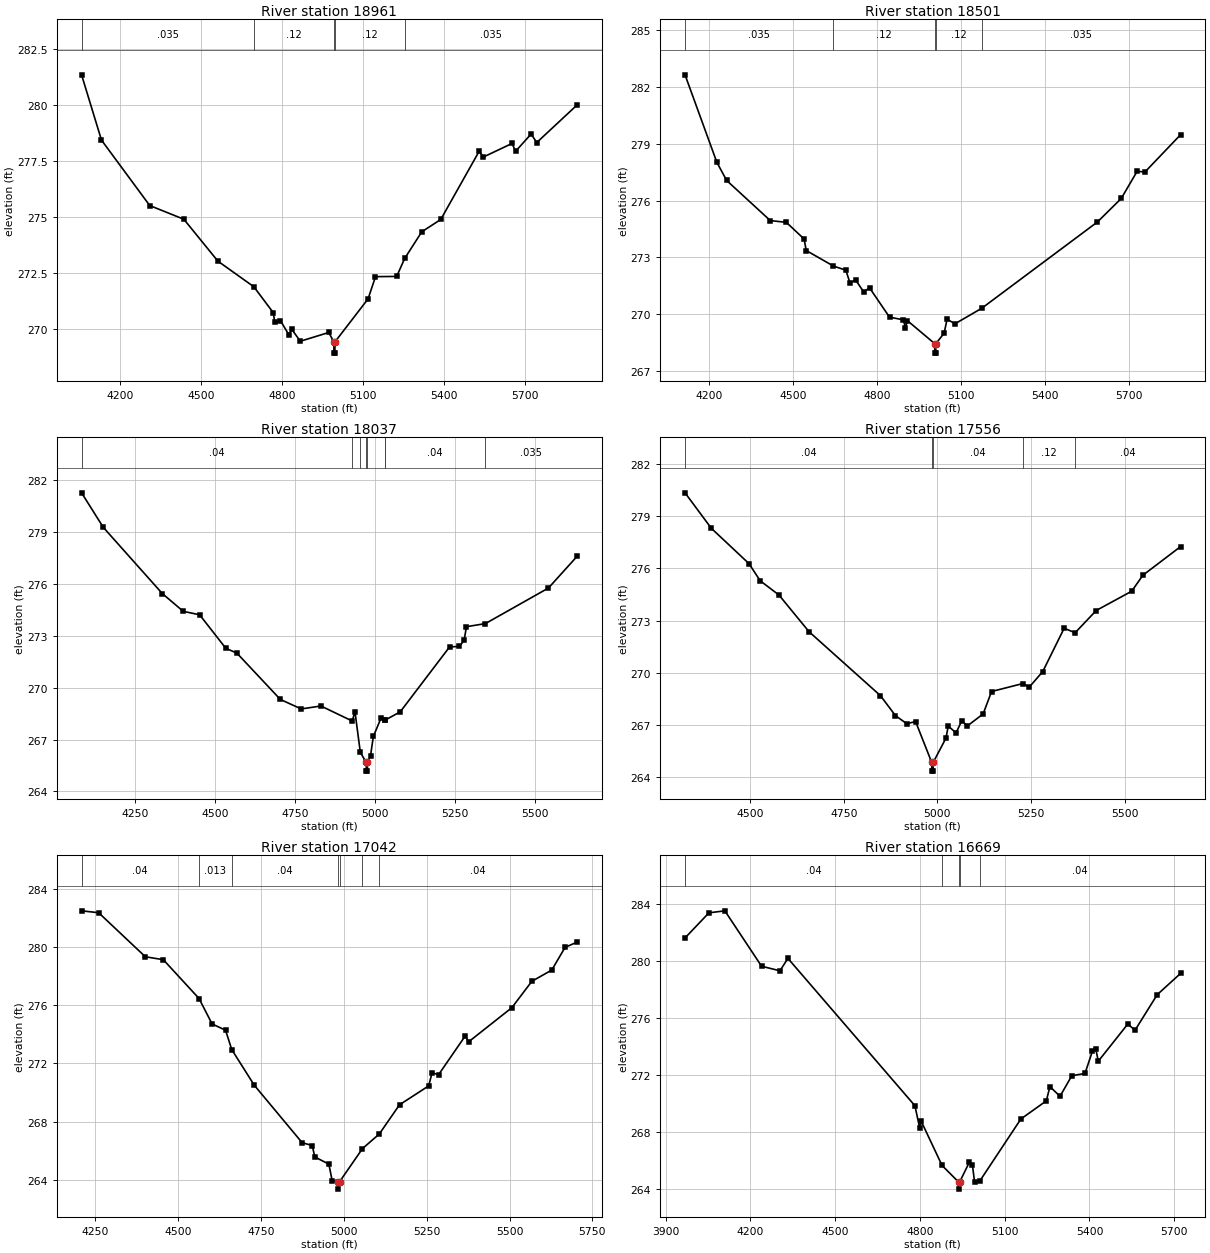
Type RM Length L Ch R = 1,18961,460,460,460
BEGIN DESCRIPTION:
TRIB 12 TO TWELVEMILE CREEK 30.0
END DESCRIPTION:
XS GIS Cut Line= 3
      2490975.01     13546675.00      2490075.00     13546375.00
      2489375.01     13545825.01
#Sta/Elev= 30
  4055.6  281.34  4129.4  278.43  4308.6  275.51  4435.1  274.90  4561.6  273.03
  4694.8  271.89  4767.1  270.73  4772.4  270.30  4793.5  270.38  4825.1  269.74
  4835.6  269.99  4867.3  269.46  4972.7  269.85  4991.7  269.43  4992.0  268.93
  4995.5  268.93  4995.7  269.43  5118.7  271.35  5146.2  272.34  5224.8  272.35
  5254.4  273.15  5317.9  274.34  5388.4  274.89  5531.2  277.94  5545.7  277.67
  5652.9  278.28  5665.9  277.93  5723.7  278.70  5744.5  278.32  5894.5  280.00
#Mann=5,-1,0
  4055.6   0.035       0  4694.8    0.12       0  4991.7    0.05       0
  4995.7    0.12       0  5254.4   0.035       0
Bank Sta=4991.7,4995.7
Exp/Cntr=0.3,0.1

Type RM Length L Ch R = 1,18501,464,464,464
BEGIN DESCRIPTION:
TRIB 12 TO TWELVEMILE CREEK 29.0
END DESCRIPTION:
XS GIS Cut Line= 3
      2491025.02     13546625.01      2490325.00     13546025.00
      2489725.00     13545425.00
#Sta/Elev= 30
  4113.9  282.64  4227.5  278.02  4262.6  277.06  4418.5  274.94  4475.6  274.85
  4539.2  273.97  4546.9  273.36  4643.9  272.54  4688.5  272.32  4702.8  271.66
  4723.6  271.80  4752.2  271.17  4773.0  271.39  4844.4  269.84  4893.7  269.70
  4901.4  269.28  4908.0  269.66  5005.9  268.44  5006.1  267.94  5009.6  267.94
  5009.9  268.44  5039.4  268.99  5050.0  269.73  5078.3  269.49  5174.0  270.31
  5587.4  274.87  5672.3  276.11  5728.8  277.54  5757.1  277.51  5884.4  279.48
#Mann=5,-1,0
  4113.9   0.035       0  4643.9    0.12       0  5005.9    0.05       0
  5009.9    0.12       0  5174.0   0.035       0
Bank Sta=5005.9,5009.9
Exp/Cntr=0.3,0.1

Type RM Length L Ch R = 1,18037,481,481,481
BEGIN DESCRIPTION:
TRIB 12 TO TWELVEMILE CREEK 28.0
END DESCRIPTION:
XS GIS Cut Line= 3
      2491374.99     13545425.00      2490475.00     13545625.00
      2489925.04     13545325.02
#Sta/Elev= 30
  4083.5  281.28  4151.4  279.28  4335.7  275.45  4401.1  274.42  4452.3  274.22
  4534.2  272.28  4568.8  272.00  4704.5  269.32  4769.8  268.77  4831.3  268.94
  4929.2  268.07  4937.6  268.62  4954.4  266.26  4972.7  265.67  4973.0  265.17
  4976.5  265.17  4976.7  265.67  4986.2  266.06  4995.2  267.18  5019.2  268.25
  5030.1  268.15  5031.6  268.12  5079.0  268.60  5233.3  272.36  5264.1  272.39
  5278.8  272.75  5285.9  273.53  5345.2  273.71  5542.2  275.77  5631.9  277.61
#Mann=8,-1,0
  4083.5    0.04       0  4929.2    0.12       0  4954.4    0.05       0
  4972.7    0.05       0  4976.7    0.05       0  5030.1    0.12       0
  5031.6    0.04       0  5345.2   0.035       0
Bank Sta=4972.7,4976.7
Exp/Cntr=0.3,0.1

Type RM Length L Ch R = 1,17556,514,514,514
BEGIN DESCRIPTION:
TRIB 12 TO TWELVEMILE CREEK 27.0
END DESCRIPTION:
XS GIS Cut Line= 3
      2491324.98     13545325.00      2490725.00     13545275.00
      2490124.97     13544874.98
#Sta/Elev= 30
  4326.3  280.35  4396.5  278.31  4496.9  276.28  4527.0  275.29  4577.1  274.47
  4657.4  272.36  4848.1  268.68  4888.2  267.53  4918.3  267.07  4941.9  267.19
  4984.9  264.84  4985.2  264.34  4988.7  264.34  4988.9  264.84  5023.0  266.24
  5029.0  266.93  5050.0  266.54  5065.1  267.24  5080.1  266.94  5122.2  267.63
  5144.7  268.92  5228.5  269.38  5245.3  269.17  5281.4  270.07  5338.5  272.56
  5367.8  272.30  5424.1  273.58  5518.8  274.69  5548.8  275.61  5649.5  277.26
#Mann=5,-1,0
  4326.3    0.04       0  4984.9    0.04       0  4988.9    0.04       0
  5228.5    0.12       0  5367.8    0.04       0
Bank Sta=4984.9,4988.9
Exp/Cntr=0.3,0.1

Type RM Length L Ch R = 1,17042,373,373,373
BEGIN DESCRIPTION:
Mapping XS 5327fde9
END DESCRIPTION:
XS GIS Cut Line= 3
      2491516.17     13544856.58      2490800.06     13544778.46
      2490028.71     13544717.79
#Sta/Elev= 30
  4209.9  282.50  4261.4  282.37  4402.2  279.34  4456.3  279.14  4564.0  276.47
  4603.4  274.72  4644.0  274.29  4662.6  272.96  4730.4  270.51  4875.0  266.55
  4905.2  266.36  4913.1  265.57  4955.4  265.08  4965.4  263.94  4983.5  263.86
  4983.7  263.36  4987.5  263.86  5056.8  266.15  5107.4  267.15  5168.4  269.16
  5256.3  270.46  5266.4  271.35  5286.4  271.24  5366.7  273.90  5376.7  273.49
  5507.1  275.84  5567.3  277.65  5627.5  278.43  5667.6  279.99  5704.0  280.35
#Mann=7,-1,0
  4209.9    0.04       0  4564.0   0.013       0  4662.6    0.04       0
  4983.5    0.04       0  4987.5    0.04       0  5056.8    0.12       0
  5107.4    0.04       0
Bank Sta=4983.5,4987.5
Exp/Cntr=0.3,0.1

Type RM Length L Ch R = 1,16669,244,244,244
BEGIN DESCRIPTION:
Mapping XS 81875306
END DESCRIPTION:
XS GIS Cut Line= 4
      2491776.61     13544496.34      2491112.56     13544318.39
      2490548.33     13544535.41      2490105.58     13544665.62
#Sta/Elev= 30
  3969.0  281.59  4053.5  283.35  4109.9  283.49  4239.8  279.61  4304.8  279.29
  4333.0  280.16  4782.4  269.84  4799.4  268.26  4804.7  268.75  4878.3  265.66
  4936.7  264.50  4936.9  264.00  4940.7  264.50  4975.3  265.90  4986.0  265.66
  4993.3  264.52  5011.3  264.55  5157.2  268.91  5247.2  270.18  5260.1  271.18
  5295.7  270.50  5337.4  271.94  5384.0  272.10  5410.4  273.66  5422.5  273.79
  5431.2  272.96  5535.5  275.56  5561.2  275.13  5639.7  277.62  5722.5  279.11
#Mann=5,-1,0
  3969.0    0.04       0  4878.3   0.013       0  4936.7    0.03       0
  4940.7   0.013       0  5011.3    0.04       0
Bank Sta=4936.7,4940.7
Exp/Cntr=0.3,0.1

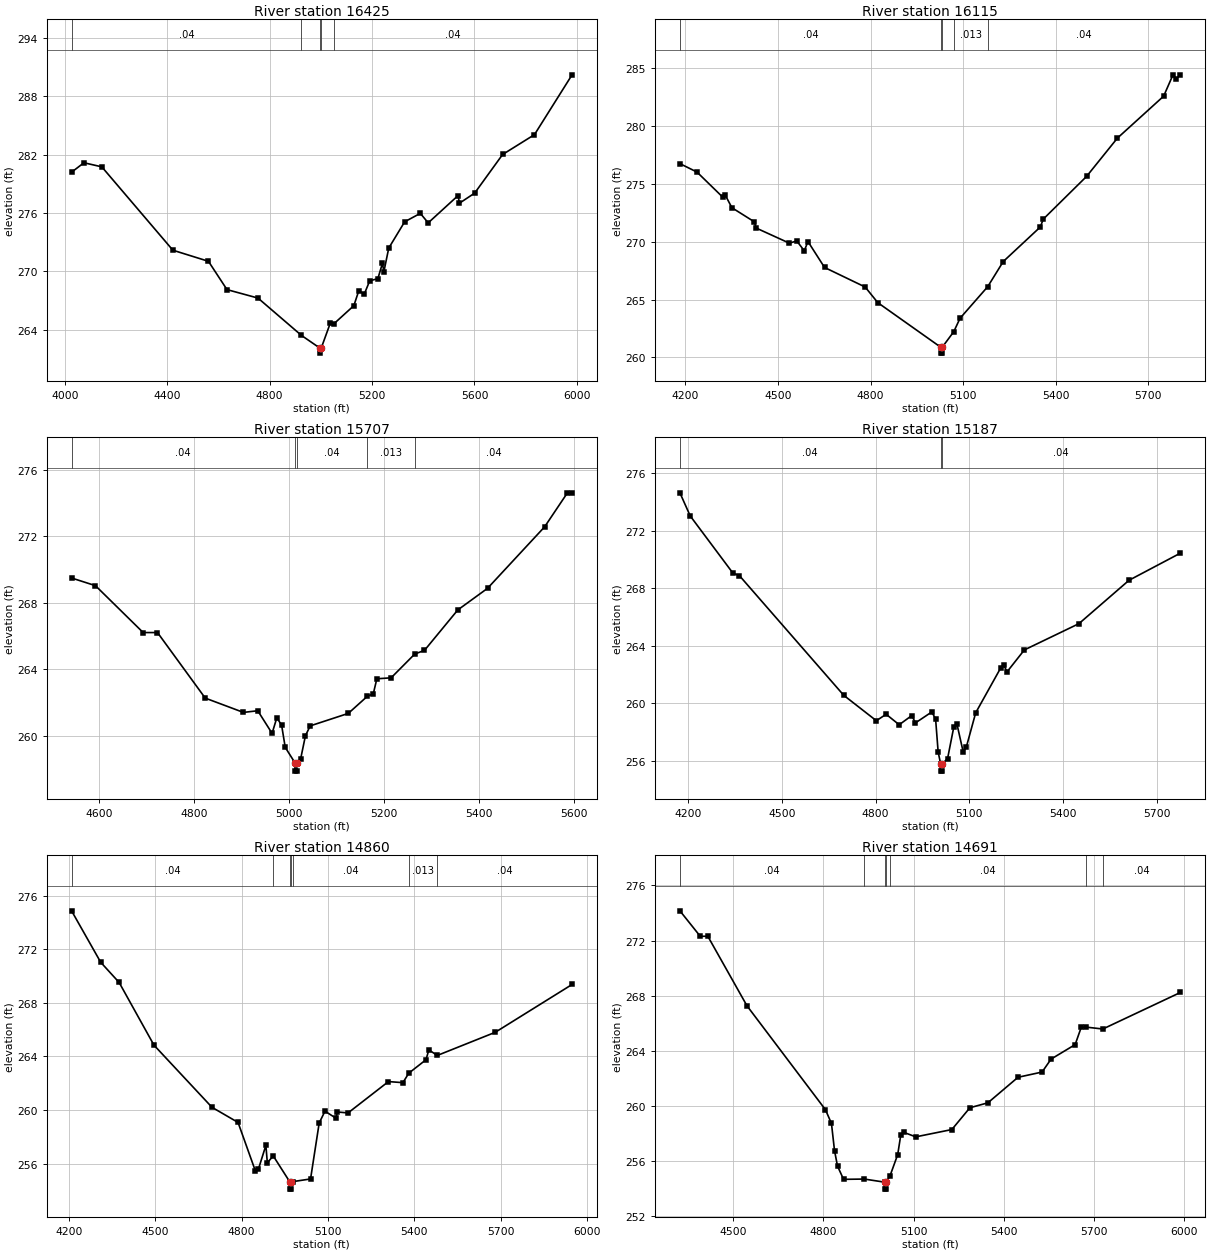
Type RM Length L Ch R = 1,16425,310,310,310
BEGIN DESCRIPTION:
Mapping XS 6c441678
END DESCRIPTION:
XS GIS Cut Line= 4
      2491733.25     13544340.10      2491177.67     13544092.70
      2490387.74     13544379.16      2489889.26     13544465.85
#Sta/Elev= 30
  4026.7  280.19  4075.1  281.16  4144.8  280.74  4422.3  272.17  4561.2  271.03
  4633.6  268.12  4754.7  267.25  4924.5  263.41  4997.4  262.09  4997.6  261.59
  5001.4  262.09  5037.1  264.68  5050.0  264.58  5129.0  266.47  5148.3  268.00
  5169.6  267.65  5190.9  269.02  5222.8  269.25  5240.8  270.83  5246.2  269.95
  5265.3  272.39  5327.4  275.09  5388.6  275.96  5419.3  274.98  5536.1  277.79
  5541.2  277.00  5600.8  278.04  5709.9  282.01  5834.3  284.05  5981.1  290.20
#Mann=5,-1,0
  4026.7    0.04       0  4924.5   0.013       0  4997.4    0.03       0
  5001.4   0.013       0  5050.0    0.04       0
Bank Sta=4997.4,5001.4
Exp/Cntr=0.3,0.1

Type RM Length L Ch R = 1,16115,408,408,408
BEGIN DESCRIPTION:
Mapping XS 8ffce5a7
END DESCRIPTION:
XS GIS Cut Line= 3
      2491750.60     13544170.83      2491195.03     13543949.47
      2490170.75     13543962.49
#Sta/Elev= 30
  4182.0  276.74  4237.4  276.01  4321.0  273.84  4328.0  274.07  4350.6  272.93
  4423.4  271.71  4428.8  271.18  4536.7  269.87  4560.9  270.06  4585.2  269.21
  4597.1  270.01  4650.9  267.77  4782.6  266.08  4823.5  264.73  5028.1  260.87
  5028.3  260.37  5031.8  260.37  5032.1  260.87  5069.9  262.23  5090.1  263.38
  5179.8  266.11  5230.1  268.28  5350.1  271.26  5360.1  271.95  5500.1  275.63
  5600.1  278.94  5750.2  282.57  5780.2  284.40  5790.2  284.05  5804.4  284.41
#Mann=5,-1,0
  4182.0    0.04       0  5028.1    0.04       0  5032.1    0.04       0
  5069.9   0.013       0  5179.8    0.04       0
Bank Sta=5028.1,5032.1
Exp/Cntr=0.3,0.1

Type RM Length L Ch R = 1,15707,520,520,520
BEGIN DESCRIPTION:
TRIB 12 TO TWELVEMILE CREEK 23.0
END DESCRIPTION:
XS GIS Cut Line= 3
      2491525.00     13543625.00      2491075.00     13543575.00
      2490475.05     13543625.00
#Sta/Elev= 30
  4542.0  269.50  4592.3  269.04  4692.9  266.22  4723.1  266.22  4823.7  262.28
  4904.2  261.42  4934.4  261.52  4964.6  260.16  4974.6  261.10  4984.7  260.65
  4992.3  259.32  5012.8  258.39  5013.1  257.89  5016.6  257.89  5016.8  258.39
  5024.9  258.64  5034.9  260.02  5044.9  260.61  5125.2  261.36  5165.4  262.39
  5177.9  262.54  5185.4  263.44  5215.5  263.50  5265.3  264.93  5285.8  265.15
  5356.0  267.58  5418.7  268.88  5539.1  272.58  5586.8  274.61  5596.8  274.62
#Mann=5,-1,0
  4542.0    0.04       0  5012.8    0.04       0  5016.8    0.04       0
  5165.4   0.013       0  5265.3    0.04       0
Bank Sta=5012.8,5016.8
Exp/Cntr=0.3,0.1

Type RM Length L Ch R = 1,15187,327,327,327
BEGIN DESCRIPTION:
Mapping XS e43c6225
END DESCRIPTION:
XS GIS Cut Line= 3
      2491967.61     13543350.51      2491186.35     13543120.47
      2490400.80     13543146.51
#Sta/Elev= 30
  4174.3  274.65  4207.3  273.04  4343.8  269.06  4364.7  268.88  4698.2  260.55
  4802.5  258.78  4833.8  259.23  4875.5  258.50  4915.8  259.14  4927.6  258.63
  4979.7  259.39  4991.9  258.91  5000.1  256.60  5008.1  255.77  5008.3  255.27
  5011.8  255.27  5012.1  255.77  5030.1  256.13  5050.1  258.34  5060.1  258.56
  5080.1  256.61  5090.1  256.94  5120.1  259.33  5200.2  262.46  5210.2  262.65
  5220.2  262.18  5275.7  263.71  5450.3  265.54  5610.4  268.56  5774.7  270.45
#Mann=3,-1,0
  4174.3    0.04       0  5008.1    0.04       0  5012.1    0.04       0
Bank Sta=5008.1,5012.1
Exp/Cntr=0.3,0.1

Type RM Length L Ch R = 1,14860,169,169,169
BEGIN DESCRIPTION:
Mapping XS 266aa967
END DESCRIPTION:
XS GIS Cut Line= 3
      2492089.11     13542942.52      2491277.49     13542842.70
      2490358.72     13542907.70
#Sta/Elev= 30
  4209.1  274.87  4310.3  271.03  4374.4  269.52  4495.4  264.84  4696.9  260.20
  4787.5  259.07  4848.0  255.43  4858.1  255.57  4884.2  257.36  4889.2  256.06
  4909.8  256.57  4968.5  254.59  4968.7  254.09  4972.2  254.09  4972.5  254.59
  4977.7  254.65  5039.4  254.85  5069.4  259.03  5089.5  259.91  5127.4  259.39
  5132.5  259.85  5169.7  259.78  5310.0  262.12  5360.2  262.04  5380.8  262.75
  5440.4  263.75  5450.4  264.49  5479.6  264.07  5681.0  265.80  5947.9  269.37
#Mann=7,-1,0
  4209.1    0.04       0  4909.8     0.1       0  4968.5    0.04       0
  4972.5     0.1       0  4977.7    0.04       0  5380.8   0.013       0
  5479.6    0.04       0
Bank Sta=4968.5,4972.5
Exp/Cntr=0.3,0.1

Type RM Length L Ch R = 1,14691,78,78,78
BEGIN DESCRIPTION:
Mapping XS e0d684d9
END DESCRIPTION:
XS GIS Cut Line= 3
      2492067.43     13542664.75      2491507.53     13542708.15
      2490405.12     13542712.49
#Sta/Elev= 30
  4323.2  274.16  4391.0  272.31  4415.9  272.32  4546.3  267.27  4807.1  259.74
  4827.1  258.74  4837.2  256.78  4847.2  255.65  4867.3  254.69  4936.5  254.71
  5005.3  254.48  5005.6  253.98  5009.1  253.98  5009.3  254.48  5021.7  254.94
  5047.3  256.48  5057.3  257.87  5067.3  258.10  5107.3  257.77  5227.3  258.30
  5287.3  259.88  5347.3  260.24  5447.3  262.09  5527.3  262.47  5557.3  263.41
  5637.3  264.46  5657.3  265.70  5672.9  265.73  5729.3  265.59  5987.2  268.24
#Mann=7,-1,0
  4323.2    0.04       0  4936.5     0.1       0  5005.3    0.05       0
  5009.3     0.1       0  5021.7    0.04       0  5672.9   0.013       0
  5729.3    0.04       0
Bank Sta=5005.3,5009.3
Exp/Cntr=0.3,0.1

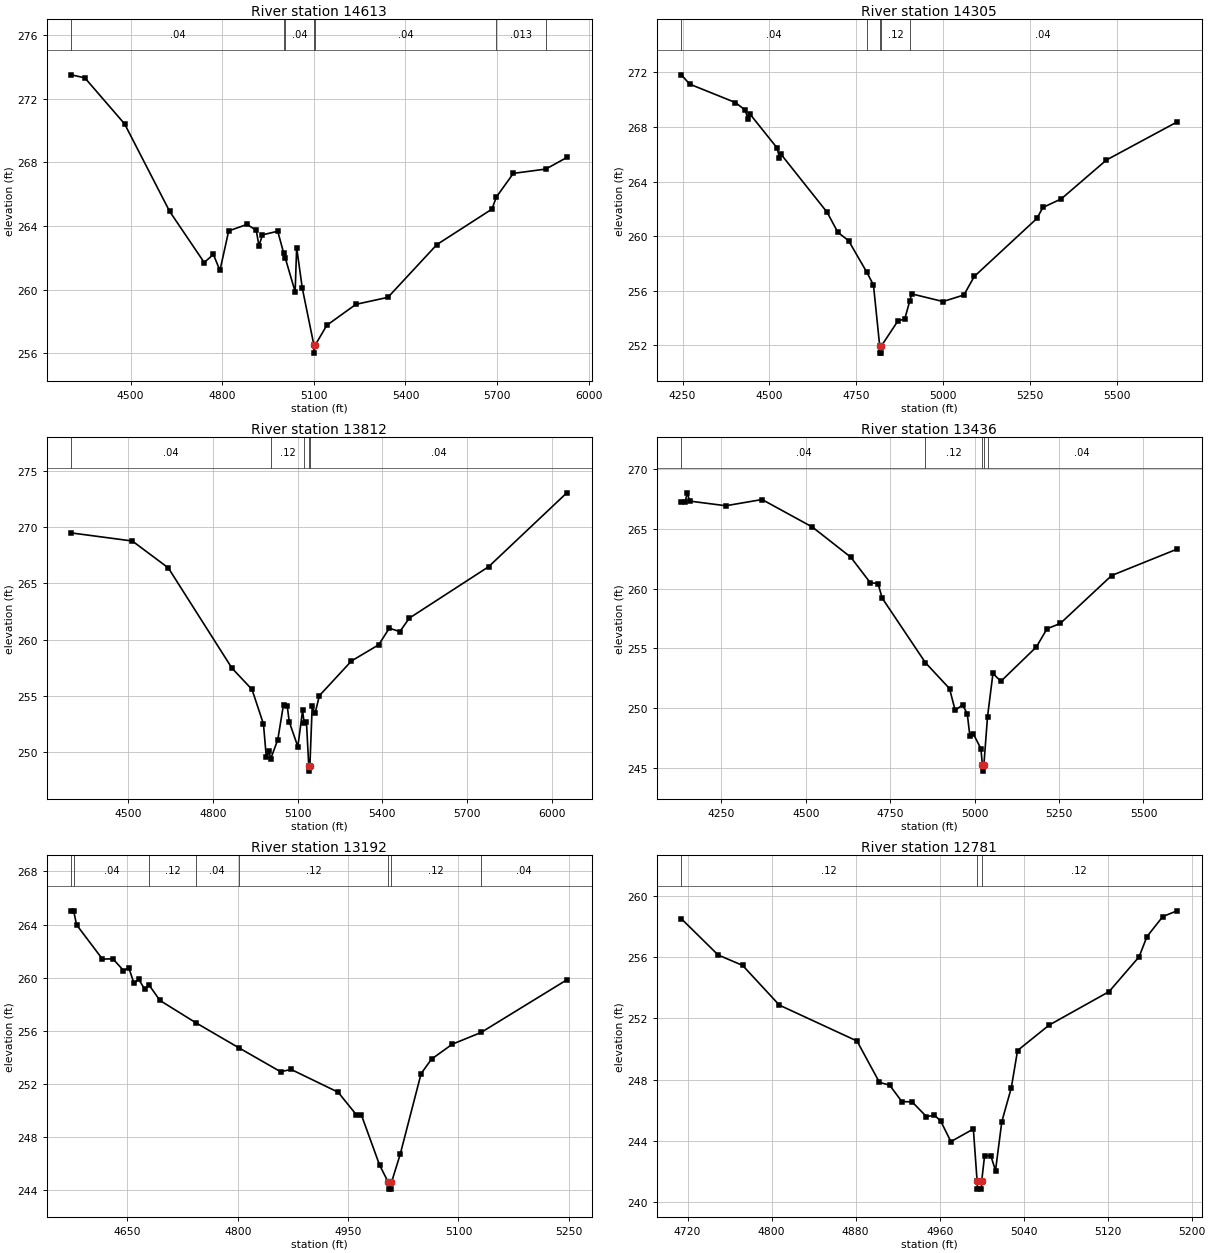
Type RM Length L Ch R = 1,14613,308,308,308
BEGIN DESCRIPTION:
Mapping XS d0526307
END DESCRIPTION:
XS GIS Cut Line= 4
      2492089.12     13542599.64      2491537.91     13542634.36
      2491286.17     13542656.06      2490470.18     13542617.00
#Sta/Elev= 30
  4306.2  273.51  4350.4  273.32  4480.7  270.42  4628.0  264.92  4741.2  261.70
  4771.2  262.21  4792.7  261.20  4821.3  263.69  4881.5  264.10  4911.6  263.72
  4920.4  262.75  4931.7  263.44  4981.9  263.67  5001.6  262.27  5006.9  261.96
  5038.8  259.86  5043.8  262.64  5062.2  260.09  5100.3  256.50  5100.6  256.00
  5104.3  256.50  5142.4  257.75  5237.8  259.07  5342.6  259.51  5502.8  262.83
  5683.0  265.06  5697.4  265.82  5753.1  267.31  5859.3  267.58  5928.1  268.31
#Mann=7,-1,0
  4306.2    0.04       0  5001.6     0.1       0  5006.9    0.04       0
  5100.3    0.04       0  5104.3    0.04       0  5697.4   0.013       0
  5859.3    0.04       0
Bank Sta=5100.3,5104.3
Exp/Cntr=0.3,0.1

Type RM Length L Ch R = 1,14305,493,493,493
BEGIN DESCRIPTION:
Mapping XS 612021b3
END DESCRIPTION:
XS GIS Cut Line= 3
      2492063.06     13542495.47      2491533.57     13542369.61
      2490652.50     13542334.88
#Sta/Elev= 30
  4246.5  271.82  4270.2  271.14  4401.9  269.79  4429.5  269.25  4438.9  268.56
  4444.0  268.94  4522.0  266.46  4528.4  265.75  4533.5  265.99  4665.9  261.75
  4696.8  260.28  4727.6  259.67  4779.6  257.38  4799.3  256.42  4817.3  251.93
  4817.6  251.43  4821.1  251.43  4821.4  251.93  4869.4  253.78  4889.4  253.94
  4903.6  255.24  4909.4  255.77  4999.5  255.21  5059.5  255.69  5089.5  257.05
  5269.7  261.30  5286.7  262.10  5339.7  262.73  5469.8  265.58  5672.5  268.36
#Mann=5,-1,0
  4246.5    0.04       0  4779.6    0.12       0  4817.3    0.04       0
  4821.4    0.12       0  4903.6    0.04       0
Bank Sta=4817.3,4821.4
Exp/Cntr=0.3,0.1

Type RM Length L Ch R = 1,13812,376,376,376
BEGIN DESCRIPTION:
Mapping XS f92648bd
END DESCRIPTION:
XS GIS Cut Line= 4
      2492054.38     13542399.97      2491668.12     13542074.47
      2491147.29     13541983.32      2490431.13     13542074.47
#Sta/Elev= 30
  4298.2  269.49  4514.3  268.77  4641.7  266.38  4867.4  257.45  4938.5  255.55
  4979.1  252.47  4989.2  249.50  4998.8  250.07  5004.5  249.36  5029.8  251.08
  5050.1  254.21  5063.3  254.08  5070.4  252.67  5100.9  250.46  5117.7  253.68
  5123.1  252.58  5131.3  252.68  5139.5  248.78  5139.7  248.28  5143.6  248.78
  5151.7  254.05  5161.8  253.42  5177.2  255.00  5291.0  258.09  5387.4  259.53
  5425.1  261.01  5462.3  260.70  5495.7  261.90  5776.9  266.48  6054.0  273.06
#Mann=5,-1,0
  4298.2    0.04       0  5004.5    0.12       0  5123.1    0.04       0
  5139.5    0.04       0  5143.6    0.04       0
Bank Sta=5139.5,5143.6
Exp/Cntr=0.3,0.1

Type RM Length L Ch R = 1,13436,244,244,244
BEGIN DESCRIPTION:
Mapping XS e6355e43
END DESCRIPTION:
XS GIS Cut Line= 3
      2492193.27     13542191.64      2491750.58     13541840.09
      2490921.55     13541484.17
#Sta/Elev= 30
  4131.5  267.25  4142.1  267.21  4149.3  268.00  4155.7  267.31  4263.1  266.92
  4370.4  267.44  4519.4  265.14  4633.2  262.62  4690.8  260.49  4713.8  260.42
  4726.2  259.20  4854.4  253.80  4925.6  251.64  4942.3  249.82  4964.1  250.27
  4978.1  249.55  4985.8  247.69  4996.2  247.85  5018.5  246.62  5023.1  245.24
  5023.4  244.74  5027.3  245.24  5038.2  249.30  5054.2  252.90  5077.8  252.25
  5182.9  255.12  5214.4  256.64  5253.6  257.08  5405.8  261.09  5599.0  263.29
#Mann=5,-1,0
  4131.5    0.04       0  4854.4    0.12       0  5023.1    0.05       0
  5027.3    0.12       0  5038.2    0.04       0
Bank Sta=5023.1,5027.3
Exp/Cntr=0.3,0.1

Type RM Length L Ch R = 1,13192,411,411,411
BEGIN DESCRIPTION:
TRIB 12 TO TWELVEMILE CREEK 18.0
END DESCRIPTION:
XS GIS Cut Line= 3
      2491874.97     13541774.97      2491575.00     13541525.00
      2491375.01     13541325.01
#Sta/Elev= 30
  4573.9  265.03  4577.1  265.03  4581.0  263.98  4616.2  261.40  4630.5  261.42
  4644.8  260.54  4652.0  260.74  4659.1  259.58  4665.6  259.87  4673.4  259.15
  4679.8  259.43  4694.3  258.29  4742.9  256.62  4801.5  254.73  4858.3  252.93
  4872.6  253.10  4936.4  251.39  4961.1  249.70  4967.9  249.70  4992.7  245.92
  5004.7  244.60  5004.9  244.10  5008.6  244.10  5008.9  244.60  5020.9  246.74
  5049.2  252.79  5063.4  253.88  5091.6  255.00  5130.6  255.88  5247.2  259.84
#Mann=8,-1,0
  4573.9    0.12       0  4577.1    0.04       0  4679.8    0.12       0
  4742.9    0.04       0  4801.5    0.12       0  5004.7    0.05       0
  5008.9    0.12       0  5130.6    0.04       0
Bank Sta=5004.7,5008.9
Exp/Cntr=0.3,0.1

Type RM Length L Ch R = 1,12781,486,486,486
BEGIN DESCRIPTION:
TRIB 12 TO TWELVEMILE CREEK 17.0
END DESCRIPTION:
XS GIS Cut Line= 3
      2492025.02     13541325.01      2491775.00     13541175.00
      2491625.04     13541075.03
#Sta/Elev= 30
  4714.1  258.50  4749.1  256.14  4772.4  255.46  4807.4  252.87  4881.3  250.53
  4902.7  247.83  4912.4  247.65  4924.0  246.58  4933.8  246.56  4947.4  245.60
  4955.1  245.69  4961.0  245.31  4970.7  243.97  4992.1  244.79  4995.7  241.37
  4996.0  240.87  4999.7  240.87  5000.0  241.37  5002.8  243.05  5008.7  243.05
  5013.2  242.08  5019.2  245.27  5028.2  247.47  5034.2  249.91  5064.3  251.57
  5121.3  253.75  5149.9  256.02  5157.4  257.34  5172.4  258.64  5185.9  259.02
#Mann=3,-1,0
  4714.1    0.12       0  4995.7    0.05       0  5000.0    0.12       0
Bank Sta=4995.7,5000
Exp/Cntr=0.3,0.1

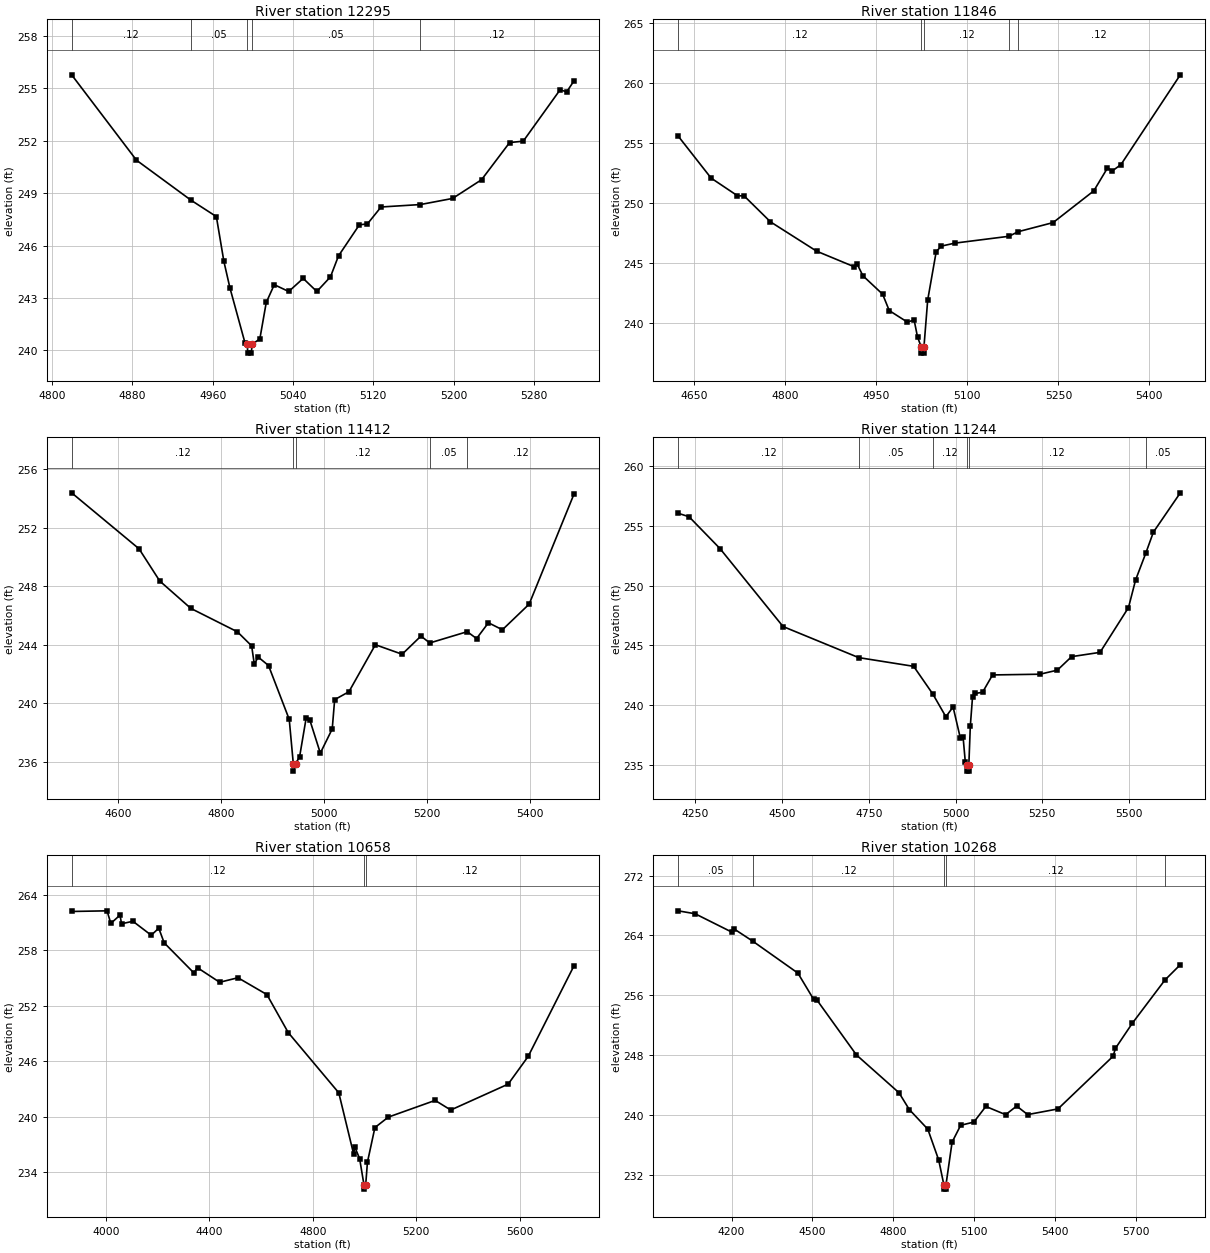
Type RM Length L Ch R = 1,12295,449,449,449
BEGIN DESCRIPTION:
TRIB 12 TO TWELVEMILE CREEK 16.0
END DESCRIPTION:
XS GIS Cut Line= 3
      2492224.99     13541024.98      2492125.00     13540875.00
      2491875.01     13540675.01
#Sta/Elev= 30
  4819.5  255.78  4884.1  250.89  4938.4  248.60  4963.7  247.66  4971.2  245.09
  4977.2  243.58  4992.2  240.43  4994.6  240.34  4994.9  239.84  4998.7  239.84
  4999.0  240.34  5007.0  240.65  5013.4  242.74  5021.4  243.76  5035.8  243.37
  5050.2  244.12  5063.8  243.37  5077.4  244.21  5085.4  245.41  5106.2  247.19
  5114.2  247.24  5127.8  248.21  5167.0  248.35  5199.1  248.70  5227.9  249.77
  5255.9  251.90  5269.5  251.98  5306.3  254.93  5312.7  254.80  5319.9  255.42
#Mann=5,-1,0
  4819.5    0.12       0  4938.4    0.05       0  4994.6    0.05       0
  4999.0    0.05       0  5167.0    0.12       0
Bank Sta=4994.6,4999
Exp/Cntr=0.3,0.1

Type RM Length L Ch R = 1,11846,434,434,434
BEGIN DESCRIPTION:
TRIB 12 TO TWELVEMILE CREEK 15.0
END DESCRIPTION:
XS GIS Cut Line= 3
      2492524.98     13540874.96      2492375.00     13540525.00
      2491974.96     13540324.98
#Sta/Elev= 30
  4623.0  255.56  4677.4  252.06  4720.9  250.59  4731.8  250.58  4775.3  248.42
  4851.4  245.98  4913.1  244.69  4918.5  244.88  4927.6  243.94  4960.2  242.40
  4971.1  241.04  5001.0  240.08  5012.1  240.26  5017.7  238.85  5023.9  238.00
  5024.2  237.50  5028.0  237.50  5028.3  238.00  5034.5  241.92  5048.5  245.93
  5056.8  246.40  5079.2  246.65  5168.5  247.22  5183.6  247.60  5241.3  248.36
  5308.4  251.00  5330.8  252.89  5339.2  252.67  5353.1  253.18  5451.0  260.65
#Mann=5,-1,0
  4623.0    0.12       0  5023.9    0.05       0  5028.3    0.12       0
  5168.5    0.05       0  5183.6    0.12       0
Bank Sta=5023.9,5028.3
Exp/Cntr=0.3,0.1

Type RM Length L Ch R = 1,11412,168,168,168
BEGIN DESCRIPTION:
TRIB 12 TO TWELVEMILE CREEK 14.0
END DESCRIPTION:
XS GIS Cut Line= 3
      2492775.00     13540825.02      2492725.00     13540325.00
      2492325.01     13540075.00
#Sta/Elev= 30
  4510.3  254.37  4641.0  250.55  4681.2  248.35  4741.5  246.48  4831.9  244.88
  4859.5  243.92  4864.6  242.67  4872.1  243.16  4892.2  242.58  4932.4  238.90
  4940.3  235.87  4940.6  235.37  4944.7  235.87  4952.5  236.35  4965.1  238.97
  4972.6  238.83  4992.7  236.60  5015.8  238.25  5020.5  240.25  5048.2  240.79
  5099.5  244.00  5151.4  243.35  5187.9  244.59  5205.0  244.12  5277.7  244.89
  5295.8  244.42  5318.8  245.50  5345.9  245.02  5397.8  246.77  5484.5  254.26
#Mann=5,-1,0
  4510.3    0.12       0  4940.3    0.05       0  4944.7    0.12       0
  5205.0    0.05       0  5277.7    0.12       0
Bank Sta=4940.3,4944.7
Exp/Cntr=0.3,0.1

Type RM Length L Ch R = 1,11244,586,586,586
BEGIN DESCRIPTION:
Mapping XS 23ad2836
END DESCRIPTION:
XS GIS Cut Line= 4
      2492879.05     13540976.41      2492935.48     13540338.36
      2492688.08     13540025.86      2492289.36     13539934.84
#Sta/Elev= 30
  4200.1  256.05  4231.6  255.76  4320.7  253.10  4502.7  246.57  4720.7  243.97
  4879.3  243.24  4934.6  240.92  4972.2  239.02  4993.0  239.84  5013.8  237.25
  5021.9  237.30  5028.3  235.21  5034.0  234.97  5034.3  234.47  5038.1  234.47
  5038.4  234.97  5042.7  238.26  5049.1  240.69  5057.1  240.97  5078.0  241.07
  5106.8  242.52  5243.4  242.58  5293.7  242.92  5334.7  244.05  5416.8  244.41
  5498.8  248.16  5519.3  250.47  5548.4  252.69  5570.6  254.47  5648.2  257.76
#Mann=6,-1,0
  4200.1    0.12       0  4720.7    0.05       0  4934.6    0.12       0
  5034.0    0.05       0  5038.4    0.12       0  5548.4    0.05       0
Bank Sta=5034,5038.4
Exp/Cntr=0.3,0.1

Type RM Length L Ch R = 1,10658,390,390,390
BEGIN DESCRIPTION:
Mapping XS f2ba7d38
END DESCRIPTION:
XS GIS Cut Line= 3
      2493972.81     13540468.57      2493534.44     13539882.63
      2492332.22     13539739.40
#Sta/Elev= 30
  3867.2  262.21  4004.1  262.28  4018.7  260.92  4054.1  261.81  4060.4  260.88
  4104.2  261.15  4175.0  259.64  4204.2  260.40  4225.0  258.82  4339.7  255.57
  4354.2  256.12  4439.7  254.55  4510.5  255.04  4622.4  253.22  4704.9  249.11
  4900.5  242.59  4957.6  236.00  4962.7  236.71  4981.1  235.47  4997.7  232.67
  4998.2  232.17  5004.7  232.67  5011.3  235.08  5040.2  238.83  5091.9  239.96
  5273.2  241.77  5333.6  240.73  5555.6  243.53  5633.1  246.53  5809.7  256.30
#Mann=3,-1,0
  3867.2    0.12       0  4997.7    0.05       0  5004.7    0.12       0
Bank Sta=4997.7,5004.7
Exp/Cntr=0.3,0.1

Type RM Length L Ch R = 1,10268,363,363,363
BEGIN DESCRIPTION:
Mapping XS 6c8d0db1
END DESCRIPTION:
XS GIS Cut Line= 3
      2494033.54     13539778.45      2493017.94     13539444.26
      2492241.03     13539609.19
#Sta/Elev= 30
  4001.5  267.29  4064.5  266.90  4200.0  264.46  4210.5  264.84  4279.0  263.22
  4445.9  258.97  4504.2  255.47  4515.8  255.41  4663.2  248.03  4821.1  242.98
  4859.2  240.74  4928.0  238.11  4968.5  233.98  4988.0  230.60  4988.5  230.10
  4994.6  230.10  4995.1  230.60  5018.1  236.38  5049.9  238.63  5098.8  239.06
  5143.3  241.15  5216.8  240.05  5257.7  241.20  5298.6  240.06  5411.0  240.82
  5615.5  247.86  5624.3  248.92  5687.1  252.28  5808.0  258.05  5864.9  260.09
#Mann=5,-1,0
  4001.5    0.05       0  4279.0    0.12       0  4988.0    0.05       0
  4995.1    0.12       0  5808.0    0.05       0
Bank Sta=4988,4995.1
Exp/Cntr=0.3,0.1

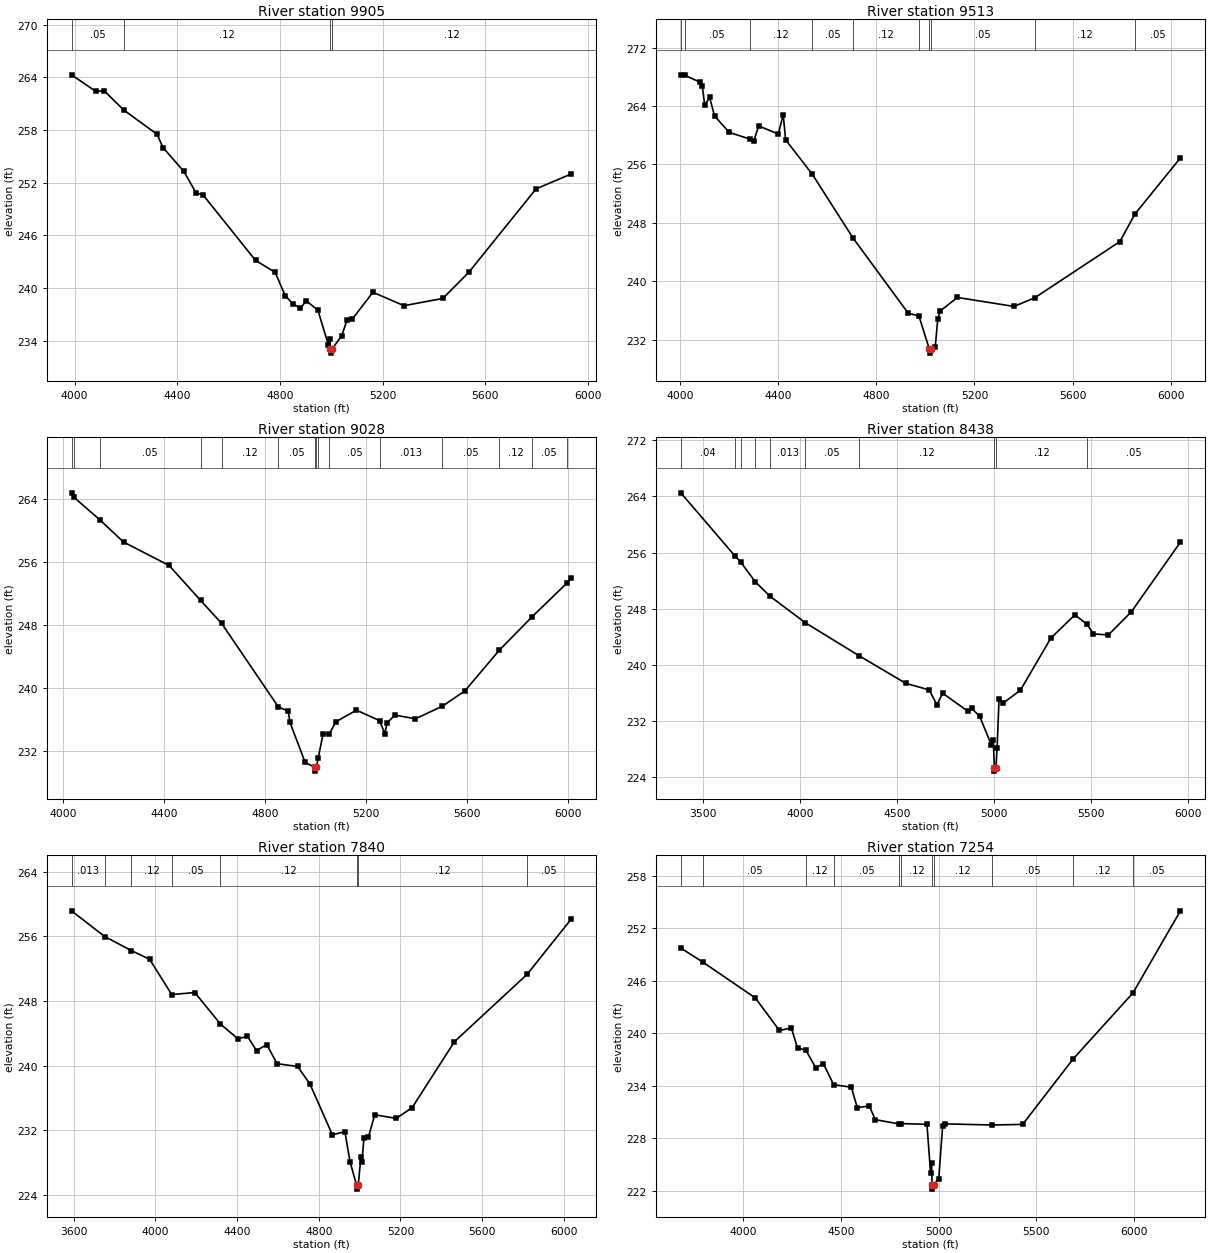
Type RM Length L Ch R = 1,9905,392,392,392
BEGIN DESCRIPTION:
Mapping XS 9bea4c5e
END DESCRIPTION:
XS GIS Cut Line= 3
      2494050.89     13539526.71      2493117.77     13539114.40
      2492199.77     13539239.97
#Sta/Elev= 30
  3987.8  264.30  4082.9  262.40  4114.5  262.49  4191.2  260.29  4321.4  257.51
  4344.1  256.01  4425.5  253.28  4472.2  250.87  4500.9  250.58  4704.9  243.13
  4781.4  241.77  4820.3  239.11  4849.0  238.22  4879.8  237.65  4901.7  238.54
  4947.7  237.46  4988.9  233.48  4994.3  234.18  4996.5  233.06  4997.0  232.56
  5003.6  233.06  5041.0  234.56  5061.2  236.35  5081.4  236.43  5162.1  239.50
  5283.3  237.97  5434.7  238.80  5535.6  241.78  5798.0  251.30  5934.5  252.99
#Mann=4,-1,0
  3987.8    0.05       0  4191.2    0.12       0  4996.5    0.05       0
  5003.6    0.12       0
Bank Sta=4996.5,5003.6
Exp/Cntr=0.3,0.1

Type RM Length L Ch R = 1,9513,485,485,485
BEGIN DESCRIPTION:
Mapping XS 13e3941f
END DESCRIPTION:
XS GIS Cut Line= 3
      2494072.63     13538749.81      2493048.33     13538741.13
      2492038.52     13538823.48
#Sta/Elev= 30
  4002.6  268.26  4017.9  268.21  4080.2  267.27  4090.2  266.78  4100.2  264.11
  4120.2  265.16  4140.2  262.63  4200.2  260.38  4284.2  259.47  4300.2  259.19
  4320.2  261.26  4400.2  260.16  4420.2  262.81  4430.2  259.36  4538.3  254.68
  4705.3  245.91  4930.3  235.62  4973.6  235.27  5016.6  230.67  5017.1  230.17
  5024.0  230.67  5040.3  231.06  5050.3  234.81  5060.4  235.94  5130.6  237.79
  5361.4  236.56  5445.8  237.74  5792.8  245.43  5854.7  249.21  6040.1  256.89
#Mann=10,-1,0
  4002.6    0.04       0  4017.9    0.05       0  4284.2    0.12       0
  4538.3    0.05       0  4705.3    0.12       0  4973.6    0.05       0
  5016.6    0.05       0  5024.0    0.05       0  5445.8    0.12       0
  5854.7    0.05       0
Bank Sta=5016.6,5024
Exp/Cntr=0.3,0.1

Type RM Length L Ch R = 1,9028,590,590,590
BEGIN DESCRIPTION:
Mapping XS 295594e6
END DESCRIPTION:
XS GIS Cut Line= 3
      2493894.72     13538498.09      2493191.56     13538250.68
      2491978.12     13538463.03
#Sta/Elev= 30
  4034.3  264.72  4043.7  264.16  4147.1  261.28  4240.1  258.49  4420.6  255.52
  4545.0  251.10  4628.5  248.18  4852.6  237.62  4892.4  237.06  4898.1  235.70
  4959.0  230.58  4995.9  229.98  4996.4  229.48  5003.3  229.98  5010.1  231.09
  5030.0  234.22  5053.2  234.12  5080.8  235.74  5162.0  237.20  5253.9  235.87
  5273.7  234.23  5283.8  235.62  5314.3  236.57  5395.5  236.11  5502.2  237.71
  5590.7  239.63  5727.2  244.79  5855.8  248.99  5994.2  253.27  6011.6  253.93
#Mann=15,-1,0
  4034.3    0.05       0  4043.7    0.12       0  4147.1    0.05       0
  4545.0   0.013       0  4628.5    0.12       0  4852.6    0.05       0
  4995.9    0.05       0  5003.3    0.05       0  5010.1   0.013       0
  5053.2    0.05       0  5253.9   0.013       0  5502.2    0.05       0
  5727.2    0.12       0  5855.8    0.05       0  5994.2    0.04       0
Bank Sta=4995.9,5003.3
Exp/Cntr=0.3,0.1

Type RM Length L Ch R = 1,8438,598,598,598
BEGIN DESCRIPTION:
Mapping XS 32b5ec88
END DESCRIPTION:
XS GIS Cut Line= 4
      2494267.91     13538233.31      2493226.28     13537829.68
      2492436.35     13537821.00      2491789.83     13537977.20
#Sta/Elev= 30
  3386.5  264.52  3664.7  255.54  3694.3  254.68  3769.0  251.87  3845.7  249.78
  4028.4  245.99  4304.7  241.29  4544.9  237.36  4664.9  236.43  4704.9  234.32
  4734.9  235.95  4864.9  233.38  4884.9  233.78  4924.9  232.68  4984.9  228.63
  4994.9  229.32  5001.0  225.35  5001.5  224.85  5008.9  225.35  5014.9  228.17
  5024.9  235.12  5044.9  234.52  5134.9  236.38  5291.8  243.82  5415.2  247.12
  5477.4  245.80  5511.0  244.41  5587.8  244.26  5706.5  247.58  5958.7  257.49
#Mann=10,-1,0
  3386.5    0.04       0  3664.7    0.12       0  3694.3    0.04       0
  3769.0    0.05       0  3845.7   0.013       0  4028.4    0.05       0
  4304.7    0.12       0  5001.0    0.05       0  5008.9    0.12       0
  5477.4    0.05       0
Bank Sta=5001,5008.9
Exp/Cntr=0.3,0.1

Type RM Length L Ch R = 1,7840,586,586,586
BEGIN DESCRIPTION:
Mapping XS 49fb33fa
END DESCRIPTION:
XS GIS Cut Line= 3
      2494124.70     13537413.01      2492753.19     13537248.08
      2491743.35     13537590.47
#Sta/Elev= 30
  3588.8  259.17  3751.0  255.99  3882.4  254.24  3971.2  253.17  4079.8  248.80
  4192.8  249.05  4318.2  245.15  4404.3  243.31  4450.6  243.62  4495.0  241.87
  4545.3  242.60  4595.7  240.24  4696.4  239.89  4756.9  237.72  4866.5  231.44
  4928.1  231.80  4953.7  228.02  4985.4  225.20  4985.9  224.70  4993.4  225.20
  5006.3  228.62  5011.6  228.10  5021.1  230.98  5043.0  231.12  5074.4  233.91
  5179.5  233.46  5257.6  234.80  5464.6  242.96  5820.9  251.31  6036.5  258.14
#Mann=8,-1,0
  3588.8   0.013       0  3751.0    0.04       0  3882.4    0.12       0
  4079.8    0.05       0  4318.2    0.12       0  4985.4    0.05       0
  4993.4    0.12       0  5820.9    0.05       0
Bank Sta=4985.4,4993.4
Exp/Cntr=0.3,0.1

Type RM Length L Ch R = 1,7254,370,370,370
BEGIN DESCRIPTION:
Mapping XS 49d52450
END DESCRIPTION:
XS GIS Cut Line= 4
      2494068.27     13536944.25      2492913.78     13536696.86
      2492531.83     13536670.82      2491738.78     13537268.86
#Sta/Elev= 30
  3680.5  249.74  3793.7  248.13  4062.2  244.04  4185.0  240.34  4246.3  240.61
  4277.8  238.35  4320.7  238.07  4371.6  236.05  4410.0  236.56  4462.3  234.15
  4553.1  233.85  4583.8  231.53  4645.2  231.71  4675.9  230.15  4799.2  229.66
  4806.6  229.70  4940.2  229.62  4958.7  224.08  4963.7  225.15  4966.2  222.72
  4966.7  222.22  4974.2  222.72  5000.3  223.37  5020.3  229.39  5030.4  229.67
  5274.8  229.54  5429.8  229.61  5687.5  237.06  5994.4  244.62  6237.3  253.99
#Mann=11,-1,0
  3680.5    0.04       0  3793.7    0.05       0  4320.7    0.12       0
  4462.3    0.05       0  4799.2    0.04       0  4806.6    0.12       0
  4966.2    0.05       0  4974.2    0.12       0  5274.8    0.05       0
  5687.5    0.12       0  5994.4    0.05       0
Bank Sta=4966.2,4974.2
Exp/Cntr=0.3,0.1