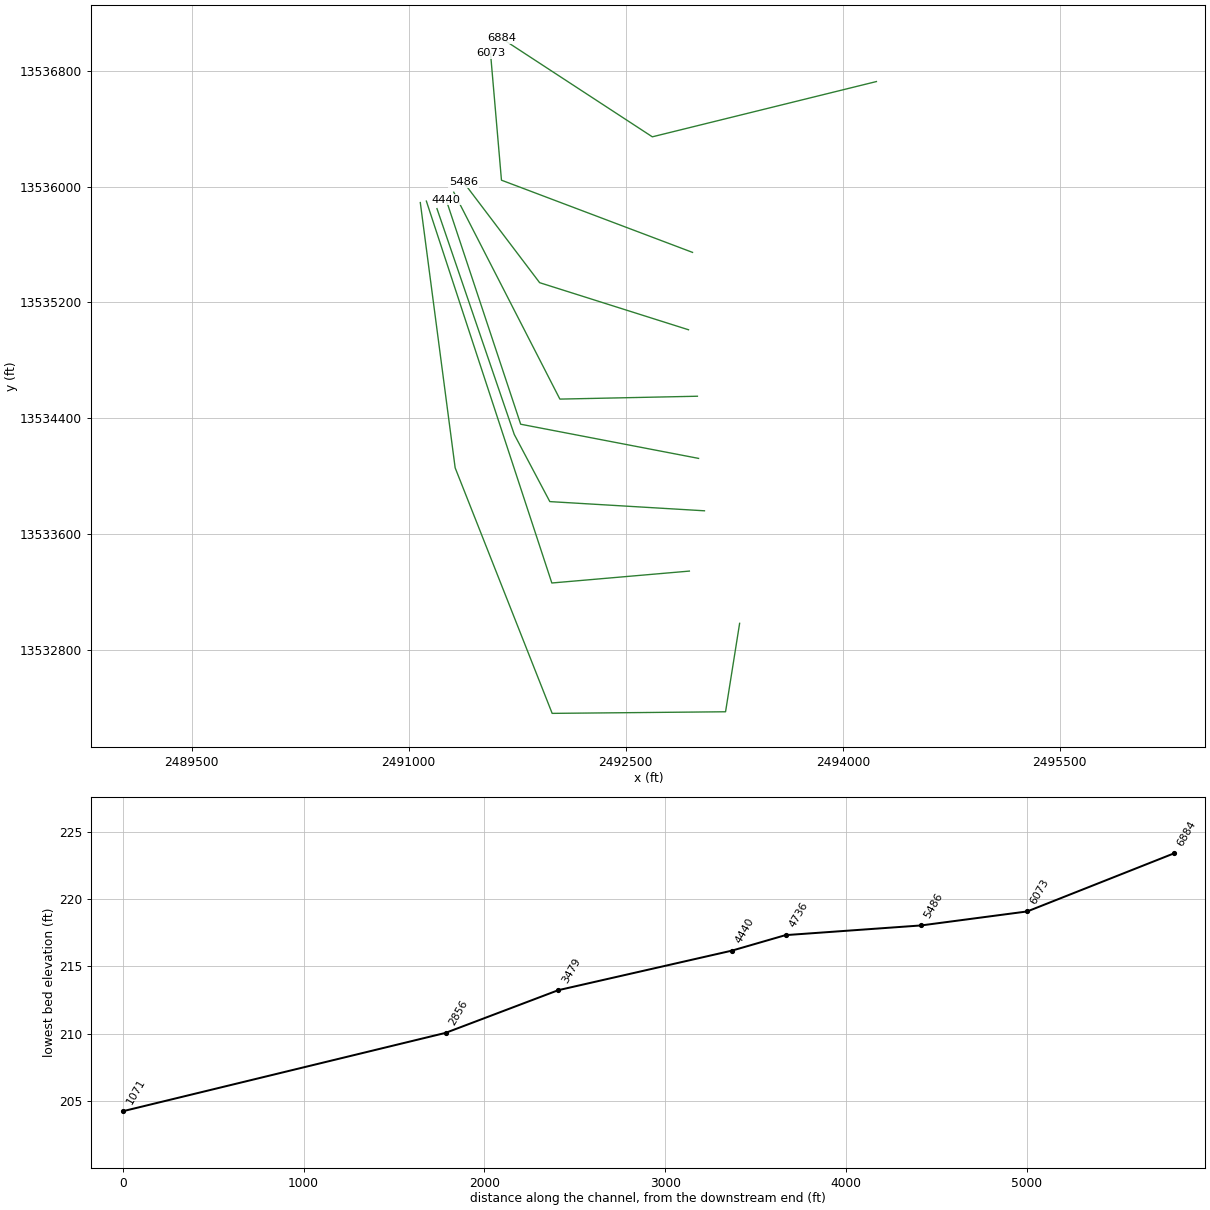
HEC-RAS study TRIB 12 TO TWELVEMILE CREEK.prj: TRIB 12 TO TWELVEMILE CREEK Base Level Engineering

--- TRIB 12 TO TWELVEMILE CREEK.g01 (geometry) --- (continued)

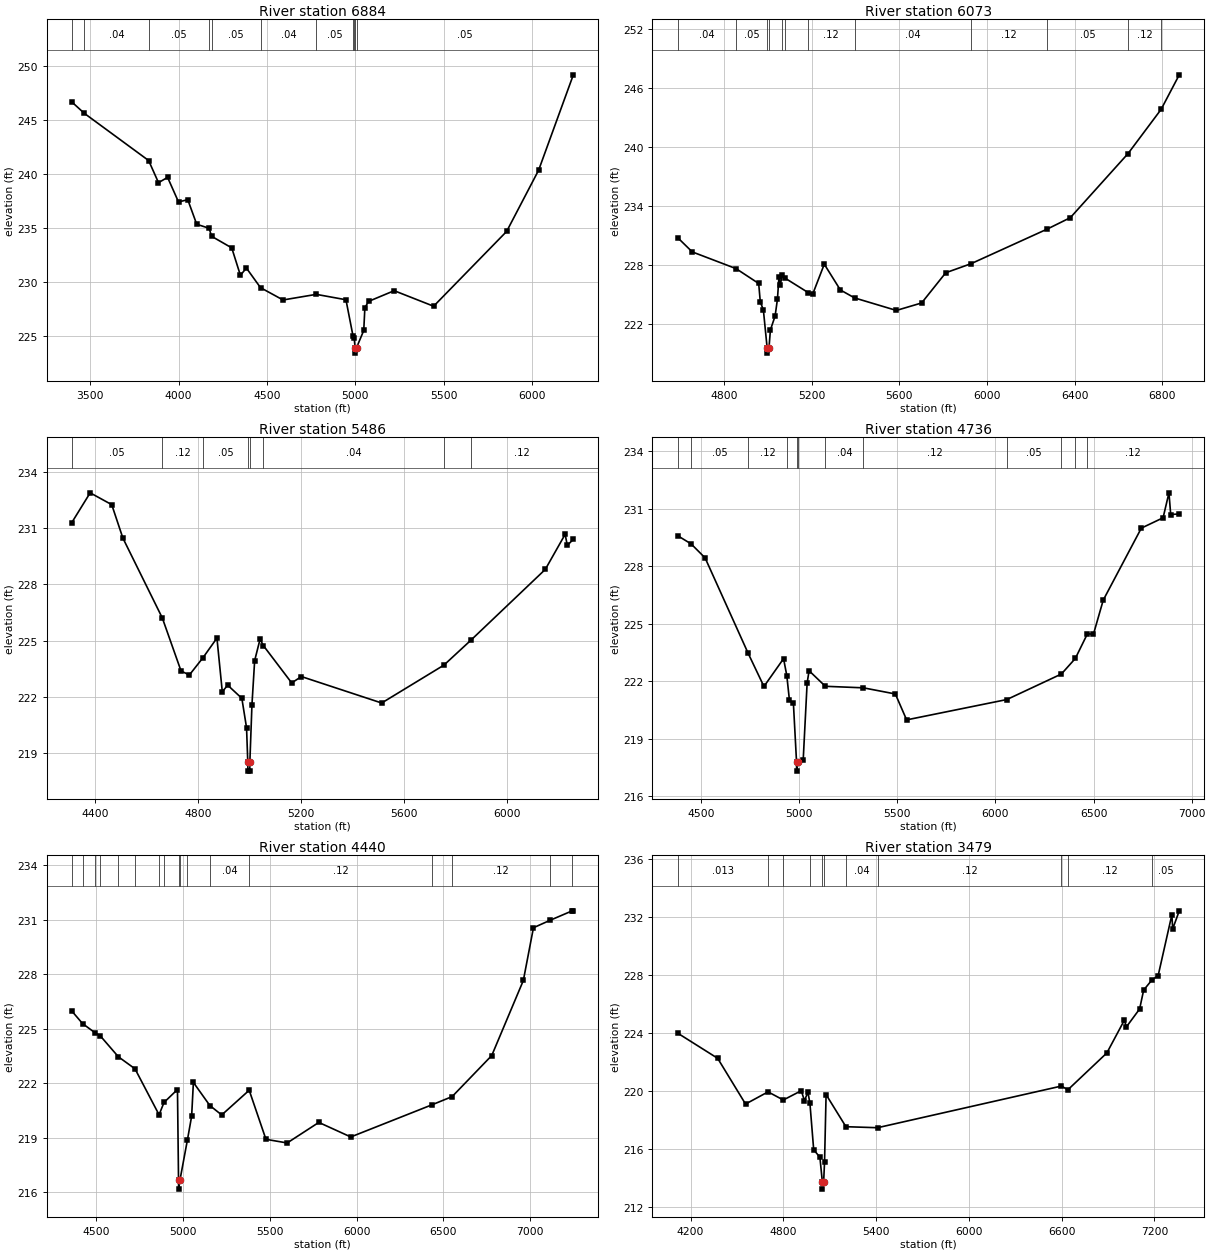
Type RM Length L Ch R = 1,6884,811,811,811
BEGIN DESCRIPTION:
Mapping XS ff48e9e9
END DESCRIPTION:
XS GIS Cut Line= 3
      2494232.32     13536726.37      2492683.74     13536344.43
      2491642.04     13537025.01
#Sta/Elev= 30
  3394.9  246.70  3466.7  245.63  3830.8  241.25  3886.5  239.20  3938.0  239.69
  3999.8  237.41  4052.2  237.62  4102.8  235.34  4173.2  234.97  4186.6  234.23
  4301.1  233.15  4350.0  230.61  4384.0  231.28  4464.0  229.46  4591.4  228.32
  4779.6  228.84  4947.4  228.34  4987.5  224.97  4994.1  224.78  4999.2  223.89
  4999.7  223.39  5007.2  223.89  5048.1  225.49  5054.5  227.60  5075.6  228.19
  5220.4  229.18  5443.6  227.74  5856.9  234.68  6037.9  240.36  6234.2  249.20
#Mann=11,-1,0
  3394.9    0.05       0  3466.7    0.04       0  3830.8    0.05       0
  4173.2    0.12       0  4186.6    0.05       0  4464.0    0.04       0
  4779.6    0.05       0  4987.5    0.12       0  4994.1    0.05       0
  4999.2    0.05       0  5007.2    0.05       0
Bank Sta=4999.2,5007.2
Exp/Cntr=0.3,0.1

Type RM Length L Ch R = 1,6073,587,587,587
BEGIN DESCRIPTION:
Mapping XS 2b43ac39
END DESCRIPTION:
XS GIS Cut Line= 3
      2492961.52     13535545.82      2491641.19     13536044.78
      2491565.73     13536920.37
#Sta/Elev= 30
  4587.6  230.83  4654.7  229.37  4854.7  227.67  4958.0  226.16  4965.3  224.29
  4979.4  223.47  4996.7  219.58  4997.2  219.08  5004.9  219.58  5011.5  221.44
  5032.9  222.85  5043.6  224.57  5050.5  226.81  5055.8  225.96  5065.4  226.98
  5077.2  226.72  5183.5  225.24  5203.9  225.04  5257.4  228.12  5330.9  225.50
  5396.0  224.69  5586.5  223.42  5701.8  224.18  5811.9  227.25  5927.3  228.17
  6275.1  231.69  6380.7  232.85  6644.3  239.37  6795.1  243.86  6877.9  247.37
#Mann=12,-1,0
  4587.6    0.04       0  4854.7    0.05       0  4996.7    0.05       0
  5004.9    0.05       0  5065.4    0.12       0  5077.2    0.05       0
  5183.5    0.12       0  5396.0    0.04       0  5927.3    0.12       0
  6275.1    0.05       0  6644.3    0.12       0  6795.1    0.05       0
Bank Sta=4996.7,5004.9
Exp/Cntr=0.3,0.1

Type RM Length L Ch R = 1,5486,750,750,750
BEGIN DESCRIPTION:
Mapping XS 715b0e84
END DESCRIPTION:
XS GIS Cut Line= 3
      2492933.74     13535011.10      2491905.08     13535336.44
      2491378.20     13536031.91
#Sta/Elev= 30
  4308.2  231.27  4380.3  232.87  4464.2  232.24  4507.5  230.46  4661.0  226.20
  4733.7  223.38  4766.0  223.16  4818.9  224.08  4873.4  225.13  4894.2  222.27
  4915.2  222.62  4970.3  221.92  4988.6  220.35  4993.3  218.54  4993.8  218.04
  5001.0  218.04  5001.5  218.54  5009.6  221.58  5020.1  223.93  5041.1  225.07
  5054.5  224.72  5164.2  222.74  5201.8  223.08  5514.2  221.67  5756.4  223.69
  5861.4  225.02  6150.6  228.79  6227.8  230.66  6236.1  230.07  6259.6  230.39
#Mann=8,-1,0
  4308.2    0.05       0  4661.0    0.12       0  4818.9    0.05       0
  4993.3    0.05       0  5001.5    0.05       0  5054.5    0.04       0
  5756.4    0.05       0  5861.4    0.12       0
Bank Sta=4993.3,5001.5
Exp/Cntr=0.3,0.1

Type RM Length L Ch R = 1,4736,296,296,296
BEGIN DESCRIPTION:
Mapping XS 25d5a26e
END DESCRIPTION:
XS GIS Cut Line= 3
      2492995.33     13534551.72      2492044.85     13534531.93
      2491311.57     13535961.67
#Sta/Elev= 30
  4379.4  229.59  4448.4  229.16  4519.8  228.43  4739.7  223.45  4819.8  221.73
  4919.8  223.18  4936.3  222.30  4949.9  221.00  4969.9  220.87  4985.8  217.82
  4986.3  217.32  4994.0  217.82  5019.9  217.90  5039.9  221.91  5049.9  222.55
  5132.9  221.74  5326.8  221.66  5489.7  221.34  5547.1  219.99  6058.1  221.05
  6336.1  222.38  6407.1  223.19  6469.0  224.48  6499.4  224.45  6549.4  226.23
  6743.5  229.98  6854.5  230.52  6884.4  231.82  6893.3  230.69  6936.9  230.72
#Mann=12,-1,0
  4379.4    0.04       0  4448.4    0.05       0  4739.7    0.12       0
  4936.3    0.05       0  4985.8    0.05       0  4994.0    0.05       0
  5132.9    0.04       0  5326.8    0.12       0  6058.1    0.05       0
  6336.1    0.12       0  6407.1    0.05       0  6469.0    0.12       0
Bank Sta=4985.8,4994
Exp/Cntr=0.3,0.1

Type RM Length L Ch R = 1,4440,961,961,961
BEGIN DESCRIPTION:
Mapping XS 53451959
END DESCRIPTION:
XS GIS Cut Line= 3
      2493003.16     13534122.22      2491774.02     13534358.32
      2491258.53     13535910.45
#Sta/Elev= 30
  4360.6  225.98  4423.2  225.28  4495.3  224.77  4525.7  224.60  4629.7  223.45
  4725.2  222.79  4863.8  220.26  4892.3  220.94  4969.7  221.65  4975.8  216.67
  4976.3  216.17  4984.0  216.67  5027.2  218.89  5051.2  220.18  5061.3  222.04
  5155.9  220.77  5224.3  220.25  5382.5  221.61  5478.8  218.91  5601.0  218.71
  5783.1  219.84  5967.0  219.04  6437.1  220.82  6550.3  221.26  6778.3  223.52
  6960.1  227.65  7018.2  230.55  7111.7  230.95  7241.3  231.48  7247.7  231.47
#Mann=17,-1,0
  4360.6    0.04       0  4423.2    0.05       0  4495.3    0.04       0
  4525.7    0.05       0  4629.7    0.04       0  4725.2    0.12       0
  4863.8    0.05       0  4892.3    0.12       0  4975.8    0.05       0
  4984.0    0.12       0  5027.2    0.05       0  5155.9    0.04       0
  5382.5    0.12       0  6437.1    0.05       0  6550.3    0.12       0
  7111.7    0.05       0  7241.3    0.12       0
Bank Sta=4975.8,4984
Exp/Cntr=0.3,0.1

Type RM Length L Ch R = 1,3479,623,623,623
BEGIN DESCRIPTION:
Mapping XS 343154b8
END DESCRIPTION:
XS GIS Cut Line= 4
      2493043.98     13533760.06      2491975.41     13533823.60
      2491729.72     13534287.38      2491195.52     13535848.09
#Sta/Elev= 30
  4116.2  223.98  4375.6  222.24  4556.0  219.09  4701.6  219.93  4800.2  219.37
  4916.6  220.01  4936.6  219.33  4959.6  219.90  4972.4  219.14  4996.7  215.94
  5036.8  215.43  5052.7  213.73  5053.2  213.23  5061.0  213.73  5066.9  215.08
  5076.9  219.74  5205.2  217.53  5409.7  217.46  6599.2  220.33  6640.5  220.07
  6892.8  222.61  7005.7  224.86  7019.6  224.41  7104.8  225.64  7130.8  226.94
  7182.3  227.61  7224.7  227.94  7313.3  232.13  7318.6  231.15  7361.1  232.40
#Mann=11,-1,0
  4116.2   0.013       0  4701.6    0.05       0  4800.2    0.12       0
  4972.4   0.013       0  5052.7    0.03       0  5061.0   0.013       0
  5205.2    0.04       0  5409.7    0.12       0  6599.2    0.05       0
  6640.5    0.12       0  7182.3    0.05       0
Bank Sta=5052.7,5061
Exp/Cntr=0.3,0.1

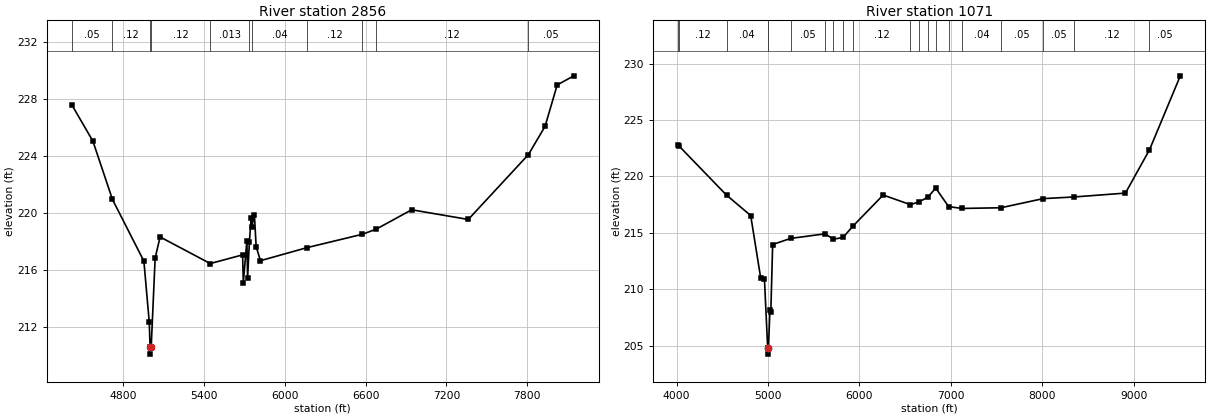
Type RM Length L Ch R = 1,2856,1785,1785,1785
BEGIN DESCRIPTION:
Mapping XS 57eca0f1
END DESCRIPTION:
XS GIS Cut Line= 3
      2492939.78     13533343.39      2491989.30     13533261.10
      2491122.29     13535900.19
#Sta/Elev= 30
  4415.2  227.61  4573.0  225.04  4718.3  220.94  4952.0  216.60  4992.1  212.29
  4998.0  210.56  4998.5  210.06  5006.3  210.56  5035.7  216.81  5072.4  218.30
  5445.3  216.43  5685.6  217.04  5690.9  215.09  5717.4  218.05  5722.7  215.40
  5735.7  217.91  5749.2  219.65  5752.8  218.97  5773.3  219.87  5786.3  217.62
  5818.1  216.63  6164.9  217.55  6576.1  218.49  6678.9  218.85  6941.9  220.21
  7362.7  219.53  7809.4  224.09  7933.3  226.08  8023.4  228.99  8147.1  229.63
#Mann=11,-1,0
  4415.2    0.05       0  4718.3    0.12       0  4998.0    0.05       0
  5006.3    0.12       0  5445.3   0.013       0  5735.7    0.05       0
  5752.8    0.04       0  6164.9    0.12       0  6576.1    0.05       0
  6678.9    0.12       0  7809.4    0.05       0
Bank Sta=4998,5006.3
Exp/Cntr=0.3,0.1

Type RM Length L Ch R = 1,1071,0,0,0
BEGIN DESCRIPTION:
Mapping XS 57eca0f1aa
END DESCRIPTION:
XS GIS Cut Line= 5
      2493287.03     13532982.31      2493189.80     13532371.17
      2491991.58     13532360.09      2491321.22     13534056.94
      2491080.30     13535890.00
#Sta/Elev= 30
  4017.6  222.78  4023.5  222.73  4546.7  218.34  4811.2  216.53  4921.2  210.95
  4961.2  210.92  4997.0  204.74  4997.5  204.24  5005.4  204.74  5021.2  208.19
  5031.2  207.99  5051.2  213.96  5246.5  214.50  5624.1  214.91  5715.7  214.43
  5820.9  214.59  5932.2  215.62  6259.3  218.35  6555.9  217.50  6649.6  217.73
  6750.0  218.17  6833.7  218.97  6975.1  217.32  7122.1  217.16  7546.4  217.22
  8009.0  218.03  8350.0  218.18  8907.9  218.52  9171.1  222.36  9508.0  228.92
#Mann=20,-1,0
  4017.6    0.04       0  4023.5    0.12       0  4546.7    0.04       0
  4997.0    0.05       0  5005.4    0.12       0  5246.5    0.05       0
  5624.1    0.05       0  5715.7    0.12       0  5820.9    0.05       0
  5932.2    0.12       0  6555.9   0.013       0  6649.6    0.12       0
  6750.0    0.05       0  6833.7    0.12       0  6975.1    0.05       0
  7122.1    0.04       0  7546.4    0.05       0  8009.0    0.05       0
  8350.0    0.12       0  9171.1    0.05       0
Bank Sta=4997,5005.4
Exp/Cntr=0.3,0.1

Chan Stop Cuts=-1