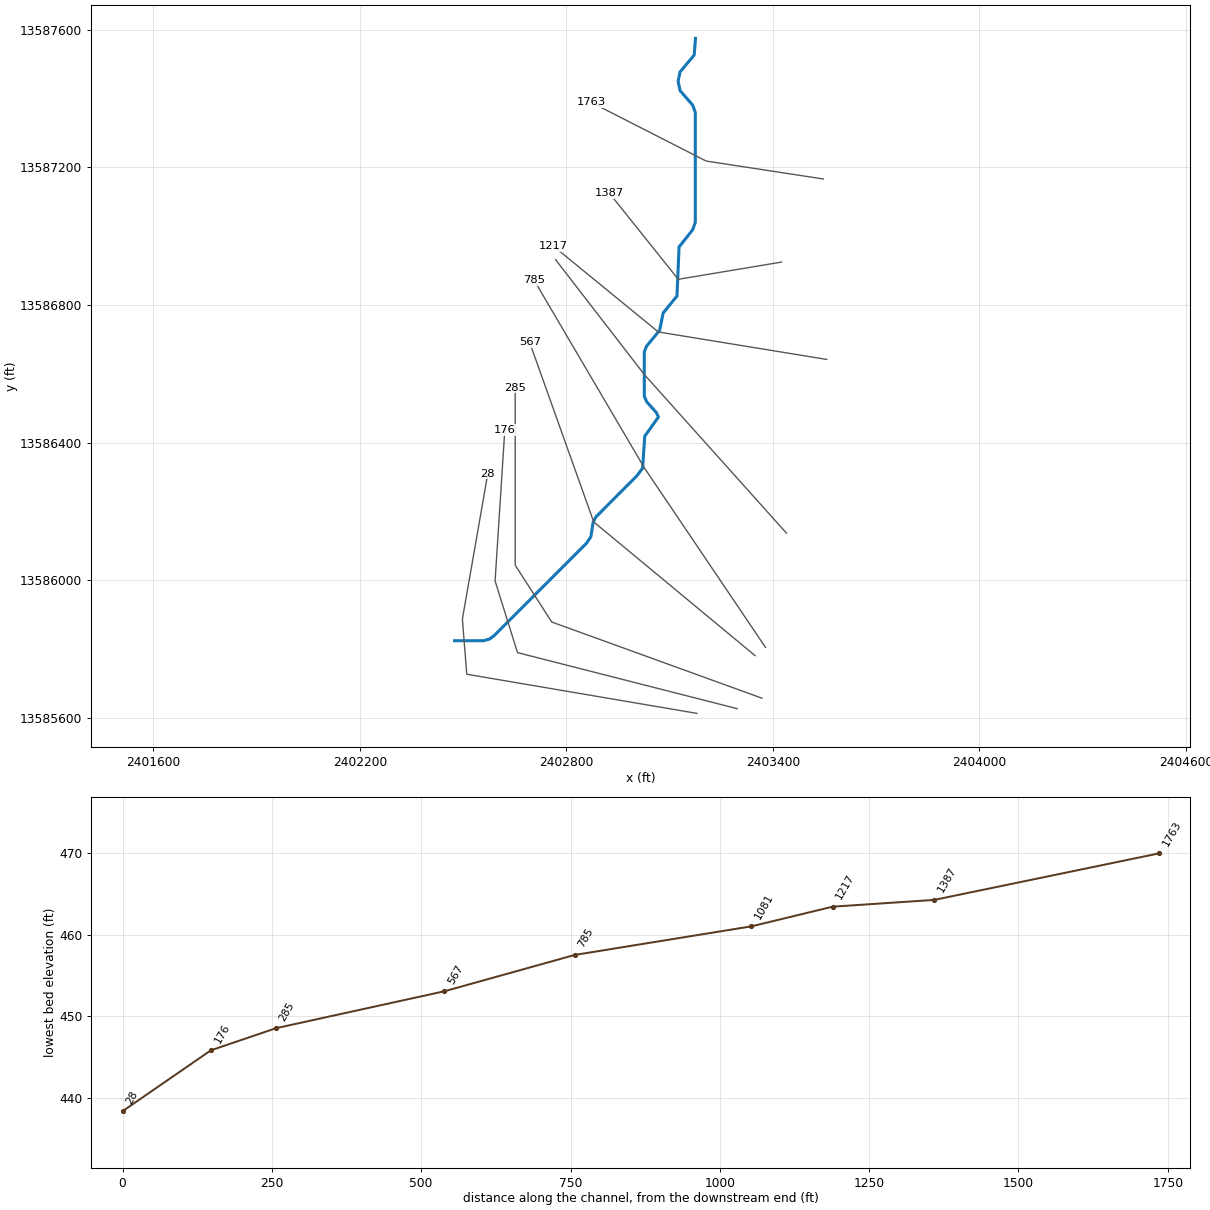
--- TRIB 12_1 TO SALT CREEK.prj (project) ---

Proj Title=TRIB 12_1 TO SALT CREEK Base Level Engineering
Current Plan=p01
Default Exp/Contr=0.3,0.1
English Units
Geom File=g01
Flow File=f01
Plan File=p01
Y Axis Title=Elevation
X Axis Title(PF)=Main Channel Distance
X Axis Title(XS)=Station
BEGIN DESCRIPTION:
TRIB 12_1 TO SALT CREEK
END DESCRIPTION:
DSS Export Rating Curves= 0
DSS Export Rating Curve Sorted= 0
DSS Export Volume Flow Curves= 0
DXF OffsetX= 0
DXF OffsetY= 0
DXF ScaleX= 1
DXF ScaleY= 10

--- TRIB 12_1 TO SALT CREEK.p01 (plan) ---

Plan Title=Multiple Run
Short Identifier=Multiple
Geom File=g01
Flow File=f01
Subcritical Flow
K Sum by GR= 0
Std Step Tol= 0.01
Critical Tol= 0.01
Num of Std Step Trials= 20
Max Error Tol= 0.3
Flow Tol Ratio= 0.001
Split Flow NTrial= 30
Split Flow Tol= 0.02
Split Flow Ratio= 0.02
Log Output Level= 0
Friction Slope Method= 1
Unsteady Friction Slope Method= 2
Unsteady Bridges Friction Slope Method= 1
Parabolic Critical Depth
Global Vel Dist=  1 , 1 , 1
Global Log Level= 0
CheckData=True
Encroach Param= -1, 0, 0, 0
BEGIN DESCRIPTION:
Multiple Run
END DESCRIPTION:

--- TRIB 12_1 TO SALT CREEK.f01 (steady flow) ---

Flow Title=Multiple
Number of Profiles=7
Profile Names=10-year,25-year,50-year,1pct_min,100-year,1pct_plu,500-year
River Rch & RM= TRIB 12_1 TO SAL,Reach-1,1763
     194     294     379     239     476     950     740
Boundary for River Rch & Prof#=TRIB 12_1 TO SAL,Reach-1,1
Up Type=0
Dn Type=3
Dn Slope=0.005
Boundary for River Rch & Prof#=TRIB 12_1 TO SAL,Reach-1,2
Up Type=0
Dn Type=3
Dn Slope=0.005
Boundary for River Rch & Prof#=TRIB 12_1 TO SAL,Reach-1,3
Up Type=0
Dn Type=3
Dn Slope=0.005
Boundary for River Rch & Prof#=TRIB 12_1 TO SAL,Reach-1,4
Up Type=0
Dn Type=3
Dn Slope=0.005
Boundary for River Rch & Prof#=TRIB 12_1 TO SAL,Reach-1,5
Up Type=0
Dn Type=3
Dn Slope=0.005
Boundary for River Rch & Prof#=TRIB 12_1 TO SAL,Reach-1,6
Up Type=0
Dn Type=3
Dn Slope=0.005
Boundary for River Rch & Prof#=TRIB 12_1 TO SAL,Reach-1,7
Up Type=0
Dn Type=3
Dn Slope=0.005

--- TRIB 12_1 TO SALT CREEK.g01 (geometry) ---

Geom Title=Existing Conditions

River Reach=TRIB 12_1 TO SAL,Reach-1
Reach XY= 30
      2403175.00     13587575.00      2403171.31     13587526.49
      2403130.12     13587477.25      2403124.53     13587450.00
      2403130.37     13587422.82      2403166.81     13587381.08
      2403174.46     13587359.79      2403174.48     13587040.22
      2403166.86     13587018.94      2403127.27     13586969.06
      2403121.24     13586826.56      2403081.12     13586777.18
      2403070.81     13586726.74      2403033.09     13586681.07
      2403026.19     13586664.50      2403026.37     13586535.44
      2403033.45     13586518.82      2403061.05     13586488.21
      2403067.44     13586475.00      2403027.56     13586419.10
      2403021.39     13586326.50      2403005.37     13586304.85
      2402885.78     13586184.68      2402877.54     13586168.95
      2402871.02     13586126.65      2402858.35     13586108.33
      2402591.76     13585841.43      2402577.50     13585830.35
      2402559.95     13585825.12      2402475.00     13585825.00

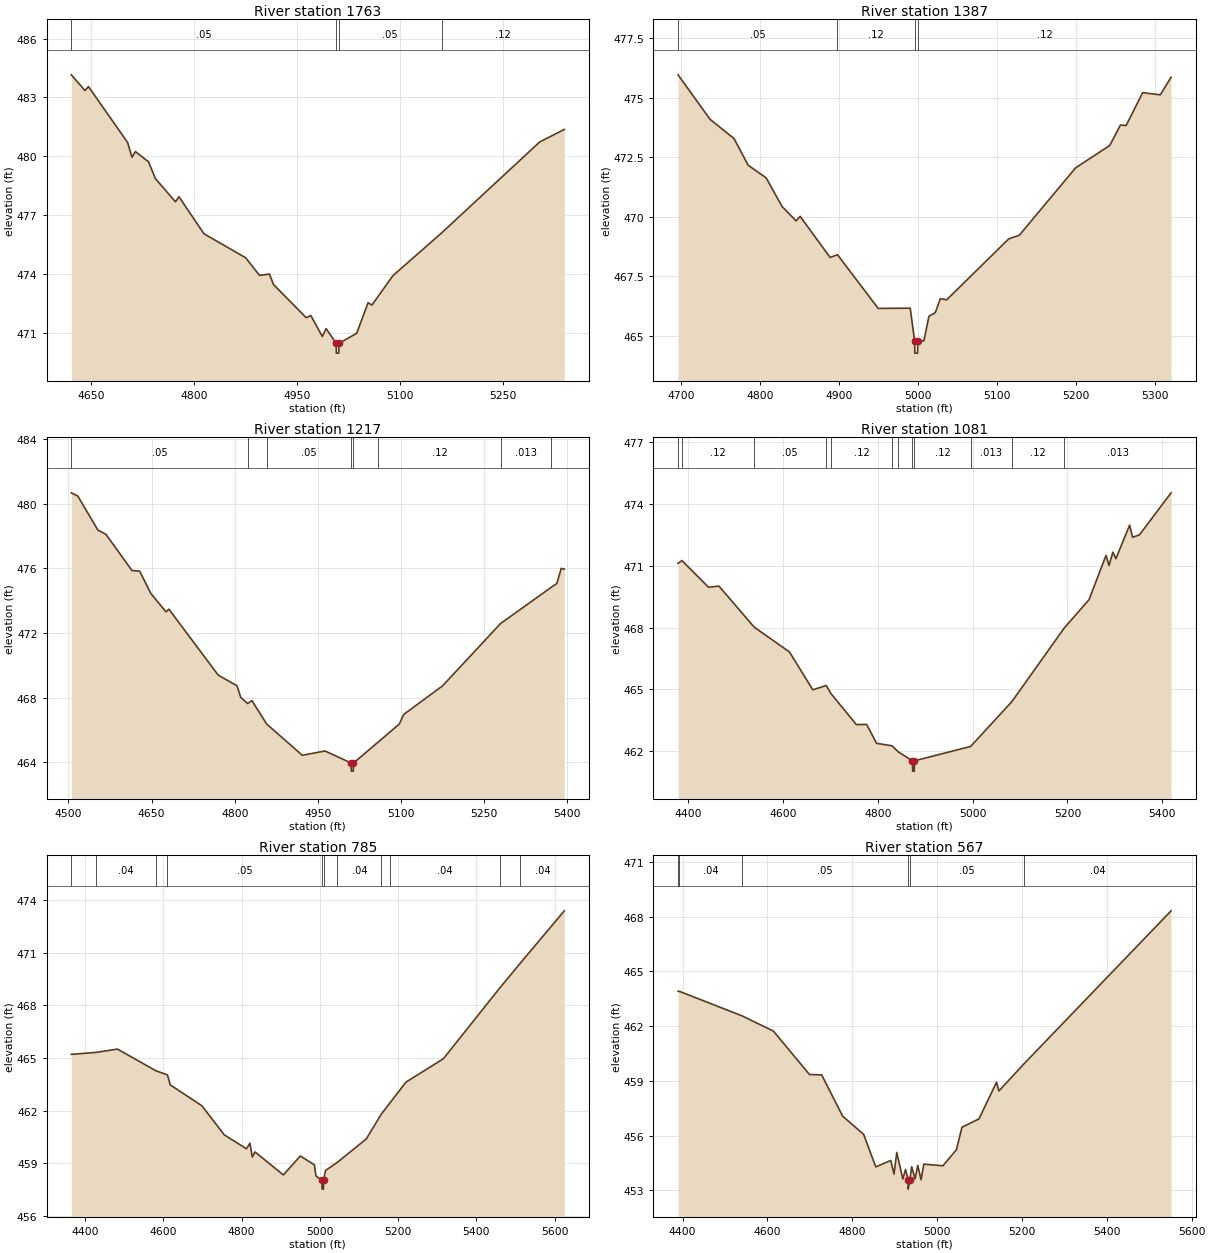
Type RM Length L Ch R = 1,1763,376,376,376
BEGIN DESCRIPTION:
Mapping XS 6e33c78c
END DESCRIPTION:
XS GIS Cut Line= 3
      2403546.19     13587166.45      2403205.90     13587218.53
      2402872.56     13587388.67
#Sta/Elev= 30
  4621.1  484.15  4641.0  483.35  4646.1  483.55  4703.2  480.70  4709.5  479.95
  4714.5  480.24  4733.6  479.72  4743.7  478.86  4772.9  477.68  4777.9  477.94
  4814.5  476.05  4875.2  474.83  4895.4  473.93  4909.8  474.00  4915.7  473.47
  4963.3  471.78  4970.3  471.88  4986.9  470.82  4992.5  471.22  5007.1  470.47
  5007.4  469.97  5010.9  469.97  5011.1  470.47  5037.0  470.98  5053.6  472.54
  5059.2  472.42  5089.9  473.92  5160.6  476.09  5303.7  480.73  5339.6  481.37
#Mann=4,-1,0
  4621.1    0.05       0  5007.1    0.05       0  5011.1    0.05       0
  5160.6    0.12       0
Bank Sta=5007.1,5011.1
Exp/Cntr=0.3,0.1

Type RM Length L Ch R = 1,1387,170,170,170
BEGIN DESCRIPTION:
TRIB 12_1 TO SALT CREEK 3.0
END DESCRIPTION:
XS GIS Cut Line= 3
      2403424.98     13586925.00      2403125.00     13586875.00
      2402924.98     13587125.02
#Sta/Elev= 30
  4696.2  475.97  4736.7  474.10  4767.1  473.29  4784.9  472.17  4807.7  471.64
  4828.0  470.43  4845.7  469.83  4850.8  470.02  4888.8  468.29  4898.0  468.41
  4949.6  466.15  4990.2  466.16  4995.8  464.77  4996.0  464.27  4999.5  464.27
  4999.8  464.77  5007.5  464.79  5013.9  465.82  5021.9  465.97  5028.3  466.56
  5036.3  466.51  5114.8  469.07  5128.4  469.23  5199.6  472.06  5242.8  473.00
  5256.4  473.86  5263.6  473.84  5284.5  475.22  5306.9  475.13  5320.5  475.87
#Mann=4,-1,0
  4696.2    0.05       0  4898.0    0.12       0  4995.8    0.05       0
  4999.8    0.12       0
Bank Sta=4995.8,4999.8
Exp/Cntr=0.3,0.1

Type RM Length L Ch R = 1,1217,136,136,136
BEGIN DESCRIPTION:
Mapping XS d229d850
END DESCRIPTION:
XS GIS Cut Line= 3
      2403556.59     13586642.14      2403067.01     13586722.00
      2402762.65     13586971.03
#Sta/Elev= 30
  4505.2  480.69  4516.9  480.49  4553.2  478.38  4567.6  478.12  4614.7  475.87
  4628.4  475.84  4648.7  474.45  4676.1  473.31  4681.2  473.48  4770.2  469.39
  4804.1  468.73  4810.8  468.01  4823.2  467.63  4831.0  467.81  4857.6  466.36
  4921.9  464.42  4962.8  464.69  5010.1  463.94  5010.3  463.44  5013.8  463.44
  5014.1  463.94  5058.7  465.24  5096.8  466.36  5104.7  466.95  5175.0  468.73
  5279.5  472.59  5371.2  474.84  5381.0  475.07  5388.9  476.01  5394.5  475.96
#Mann=8,-1,0
  4505.2    0.05       0  4823.2    0.12       0  4857.6    0.05       0
  5010.1    0.05       0  5014.1    0.05       0  5058.7    0.12       0
  5279.5   0.013       0  5371.2    0.05       0
Bank Sta=5010.1,5014.1
Exp/Cntr=0.3,0.1

Type RM Length L Ch R = 1,1081,296,296,296
BEGIN DESCRIPTION:
Mapping XS 0ace556b
END DESCRIPTION:
XS GIS Cut Line= 3
      2403439.19     13586137.67      2403026.85     13586597.77
      2402768.59     13586931.98
#Sta/Elev= 30
  4378.5  471.12  4386.6  471.26  4443.0  469.96  4464.7  470.02  4538.9  468.03
  4613.5  466.82  4662.8  464.98  4691.2  465.19  4701.0  464.80  4754.7  463.29
  4776.4  463.30  4797.4  462.38  4830.0  462.26  4843.5  461.96  4873.1  461.53
  4873.4  461.03  4876.9  461.03  4877.1  461.53  4995.8  462.23  5082.9  464.41
  5193.5  467.99  5245.6  469.36  5281.4  471.51  5287.7  471.02  5295.9  471.67
  5302.2  471.35  5331.2  472.98  5337.5  472.39  5352.0  472.51  5418.7  474.55
#Mann=12,-1,0
  4378.5    0.05       0  4386.6    0.12       0  4538.9    0.05       0
  4691.2   0.013       0  4701.0    0.12       0  4830.0    0.05       0
  4843.5    0.12       0  4873.1    0.03       0  4877.1    0.12       0
  4995.8   0.013       0  5082.9    0.12       0  5193.5   0.013       0
Bank Sta=4873.1,4877.1
Exp/Cntr=0.3,0.1

Type RM Length L Ch R = 1,785,218,218,218
BEGIN DESCRIPTION:
Mapping XS 2345b128
END DESCRIPTION:
XS GIS Cut Line= 3
      2403378.40     13585805.68      2403026.85     13586326.50
      2402706.67     13586871.67
#Sta/Elev= 30
  4364.5  465.20  4426.6  465.31  4482.5  465.50  4580.4  464.27  4610.2  464.03
  4617.5  463.46  4698.4  462.27  4755.3  460.62  4812.3  459.82  4821.2  460.14
  4827.3  459.35  4834.2  459.64  4906.6  458.33  4950.2  459.41  4986.1  458.90
  4990.0  458.27  5005.5  458.02  5005.7  457.52  5009.2  457.52  5009.5  458.02
  5014.3  458.58  5044.9  459.05  5118.7  460.38  5157.3  461.80  5180.1  462.46
  5220.4  463.62  5315.8  464.95  5459.9  468.98  5513.0  470.41  5625.1  473.38
#Mann=11,-1,0
  4364.5   0.013       0  4426.6    0.04       0  4580.4   0.013       0
  4610.2    0.05       0  5005.5    0.05       0  5009.5    0.05       0
  5044.9    0.04       0  5157.3   0.013       0  5180.1    0.04       0
  5459.9   0.013       0  5513.0    0.04       0
Bank Sta=5005.5,5009.5
Exp/Cntr=0.3,0.1

Type RM Length L Ch R = 1,567,282,282,282
BEGIN DESCRIPTION:
Mapping XS a8148fb3
END DESCRIPTION:
XS GIS Cut Line= 3
      2403348.00     13585781.82      2402879.28     13586170.25
      2402693.24     13586691.59
#Sta/Elev= 30
  4389.2  463.91  4392.1  463.91  4540.6  462.56  4613.9  461.73  4699.1  459.35
  4727.7  459.33  4777.2  457.07  4826.7  456.07  4855.3  454.29  4890.5  454.64
  4898.3  453.90  4904.8  455.08  4919.1  453.62  4925.6  454.15  4931.5  453.57
  4931.7  453.07  4935.5  453.57  4940.0  454.30  4947.8  453.63  4954.3  454.37
  4962.1  453.58  4968.6  454.44  5013.6  454.35  5045.5  455.23  5058.4  456.46
  5098.6  456.92  5140.1  458.93  5145.5  458.45  5205.7  459.96  5551.5  468.32
#Mann=6,-1,0
  4389.2    0.05       0  4392.1    0.04       0  4540.6    0.05       0
  4931.5    0.05       0  4935.5    0.05       0  5205.7    0.04       0
Bank Sta=4931.5,4935.5
Exp/Cntr=0.3,0.1

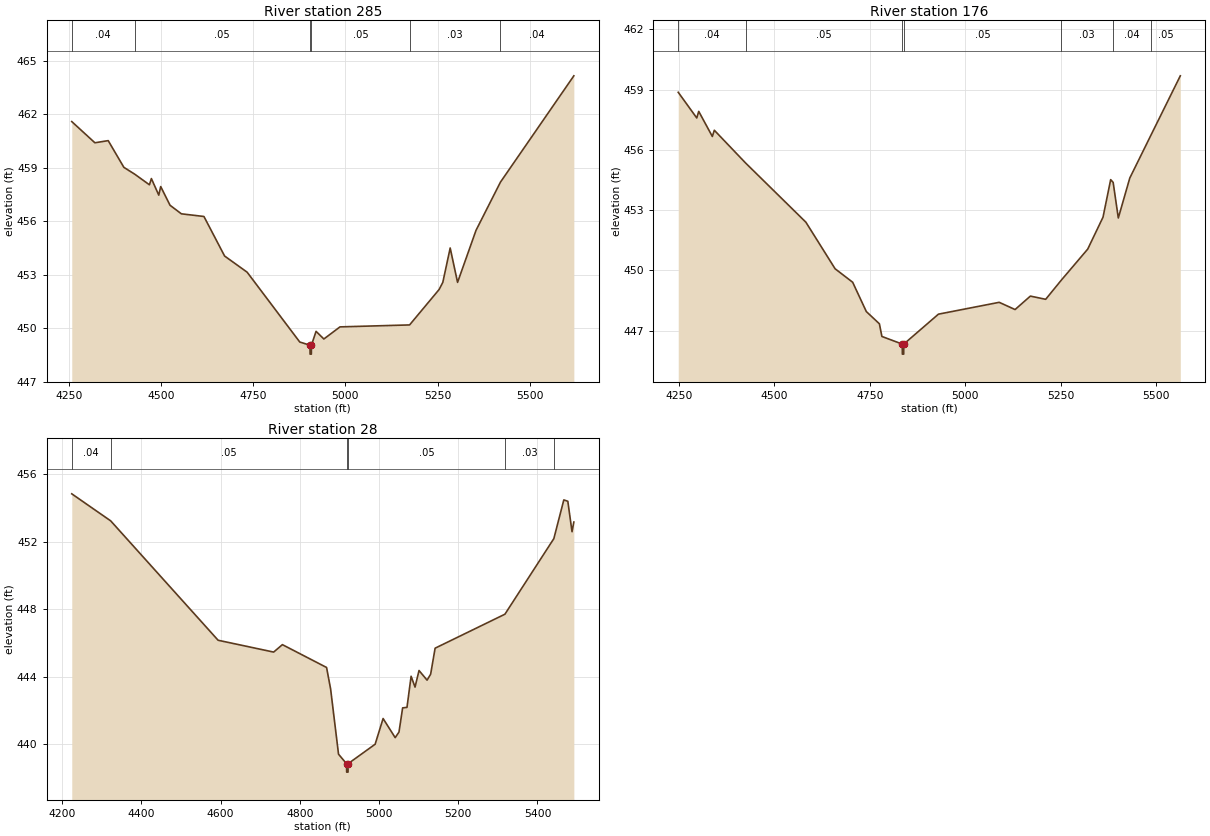
Type RM Length L Ch R = 1,285,109,109,109
BEGIN DESCRIPTION:
Mapping XS 2a1e2547aa
END DESCRIPTION:
XS GIS Cut Line= 4
      2403367.87     13585658.22      2402757.39     13585879.41
      2402651.22     13586044.57      2402651.22     13586560.31
#Sta/Elev= 30
  4258.1  461.60  4320.8  460.41  4356.9  460.53  4399.4  459.03  4428.5  458.65
  4468.7  458.05  4474.0  458.40  4494.0  457.47  4499.3  457.95  4524.6  456.90
  4555.3  456.42  4616.5  456.27  4672.5  454.05  4733.7  453.14  4876.3  449.22
  4904.0  449.04  4904.3  448.54  4907.8  448.54  4908.0  449.04  4920.5  449.82
  4941.7  449.39  4985.4  450.07  5174.1  450.18  5254.2  452.17  5264.2  452.57
  5284.2  454.50  5304.2  452.57  5354.2  455.49  5420.5  458.20  5619.5  464.17
#Mann=6,-1,0
  4258.1    0.04       0  4428.5    0.05       0  4904.0    0.05       0
  4908.0    0.05       0  5174.1    0.03       0  5420.5    0.04       0
Bank Sta=4904,4908
Exp/Cntr=0.3,0.1

Type RM Length L Ch R = 1,176,148,148,148
BEGIN DESCRIPTION:
Mapping XS b477848b
END DESCRIPTION:
XS GIS Cut Line= 4
      2403295.95     13585627.71      2402657.92     13585790.48
      2402592.82     13585998.81      2402621.03     13586437.17
#Sta/Elev= 30
  4248.0  458.87  4296.6  457.59  4301.7  457.92  4337.4  456.67  4342.6  456.98
  4424.5  455.35  4582.6  452.40  4659.2  450.08  4705.2  449.41  4741.0  447.95
  4775.3  447.34  4781.8  446.71  4835.2  446.33  4835.5  445.83  4839.0  445.83
  4839.2  446.33  4930.0  447.82  5089.3  448.41  5130.9  448.05  5171.0  448.72
  5211.1  448.56  5251.9  449.51  5321.3  451.06  5361.4  452.65  5381.5  454.52
  5388.0  454.38  5401.5  452.61  5431.6  454.60  5486.9  456.73  5564.0  459.69
#Mann=7,-1,0
  4248.0    0.04       0  4424.5    0.05       0  4835.2    0.05       0
  4839.2    0.05       0  5251.9    0.03       0  5388.0    0.04       0
  5486.9    0.05       0
Bank Sta=4835.2,4839.2
Exp/Cntr=0.3,0.1

Type RM Length L Ch R = 1,28,0,0,0
BEGIN DESCRIPTION:
Mapping XS 2a1e2547a
END DESCRIPTION:
XS GIS Cut Line= 4
      2403179.12     13585613.98      2402510.45     13585727.72
      2402497.86     13585888.26      2402571.58     13586309.96
#Sta/Elev= 30
  4224.5  454.82  4322.8  453.22  4593.9  446.16  4734.1  445.46  4756.2  445.90
  4867.7  444.55  4877.9  443.28  4897.9  439.42  4918.1  438.86  4918.4  438.36
  4921.9  438.36  4922.1  438.86  4990.3  440.01  5010.4  441.53  5040.9  440.40
  5050.5  440.73  5059.7  442.16  5070.7  442.19  5081.1  444.03  5091.0  443.39
  5101.1  444.37  5121.4  443.80  5130.4  444.15  5141.7  445.69  5317.9  447.70
  5441.4  452.17  5466.6  454.46  5476.7  454.38  5487.3  452.58  5491.9  453.15
#Mann=6,-1,0
  4224.5    0.04       0  4322.8    0.05       0  4918.1    0.05       0
  4922.1    0.05       0  5317.9    0.03       0  5441.4    0.04       0
Bank Sta=4918.1,4922.1
Exp/Cntr=0.3,0.1

Chan Stop Cuts=-1