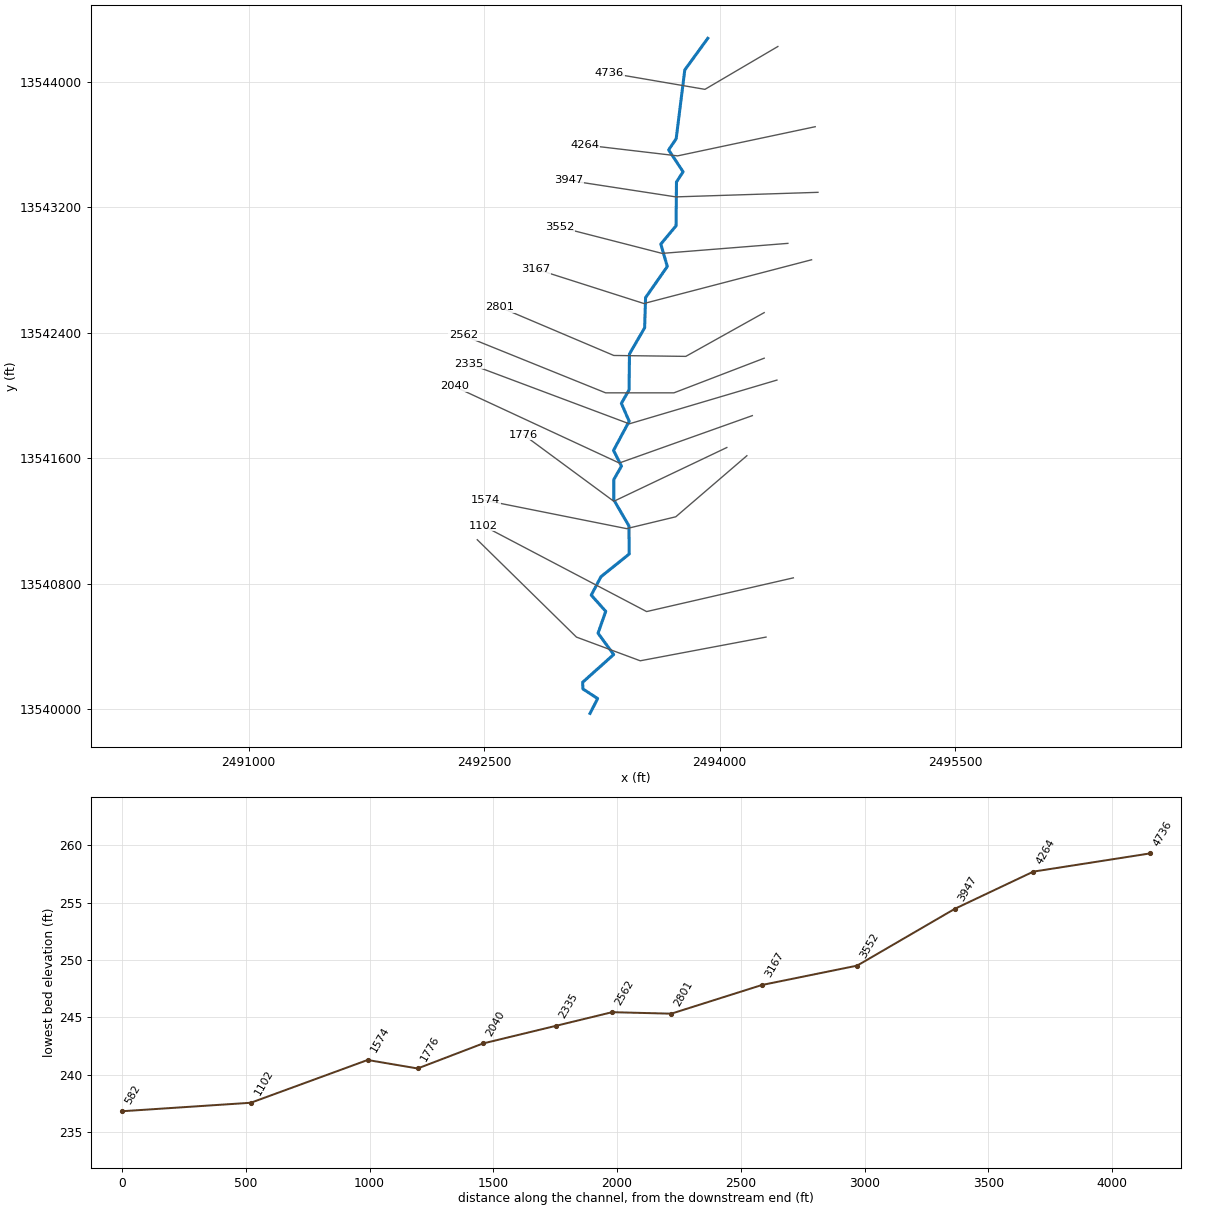
--- TRIB 12_1 TO TWELVEMILE CREEK.prj (project) ---

Proj Title=TRIB 12_1 TO TWELVEMILE CREEK Base Level Engineering
Current Plan=p01
Default Exp/Contr=0.3,0.1
English Units
Geom File=g01
Flow File=f01
Plan File=p01
Y Axis Title=Elevation
X Axis Title(PF)=Main Channel Distance
X Axis Title(XS)=Station
BEGIN DESCRIPTION:
TRIB 12_1 TO TWELVEMILE CREEK
END DESCRIPTION:
DSS Export Rating Curves= 0
DSS Export Rating Curve Sorted= 0
DSS Export Volume Flow Curves= 0
DXF OffsetX= 0
DXF OffsetY= 0
DXF ScaleX= 1
DXF ScaleY= 10

--- TRIB 12_1 TO TWELVEMILE CREEK.p01 (plan) ---

Plan Title=Multiple Run
Short Identifier=Multiple
Geom File=g01
Flow File=f01
Subcritical Flow
K Sum by GR= 0
Std Step Tol= 0.01
Critical Tol= 0.01
Num of Std Step Trials= 20
Max Error Tol= 0.3
Flow Tol Ratio= 0.001
Split Flow NTrial= 30
Split Flow Tol= 0.02
Split Flow Ratio= 0.02
Log Output Level= 0
Friction Slope Method= 1
Unsteady Friction Slope Method= 2
Unsteady Bridges Friction Slope Method= 1
Parabolic Critical Depth
Global Vel Dist=  1 , 1 , 1
Global Log Level= 0
CheckData=True
Encroach Param= -1, 0, 0, 0
BEGIN DESCRIPTION:
Multiple Run
END DESCRIPTION:

--- TRIB 12_1 TO TWELVEMILE CREEK.f01 (steady flow) ---

Flow Title=Multiple
Number of Profiles=7
Profile Names=10-year,25-year,50-year,1pct_min,100-year,1pct_plu,500-year
River Rch & RM= TRIB 12_1 TO TWE,Reach-1,4736
     443     694     915     584    1166    2326    1872
River Rch & RM= TRIB 12_1 TO TWE,Reach-1,3947
     537     850    1129     726    1448    2889    2355
River Rch & RM= TRIB 12_1 TO TWE,Reach-1,582
     794    1289    1739    1134    2264    4516    3796
Boundary for River Rch & Prof#=TRIB 12_1 TO TWE,Reach-1,1
Up Type=0
Dn Type=3
Dn Slope=0.005
Boundary for River Rch & Prof#=TRIB 12_1 TO TWE,Reach-1,2
Up Type=0
Dn Type=3
Dn Slope=0.005
Boundary for River Rch & Prof#=TRIB 12_1 TO TWE,Reach-1,3
Up Type=0
Dn Type=3
Dn Slope=0.005
Boundary for River Rch & Prof#=TRIB 12_1 TO TWE,Reach-1,4
Up Type=0
Dn Type=3
Dn Slope=0.005
Boundary for River Rch & Prof#=TRIB 12_1 TO TWE,Reach-1,5
Up Type=0
Dn Type=3
Dn Slope=0.005
Boundary for River Rch & Prof#=TRIB 12_1 TO TWE,Reach-1,6
Up Type=0
Dn Type=3
Dn Slope=0.005
Boundary for River Rch & Prof#=TRIB 12_1 TO TWE,Reach-1,7
Up Type=0
Dn Type=3
Dn Slope=0.005

--- TRIB 12_1 TO TWELVEMILE CREEK.g01 (geometry) ---

Geom Title=Existing Conditions

River Reach=TRIB 12_1 TO TWE,Reach-1
Reach XY= 30
      2493925.00     13544275.00      2493778.54     13544073.54
      2493723.76     13543635.50      2493675.72     13543564.29
      2493767.67     13543425.10      2493725.66     13543359.84
      2493722.93     13543080.86      2493625.95     13542964.51
      2493667.19     13542821.59      2493528.75     13542623.45
      2493522.76     13542430.93      2493426.20     13542264.50
      2493423.76     13542035.50      2493374.61     13541950.00
      2493424.25     13541835.69      2493324.60     13541650.00
      2493375.39     13541550.00      2493326.23     13541464.50
      2493326.19     13541335.50      2493422.76     13541169.07
      2493424.62     13540990.15      2493244.62     13540845.47
      2493182.77     13540728.23      2493275.00     13540625.00
      2493225.93     13540485.47      2493325.62     13540349.91
      2493127.94     13540173.00      2493129.77     13540130.63
      2493223.51     13540069.22      2493175.00     13539975.00

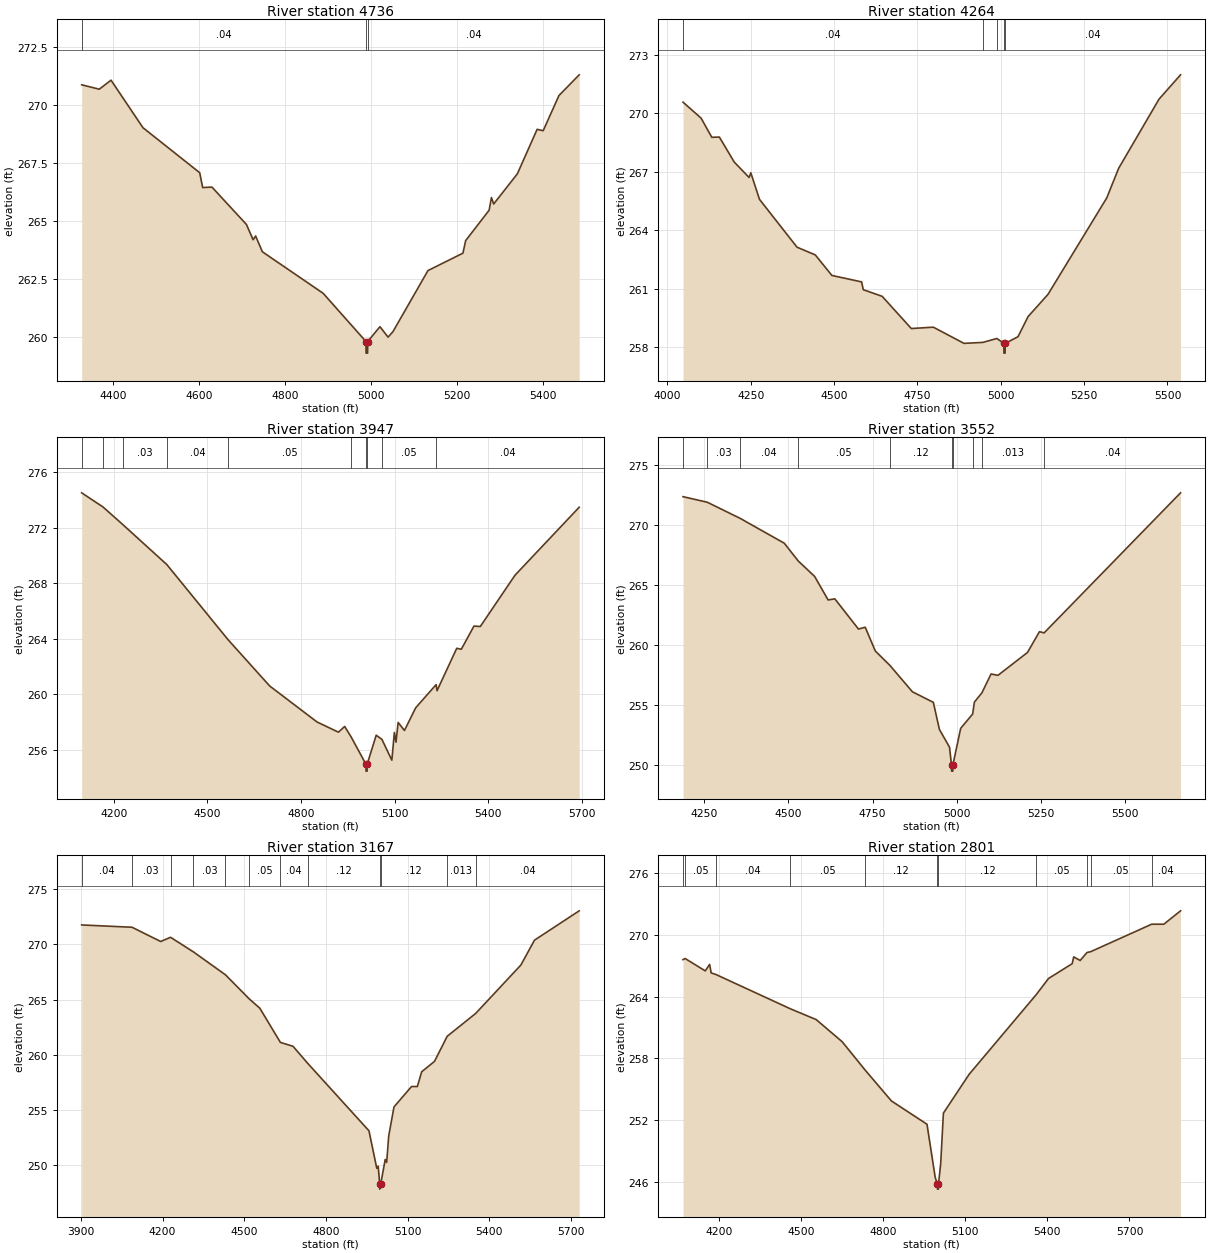
Type RM Length L Ch R = 1,4736,472,472,472
BEGIN DESCRIPTION:
Mapping XS e477b013
END DESCRIPTION:
XS GIS Cut Line= 3
      2494371.45     13544222.95      2493907.00     13543950.08
      2493298.75     13544054.35
#Sta/Elev= 30
  4327.4  270.86  4368.3  270.67  4395.6  271.06  4469.8  269.01  4601.6  267.07
  4608.5  266.43  4630.0  266.45  4710.1  264.84  4725.7  264.18  4731.5  264.34
  4747.2  263.66  4888.4  261.87  4987.9  259.79  4988.1  259.29  4991.6  259.29
  4991.9  259.79  5020.3  260.43  5039.3  259.98  5050.7  260.22  5131.9  262.85
  5213.1  263.60  5219.4  264.14  5273.9  265.45  5279.4  266.00  5284.5  265.72
  5339.5  267.02  5385.5  268.94  5399.5  268.88  5436.3  270.40  5483.2  271.29
#Mann=3,-1,0
  4327.4    0.04       0  4987.9    0.04       0  4991.9    0.04       0
Bank Sta=4987.9,4991.9
Exp/Cntr=0.3,0.1

Type RM Length L Ch R = 1,4264,317,317,317
BEGIN DESCRIPTION:
Mapping XS 5fabc7b6
END DESCRIPTION:
XS GIS Cut Line= 3
      2494609.45     13543712.05      2493732.84     13543526.28
      2493140.70     13543595.94
#Sta/Elev= 30
  4046.9  270.56  4101.2  269.74  4133.2  268.76  4156.0  268.77  4200.6  267.49
  4245.1  266.70  4250.3  266.94  4276.3  265.58  4388.8  263.13  4443.8  262.73
  4493.5  261.68  4582.6  261.35  4587.7  260.95  4644.3  260.61  4731.7  258.96
  4797.7  259.03  4889.7  258.20  4946.3  258.25  4988.2  258.45  5009.3  258.20
  5009.5  257.70  5013.0  257.70  5013.3  258.20  5051.6  258.54  5081.8  259.57
  5141.6  260.71  5317.8  265.65  5353.6  267.17  5474.5  270.71  5539.2  271.96
#Mann=5,-1,0
  4046.9    0.04       0  4946.3    0.05       0  4988.2    0.04       0
  5009.3    0.04       0  5013.3    0.04       0
Bank Sta=5009.3,5013.3
Exp/Cntr=0.3,0.1

Type RM Length L Ch R = 1,3947,395,395,395
BEGIN DESCRIPTION:
Mapping XS e517bb9e
END DESCRIPTION:
XS GIS Cut Line= 3
      2494626.88     13543294.06      2493721.22     13543265.03
      2493041.94     13543369.53
#Sta/Elev= 30
  4097.6  274.53  4165.9  273.51  4228.4  272.26  4370.2  269.36  4566.8  263.93
  4699.8  260.60  4851.7  258.00  4919.9  257.27  4939.9  257.68  4960.0  256.95
  5008.0  254.96  5008.3  254.46  5011.8  254.46  5012.0  254.96  5040.9  257.05
  5059.2  256.75  5091.0  255.25  5099.1  257.25  5104.2  256.55  5111.2  257.97
  5131.4  257.39  5167.4  259.03  5232.8  260.70  5235.7  260.26  5298.9  263.32
  5313.5  263.25  5354.0  264.92  5374.3  264.89  5485.5  268.59  5691.0  273.49
#Mann=10,-1,0
  4097.6    0.03       0  4165.9    0.04       0  4228.4    0.03       0
  4370.2    0.04       0  4566.8    0.05       0  4960.0   0.013       0
  5008.0    0.03       0  5012.0   0.013       0  5059.2    0.05       0
  5232.8    0.04       0
Bank Sta=5008,5012
Exp/Cntr=0.3,0.1

Type RM Length L Ch R = 1,3552,385,385,385
BEGIN DESCRIPTION:
Mapping XS 2a3413a9
END DESCRIPTION:
XS GIS Cut Line= 3
      2494435.26     13542968.94      2493634.14     13542905.08
      2492979.03     13543073.21
#Sta/Elev= 30
  4186.3  272.33  4258.3  271.87  4356.7  270.52  4487.5  268.46  4529.1  266.98
  4577.8  265.70  4617.9  263.74  4638.0  263.83  4708.2  261.32  4728.3  261.47
  4758.4  259.49  4801.6  258.30  4868.7  256.10  4931.0  255.22  4949.0  252.97
  4979.1  251.49  4985.0  250.00  4985.3  249.50  4988.8  249.50  4989.0  250.00
  5012.3  253.06  5047.9  254.25  5053.1  255.24  5075.6  256.02  5102.6  257.58
  5123.3  257.47  5211.0  259.37  5246.6  261.10  5260.5  261.00  5666.3  272.65
#Mann=10,-1,0
  4186.3   0.013       0  4258.3    0.03       0  4356.7    0.04       0
  4529.1    0.05       0  4801.6    0.12       0  4985.0    0.05       0
  4989.0    0.12       0  5047.9    0.05       0  5075.6   0.013       0
  5260.5    0.04       0
Bank Sta=4985,4989
Exp/Cntr=0.3,0.1

Type RM Length L Ch R = 1,3167,366,366,366
BEGIN DESCRIPTION:
Mapping XS cd8b9ad9
END DESCRIPTION:
XS GIS Cut Line= 3
      2494586.24     13542864.44      2493518.03     13542585.78
      2492828.58     13542805.94
#Sta/Elev= 30
  3902.8  271.76  4087.9  271.55  4193.0  270.26  4229.3  270.64  4313.2  269.32
  4431.1  267.24  4518.2  265.06  4557.3  264.21  4632.9  261.11  4679.2  260.76
  4733.7  259.20  4958.2  253.10  4987.0  249.69  4992.2  249.89  4997.6  248.31
  4997.8  247.81  5001.6  248.31  5017.9  250.50  5023.2  250.24  5030.9  252.65
  5050.1  255.26  5114.5  257.11  5135.9  257.11  5151.9  258.45  5198.9  259.39
  5245.7  261.67  5349.9  263.73  5516.4  268.13  5566.3  270.38  5730.5  273.04
#Mann=12,-1,0
  3902.8    0.04       0  4087.9    0.03       0  4229.3    0.04       0
  4313.2    0.03       0  4431.1    0.04       0  4518.2    0.05       0
  4632.9    0.04       0  4733.7    0.12       0  4997.6    0.05       0
  5001.6    0.12       0  5245.7   0.013       0  5349.9    0.04       0
Bank Sta=4997.6,5001.6
Exp/Cntr=0.3,0.1

Type RM Length L Ch R = 1,2801,239,239,239
BEGIN DESCRIPTION:
Mapping XS 530b56c0
END DESCRIPTION:
XS GIS Cut Line= 4
      2494284.35     13542527.72      2493785.09     13542249.06
      2493326.45     13542254.86      2492600.73     13542562.56
#Sta/Elev= 30
  4068.1  267.59  4075.9  267.70  4149.4  266.50  4165.4  267.13  4171.1  266.30
  4188.3  266.15  4460.4  262.82  4555.0  261.77  4650.0  259.62  4734.5  256.85
  4830.0  253.87  4960.0  251.61  4990.0  246.45  4998.0  245.81  4998.2  245.31
  5001.7  245.31  5002.0  245.81  5010.0  247.77  5020.0  252.69  5114.1  256.46
  5359.5  264.20  5404.2  265.76  5490.8  267.20  5496.3  267.86  5519.9  267.51
  5544.7  268.28  5558.0  268.36  5781.3  271.03  5825.7  271.03  5886.8  272.33
#Mann=11,-1,0
  4068.1    0.04       0  4075.9    0.05       0  4188.3    0.04       0
  4460.4    0.05       0  4734.5    0.12       0  4998.0    0.05       0
  5002.0    0.12       0  5359.5    0.05       0  5544.7    0.04       0
  5558.0    0.05       0  5781.3    0.04       0
Bank Sta=4998,5002
Exp/Cntr=0.3,0.1

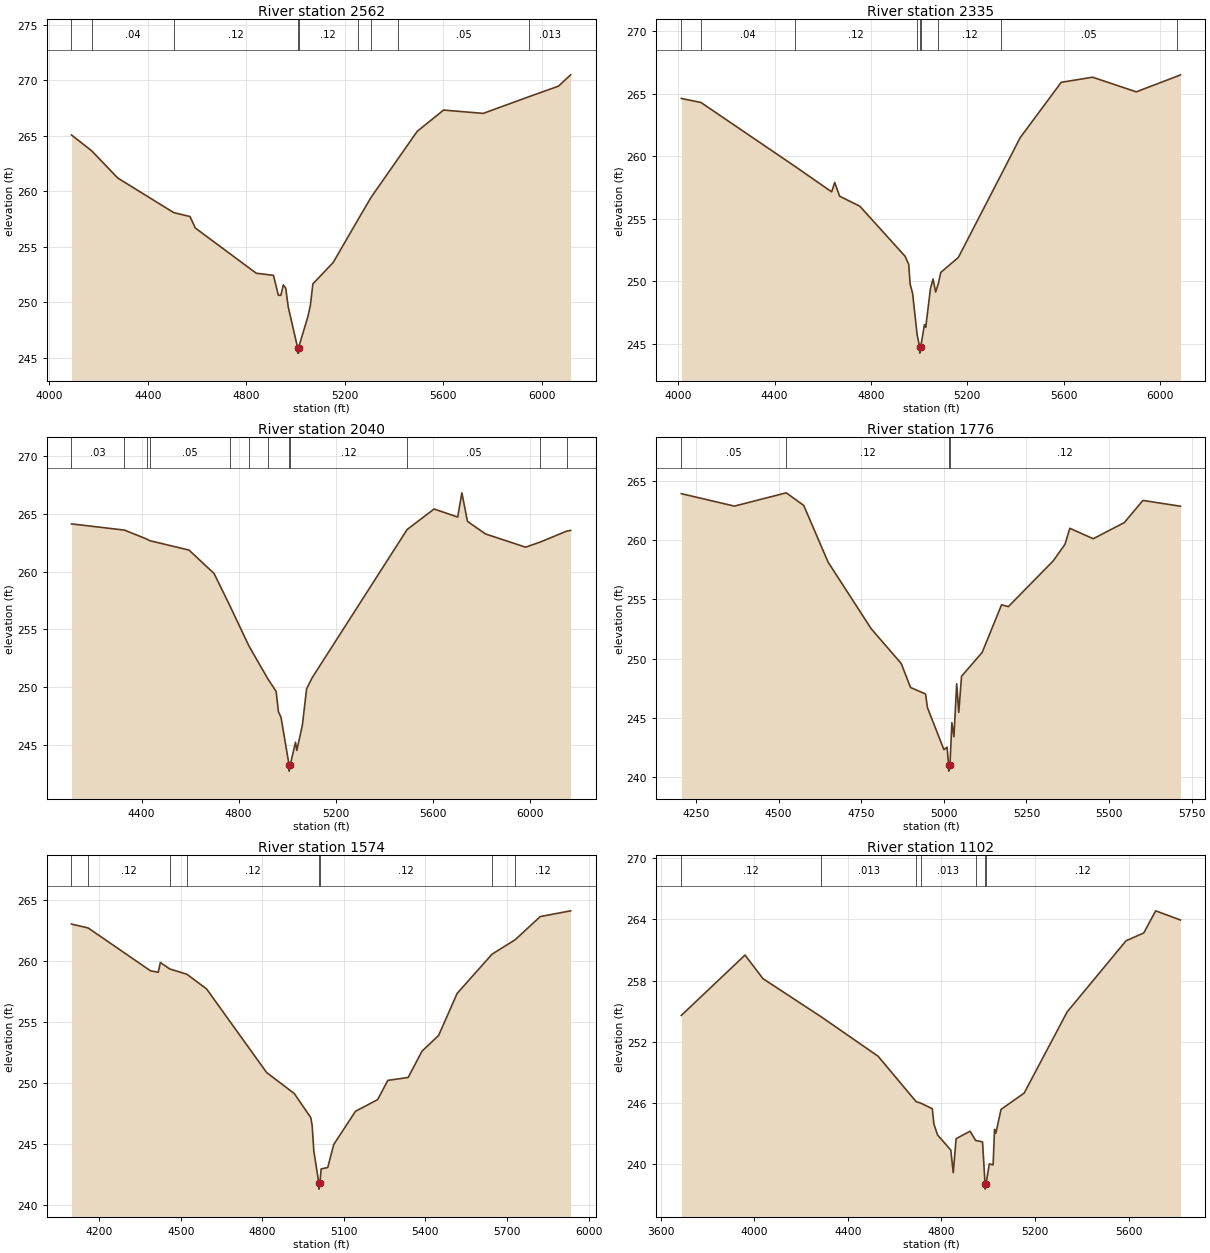
Type RM Length L Ch R = 1,2562,227,227,227
BEGIN DESCRIPTION:
Mapping XS 4ce6b4da
END DESCRIPTION:
XS GIS Cut Line= 4
      2494284.34     13542237.44      2493709.61     13542016.83
      2493274.20     13542016.83      2492369.24     13542382.30
#Sta/Elev= 30
  4090.0  265.07  4172.2  263.64  4277.5  261.20  4505.4  258.08  4571.3  257.73
  4592.7  256.70  4840.2  252.63  4910.2  252.44  4930.2  250.65  4940.2  250.64
  4950.2  251.58  4960.2  251.27  4970.2  249.59  5008.2  245.94  5008.5  245.44
  5012.0  245.44  5012.2  245.94  5050.2  248.74  5060.2  249.75  5070.2  251.67
  5152.9  253.60  5253.0  257.43  5306.4  259.45  5416.1  262.93  5493.7  265.39
  5601.0  267.31  5762.0  267.01  5948.9  268.52  6067.6  269.46  6117.0  270.48
#Mann=9,-1,0
  4090.0    0.05       0  4172.2    0.04       0  4505.4    0.12       0
  5008.2    0.05       0  5012.2    0.12       0  5253.0    0.05       0
  5306.4    0.12       0  5416.1    0.05       0  5948.9   0.013       0
Bank Sta=5008.2,5012.2
Exp/Cntr=0.3,0.1

Type RM Length L Ch R = 1,2335,295,295,295
BEGIN DESCRIPTION:
Mapping XS 19ce62d6
END DESCRIPTION:
XS GIS Cut Line= 3
      2494365.64     13542098.11      2493425.14     13541819.44
      2492403.34     13542202.62
#Sta/Elev= 30
  4012.5  264.62  4093.9  264.30  4482.8  259.21  4636.6  257.15  4649.4  257.90
  4669.8  256.80  4753.7  256.00  4941.4  252.00  4956.7  251.34  4962.3  249.79
  4972.7  249.03  4991.6  245.70  5002.2  244.75  5002.5  244.25  5006.2  244.75
  5021.9  246.53  5027.2  246.32  5046.8  249.41  5057.6  250.18  5068.3  249.14
  5079.7  249.83  5089.7  250.71  5162.5  251.90  5340.7  258.54  5418.8  261.47
  5589.7  265.91  5719.8  266.32  5901.2  265.15  6068.6  266.38  6084.7  266.51
#Mann=9,-1,0
  4012.5    0.05       0  4093.9    0.04       0  4482.8    0.12       0
  4991.6    0.05       0  5002.2    0.05       0  5006.2    0.05       0
  5079.7    0.12       0  5340.7    0.05       0  6068.6   0.013       0
Bank Sta=5002.2,5006.2
Exp/Cntr=0.3,0.1

Type RM Length L Ch R = 1,2040,264,264,264
BEGIN DESCRIPTION:
Mapping XS 5110dc1d
END DESCRIPTION:
XS GIS Cut Line= 3
      2494208.88     13541871.69      2493361.28     13541569.81
      2492310.48     13542057.47
#Sta/Elev= 30
  4111.1  264.13  4329.5  263.59  4422.0  262.81  4432.9  262.68  4595.6  261.86
  4699.1  259.83  4763.9  257.05  4842.3  253.57  4922.1  250.66  4954.9  249.62
  4964.4  247.86  4975.1  247.37  5008.6  243.21  5008.8  242.71  5012.6  243.21
  5034.7  245.21  5040.2  244.50  5063.1  246.69  5080.5  249.83  5103.4  250.80
  5495.0  263.64  5606.4  265.42  5703.5  264.72  5720.9  266.82  5743.8  264.35
  5818.0  263.26  5983.8  262.11  6044.3  262.56  6154.1  263.51  6169.3  263.56
#Mann=12,-1,0
  4111.1    0.03       0  4329.5    0.12       0  4422.0    0.03       0
  4432.9    0.05       0  4763.9    0.12       0  4842.3    0.05       0
  4922.1    0.12       0  5008.6    0.05       0  5012.6    0.12       0
  5495.0    0.05       0  6044.3   0.013       0  6154.1    0.05       0
Bank Sta=5008.6,5012.6
Exp/Cntr=0.3,0.1

Type RM Length L Ch R = 1,1776,202,202,202
BEGIN DESCRIPTION:
Mapping XS 9614e0b9
END DESCRIPTION:
XS GIS Cut Line= 3
      2494046.29     13541668.48      2493326.45     13541325.97
      2492751.68     13541749.79
#Sta/Elev= 30
  4205.2  263.92  4365.9  262.87  4522.9  263.99  4575.8  262.93  4649.6  258.15
  4780.2  252.53  4871.1  249.60  4899.3  247.58  4944.8  247.03  4950.3  245.89
  5000.4  242.34  5009.8  242.55  5014.6  241.03  5014.8  240.53  5018.6  241.03
  5024.4  244.62  5030.6  243.43  5039.0  247.89  5045.3  245.49  5053.7  248.53
  5116.2  250.54  5174.8  254.55  5195.6  254.40  5331.4  258.26  5366.9  259.65
  5381.5  261.00  5452.5  260.12  5546.5  261.48  5602.8  263.35  5716.5  262.86
#Mann=4,-1,0
  4205.2    0.05       0  4522.9    0.12       0  5014.6    0.05       0
  5018.6    0.12       0
Bank Sta=5014.6,5018.6
Exp/Cntr=0.3,0.1

Type RM Length L Ch R = 1,1574,472,472,472
BEGIN DESCRIPTION:
Mapping XS 5c74c606
END DESCRIPTION:
XS GIS Cut Line= 4
      2494174.06     13541616.25      2493721.22     13541227.28
      2493407.72     13541151.81      2492508.94     13541331.56
#Sta/Elev= 30
  4098.2  263.06  4159.6  262.74  4388.8  259.22  4417.3  259.10  4425.0  259.90
  4459.8  259.37  4522.3  258.94  4595.1  257.73  4815.8  250.86  4917.6  249.13
  4978.4  247.15  4983.5  246.49  4989.6  244.39  5008.1  241.77  5008.4  241.27
  5012.1  241.77  5016.4  242.93  5040.8  243.05  5062.8  244.94  5142.8  247.67
  5224.4  248.63  5261.7  250.21  5336.5  250.45  5387.5  252.61  5448.7  253.91
  5516.7  257.36  5645.3  260.59  5730.0  261.77  5822.6  263.68  5934.2  264.15
#Mann=8,-1,0
  4098.2    0.03       0  4159.6    0.12       0  4459.8    0.05       0
  4522.3    0.12       0  5008.1    0.05       0  5012.1    0.12       0
  5645.3    0.05       0  5730.0    0.12       0
Bank Sta=5008.1,5012.1
Exp/Cntr=0.3,0.1

Type RM Length L Ch R = 1,1102,520,520,520
BEGIN DESCRIPTION:
Mapping XS b7b415c3
END DESCRIPTION:
XS GIS Cut Line= 3
      2494470.18     13540838.31      2493535.45     13540623.50
      2492496.22     13541169.24
#Sta/Elev= 30
  3688.4  254.58  3960.5  260.50  4037.7  258.18  4287.0  254.43  4529.6  250.57
  4691.9  246.12  4711.0  245.98  4760.9  245.43  4767.8  243.91  4783.5  242.85
  4840.0  241.37  4850.4  239.15  4862.6  242.49  4922.2  243.22  4945.9  242.32
  4975.6  242.17  4986.3  238.04  4986.6  237.54  4990.3  238.04  5004.7  240.02
  5020.7  239.91  5026.8  243.40  5032.4  243.02  5054.6  245.36  5153.4  246.96
  5337.0  254.92  5588.7  261.90  5664.5  262.67  5715.4  264.84  5821.3  263.94
#Mann=7,-1,0
  3688.4    0.12       0  4287.0   0.013       0  4691.9    0.12       0
  4711.0   0.013       0  4945.9    0.12       0  4986.3    0.05       0
  4990.3    0.12       0
Bank Sta=4986.3,4990.3
Exp/Cntr=0.3,0.1

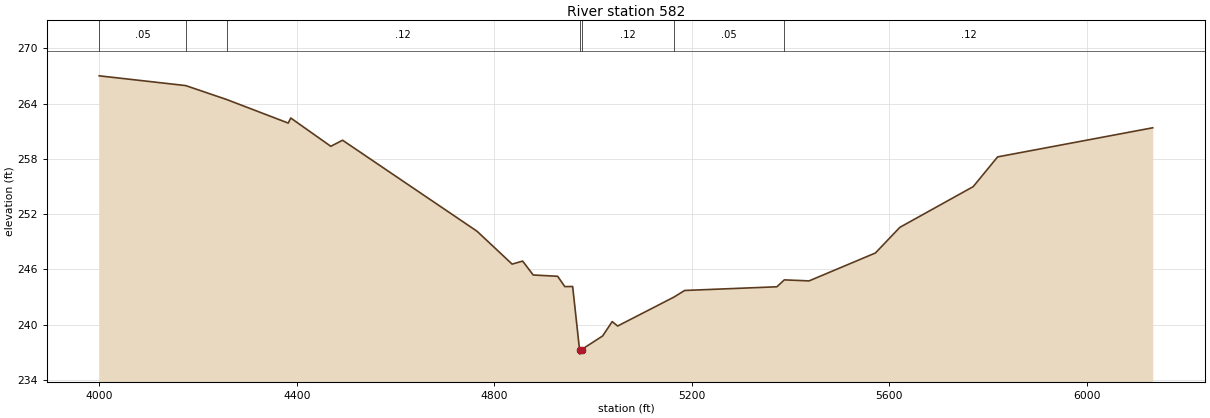
Type RM Length L Ch R = 1,582,0,0,0
BEGIN DESCRIPTION:
Mapping XS a4f7eb23
END DESCRIPTION:
XS GIS Cut Line= 4
      2494295.98     13540460.94      2493494.81     13540310.00
      2493088.42     13540460.94      2492456.70     13541081.07
#Sta/Elev= 30
  3999.7  267.01  4174.9  265.95  4257.8  264.44  4382.6  261.88  4387.7  262.43
  4468.8  259.36  4492.6  260.02  4765.0  250.14  4836.1  246.57  4857.4  246.90
  4878.8  245.39  4928.3  245.25  4942.8  244.13  4958.7  244.14  4972.6  237.30
  4972.9  236.80  4976.9  237.30  5019.4  238.77  5038.8  240.33  5049.8  239.85
  5163.8  242.99  5185.6  243.71  5372.4  244.11  5387.4  244.86  5437.6  244.75
  5572.0  247.78  5621.4  250.56  5770.0  254.98  5819.5  258.21  6133.7  261.37
#Mann=7,-1,0
  3999.7    0.05       0  4174.9   0.013       0  4257.8    0.12       0
  4972.6    0.05       0  4976.9    0.12       0  5163.8    0.05       0
  5387.4    0.12       0
Bank Sta=4972.6,4976.9
Exp/Cntr=0.3,0.1

Chan Stop Cuts=-1