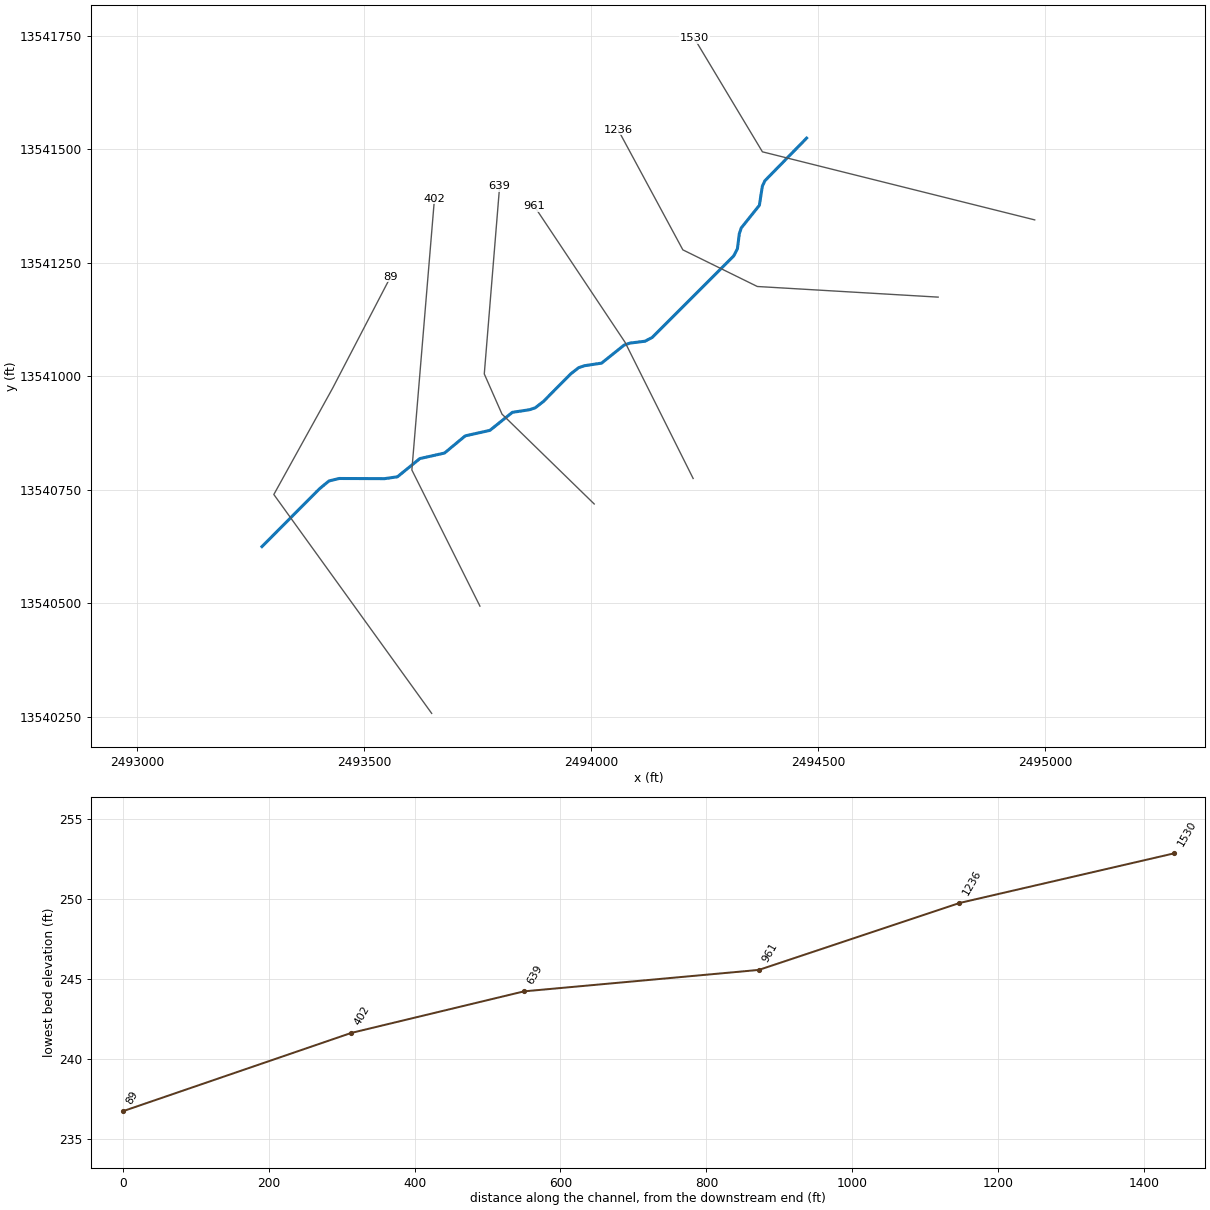
--- TRIB 12_1_1 TO TWELVEMILE CREEK.prj (project) ---

Proj Title=TRIB 12_1_1 TO TWELVEMILE CREEK Base Level Engineering
Current Plan=p01
Default Exp/Contr=0.3,0.1
English Units
Geom File=g01
Flow File=f01
Plan File=p01
Y Axis Title=Elevation
X Axis Title(PF)=Main Channel Distance
X Axis Title(XS)=Station
BEGIN DESCRIPTION:
TRIB 12_1_1 TO TWELVEMILE CREEK
END DESCRIPTION:
DSS Export Rating Curves= 0
DSS Export Rating Curve Sorted= 0
DSS Export Volume Flow Curves= 0
DXF OffsetX= 0
DXF OffsetY= 0
DXF ScaleX= 1
DXF ScaleY= 10

--- TRIB 12_1_1 TO TWELVEMILE CREEK.p01 (plan) ---

Plan Title=Multiple Run
Short Identifier=Multiple
Geom File=g01
Flow File=f01
Subcritical Flow
K Sum by GR= 0
Std Step Tol= 0.01
Critical Tol= 0.01
Num of Std Step Trials= 20
Max Error Tol= 0.3
Flow Tol Ratio= 0.001
Split Flow NTrial= 30
Split Flow Tol= 0.02
Split Flow Ratio= 0.02
Log Output Level= 0
Friction Slope Method= 1
Unsteady Friction Slope Method= 2
Unsteady Bridges Friction Slope Method= 1
Parabolic Critical Depth
Global Vel Dist=  1 , 1 , 1
Global Log Level= 0
CheckData=True
Encroach Param= -1, 0, 0, 0
BEGIN DESCRIPTION:
Multiple Run
END DESCRIPTION:

--- TRIB 12_1_1 TO TWELVEMILE CREEK.f01 (steady flow) ---

Flow Title=Multiple
Number of Profiles=7
Profile Names=10-year,25-year,50-year,1pct_min,100-year,1pct_plu,500-year
River Rch & RM= TRIB 12_1_1 TO T,Reach-1,1530
     461     731     972     627    1251    2496    2047
Boundary for River Rch & Prof#=TRIB 12_1_1 TO T,Reach-1,1
Up Type=0
Dn Type=3
Dn Slope=0.005
Boundary for River Rch & Prof#=TRIB 12_1_1 TO T,Reach-1,2
Up Type=0
Dn Type=3
Dn Slope=0.005
Boundary for River Rch & Prof#=TRIB 12_1_1 TO T,Reach-1,3
Up Type=0
Dn Type=3
Dn Slope=0.005
Boundary for River Rch & Prof#=TRIB 12_1_1 TO T,Reach-1,4
Up Type=0
Dn Type=3
Dn Slope=0.005
Boundary for River Rch & Prof#=TRIB 12_1_1 TO T,Reach-1,5
Up Type=0
Dn Type=3
Dn Slope=0.005
Boundary for River Rch & Prof#=TRIB 12_1_1 TO T,Reach-1,6
Up Type=0
Dn Type=3
Dn Slope=0.005
Boundary for River Rch & Prof#=TRIB 12_1_1 TO T,Reach-1,7
Up Type=0
Dn Type=3
Dn Slope=0.005

--- TRIB 12_1_1 TO TWELVEMILE CREEK.g01 (geometry) ---

Geom Title=Existing Conditions

River Reach=TRIB 12_1_1 TO T,Reach-1
Reach XY= 30
      2494475.00     13541525.00      2494383.09     13541431.08
      2494377.48     13541418.97      2494370.82     13541376.73
      2494331.10     13541327.19      2494326.70     13541314.30
      2494322.50     13541281.03      2494314.24     13541265.32
      2494134.68     13541085.76      2494118.96     13541077.50
      2494085.70     13541073.30      2494072.81     13541068.90
      2494023.27     13541029.19      2493985.63     13541023.49
      2493972.71     13541019.15      2493954.93     13541005.18
      2493895.07     13540944.82      2493877.29     13540930.85
      2493864.37     13540926.51      2493826.74     13540920.81
      2493777.20     13540881.08      2493722.80     13540868.92
      2493677.20     13540831.08      2493622.82     13540818.88
      2493573.44     13540778.76      2493545.14     13540774.67
      2493444.99     13540775.02      2493422.55     13540769.54
      2493401.47     13540752.15      2493275.00     13540625.00

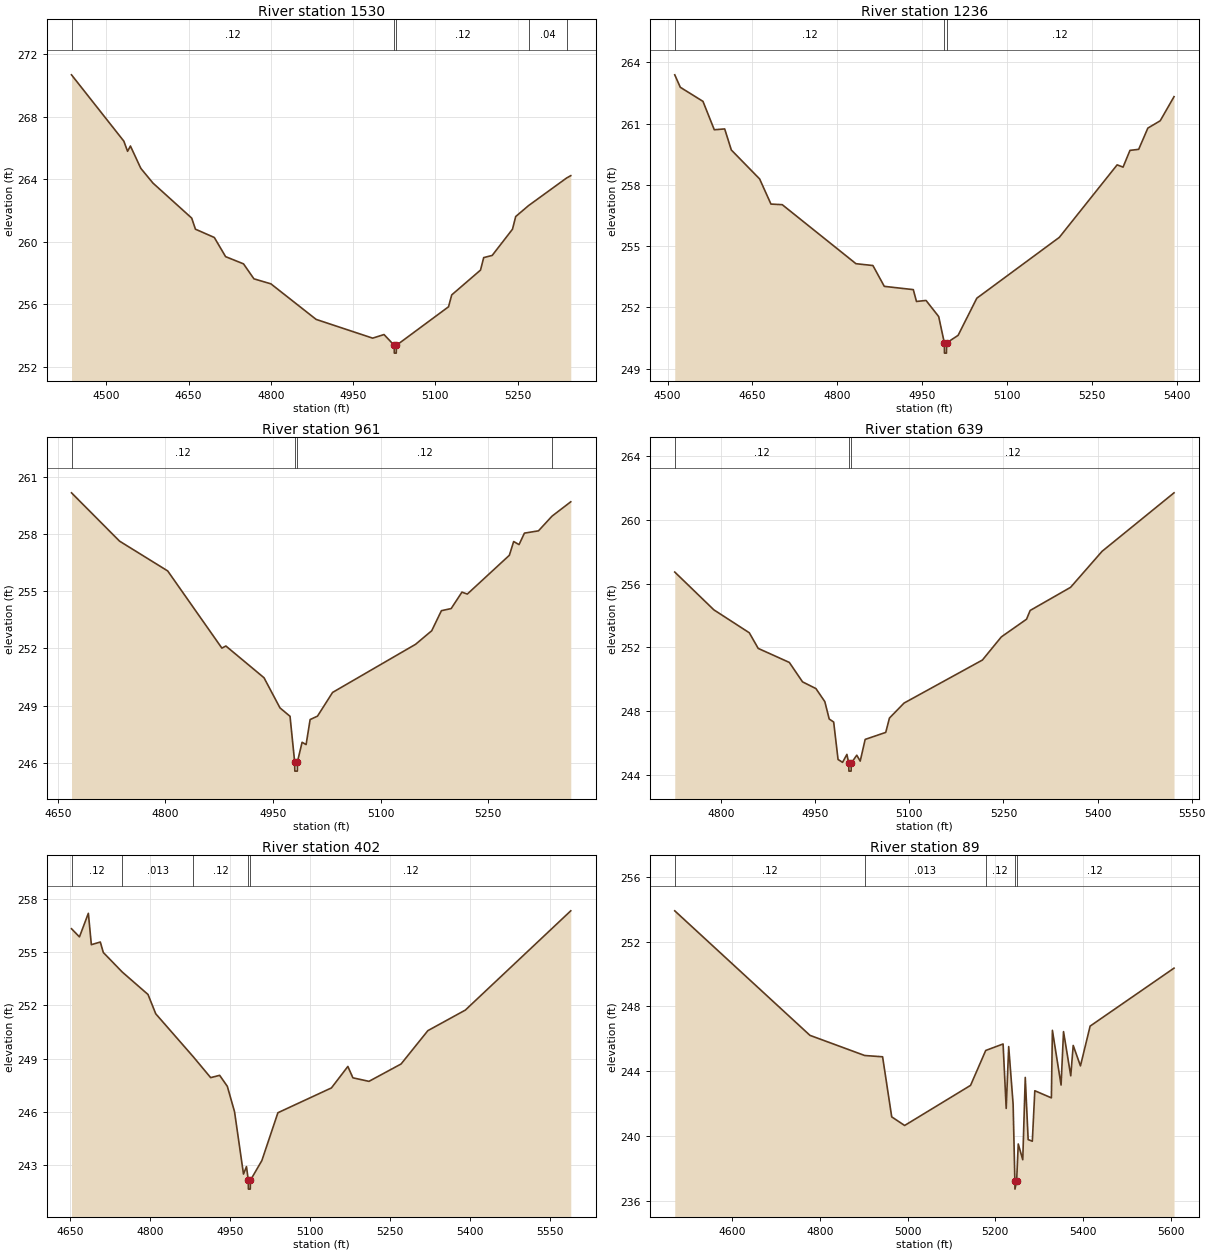
Type RM Length L Ch R = 1,1530,294,294,294
BEGIN DESCRIPTION:
TRIB 12_1-1 TO TWELVEMILE CREEK 3.0
END DESCRIPTION:
XS GIS Cut Line= 3
      2494977.56     13541344.80      2494377.60     13541494.79
      2494227.59     13541744.82
#Sta/Elev= 30
  4436.7  270.69  4532.1  266.44  4538.9  265.79  4544.1  266.13  4563.0  264.70
  4585.3  263.75  4655.8  261.51  4662.6  260.80  4697.0  260.27  4717.6  259.04
  4750.2  258.58  4769.2  257.62  4800.1  257.30  4882.6  255.02  4985.6  253.82
  5006.3  254.05  5024.9  253.36  5025.1  252.86  5028.6  252.86  5028.9  253.36
  5123.9  255.83  5129.7  256.59  5182.2  258.18  5188.0  258.98  5203.5  259.12
  5240.5  260.80  5246.3  261.61  5269.7  262.31  5339.1  264.08  5346.7  264.23
#Mann=5,-1,0
  4436.7    0.12       0  5024.9    0.05       0  5028.9    0.12       0
  5269.7    0.04       0  5339.1    0.03       0
Bank Sta=5024.9,5028.9
Exp/Cntr=0.3,0.1

Type RM Length L Ch R = 1,1236,275,275,275
BEGIN DESCRIPTION:
Mapping XS 451c046c
END DESCRIPTION:
XS GIS Cut Line= 4
      2494764.81     13541174.62      2494366.34     13541198.06
      2494202.28     13541278.79      2494059.52     13541543.54
#Sta/Elev= 30
  4512.8  263.39  4522.6  262.78  4562.7  262.09  4582.7  260.70  4601.1  260.74
  4612.8  259.71  4662.9  258.29  4682.9  257.06  4702.9  257.03  4833.2  254.14
  4863.2  254.05  4883.3  253.03  4934.6  252.87  4940.2  252.29  4957.1  252.34
  4979.5  251.55  4989.5  250.26  4989.7  249.76  4993.2  249.76  4993.5  250.26
  5013.8  250.63  5046.9  252.45  5192.8  255.43  5295.0  258.98  5305.5  258.87
  5317.7  259.69  5333.1  259.74  5349.3  260.78  5371.2  261.14  5395.6  262.32
#Mann=3,-1,0
  4512.8    0.12       0  4989.5    0.05       0  4993.5    0.12       0
Bank Sta=4989.5,4993.5
Exp/Cntr=0.3,0.1

Type RM Length L Ch R = 1,961,322,322,322
BEGIN DESCRIPTION:
TRIB 12_1-1 TO TWELVEMILE CREEK 2.0
END DESCRIPTION:
XS GIS Cut Line= 3
      2494224.98     13540775.04      2494075.00     13541075.00
      2493875.01     13541374.98
#Sta/Elev= 30
  4669.2  260.15  4736.2  257.62  4803.3  256.06  4878.8  252.02  4884.4  252.13
  4937.5  250.47  4959.8  248.89  4973.8  248.45  4980.2  246.08  4980.5  245.58
  4984.0  245.58  4984.2  246.08  4990.6  247.09  4996.2  246.97  5001.8  248.28
  5012.1  248.46  5033.1  249.70  5148.8  252.22  5171.3  252.93  5184.8  253.98
  5198.4  254.09  5213.4  254.95  5220.9  254.85  5279.5  256.88  5285.5  257.60
  5293.0  257.44  5300.5  258.04  5320.1  258.16  5339.0  258.93  5365.1  259.68
#Mann=4,-1,0
  4669.2    0.12       0  4980.2    0.05       0  4984.2    0.12       0
  5339.0    0.05       0
Bank Sta=4980.2,4984.2
Exp/Cntr=0.3,0.1

Type RM Length L Ch R = 1,639,237,237,237
BEGIN DESCRIPTION:
Mapping XS d6beb70d
END DESCRIPTION:
XS GIS Cut Line= 4
      2494006.98     13540718.87      2493803.84     13540916.81
      2493764.78     13541005.35      2493798.63     13541419.36
#Sta/Elev= 30
  4726.1  256.73  4788.4  254.36  4844.9  252.92  4859.1  251.94  4908.7  251.06
  4929.8  249.84  4951.1  249.42  4965.3  248.60  4972.3  247.51  4979.4  247.32
  4986.4  244.97  4993.6  244.79  5000.5  245.29  5003.4  244.74  5003.7  244.24
  5007.2  244.24  5007.4  244.74  5016.2  245.24  5021.7  244.87  5029.6  246.23
  5062.4  246.67  5068.3  247.57  5091.6  248.51  5216.5  251.21  5246.6  252.66
  5286.8  253.77  5292.6  254.32  5357.0  255.77  5407.2  258.03  5521.9  261.70
#Mann=3,-1,0
  4726.1    0.12       0  5003.4    0.05       0  5007.4    0.12       0
Bank Sta=5003.4,5007.4
Exp/Cntr=0.3,0.1

Type RM Length L Ch R = 1,402,313,313,313
BEGIN DESCRIPTION:
TRIB 12_1-1 TO TWELVEMILE CREEK 1.0
END DESCRIPTION:
XS GIS Cut Line= 3
      2493755.19     13540493.79      2493605.21     13540793.75
      2493655.06     13541391.91
#Sta/Elev= 30
  4652.6  256.33  4667.5  255.87  4684.2  257.20  4689.8  255.43  4706.6  255.58
  4712.2  254.99  4747.6  253.89  4796.0  252.62  4810.5  251.53  4881.0  249.10
  4913.4  247.93  4930.2  248.06  4944.6  247.44  4958.1  246.01  4974.9  242.49
  4980.5  242.91  4983.9  242.14  4984.1  241.64  4987.6  241.64  4987.9  242.14
  5009.3  243.25  5039.4  245.95  5139.7  247.35  5170.5  248.56  5179.9  247.92
  5210.0  247.72  5270.2  248.70  5320.4  250.58  5390.6  251.74  5588.2  257.34
#Mann=5,-1,0
  4652.6    0.12       0  4747.6   0.013       0  4881.0    0.12       0
  4983.9    0.05       0  4987.9    0.12       0
Bank Sta=4983.9,4987.9
Exp/Cntr=0.3,0.1

Type RM Length L Ch R = 1,89,0,0,0
BEGIN DESCRIPTION:
TRIB 12_1-1 TO TWELVEMILE CREEK 0.5
END DESCRIPTION:
XS GIS Cut Line= 4
      2493648.85     13540257.50      2493301.09     13540739.73
      2493430.66     13540974.02      2493558.41     13541219.60
#Sta/Elev= 30
  4468.9  253.89  4777.4  246.22  4902.2  244.98  4943.1  244.90  4963.9  241.20
  4993.4  240.67  5143.8  243.14  5178.4  245.29  5218.0  245.69  5225.1  241.72
  5230.8  245.53  5240.9  241.98  5244.9  237.25  5245.1  236.75  5248.9  237.25
  5252.6  239.53  5262.9  238.56  5268.6  243.63  5275.2  239.80  5284.7  239.70
  5290.4  242.81  5328.2  242.37  5330.5  246.53  5350.3  243.16  5355.9  246.45
  5372.4  243.73  5378.0  245.60  5394.5  244.34  5416.6  246.79  5608.0  250.36
#Mann=5,-1,0
  4468.9    0.12       0  4902.2   0.013       0  5178.4    0.12       0
  5244.9    0.03       0  5248.9    0.12       0
Bank Sta=5244.9,5248.9
Exp/Cntr=0.3,0.1

Chan Stop Cuts=-1