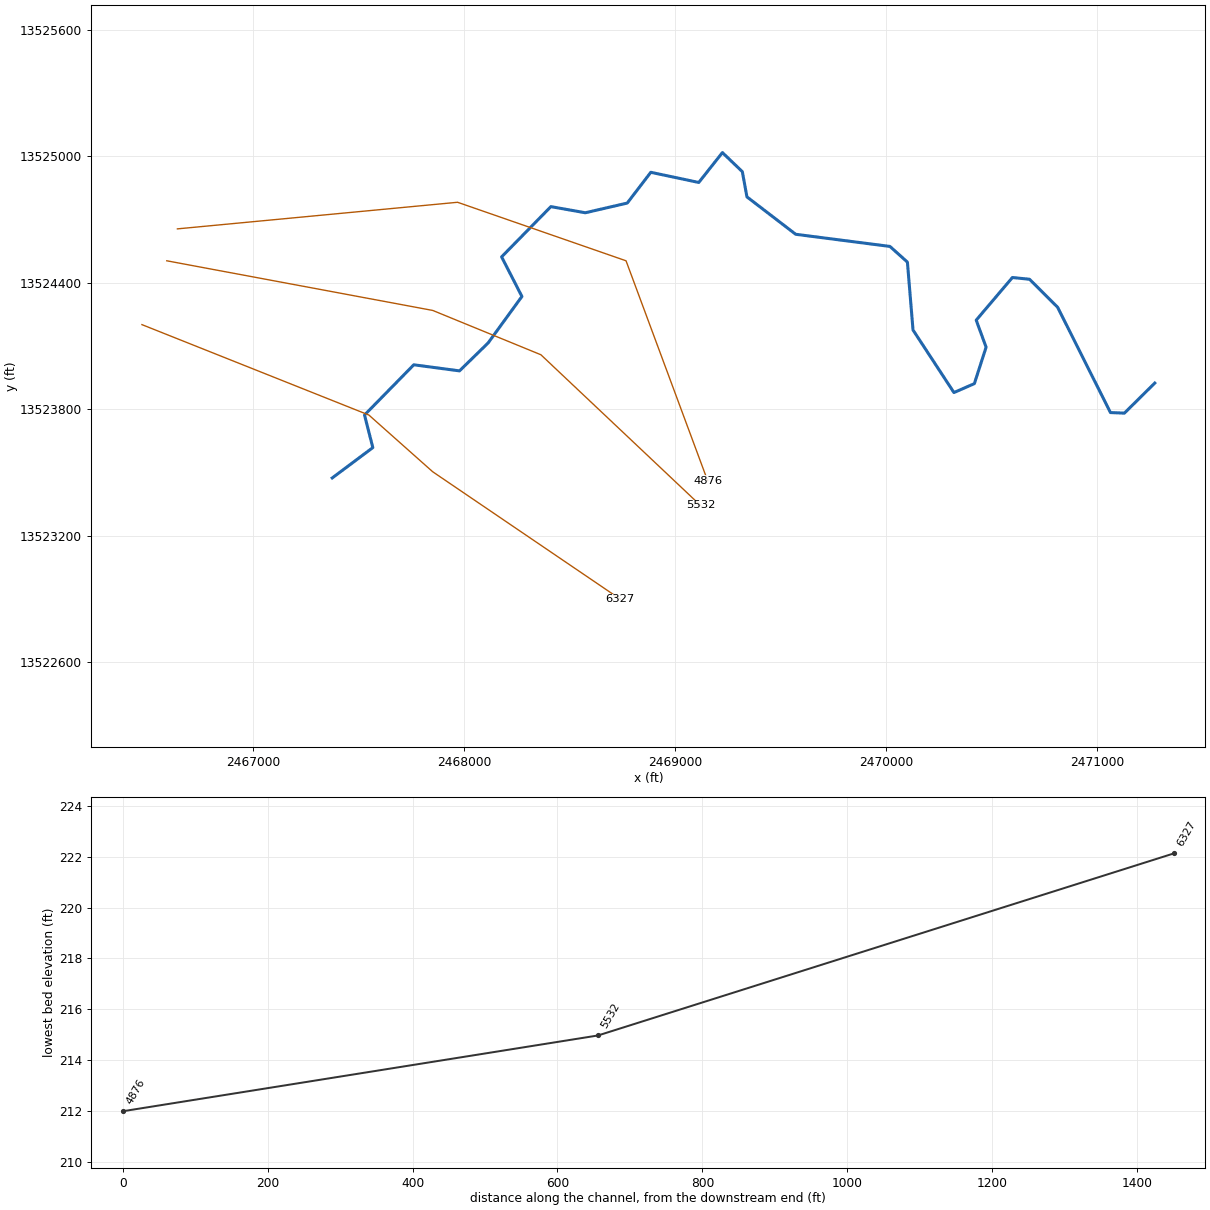
--- TRIB 13 TO FIFTEENMILE CREEK.prj (project) ---

Proj Title=TRIB 13 TO FIFTEENMILE CREEK Base Level Engineering
Current Plan=p01
Default Exp/Contr=0.3,0.1
English Units
Geom File=g01
Flow File=f01
Plan File=p01
Y Axis Title=Elevation
X Axis Title(PF)=Main Channel Distance
X Axis Title(XS)=Station
BEGIN DESCRIPTION:
TRIB 13 TO FIFTEENMILE CREEK
END DESCRIPTION:
DSS Export Rating Curves= 0
DSS Export Rating Curve Sorted= 0
DSS Export Volume Flow Curves= 0
DXF OffsetX= 0
DXF OffsetY= 0
DXF ScaleX= 1
DXF ScaleY= 10

--- TRIB 13 TO FIFTEENMILE CREEK.p01 (plan) ---

Plan Title=Multiple Run
Short Identifier=Multiple
Geom File=g01
Flow File=f01
Subcritical Flow
K Sum by GR= 0
Std Step Tol= 0.01
Critical Tol= 0.01
Num of Std Step Trials= 20
Max Error Tol= 0.3
Flow Tol Ratio= 0.001
Split Flow NTrial= 30
Split Flow Tol= 0.02
Split Flow Ratio= 0.02
Log Output Level= 0
Friction Slope Method= 1
Unsteady Friction Slope Method= 2
Unsteady Bridges Friction Slope Method= 1
Parabolic Critical Depth
Global Vel Dist=  1 , 1 , 1
Global Log Level= 0
CheckData=True
Encroach Param= -1, 0, 0, 0
BEGIN DESCRIPTION:
Multiple Run
END DESCRIPTION:

--- TRIB 13 TO FIFTEENMILE CREEK.f01 (steady flow) ---

Flow Title=Multiple
Number of Profiles=7
Profile Names=10-year,25-year,50-year,1pct_min,100-year,1pct_plu,500-year
River Rch & RM= TRIB 13 TO FIFTE,Reach-1,6327
     779    1277    1733    1139    2272    4533    3865
Boundary for River Rch & Prof#=TRIB 13 TO FIFTE,Reach-1,1
Up Type=0
Dn Type=3
Dn Slope=0.005
Boundary for River Rch & Prof#=TRIB 13 TO FIFTE,Reach-1,2
Up Type=0
Dn Type=3
Dn Slope=0.005
Boundary for River Rch & Prof#=TRIB 13 TO FIFTE,Reach-1,3
Up Type=0
Dn Type=3
Dn Slope=0.005
Boundary for River Rch & Prof#=TRIB 13 TO FIFTE,Reach-1,4
Up Type=0
Dn Type=3
Dn Slope=0.005
Boundary for River Rch & Prof#=TRIB 13 TO FIFTE,Reach-1,5
Up Type=0
Dn Type=3
Dn Slope=0.005
Boundary for River Rch & Prof#=TRIB 13 TO FIFTE,Reach-1,6
Up Type=0
Dn Type=3
Dn Slope=0.005
Boundary for River Rch & Prof#=TRIB 13 TO FIFTE,Reach-1,7
Up Type=0
Dn Type=3
Dn Slope=0.005

--- TRIB 13 TO FIFTEENMILE CREEK.g01 (geometry) ---

Geom Title=Existing Conditions

River Reach=TRIB 13 TO FIFTE,Reach-1
Reach XY= 30
      2467375.00     13523475.00      2467567.52     13523618.93
      2467528.13     13523773.37      2467761.68     13524011.63
      2467978.42     13523982.79      2468114.22     13524115.32
      2468274.45     13524335.64      2468178.10     13524523.35
      2468411.70     13524761.66      2468575.00     13524732.56
      2468773.75     13524778.46      2468885.49     13524924.42
      2469112.97     13524876.22      2469225.00     13525017.94
      2469319.47     13524927.45      2469341.30     13524807.87
      2469572.57     13524630.52      2470019.16     13524572.95
      2470102.16     13524498.59      2470128.75     13524176.55
      2470322.72     13523880.05      2470419.58     13523922.25
      2470475.28     13524095.18      2470428.34     13524223.28
      2470599.96     13524425.51      2470681.17     13524417.24
      2470814.25     13524284.69      2471064.95     13523785.02
      2471131.03     13523782.44      2471275.00     13523925.00

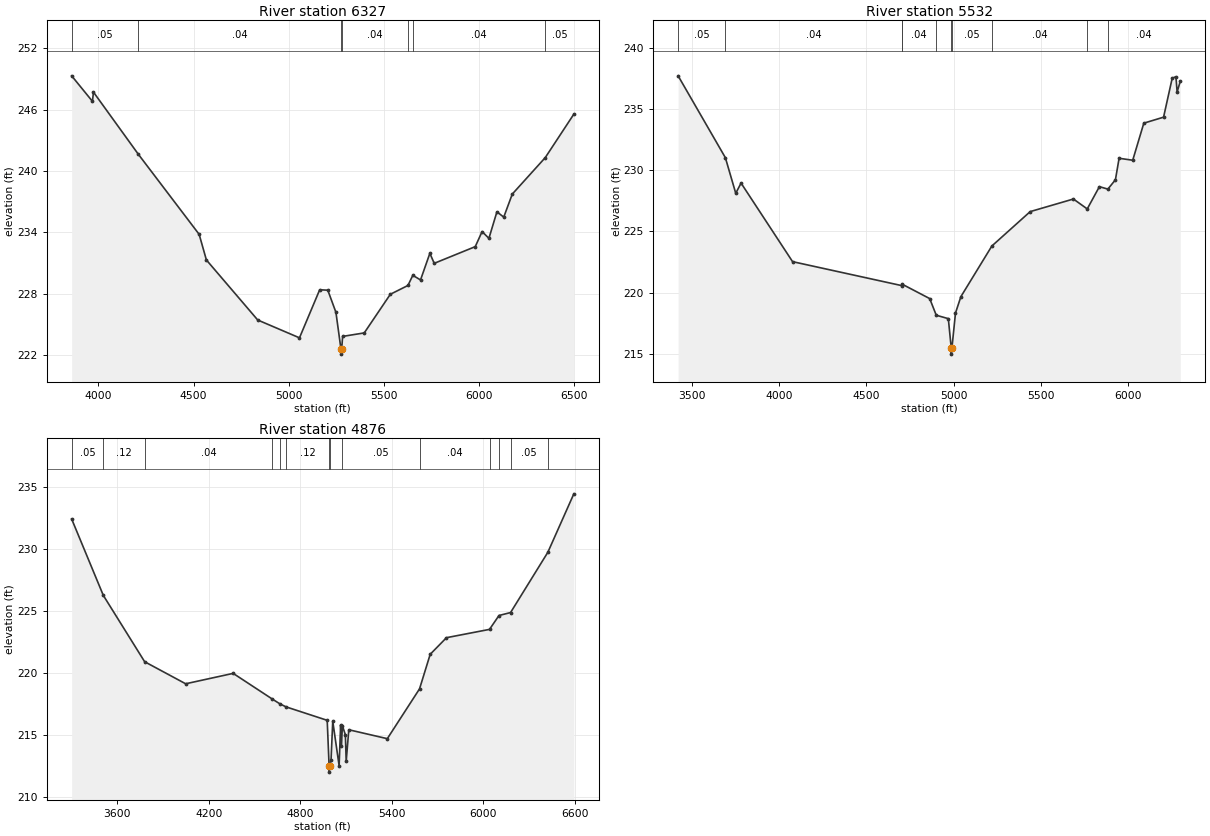
Type RM Length L Ch R = 1,6327,795,795,795
BEGIN DESCRIPTION:
LGII4662
END DESCRIPTION:
XS GIS Cut Line= 4
      2466472.77     13524202.13      2467548.95     13523773.34
      2467851.63     13523504.29      2468740.62     13522900.45
#Sta/Elev= 30
  3859.9  249.29  3969.1  246.80  3974.5  247.70  4210.0  241.64  4529.7  233.82
  4567.7  231.32  4837.4  225.46  5056.7  223.72  5162.9  228.41  5205.5  228.37
  5248.2  226.21  5274.6  222.63  5274.9  222.13  5278.6  222.63  5283.3  223.86
  5397.0  224.20  5534.0  227.97  5626.5  228.83  5652.1  229.82  5692.6  229.37
  5741.7  231.97  5764.5  230.99  5980.1  232.62  6016.0  234.09  6051.9  233.43
  6093.9  236.02  6129.8  235.50  6174.7  237.75  6347.9  241.31  6498.0  245.55
#Mann=7,-1,0
  3859.9    0.05       0  4210.0    0.04       0  5274.6    0.04       0
  5278.6    0.04       0  5626.5    0.05       0  5652.1    0.04       0
  6347.9    0.05       0
Bank Sta=5274.6,5278.6
Exp/Cntr=0.3,0.1

Type RM Length L Ch R = 1,5532,656,656,656
BEGIN DESCRIPTION:
LGII4661
END DESCRIPTION:
XS GIS Cut Line= 4
      2466590.45     13524504.82      2467851.63     13524269.40
      2468364.51     13524059.21      2469120.64     13523345.08
#Sta/Elev= 30
  3420.9  237.72  3691.6  231.03  3751.1  228.12  3781.6  228.95  4076.6  222.53
  4702.4  220.57  4705.5  220.68  4862.4  219.51  4899.9  218.15  4969.1  217.87
  4985.7  215.47  4986.0  214.97  4989.7  215.47  5010.1  218.33  5041.1  219.67
  5218.6  223.81  5438.1  226.62  5685.7  227.65  5765.0  226.84  5834.6  228.66
  5883.1  228.46  5926.4  229.22  5947.5  230.98  6025.6  230.82  6089.1  233.85
  6202.3  234.34  6251.7  237.52  6273.1  237.65  6280.0  236.40  6298.2  237.28
#Mann=10,-1,0
  3420.9    0.05       0  3691.6    0.04       0  4702.4    0.03       0
  4705.5    0.04       0  4899.9    0.05       0  4985.7    0.05       0
  4989.7    0.05       0  5218.6    0.04       0  5765.0    0.05       0
  5883.1    0.04       0
Bank Sta=4985.7,4989.7
Exp/Cntr=0.3,0.1

Type RM Length L Ch R = 1,4876,0,0,0
BEGIN DESCRIPTION:
LGII4660
END DESCRIPTION:
XS GIS Cut Line= 4
      2466640.91     13524656.16      2467969.34     13524782.28
      2468768.09     13524504.82      2469154.86     13523462.22
#Sta/Elev= 30
  3301.9  232.42  3509.6  226.25  3780.4  220.90  4049.3  219.12  4360.7  219.96
  4618.1  217.88  4665.8  217.51  4706.5  217.26  4977.1  216.17  4989.6  212.49
  4989.9  211.99  4993.6  212.49  5002.2  212.93  5013.5  216.10  5055.2  212.51
  5065.2  215.80  5070.5  214.08  5076.6  215.74  5096.3  215.00  5101.6  212.86
  5118.7  215.41  5371.1  214.69  5582.4  218.71  5652.3  221.50  5759.0  222.84
  6041.1  223.51  6103.2  224.63  6179.2  224.87  6423.4  229.73  6593.9  234.45
#Mann=14,-1,0
  3301.9    0.05       0  3509.6    0.12       0  3780.4    0.04       0
  4618.1    0.05       0  4665.8    0.04       0  4706.5    0.12       0
  4989.6    0.05       0  4993.6    0.12       0  5076.6    0.05       0
  5582.4    0.04       0  6041.1    0.05       0  6103.2    0.04       0
  6179.2    0.05       0  6423.4    0.04       0
Bank Sta=4989.6,4993.6
Exp/Cntr=0.3,0.1

Chan Stop Cuts=-1