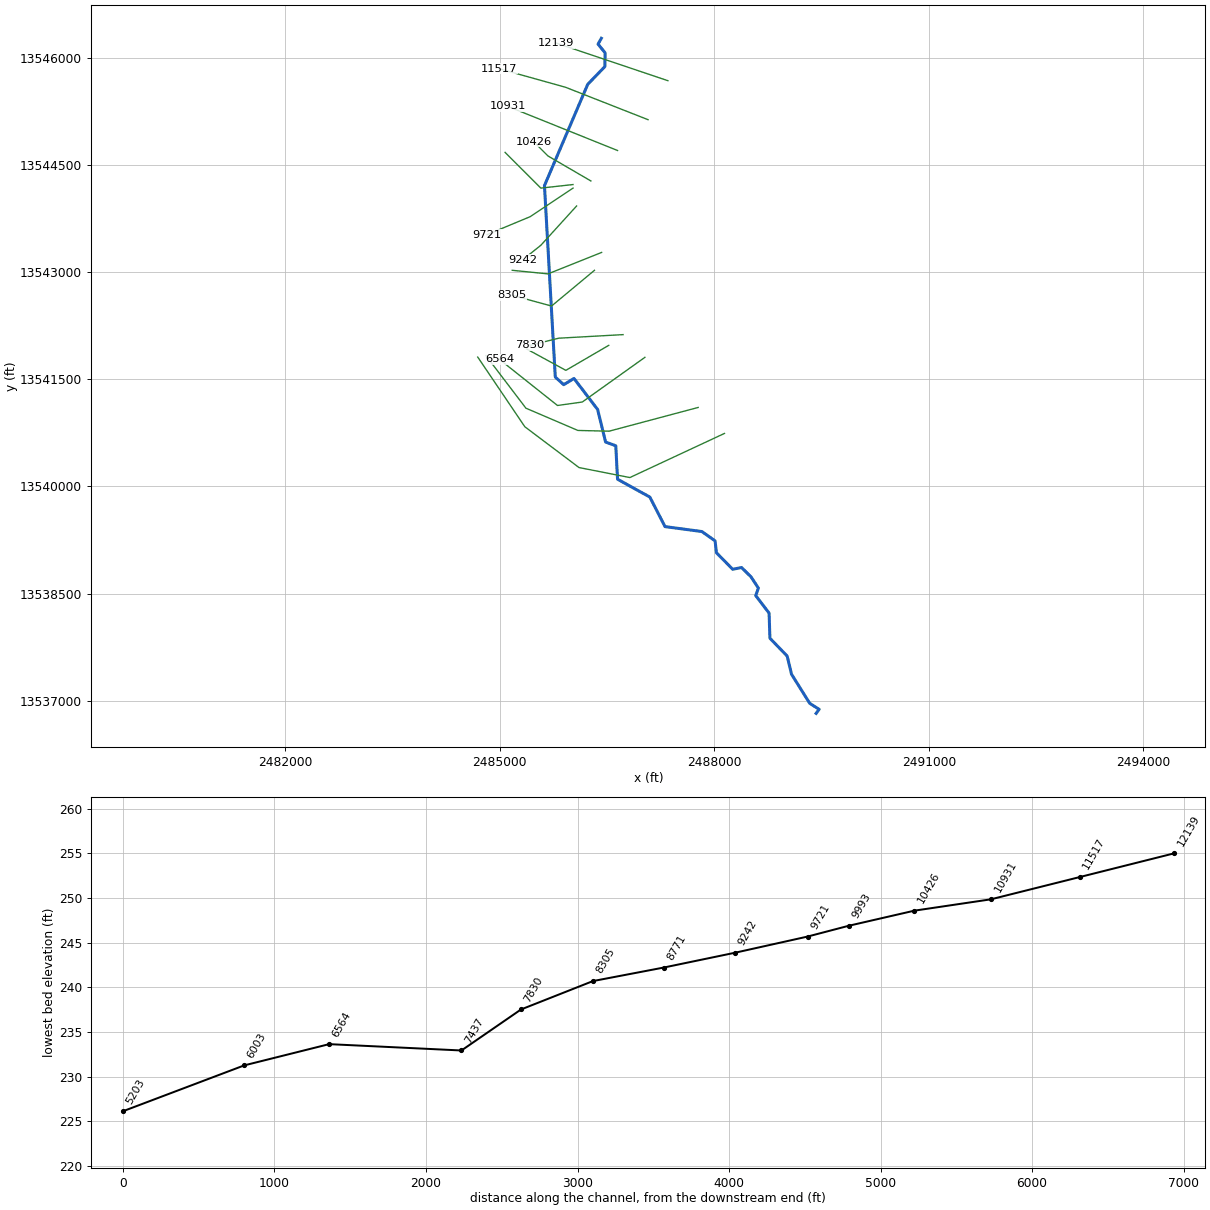
--- TRIB 13 TO TWELVEMILE CREEK.prj (project) ---

Proj Title=TRIB 13 TO TWELVEMILE CREEK Base Level Engineering
Current Plan=p01
Default Exp/Contr=0.3,0.1
English Units
Geom File=g01
Flow File=f01
Plan File=p01
Y Axis Title=Elevation
X Axis Title(PF)=Main Channel Distance
X Axis Title(XS)=Station
BEGIN DESCRIPTION:
TRIB 13 TO TWELVEMILE CREEK
END DESCRIPTION:
DSS Export Rating Curves= 0
DSS Export Rating Curve Sorted= 0
DSS Export Volume Flow Curves= 0
DXF OffsetX= 0
DXF OffsetY= 0
DXF ScaleX= 1
DXF ScaleY= 10

--- TRIB 13 TO TWELVEMILE CREEK.p01 (plan) ---

Plan Title=Multiple Run
Short Identifier=Multiple
Geom File=g01
Flow File=f01
Subcritical Flow
K Sum by GR= 0
Std Step Tol= 0.01
Critical Tol= 0.01
Num of Std Step Trials= 20
Max Error Tol= 0.3
Flow Tol Ratio= 0.001
Split Flow NTrial= 30
Split Flow Tol= 0.02
Split Flow Ratio= 0.02
Log Output Level= 0
Friction Slope Method= 1
Unsteady Friction Slope Method= 2
Unsteady Bridges Friction Slope Method= 1
Parabolic Critical Depth
Global Vel Dist=  1 , 1 , 1
Global Log Level= 0
CheckData=True
Encroach Param= -1, 0, 0, 0
BEGIN DESCRIPTION:
Multiple Run
END DESCRIPTION:

--- TRIB 13 TO TWELVEMILE CREEK.f01 (steady flow) ---

Flow Title=Multiple
Number of Profiles=7
Profile Names=10-year,25-year,50-year,1pct_min,100-year,1pct_plu,500-year
River Rch & RM= TRIB 13 TO TWELV,Reach-1,12139
     652    1045    1396     902    1800    3592    2962
River Rch & RM= TRIB 13 TO TWELV,Reach-1,10931
     846    1375    1855    1210    2414    4817    4048
River Rch & RM= TRIB 13 TO TWELV,Reach-1,8771
    1036    1702    2312    1517    3026    6038    5135
River Rch & RM= TRIB 13 TO TWELV,Reach-1,5203
    1170    1930    2628    1728    3448    6879    5875
Boundary for River Rch & Prof#=TRIB 13 TO TWELV,Reach-1,1
Up Type=0
Dn Type=3
Dn Slope=0.005
Boundary for River Rch & Prof#=TRIB 13 TO TWELV,Reach-1,2
Up Type=0
Dn Type=3
Dn Slope=0.005
Boundary for River Rch & Prof#=TRIB 13 TO TWELV,Reach-1,3
Up Type=0
Dn Type=3
Dn Slope=0.005
Boundary for River Rch & Prof#=TRIB 13 TO TWELV,Reach-1,4
Up Type=0
Dn Type=3
Dn Slope=0.005
Boundary for River Rch & Prof#=TRIB 13 TO TWELV,Reach-1,5
Up Type=0
Dn Type=3
Dn Slope=0.005
Boundary for River Rch & Prof#=TRIB 13 TO TWELV,Reach-1,6
Up Type=0
Dn Type=3
Dn Slope=0.005
Boundary for River Rch & Prof#=TRIB 13 TO TWELV,Reach-1,7
Up Type=0
Dn Type=3
Dn Slope=0.005

--- TRIB 13 TO TWELVEMILE CREEK.g01 (geometry) ---

Geom Title=Existing Conditions

River Reach=TRIB 13 TO TWELV,Reach-1
Reach XY= 30
      2486420.98     13546270.98      2486374.82     13546190.24
      2486472.94     13546069.14      2486471.25     13545876.55
      2486230.73     13545627.55      2485625.52     13544209.78
      2485777.05     13541530.84      2485895.16     13541424.53
      2486038.34     13541511.59      2486369.17     13541077.30
      2486480.52     13540622.03      2486622.93     13540569.54
      2486647.82     13540101.42      2487099.36     13539851.98
      2487311.31     13539438.50      2487827.52     13539369.26
      2488011.79     13539238.73      2488030.47     13539072.55
      2488258.33     13538841.23      2488382.00     13538865.92
      2488514.30     13538734.97      2488617.17     13538578.40
      2488580.12     13538472.71      2488766.93     13538228.31
      2488778.54     13537876.46      2489019.53     13537627.45
      2489080.84     13537372.71      2489335.64     13536965.00
      2489466.38     13536882.04      2489425.00     13536825.00

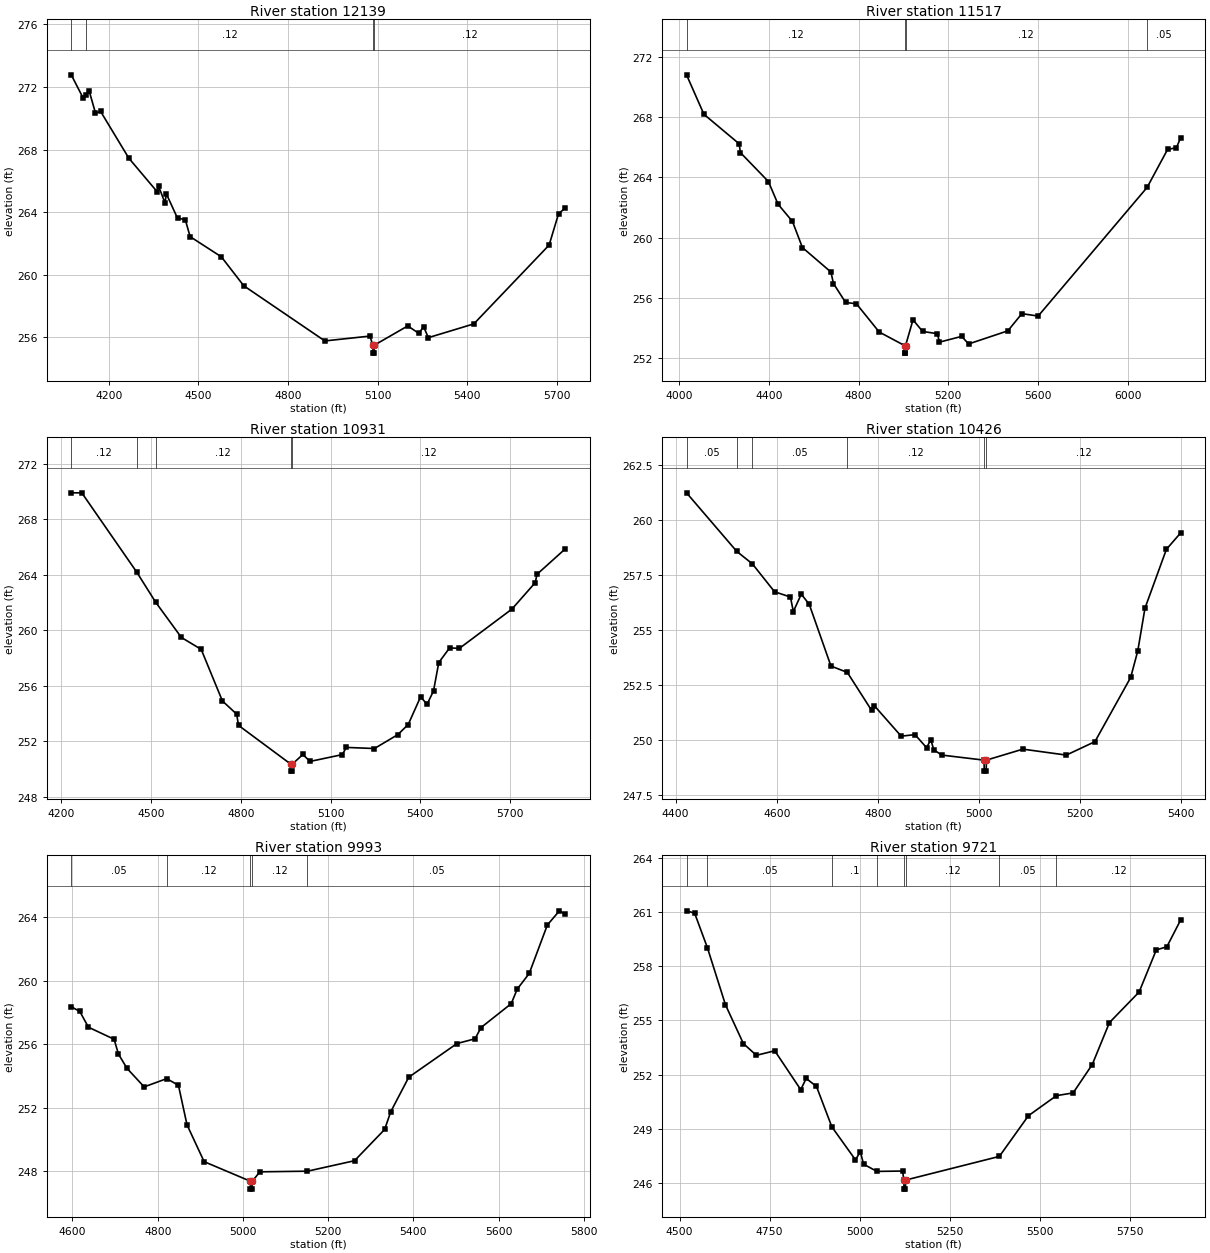
Type RM Length L Ch R = 1,12139,622,622,622
BEGIN DESCRIPTION:
LGII4578
END DESCRIPTION:
XS GIS Cut Line= 2
      2487351.89     13545678.24      2485785.11     13546206.37
#Sta/Elev= 30
  4074.8  272.78  4115.3  271.27  4125.1  271.47  4134.8  271.75  4155.9  270.33
  4173.0  270.44  4267.4  267.45  4361.9  265.31  4367.2  265.65  4388.1  264.60
  4393.4  265.15  4430.3  263.61  4456.3  263.52  4472.5  262.43  4577.0  261.14
  4651.9  259.29  4923.3  255.76  5074.0  256.07  5084.0  255.48  5084.2  254.98
  5087.7  254.98  5088.0  255.48  5200.7  256.72  5238.1  256.24  5253.4  256.68
  5269.6  255.97  5421.7  256.85  5673.6  261.89  5705.1  263.89  5728.2  264.28
#Mann=4,-1,0
  4074.8   0.035       0  4125.1    0.12       0  5084.0    0.05       0
  5088.0    0.12       0
Bank Sta=5084,5088
Exp/Cntr=0.3,0.1

Type RM Length L Ch R = 1,11517,586,586,586
BEGIN DESCRIPTION:
LGII4577
END DESCRIPTION:
XS GIS Cut Line= 3
      2487074.56     13545132.55      2485921.54     13545585.84
      2484992.98     13545845.49
#Sta/Elev= 30
  4033.0  270.80  4110.6  268.18  4267.8  266.22  4273.1  265.64  4397.9  263.72
  4441.1  262.21  4505.3  261.07  4549.5  259.34  4676.9  257.71  4688.0  256.95
  4741.9  255.70  4790.7  255.60  4892.1  253.73  5005.5  252.83  5005.7  252.33
  5009.2  252.33  5009.5  252.83  5042.6  254.54  5085.5  253.77  5151.0  253.62
  5160.7  253.06  5259.4  253.44  5290.8  252.94  5465.6  253.81  5527.9  254.95
  5600.6  254.79  6086.4  263.33  6177.7  265.85  6217.1  265.96  6236.1  266.64
#Mann=4,-1,0
  4033.0    0.12       0  5005.5    0.05       0  5009.5    0.12       0
  6086.4    0.05       0
Bank Sta=5005.5,5009.5
Exp/Cntr=0.3,0.1

Type RM Length L Ch R = 1,10931,505,505,505
BEGIN DESCRIPTION:
LGII4576
END DESCRIPTION:
XS GIS Cut Line= 2
      2486647.70     13544701.25      2485116.19     13545317.37
#Sta/Elev= 30
  4233.9  269.91  4269.1  269.91  4452.4  264.20  4515.6  262.03  4601.8  259.48
  4668.0  258.62  4738.8  254.90  4786.5  253.95  4792.6  253.14  4967.5  250.34
  4967.8  249.84  4971.7  249.84  4972.1  250.34  5007.5  251.04  5031.7  250.54
  5139.2  251.03  5153.0  251.55  5246.7  251.47  5324.6  252.47  5359.5  253.20
  5400.9  255.20  5422.5  254.66  5444.0  255.62  5461.6  257.67  5497.9  258.73
  5530.3  258.69  5706.2  261.53  5784.1  263.44  5789.5  264.03  5884.7  265.88
#Mann=5,-1,0
  4233.9    0.12       0  4452.4    0.05       0  4515.6    0.12       0
  4967.5    0.05       0  4972.1    0.12       0
Bank Sta=4967.5,4972.1
Exp/Cntr=0.3,0.1

Type RM Length L Ch R = 1,10426,433,433,433
BEGIN DESCRIPTION:
TRIB 13 TO TWELVEMILE CREEK 9.0
END DESCRIPTION:
XS GIS Cut Line= 3
      2486275.00     13544275.00      2485675.00     13544625.00
      2485474.98     13544825.02
#Sta/Elev= 30
  4421.6  261.23  4520.8  258.57  4551.8  258.00  4595.7  256.73  4627.1  256.49
  4632.9  255.83  4648.6  256.62  4664.3  256.16  4707.3  253.35  4739.7  253.06
  4787.5  251.34  4793.3  251.54  4846.2  250.16  4873.5  250.23  4896.3  249.64
  4904.9  249.99  4910.7  249.54  4926.4  249.30  5010.1  249.07  5010.5  248.57
  5014.4  248.57  5014.7  249.07  5086.9  249.57  5172.8  249.30  5229.4  249.91
  5300.1  252.83  5314.2  254.04  5328.4  255.98  5370.8  258.66  5399.1  259.41
#Mann=6,-1,0
  4421.6    0.05       0  4520.8    0.12       0  4551.8    0.05       0
  4739.7    0.12       0  5010.1    0.05       0  5014.7    0.12       0
Bank Sta=5010.1,5014.7
Exp/Cntr=0.3,0.1

Type RM Length L Ch R = 1,9993,272,272,272
BEGIN DESCRIPTION:
TRIB 13 TO TWELVEMILE CREEK 8.0
END DESCRIPTION:
XS GIS Cut Line= 3
      2486025.02     13544225.00      2485575.00     13544175.00
      2485075.00     13544675.00
#Sta/Elev= 30
  4597.1  258.37  4617.2  258.07  4637.4  257.08  4697.7  256.32  4707.8  255.39
  4727.9  254.49  4768.2  253.32  4821.2  253.84  4848.7  253.42  4868.8  250.93
  4909.0  248.61  5017.4  247.38  5017.7  246.88  5021.7  246.88  5022.1  247.38
  5039.8  247.97  5151.6  248.01  5262.0  248.67  5332.7  250.64  5346.9  251.75
  5389.3  253.93  5502.4  256.05  5544.9  256.35  5559.0  257.06  5629.7  258.56
  5643.9  259.48  5672.1  260.47  5714.6  263.52  5742.9  264.41  5757.0  264.19
#Mann=5,-1,0
  4597.1    0.05       0  4821.2    0.12       0  5017.4    0.05       0
  5022.1    0.12       0  5151.6    0.05       0
Bank Sta=5017.4,5022.1
Exp/Cntr=0.3,0.1

Type RM Length L Ch R = 1,9721,479,479,479
BEGIN DESCRIPTION:
TRIB 13 TO TWELVEMILE CREEK 7.0
END DESCRIPTION:
XS GIS Cut Line= 3
      2486024.97     13544174.98      2485425.00     13543775.00
      2484824.97     13543524.99
#Sta/Elev= 30
  4519.3  261.06  4541.8  260.93  4577.4  259.01  4627.4  255.86  4677.0  253.72
  4713.1  253.07  4764.1  253.32  4836.2  251.17  4851.3  251.79  4879.8  251.35
  4922.6  249.11  4988.0  247.29  5001.5  247.74  5010.5  247.05  5047.5  246.65
  5118.7  246.67  5122.3  246.17  5122.7  245.67  5126.7  245.67  5127.0  246.17
  5387.3  247.48  5467.9  249.73  5545.7  250.84  5591.9  250.99  5645.0  252.56
  5692.7  254.88  5775.0  256.57  5822.7  258.90  5851.9  259.07  5890.4  260.56
#Mann=8,-1,0
  4519.3    0.12       0  4577.4    0.05       0  4922.6     0.1       0
  5047.5    0.12       0  5122.3    0.05       0  5127.0    0.12       0
  5387.3    0.05       0  5545.7    0.12       0
Bank Sta=5122.3,5127
Exp/Cntr=0.3,0.1

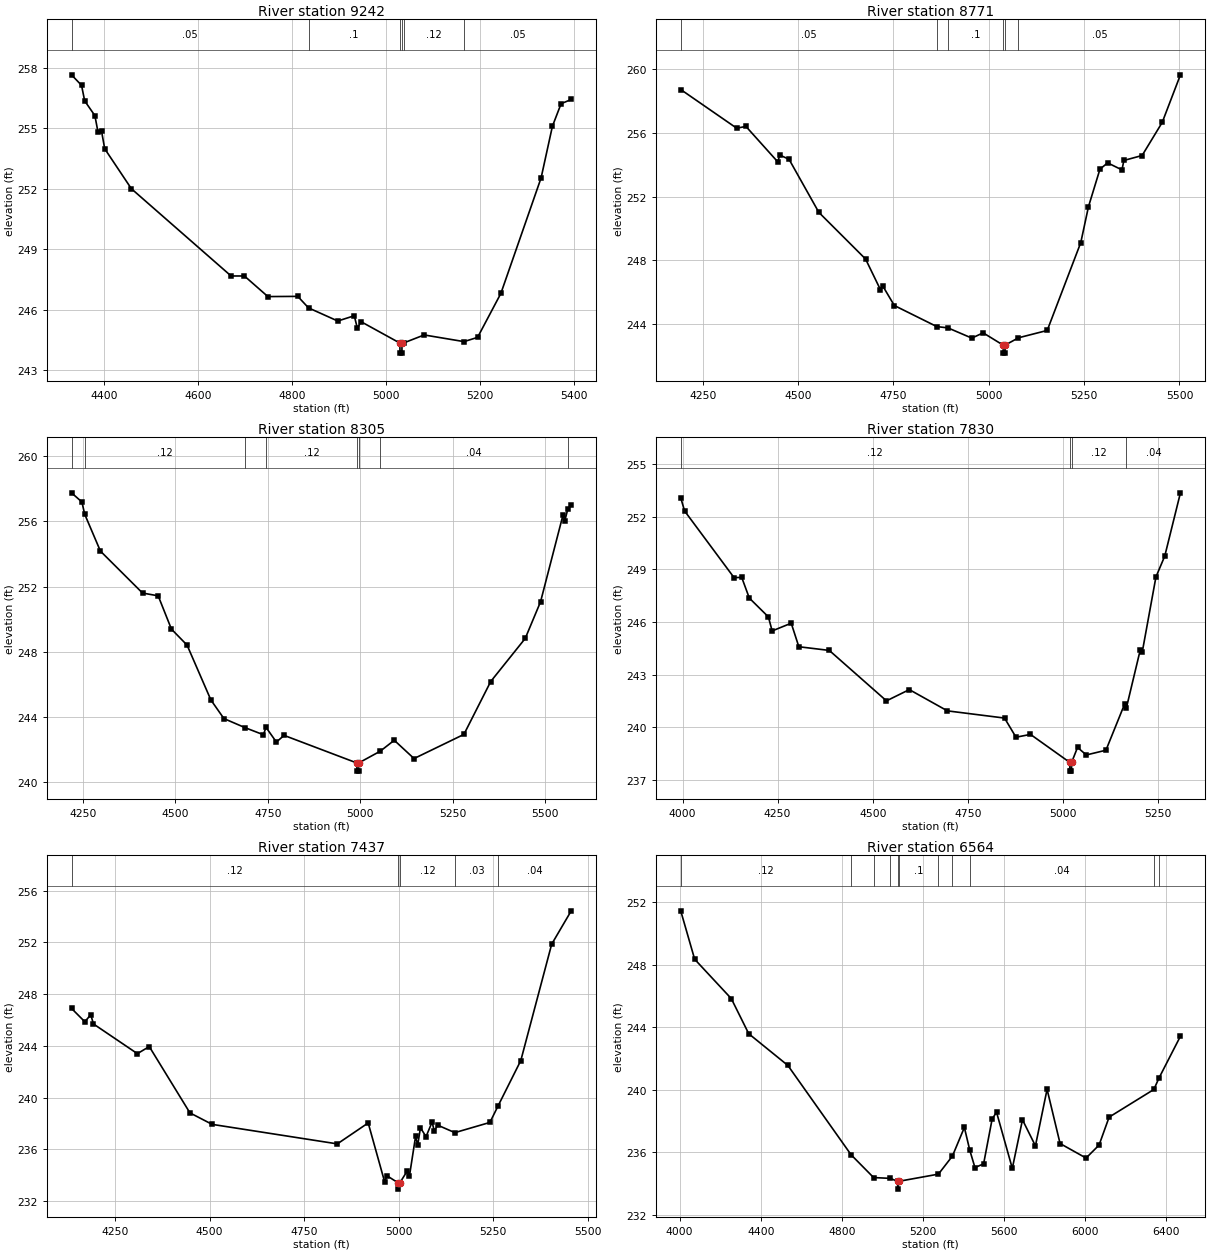
Type RM Length L Ch R = 1,9242,471,471,471
BEGIN DESCRIPTION:
TRIB 13 TO TWELVEMILE CREEK 6.0
END DESCRIPTION:
XS GIS Cut Line= 3
      2486075.00     13543925.00      2485575.00     13543375.00
      2485324.97     13543174.98
#Sta/Elev= 30
  4330.9  257.64  4352.2  257.12  4358.9  256.35  4380.6  255.62  4387.3  254.80
  4394.8  254.85  4401.5  253.98  4458.3  252.00  4670.5  247.68  4698.8  247.68
  4748.8  246.66  4812.4  246.67  4835.3  246.10  4897.5  245.45  4932.6  245.71
  4939.4  245.08  4946.8  245.42  5029.6  244.36  5030.0  243.86  5034.0  243.86
  5034.3  244.36  5038.4  244.37  5081.4  244.76  5166.2  244.43  5195.1  244.64
  5244.7  246.82  5330.3  252.54  5354.3  255.09  5372.8  256.21  5394.4  256.42
#Mann=6,-1,0
  4330.9    0.05       0  4835.3     0.1       0  5029.6    0.05       0
  5034.3     0.1       0  5038.4    0.12       0  5166.2    0.05       0
Bank Sta=5029.6,5034.3
Exp/Cntr=0.3,0.1

Type RM Length L Ch R = 1,8771,466,466,466
BEGIN DESCRIPTION:
TRIB 13 TO TWELVEMILE CREEK 5.0
END DESCRIPTION:
XS GIS Cut Line= 3
      2486425.00     13543275.00      2485675.00     13542975.00
      2485174.97     13543025.00
#Sta/Elev= 30
  4192.2  258.70  4338.9  256.28  4363.2  256.39  4446.7  254.17  4452.0  254.60
  4476.3  254.33  4554.4  251.01  4676.9  248.09  4715.9  246.17  4721.3  246.43
  4752.3  245.18  4863.8  243.86  4892.9  243.78  4955.5  243.14  4985.2  243.47
  5037.7  242.70  5038.1  242.20  5042.3  242.20  5042.7  242.70  5077.8  243.16
  5153.2  243.62  5241.2  249.12  5261.3  251.36  5291.4  253.71  5311.5  254.11
  5349.2  253.67  5354.2  254.26  5402.0  254.57  5454.7  256.64  5502.5  259.62
#Mann=6,-1,0
  4192.2    0.05       0  4863.8    0.12       0  4892.9     0.1       0
  5037.7    0.05       0  5042.7     0.1       0  5077.8    0.05       0
Bank Sta=5037.7,5042.7
Exp/Cntr=0.3,0.1

Type RM Length L Ch R = 1,8305,475,475,475
BEGIN DESCRIPTION:
TRIB 13 TO TWELVEMILE CREEK 4.0
END DESCRIPTION:
XS GIS Cut Line= 3
      2486325.00     13543025.00      2485725.00     13542525.00
      2485175.02     13542675.00
#Sta/Elev= 30
  4219.0  257.74  4247.0  257.18  4254.6  256.43  4297.1  254.17  4411.0  251.60
  4453.3  251.43  4489.1  249.39  4531.4  248.41  4595.8  245.05  4631.0  243.91
  4688.5  243.35  4737.7  242.92  4744.9  243.37  4772.9  242.47  4793.7  242.88
  4990.4  241.19  4990.7  240.69  4995.0  240.69  4995.4  241.19  5053.6  241.91
  5091.6  242.58  5145.1  241.46  5279.9  242.94  5352.4  246.18  5445.7  248.82
  5487.2  251.07  5547.7  256.37  5552.8  256.04  5560.9  256.75  5570.1  256.98
#Mann=8,-1,0
  4219.0    0.05       0  4254.6    0.12       0  4688.5    0.05       0
  4744.9    0.12       0  4990.4    0.05       0  4995.4    0.12       0
  5053.6    0.04       0  5560.9    0.05       0
Bank Sta=4990.4,4995.4
Exp/Cntr=0.3,0.1

Type RM Length L Ch R = 1,7830,393,393,393
BEGIN DESCRIPTION:
TRIB 13 TO TWELVEMILE CREEK 3.0
END DESCRIPTION:
XS GIS Cut Line= 3
      2486725.04     13542125.00      2485825.00     13542075.00
      2485425.03     13541975.01
#Sta/Elev= 30
  3995.3  253.07  4005.4  252.32  4135.6  248.52  4155.6  248.54  4175.6  247.36
  4225.7  246.29  4235.7  245.49  4285.8  245.93  4305.8  244.59  4385.9  244.38
  4536.2  241.51  4596.3  242.15  4696.4  240.94  4846.6  240.53  4876.7  239.44
  4914.8  239.60  5017.9  238.01  5018.3  237.51  5022.6  237.51  5023.0  238.01
  5038.5  238.86  5061.6  238.43  5113.2  238.70  5162.1  241.32  5166.7  241.09
  5203.4  244.41  5208.5  244.27  5244.6  248.56  5267.8  249.75  5309.0  253.35
#Mann=4,-1,0
  3995.3    0.12       0  5017.9    0.05       0  5023.0    0.12       0
  5166.7    0.04       0
Bank Sta=5017.9,5023
Exp/Cntr=0.3,0.1

Type RM Length L Ch R = 1,7437,873,873,873
BEGIN DESCRIPTION:
TRIB 13 TO TWELVEMILE CREEK 2.0
END DESCRIPTION:
XS GIS Cut Line= 3
      2486525.00     13541975.00      2485925.00     13541625.00
      2485375.02     13541924.99
#Sta/Elev= 30
  4134.8  246.90  4169.9  245.87  4185.7  246.41  4192.7  245.70  4308.9  243.40
  4340.3  243.95  4447.8  238.82  4506.5  237.93  4837.5  236.42  4919.1  238.04
  4962.8  233.46  4968.5  233.96  4997.5  233.42  4997.9  232.92  5003.1  233.42
  5022.6  234.34  5028.3  233.96  5044.4  237.00  5050.1  236.33  5057.2  237.67
  5072.0  236.98  5088.1  238.11  5093.8  237.41  5102.8  237.87  5148.2  237.29
  5240.9  238.08  5262.0  239.33  5322.6  242.87  5404.2  251.87  5455.9  254.45
#Mann=5,-1,0
  4134.8    0.12       0  4997.5    0.05       0  5003.1    0.12       0
  5148.2    0.03       0  5262.0    0.04       0
Bank Sta=4997.5,5003.1
Exp/Cntr=0.3,0.1

Type RM Length L Ch R = 1,6564,561,561,561
BEGIN DESCRIPTION:
Mapping XS 37a92c0c
END DESCRIPTION:
XS GIS Cut Line= 4
      2487030.04     13541806.98      2486155.02     13541181.96
      2485807.80     13541133.35      2484995.32     13541779.17
#Sta/Elev= 30
  4005.4  251.45  4074.1  248.35  4254.7  245.83  4340.8  243.58  4533.7  241.55
  4845.4  235.83  4956.4  234.37  5037.9  234.32  5074.8  234.13  5075.3  233.63
  5080.5  234.13  5276.0  234.59  5345.1  235.75  5403.9  237.58  5430.8  236.11
  5456.1  235.01  5498.8  235.25  5541.0  238.13  5562.6  238.55  5640.3  234.96
  5690.4  238.07  5754.3  236.40  5811.7  240.02  5875.8  236.55  6003.9  235.62
  6068.0  236.45  6117.6  238.24  6338.1  240.01  6363.7  240.75  6469.2  243.42
#Mann=11,-1,0
  4005.4    0.12       0  4845.4     0.1       0  4956.4    0.03       0
  5037.9     0.1       0  5074.8    0.03       0  5080.5     0.1       0
  5276.0    0.03       0  5345.1    0.05       0  5430.8    0.04       0
  6338.1    0.05       0  6363.7    0.04       0
Bank Sta=5074.8,5080.5
Exp/Cntr=0.3,0.1

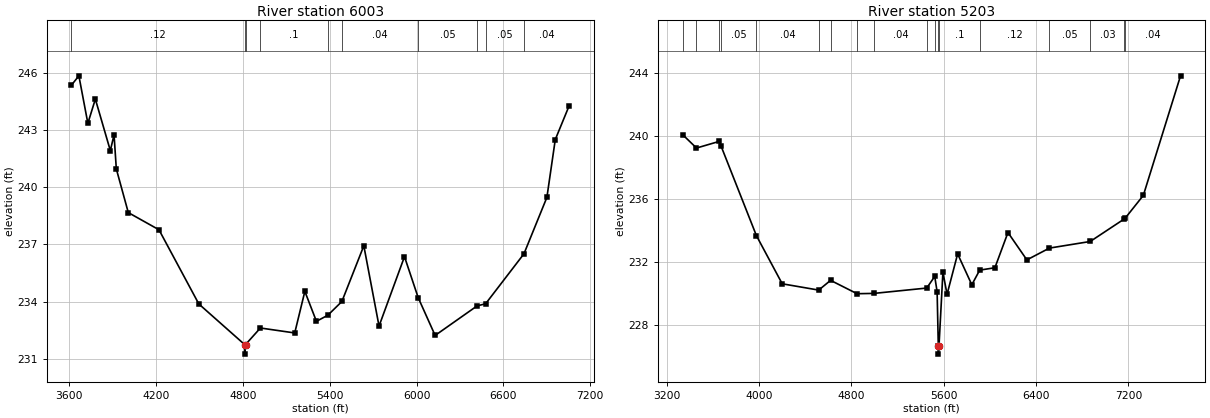
Type RM Length L Ch R = 1,6003,800,800,800
BEGIN DESCRIPTION:
4819
END DESCRIPTION:
XS GIS Cut Line= 5
      2487774.79     13541105.87      2486529.16     13540773.70
      2486093.18     13540784.08      2485366.53     13541095.50
      2484806.95     13541831.24
#Sta/Elev= 30
  3614.4  245.35  3665.9  245.84  3728.0  243.35  3779.8  244.62  3883.3  241.92
  3909.0  242.75  3924.7  240.96  4007.5  238.67  4219.5  237.77  4495.0  233.88
  4811.9  231.75  4812.3  231.25  4817.6  231.75  4920.5  232.62  5157.8  232.36
  5227.8  234.54  5307.8  232.97  5386.9  233.29  5483.8  234.01  5635.4  236.93
  5740.6  232.72  5916.5  236.36  6011.2  234.21  6128.3  232.23  6418.6  233.78
  6477.2  233.89  6742.3  236.51  6900.9  239.47  6958.8  242.50  7054.6  244.27
#Mann=10,-1,0
  3614.4    0.12       0  4811.9    0.05       0  4817.6    0.12       0
  4920.5     0.1       0  5386.9    0.12       0  5483.8    0.04       0
  6011.2    0.05       0  6418.6    0.03       0  6477.2    0.05       0
  6742.3    0.04       0
Bank Sta=4811.9,4817.6
Exp/Cntr=0.3,0.1

Type RM Length L Ch R = 1,5203,0,0,0
BEGIN DESCRIPTION:
4818
END DESCRIPTION:
XS GIS Cut Line= 5
      2488143.31     13540742.54      2486819.82     13540124.91
      2486108.75     13540265.05      2485350.96     13540835.98
      2484692.36     13541810.92
#Sta/Elev= 30
  3340.1  240.06  3458.6  239.22  3654.1  239.64  3669.5  239.38  3977.6  233.65
  4201.0  230.59  4517.2  230.19  4619.8  230.81  4849.2  229.96  4995.0  229.98
  5452.6  230.32  5522.0  231.06  5542.6  230.08  5552.9  226.62  5553.4  226.12
  5558.7  226.62  5592.7  231.33  5628.6  229.92  5720.3  232.49  5843.1  230.53
  5911.4  231.46  6043.0  231.61  6156.1  233.85  6319.9  232.11  6515.2  232.86
  6868.4  233.28  7165.1  234.72  7172.3  234.77  7328.6  236.21  7650.7  243.81
#Mann=18,-1,0
  3340.1    0.12       0  3458.6    0.05       0  3654.1    0.12       0
  3669.5    0.05       0  3977.6    0.04       0  4517.2    0.05       0
  4619.8    0.04       0  4849.2    0.03       0  4995.0    0.04       0
  5452.6    0.12       0  5522.0     0.1       0  5552.9    0.04       0
  5558.7     0.1       0  5911.4    0.12       0  6515.2    0.05       0
  6868.4    0.03       0  7165.1    0.12       0  7172.3    0.04       0
Bank Sta=5552.9,5558.7
Exp/Cntr=0.3,0.1

Chan Stop Cuts=-1