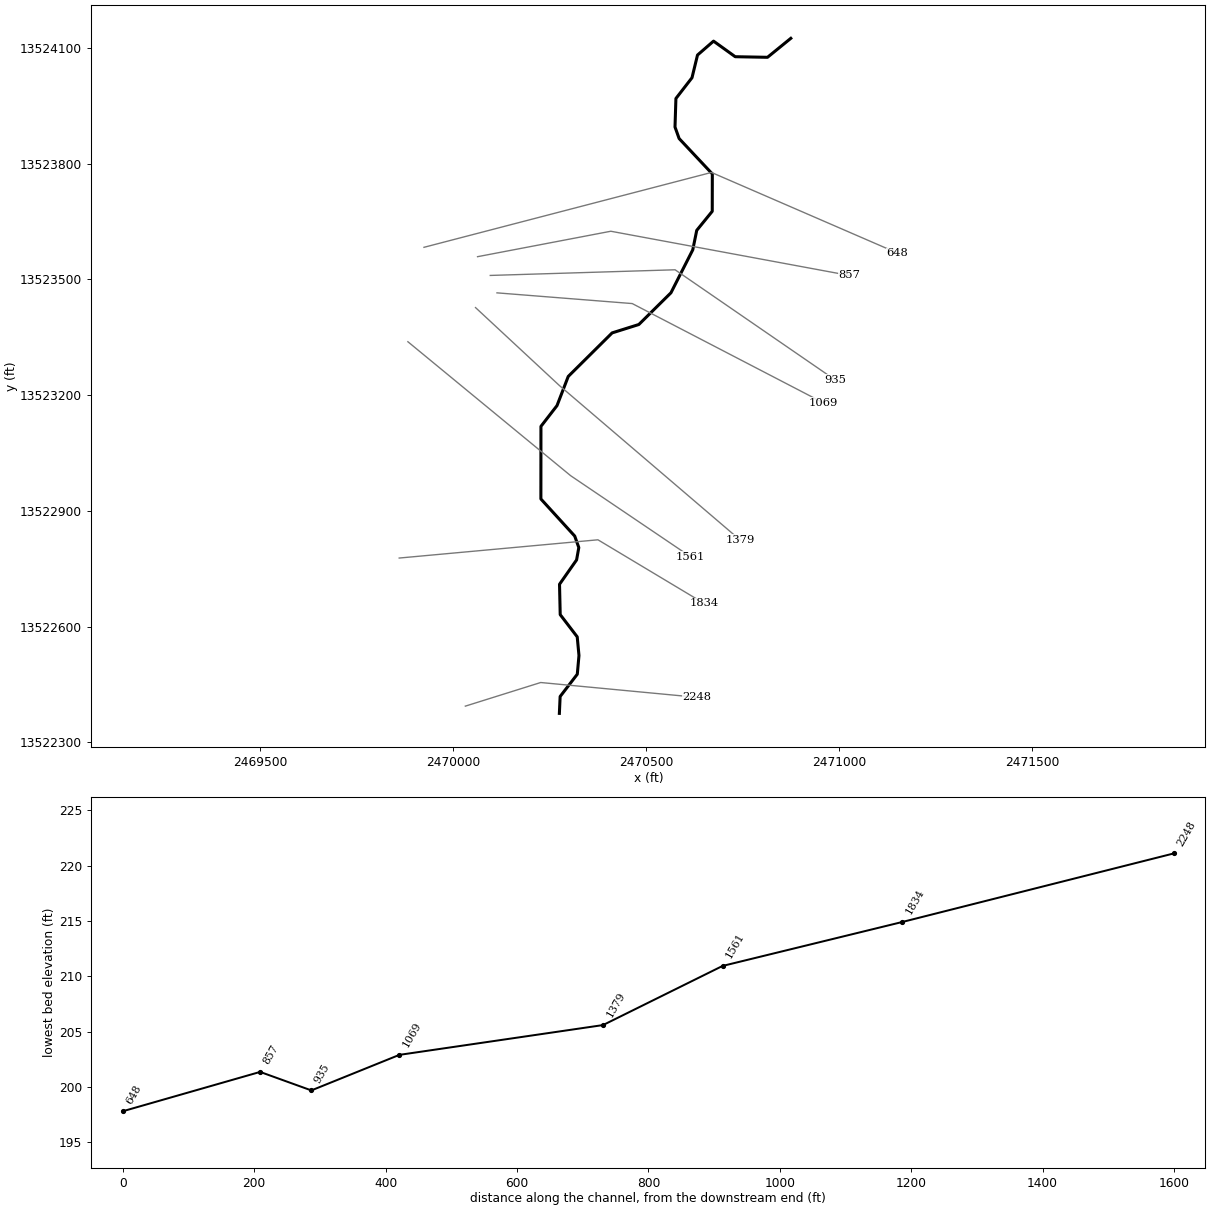
--- TRIB 13_1 TO FIFTEENMILE CREEK.prj (project) ---

Proj Title=TRIB 13_1 TO FIFTEENMILE CREEK Base Level Engineering
Current Plan=p01
Default Exp/Contr=0.3,0.1
English Units
Geom File=g01
Flow File=f01
Plan File=p01
Y Axis Title=Elevation
X Axis Title(PF)=Main Channel Distance
X Axis Title(XS)=Station
BEGIN DESCRIPTION:
TRIB 13_1 TO FIFTEENMILE CREEK
END DESCRIPTION:
DSS Export Rating Curves= 0
DSS Export Rating Curve Sorted= 0
DSS Export Volume Flow Curves= 0
DXF OffsetX= 0
DXF OffsetY= 0
DXF ScaleX= 1
DXF ScaleY= 10

--- TRIB 13_1 TO FIFTEENMILE CREEK.p01 (plan) ---

Plan Title=Multiple Run
Short Identifier=Multiple
Geom File=g01
Flow File=f01
Subcritical Flow
K Sum by GR= 0
Std Step Tol= 0.01
Critical Tol= 0.01
Num of Std Step Trials= 20
Max Error Tol= 0.3
Flow Tol Ratio= 0.001
Split Flow NTrial= 30
Split Flow Tol= 0.02
Split Flow Ratio= 0.02
Log Output Level= 0
Friction Slope Method= 1
Unsteady Friction Slope Method= 2
Unsteady Bridges Friction Slope Method= 1
Parabolic Critical Depth
Global Vel Dist=  1 , 1 , 1
Global Log Level= 0
CheckData=True
Encroach Param= -1, 0, 0, 0
BEGIN DESCRIPTION:
Multiple Run
END DESCRIPTION:

--- TRIB 13_1 TO FIFTEENMILE CREEK.f01 (steady flow) ---

Flow Title=Multiple
Number of Profiles=7
Profile Names=10-year,25-year,50-year,1pct_min,100-year,1pct_plu,500-year
River Rch & RM= TRIB 13_1 TO FIF,Reach-1,2248
     564     909    1221     795    1586    3165    2648
Boundary for River Rch & Prof#=TRIB 13_1 TO FIF,Reach-1,1
Up Type=0
Dn Type=3
Dn Slope=0.005
Boundary for River Rch & Prof#=TRIB 13_1 TO FIF,Reach-1,2
Up Type=0
Dn Type=3
Dn Slope=0.005
Boundary for River Rch & Prof#=TRIB 13_1 TO FIF,Reach-1,3
Up Type=0
Dn Type=3
Dn Slope=0.005
Boundary for River Rch & Prof#=TRIB 13_1 TO FIF,Reach-1,4
Up Type=0
Dn Type=3
Dn Slope=0.005
Boundary for River Rch & Prof#=TRIB 13_1 TO FIF,Reach-1,5
Up Type=0
Dn Type=3
Dn Slope=0.005
Boundary for River Rch & Prof#=TRIB 13_1 TO FIF,Reach-1,6
Up Type=0
Dn Type=3
Dn Slope=0.005
Boundary for River Rch & Prof#=TRIB 13_1 TO FIF,Reach-1,7
Up Type=0
Dn Type=3
Dn Slope=0.005

--- TRIB 13_1 TO FIFTEENMILE CREEK.g01 (geometry) ---

Geom Title=Existing Conditions

River Reach=TRIB 13_1 TO FIF,Reach-1
Reach XY= 30
      2470275.00     13522375.00      2470276.99     13522418.73
      2470321.48     13522476.53      2470325.82     13522525.00
      2470321.29     13522573.40      2470277.17     13522630.97
      2470275.40     13522709.73      2470319.64     13522772.83
      2470325.39     13522804.87      2470314.79     13522834.67
      2470227.07     13522930.86      2470227.24     13523119.07
      2470268.86     13523172.83      2470298.01     13523248.47
      2470411.79     13523361.37      2470481.07     13523383.15
      2470564.24     13523465.30      2470620.84     13523576.72
      2470631.12     13523627.18      2470671.33     13523676.59
      2470671.53     13523773.50      2470585.46     13523865.22
      2470574.79     13523895.05      2470577.14     13523969.03
      2470618.85     13524022.88      2470633.13     13524081.70
      2470674.68     13524117.77      2470730.87     13524077.37
      2470814.54     13524075.82      2470875.00     13524125.00

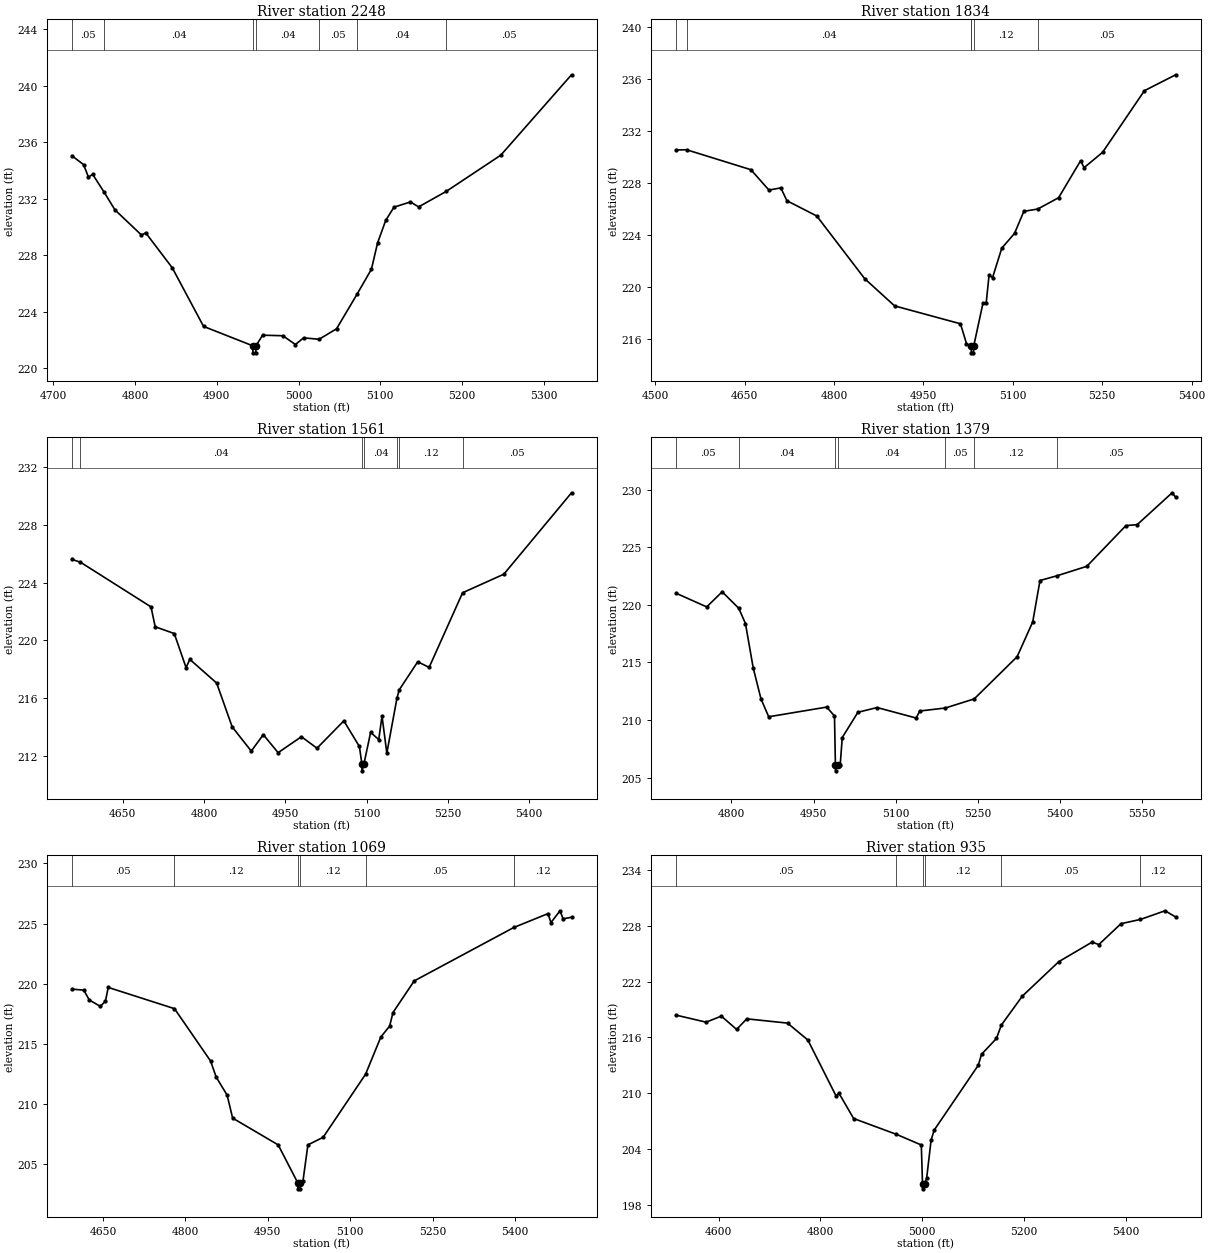
Type RM Length L Ch R = 1,2248,414,414,414
BEGIN DESCRIPTION:
TRIB 13_1 TO FIFTEENMILE CREEK 5.0
END DESCRIPTION:
XS GIS Cut Line= 3
      2470031.25     13522393.76      2470226.64     13522455.01
      2470631.16     13522416.68
#Sta/Elev= 30
  4722.8  235.05  4737.2  234.42  4743.1  233.54  4748.3  233.73  4762.4  232.46
  4775.5  231.22  4807.9  229.44  4813.2  229.59  4845.6  227.12  4883.9  222.97
  4944.0  221.60  4944.3  221.10  4947.8  221.10  4948.0  221.60  4956.1  222.35
  4980.9  222.31  4996.2  221.69  5006.3  222.16  5025.2  222.06  5046.5  222.80
  5071.7  225.26  5089.2  227.02  5096.7  228.88  5106.7  230.48  5116.8  231.41
  5136.9  231.78  5146.9  231.43  5180.5  232.52  5247.4  235.09  5333.9  240.78
#Mann=7,-1,0
  4722.8    0.05       0  4762.4    0.04       0  4944.0    0.04       0
  4948.0    0.04       0  5025.2    0.05       0  5071.7    0.04       0
  5180.5    0.05       0
Bank Sta=4944,4948
Exp/Cntr=0.3,0.1

Type RM Length L Ch R = 1,1834,273,273,273
BEGIN DESCRIPTION:
TRIB 13_1 TO FIFTEENMILE CREEK 4.0
END DESCRIPTION:
XS GIS Cut Line= 3
      2469859.79     13522777.68      2470375.00     13522825.00
      2470650.17     13522660.06
#Sta/Elev= 30
  4534.9  230.54  4552.6  230.56  4660.6  229.02  4690.8  227.45  4710.8  227.62
  4720.9  226.63  4771.1  225.45  4851.4  220.62  4901.6  218.52  5012.1  217.14
  5022.2  215.61  5029.4  215.42  5030.2  215.40  5030.4  214.90  5033.9  214.90
  5034.2  215.40  5049.8  218.72  5055.2  218.72  5060.1  220.91  5065.9  220.70
  5081.4  222.97  5102.8  224.11  5118.4  225.81  5141.8  225.99  5176.7  226.86
  5213.6  229.71  5219.5  229.18  5250.5  230.36  5320.6  235.11  5373.1  236.34
#Mann=6,-1,0
  4534.9    0.05       0  4552.6    0.04       0  5029.4    0.12       0
  5030.2    0.04       0  5034.2    0.12       0  5141.8    0.05       0
Bank Sta=5030.2,5034.2
Exp/Cntr=0.3,0.1

Type RM Length L Ch R = 1,1561,182,182,182
BEGIN DESCRIPTION:
Mapping XS 0a06edf2
END DESCRIPTION:
XS GIS Cut Line= 3
      2469882.29     13523338.46      2470304.19     13522991.22
      2470614.93     13522781.17
#Sta/Elev= 30
  4556.5  225.62  4572.4  225.42  4702.5  222.32  4710.2  220.94  4745.4  220.47
  4767.2  218.10  4774.0  218.68  4823.6  217.03  4852.2  213.99  4887.4  212.31
  4909.6  213.45  4936.9  212.20  4979.9  213.31  5008.6  212.51  5058.1  214.41
  5086.8  212.63  5091.3  211.44  5091.6  210.94  5095.3  211.44  5107.5  213.61
  5122.5  213.11  5128.5  214.74  5137.4  212.17  5156.1  215.99  5160.4  216.57
  5194.4  218.51  5215.4  218.12  5277.1  223.30  5353.2  224.59  5478.0  230.24
#Mann=7,-1,0
  4556.5    0.05       0  4572.4    0.04       0  5091.3    0.04       0
  5095.3    0.04       0  5156.1    0.05       0  5160.4    0.12       0
  5277.1    0.05       0
Bank Sta=5091.3,5095.3
Exp/Cntr=0.3,0.1

Type RM Length L Ch R = 1,1379,310,310,310
BEGIN DESCRIPTION:
TRIB 13_1 TO FIFTEENMILE CREEK 3.0
END DESCRIPTION:
XS GIS Cut Line= 3
      2470057.67     13523426.98      2470275.00     13523225.00
      2470743.46     13522824.53
#Sta/Elev= 30
  4698.7  221.01  4754.8  219.82  4783.1  221.13  4813.4  219.70  4825.6  218.38
  4839.8  214.53  4854.0  211.84  4868.1  210.29  4974.1  211.13  4988.3  210.36
  4990.0  206.10  4990.2  205.60  4994.0  206.10  4998.7  206.10  5002.5  208.49
  5031.1  210.68  5066.2  211.09  5137.6  210.18  5144.1  210.79  5190.8  211.05
  5243.6  211.84  5322.0  215.50  5350.5  218.52  5363.8  222.11  5394.8  222.52
  5449.3  223.34  5520.7  226.87  5541.5  226.96  5605.2  229.72  5611.7  229.33
#Mann=7,-1,0
  4698.7    0.05       0  4813.4    0.04       0  4990.0    0.04       0
  4994.0    0.04       0  5190.8    0.05       0  5243.6    0.12       0
  5394.8    0.05       0
Bank Sta=4990,4994
Exp/Cntr=0.3,0.1

Type RM Length L Ch R = 1,1069,134,134,134
BEGIN DESCRIPTION:
Mapping XS 282f9fa4
END DESCRIPTION:
XS GIS Cut Line= 3
      2470113.27     13523465.18      2470463.91     13523437.40
      2470958.73     13523180.45
#Sta/Elev= 30
  4593.3  219.54  4615.1  219.45  4625.1  218.63  4645.2  218.10  4654.5  218.54
  4659.5  219.68  4780.1  217.91  4845.8  213.55  4855.9  212.22  4875.9  210.71
  4885.9  208.80  4968.8  206.57  5004.4  203.41  5004.6  202.91  5008.1  202.91
  5008.4  203.41  5013.9  203.56  5022.9  206.57  5050.6  207.20  5127.8  212.45
  5155.6  215.55  5171.6  216.46  5177.7  217.59  5216.3  220.22  5397.6  224.67
  5459.6  225.82  5465.2  225.08  5481.7  226.06  5487.3  225.39  5502.6  225.52
#Mann=6,-1,0
  4593.3    0.05       0  4780.1    0.12       0  5004.4    0.05       0
  5008.4    0.12       0  5127.8    0.05       0  5397.6    0.12       0
Bank Sta=5004.4,5008.4
Exp/Cntr=0.3,0.1

Type RM Length L Ch R = 1,935,78,78,78
BEGIN DESCRIPTION:
TRIB 13_1 TO FIFTEENMILE CREEK 2.0
END DESCRIPTION:
XS GIS Cut Line= 3
      2470095.83     13523510.32      2470575.00     13523525.00
      2470989.56     13523239.76
#Sta/Elev= 30
  4515.9  218.40  4575.1  217.64  4605.1  218.29  4635.1  216.86  4655.1  218.00
  4735.2  217.54  4775.2  215.72  4831.1  209.65  4836.1  210.02  4865.2  207.27
  4949.2  205.57  4998.3  204.42  5000.7  200.20  5001.0  199.70  5004.7  200.20
  5008.8  200.83  5017.6  204.97  5023.7  206.03  5110.3  213.00  5116.7  214.18
  5146.1  215.89  5155.7  217.33  5196.9  220.44  5268.6  224.15  5334.2  226.26
  5347.3  225.99  5391.0  228.24  5429.3  228.70  5477.6  229.63  5498.5  228.96
#Mann=6,-1,0
  4515.9    0.05       0  4949.2    0.12       0  5000.7    0.05       0
  5004.7    0.12       0  5155.7    0.05       0  5429.3    0.12       0
Bank Sta=5000.7,5004.7
Exp/Cntr=0.3,0.1

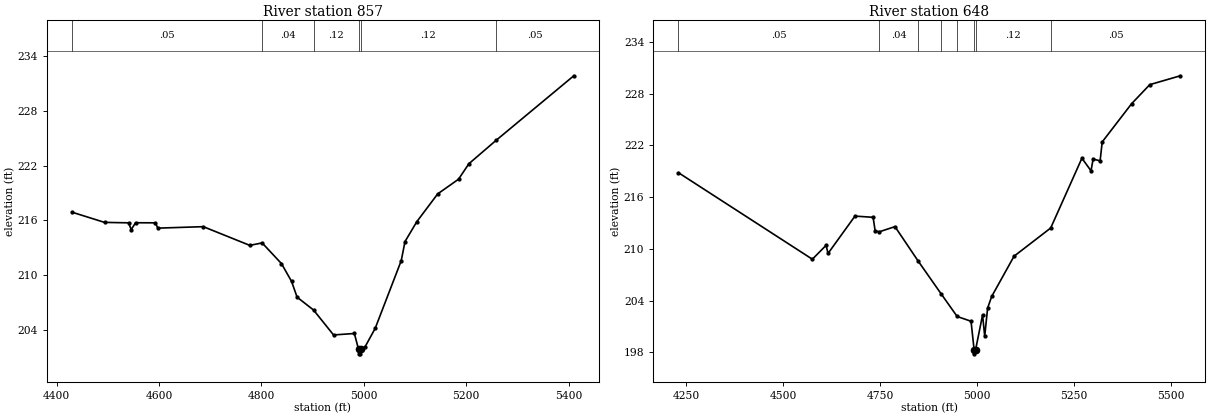
Type RM Length L Ch R = 1,857,209,209,209
BEGIN DESCRIPTION:
Mapping XS f7d0ef30
END DESCRIPTION:
XS GIS Cut Line= 3
      2470062.92     13523558.94      2470408.36     13523624.90
      2471026.44     13523510.31
#Sta/Elev= 30
  4429.8  216.90  4493.4  215.78  4540.5  215.73  4545.5  214.99  4554.1  215.74
  4592.6  215.73  4597.7  215.15  4686.4  215.31  4777.2  213.26  4801.3  213.53
  4839.1  211.26  4858.8  209.31  4869.6  207.58  4901.8  206.17  4940.8  203.44
  4981.5  203.60  4989.6  201.87  4989.9  201.37  4993.4  201.37  4993.6  201.87
  5001.8  202.08  5022.2  204.17  5073.0  211.58  5080.4  213.68  5103.5  215.86
  5144.2  218.90  5184.9  220.51  5205.2  222.21  5258.5  224.78  5410.1  231.85
#Mann=6,-1,0
  4429.8    0.05       0  4801.3    0.04       0  4901.8    0.12       0
  4989.6    0.05       0  4993.6    0.12       0  5258.5    0.05       0
Bank Sta=4989.6,4993.6
Exp/Cntr=0.3,0.1

Type RM Length L Ch R = 1,648,0,0,0
BEGIN DESCRIPTION:
TRIB 13_1 TO FIFTEENMILE CREEK 1.0
END DESCRIPTION:
XS GIS Cut Line= 3
      2469924.01     13523583.24      2470669.30     13523777.35
      2471151.59     13523568.29
#Sta/Elev= 30
  4229.4  218.82  4575.1  208.79  4610.5  210.40  4615.6  209.46  4685.1  213.79
  4732.0  213.65  4737.1  212.11  4747.3  211.96  4788.4  212.57  4848.1  208.59
  4907.7  204.77  4949.0  202.15  4984.8  201.60  4992.7  198.32  4993.0  197.82
  4996.7  198.32  5014.6  202.33  5020.1  199.86  5027.6  203.12  5038.1  204.47
  5095.9  209.14  5190.5  212.41  5271.1  220.50  5294.6  219.04  5300.0  220.40
  5318.1  220.20  5323.5  222.39  5399.4  226.82  5446.3  229.03  5525.2  230.06
#Mann=8,-1,0
  4229.4    0.05       0  4747.3    0.04       0  4848.1    0.12       0
  4907.7    0.05       0  4949.0    0.12       0  4992.7    0.05       0
  4996.7    0.12       0  5190.5    0.05       0
Bank Sta=4992.7,4996.7
Exp/Cntr=0.3,0.1

Chan Stop Cuts=-1