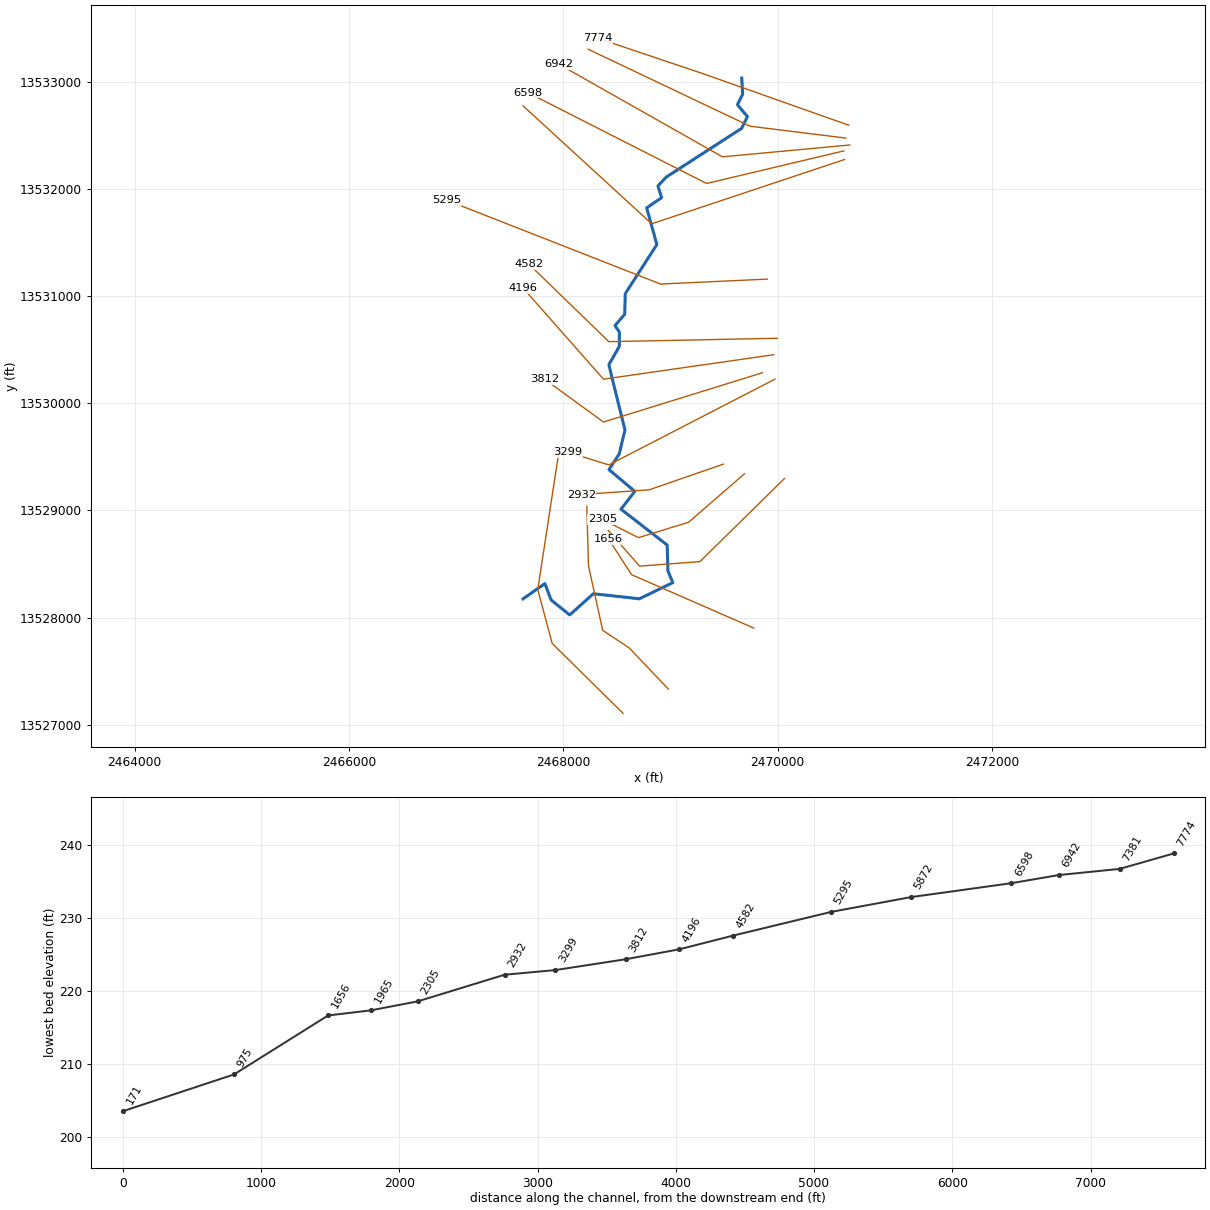
--- TRIB 14 TO FIFTEENMILE CREEK.prj (project) ---

Proj Title=TRIB 14 TO FIFTEENMILE CREEK Base Level Engineering
Current Plan=p01
Default Exp/Contr=0.3,0.1
English Units
Geom File=g01
Flow File=f01
Plan File=p01
Y Axis Title=Elevation
X Axis Title(PF)=Main Channel Distance
X Axis Title(XS)=Station
BEGIN DESCRIPTION:
TRIB 14 TO FIFTEENMILE CREEK
END DESCRIPTION:
DSS Export Rating Curves= 0
DSS Export Rating Curve Sorted= 0
DSS Export Volume Flow Curves= 0
DXF OffsetX= 0
DXF OffsetY= 0
DXF ScaleX= 1
DXF ScaleY= 10

--- TRIB 14 TO FIFTEENMILE CREEK.p01 (plan) ---

Plan Title=Multiple Run
Short Identifier=Multiple
Geom File=g01
Flow File=f01
Subcritical Flow
K Sum by GR= 0
Std Step Tol= 0.01
Critical Tol= 0.01
Num of Std Step Trials= 20
Max Error Tol= 0.3
Flow Tol Ratio= 0.001
Split Flow NTrial= 30
Split Flow Tol= 0.02
Split Flow Ratio= 0.02
Log Output Level= 0
Friction Slope Method= 1
Unsteady Friction Slope Method= 2
Unsteady Bridges Friction Slope Method= 1
Parabolic Critical Depth
Global Vel Dist=  1 , 1 , 1
Global Log Level= 0
CheckData=True
Encroach Param= -1, 0, 0, 0
BEGIN DESCRIPTION:
Multiple Run
END DESCRIPTION:

--- TRIB 14 TO FIFTEENMILE CREEK.f01 (steady flow) ---

Flow Title=Multiple
Number of Profiles=7
Profile Names=10-year,25-year,50-year,1pct_min,100-year,1pct_plu,500-year
River Rch & RM= TRIB 14 TO FIFTE,Reach-1,7774
     689    1115    1501     978    1950    3892    3260
River Rch & RM= TRIB 14 TO FIFTE,Reach-1,6942
     865    1416    1918    1257    2507    5003    4241
Boundary for River Rch & Prof#=TRIB 14 TO FIFTE,Reach-1,1
Up Type=0
Dn Type=3
Dn Slope=0.005
Boundary for River Rch & Prof#=TRIB 14 TO FIFTE,Reach-1,2
Up Type=0
Dn Type=3
Dn Slope=0.005
Boundary for River Rch & Prof#=TRIB 14 TO FIFTE,Reach-1,3
Up Type=0
Dn Type=3
Dn Slope=0.005
Boundary for River Rch & Prof#=TRIB 14 TO FIFTE,Reach-1,4
Up Type=0
Dn Type=3
Dn Slope=0.005
Boundary for River Rch & Prof#=TRIB 14 TO FIFTE,Reach-1,5
Up Type=0
Dn Type=3
Dn Slope=0.005
Boundary for River Rch & Prof#=TRIB 14 TO FIFTE,Reach-1,6
Up Type=0
Dn Type=3
Dn Slope=0.005
Boundary for River Rch & Prof#=TRIB 14 TO FIFTE,Reach-1,7
Up Type=0
Dn Type=3
Dn Slope=0.005

--- TRIB 14 TO FIFTEENMILE CREEK.g01 (geometry) ---

Geom Title=Existing Conditions

River Reach=TRIB 14 TO FIFTE,Reach-1
Reach XY= 30
      2469665.19     13533034.81      2469673.79     13532885.48
      2469625.61     13532785.62      2469717.70     13532675.08
      2469664.26     13532565.30      2468961.73     13532111.37
      2468882.81     13532028.42      2468917.61     13531918.67
      2468778.04     13531823.58      2468873.20     13531481.11
      2468578.55     13531023.53      2468572.92     13530830.85
      2468482.33     13530725.10      2468523.62     13530664.56
      2468522.77     13530530.93      2468425.08     13530359.61
      2468575.40     13529750.00      2468521.44     13529526.47
      2468426.57     13529381.04      2468667.42     13529178.35
      2468538.41     13529011.67      2468969.54     13528677.45
      2468976.24     13528435.50      2469021.97     13528326.39
      2468709.79     13528175.51      2468280.85     13528222.94
      2468059.64     13528024.89      2467885.52     13528165.22
      2467828.62     13528317.53      2467625.00     13528175.00

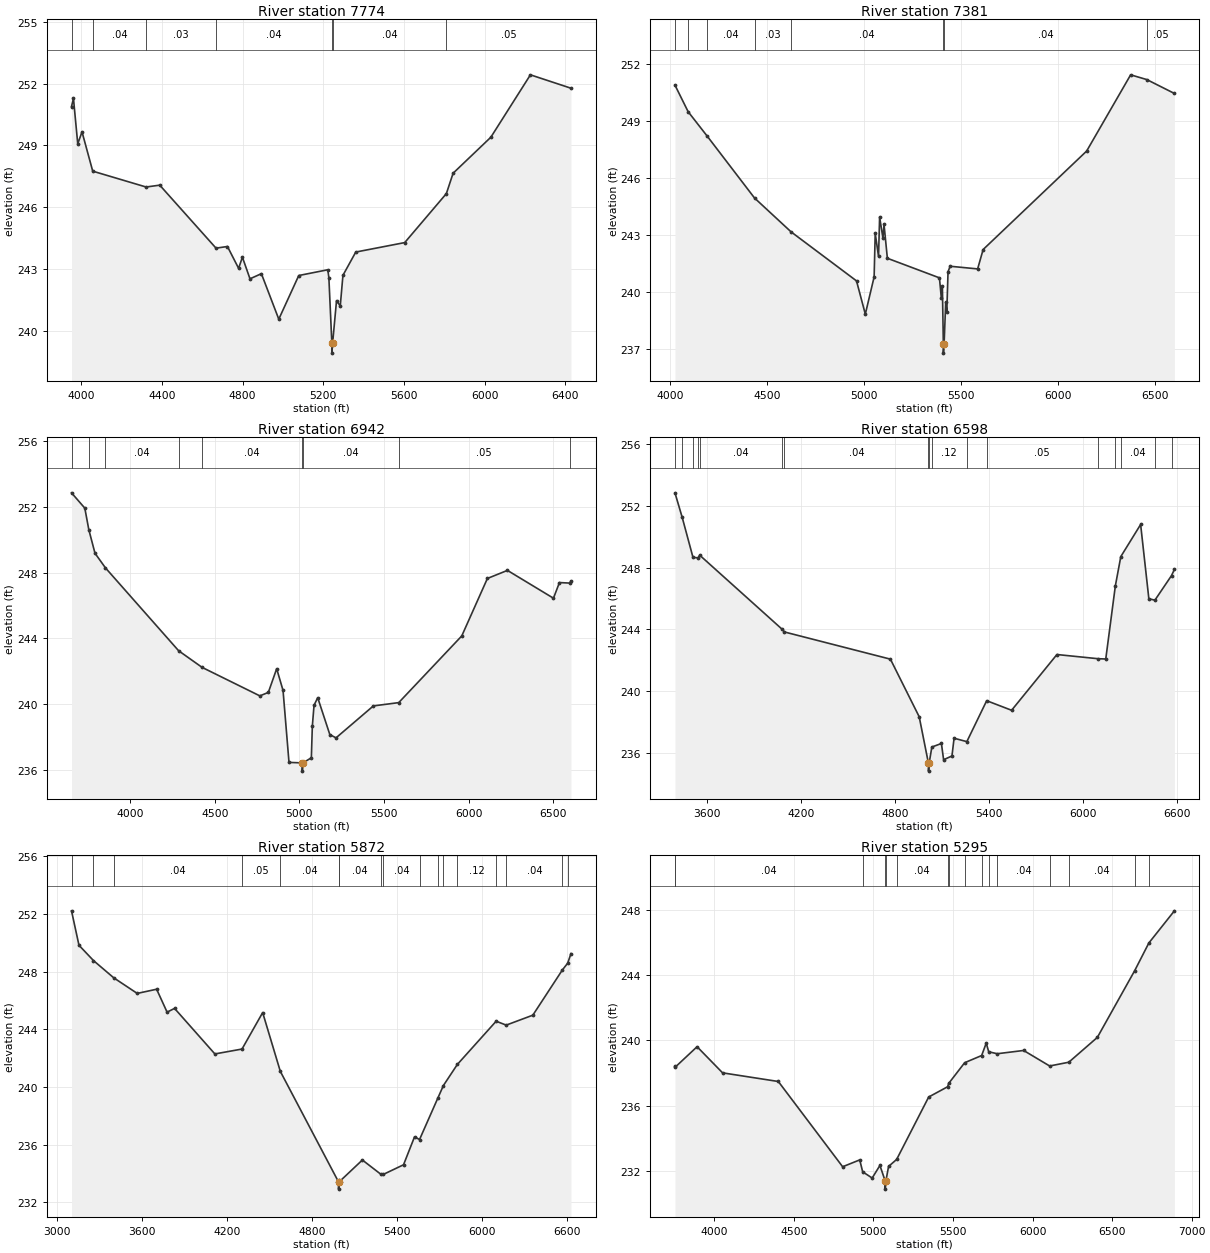
Type RM Length L Ch R = 1,7774,393,393,393
BEGIN DESCRIPTION:
LGII4595
END DESCRIPTION:
XS GIS Cut Line= 3
      2470664.11     13532594.64      2469309.53     13533073.81
      2468323.57     13533405.53
#Sta/Elev= 30
  3951.2  250.89  3960.9  251.28  3982.1  249.08  4003.3  249.66  4056.4  247.75
  4321.1  246.98  4388.8  247.07  4667.9  244.01  4724.6  244.09  4779.9  243.03
  4798.8  243.57  4836.4  242.52  4892.9  242.77  4979.2  240.56  5078.3  242.68
  5222.2  242.96  5227.6  242.58  5242.3  239.41  5242.6  238.91  5246.3  239.41
  5265.6  241.46  5284.1  241.20  5297.4  242.69  5361.0  243.82  5603.8  244.28
  5810.4  246.66  5843.8  247.65  6031.1  249.40  6227.2  252.43  6428.3  251.78
#Mann=7,-1,0
  3951.2   0.013       0  4056.4    0.04       0  4321.1    0.03       0
  4667.9    0.04       0  5242.3    0.04       0  5246.3    0.04       0
  5810.4    0.05       0
Bank Sta=5242.3,5246.3
Exp/Cntr=0.3,0.1

Type RM Length L Ch R = 1,7381,439,439,439
BEGIN DESCRIPTION:
LGII4594
END DESCRIPTION:
XS GIS Cut Line= 3
      2470636.46     13532474.86      2469742.61     13532585.44
      2468231.39     13533304.19
#Sta/Elev= 30
  4027.1  250.88  4095.0  249.48  4194.4  248.18  4437.2  244.94  4625.5  243.16
  4962.8  240.58  5008.2  238.83  5053.6  240.79  5059.2  243.08  5076.3  241.87
  5081.9  243.94  5099.1  242.83  5104.6  243.55  5121.8  241.77  5390.2  240.74
  5399.9  239.68  5405.4  240.30  5410.3  237.28  5410.6  236.78  5414.3  237.28
  5422.6  239.47  5428.1  238.93  5434.5  241.06  5445.3  241.35  5587.1  241.21
  5615.4  242.23  6148.9  247.41  6375.7  251.42  6459.0  251.17  6601.2  250.44
#Mann=8,-1,0
  4027.1    0.04       0  4095.0   0.013       0  4194.4    0.04       0
  4437.2    0.03       0  4625.5    0.04       0  5410.3    0.04       0
  5414.3    0.04       0  6459.0    0.05       0
Bank Sta=5410.3,5414.3
Exp/Cntr=0.3,0.1

Type RM Length L Ch R = 1,6942,344,344,344
BEGIN DESCRIPTION:
LGII4593
END DESCRIPTION:
XS GIS Cut Line= 3
      2470673.25     13532410.36      2469484.61     13532299.79
      2467955.00     13533165.95
#Sta/Elev= 30
  3653.3  252.84  3731.9  251.91  3755.6  250.60  3792.1  249.17  3854.1  248.28
  4286.3  243.25  4425.1  242.24  4766.3  240.51  4816.5  240.72  4865.8  242.16
  4903.4  240.84  4938.6  236.47  5017.0  236.44  5017.3  235.94  5021.0  236.44
  5070.7  236.75  5076.5  238.67  5086.6  239.94  5108.3  240.40  5179.9  238.16
  5216.5  237.96  5437.2  239.90  5587.1  240.10  5959.6  244.15  6111.1  247.64
  6229.5  248.13  6501.5  246.44  6536.8  247.39  6597.1  247.36  6604.9  247.47
#Mann=9,-1,0
  3653.3    0.04       0  3755.6   0.013       0  3854.1    0.04       0
  4286.3    0.03       0  4425.1    0.04       0  5017.0    0.04       0
  5021.0    0.04       0  5587.1    0.05       0  6597.1    0.04       0
Bank Sta=5017,5021
Exp/Cntr=0.3,0.1

Type RM Length L Ch R = 1,6598,726,726,726
BEGIN DESCRIPTION:
LGII4592
END DESCRIPTION:
XS GIS Cut Line= 3
      2470617.95     13532355.07      2469337.17     13532051.00
      2467669.69     13532898.56
#Sta/Elev= 30
  3396.3  252.84  3442.5  251.25  3511.3  248.66  3542.9  248.63  3554.4  248.80
  4078.6  244.02  4095.2  243.83  4771.1  242.07  4954.8  238.34  5013.9  235.32
  5014.2  234.82  5018.0  235.32  5035.5  236.38  5096.5  236.61  5110.5  235.56
  5163.8  235.80  5177.3  236.95  5258.8  236.73  5385.4  239.38  5544.4  238.76
  5833.6  242.37  6094.6  242.10  6145.2  242.08  6206.5  246.82  6241.2  248.71
  6367.7  250.79  6420.2  245.98  6458.8  245.89  6564.7  247.48  6583.2  247.88
#Mann=17,-1,0
  3396.3    0.04       0  3442.5   0.013       0  3511.3    0.04       0
  3542.9   0.013       0  3554.4    0.04       0  4078.6    0.03       0
  4095.2    0.04       0  5013.9    0.04       0  5018.0    0.04       0
  5035.5    0.12       0  5258.8    0.04       0  5385.4    0.05       0
  6094.6    0.04       0  6206.5    0.05       0  6241.2    0.04       0
  6458.8    0.05       0  6564.7    0.04       0
Bank Sta=5013.9,5018
Exp/Cntr=0.3,0.1

Type RM Length L Ch R = 1,5872,577,577,577
BEGIN DESCRIPTION:
TRIB 14 TO FIFTEENMILE CREEK 8.0
END DESCRIPTION:
XS GIS Cut Line= 3
      2470624.98     13532274.99      2468825.00     13531675.00
      2467625.02     13532774.98
#Sta/Elev= 30
  3103.0  252.22  3155.7  249.83  3257.9  248.77  3401.3  247.57  3566.8  246.49
  3703.8  246.78  3777.6  245.19  3830.3  245.45  4114.9  242.29  4306.5  242.63
  4452.2  245.16  4576.8  241.08  4987.7  233.41  4988.0  232.91  4991.9  233.41
  5156.0  234.93  5286.6  233.94  5303.5  233.93  5446.5  234.60  5524.2  236.54
  5559.4  236.35  5689.2  239.24  5728.0  240.10  5826.2  241.56  6100.1  244.56
  6171.3  244.29  6359.1  244.98  6567.8  248.12  6605.2  248.59  6628.2  249.25
#Mann=17,-1,0
  3103.0    0.04       0  3257.9   0.013       0  3401.3    0.04       0
  4306.5    0.05       0  4576.8    0.04       0  4987.7    0.04       0
  4991.9    0.04       0  5286.6    0.05       0  5303.5    0.04       0
  5559.4    0.05       0  5689.2    0.12       0  5728.0    0.04       0
  5826.2    0.12       0  6100.1    0.05       0  6171.3    0.04       0
  6567.8    0.05       0  6605.2    0.04       0
Bank Sta=4987.7,4991.9
Exp/Cntr=0.3,0.1

Type RM Length L Ch R = 1,5295,713,713,713
BEGIN DESCRIPTION:
TRIB 14 TO FIFTEENMILE CREEK 7.0
END DESCRIPTION:
XS GIS Cut Line= 3
      2469903.87     13531158.69      2468907.29     13531112.69
      2466914.22     13531894.59
#Sta/Elev= 30
  3753.0  238.39  3755.9  238.36  3892.0  239.60  4052.2  238.00  4402.6  237.47
  4806.8  232.25  4914.2  232.67  4932.6  231.94  4992.3  231.56  5041.1  232.33
  5074.0  231.38  5074.4  230.88  5078.5  231.38  5095.4  232.27  5146.2  232.70
  5347.5  236.52  5466.7  237.15  5473.0  237.35  5573.5  238.62  5680.3  239.06
  5709.1  239.82  5724.7  239.29  5778.3  239.17  5944.1  239.37  6107.6  238.42
  6227.9  238.65  6407.4  240.17  6641.7  244.25  6731.0  245.95  6891.6  247.92
#Mann=16,-1,0
  3753.0   0.013       0  3755.9    0.04       0  4932.6    0.12       0
  5074.0    0.05       0  5078.5    0.12       0  5146.2    0.04       0
  5466.7    0.12       0  5473.0    0.04       0  5573.5    0.05       0
  5680.3    0.04       0  5724.7    0.05       0  5778.3    0.04       0
  6107.6    0.05       0  6227.9    0.04       0  6641.7    0.12       0
  6731.0    0.05       0
Bank Sta=5074,5078.5
Exp/Cntr=0.3,0.1

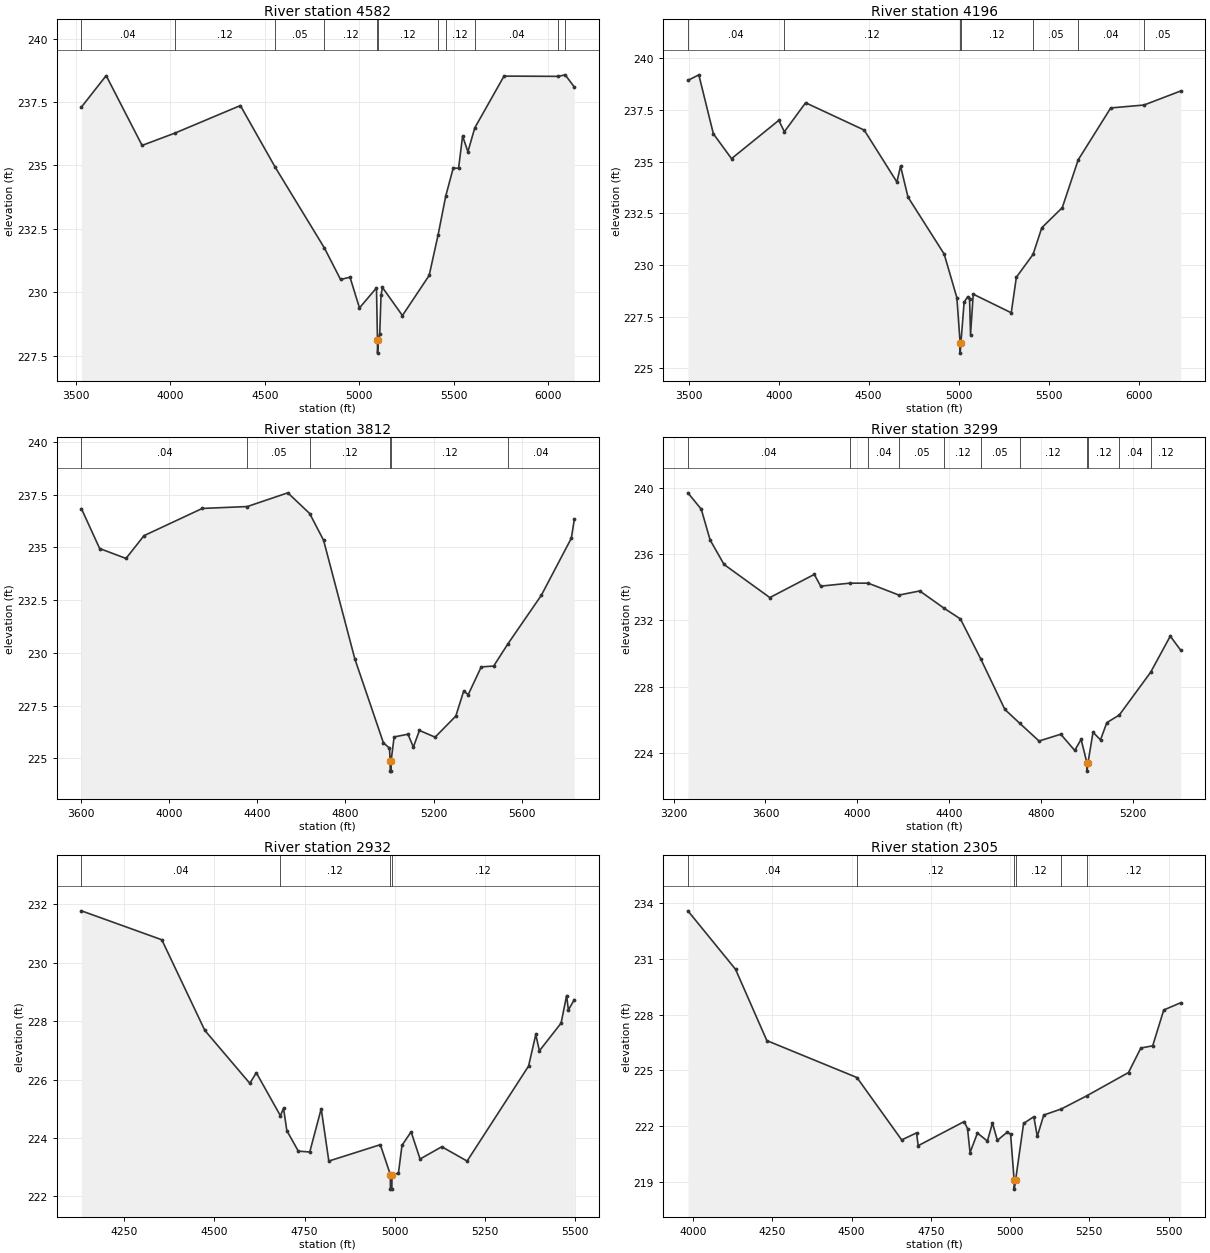
Type RM Length L Ch R = 1,4582,386,386,386
BEGIN DESCRIPTION:
TRIB 14 TO FIFTEENMILE CREEK 6.0
END DESCRIPTION:
XS GIS Cut Line= 3
      2469995.86     13530606.75      2468425.00     13530575.00
      2467680.73     13531296.70
#Sta/Elev= 30
  3529.3  237.30  3660.2  238.54  3850.2  235.79  4022.2  236.27  4370.3  237.36
  4554.7  234.93  4815.0  231.75  4900.4  230.51  4950.4  230.60  5000.5  229.39
  5090.5  230.18  5095.7  228.11  5096.0  227.61  5100.2  228.11  5107.6  228.36
  5114.5  229.88  5121.7  230.20  5227.7  229.09  5369.2  230.67  5416.6  232.27
  5456.8  233.79  5496.5  234.90  5524.8  234.89  5546.1  236.16  5574.2  235.54
  5610.5  236.48  5765.3  238.52  6052.8  238.51  6089.0  238.57  6137.2  238.09
#Mann=11,-1,0
  3529.3    0.04       0  4022.2    0.12       0  4554.7    0.05       0
  4815.0    0.12       0  5095.7    0.05       0  5100.2    0.12       0
  5416.6    0.04       0  5456.8    0.12       0  5610.5    0.04       0
  6052.8    0.05       0  6089.0   0.013       0
Bank Sta=5095.7,5100.2
Exp/Cntr=0.3,0.1

Type RM Length L Ch R = 1,4196,384,384,384
BEGIN DESCRIPTION:
TRIB 14 TO FIFTEENMILE CREEK 5.0
END DESCRIPTION:
XS GIS Cut Line= 3
      2469965.13     13530453.42      2468375.00     13530225.00
      2467625.02     13531074.98
#Sta/Elev= 30
  3495.0  238.92  3555.7  239.19  3636.6  236.34  3737.6  235.14  4000.3  236.99
  4031.3  236.44  4149.4  237.84  4475.1  236.52  4656.9  234.01  4677.1  234.78
  4718.6  233.28  4919.6  230.53  4990.3  228.42  5008.3  226.24  5008.6  225.74
  5012.8  226.24  5030.7  228.21  5050.9  228.47  5061.0  228.35  5066.2  226.63
  5081.2  228.59  5292.6  227.69  5321.1  229.41  5413.7  230.51  5462.4  231.80
  5576.2  232.77  5664.7  235.08  5845.6  237.59  6030.3  237.73  6235.0  238.41
#Mann=7,-1,0
  3495.0    0.04       0  4031.3    0.12       0  5008.3    0.05       0
  5012.8    0.12       0  5413.7    0.05       0  5664.7    0.04       0
  6030.3    0.05       0
Bank Sta=5008.3,5012.8
Exp/Cntr=0.3,0.1

Type RM Length L Ch R = 1,3812,513,513,513
BEGIN DESCRIPTION:
TRIB 14 TO FIFTEENMILE CREEK 4.0
END DESCRIPTION:
XS GIS Cut Line= 3
      2469857.86     13530284.79      2468375.00     13529825.00
      2467824.99     13530225.01
#Sta/Elev= 30
  3604.1  236.83  3686.7  234.94  3806.0  234.47  3887.5  235.55  4151.5  236.84
  4355.5  236.93  4538.9  237.58  4638.0  236.60  4701.0  235.33  4842.5  229.71
  4972.1  225.73  4999.5  225.48  5002.5  224.89  5002.8  224.39  5006.7  224.39
  5007.0  224.89  5020.5  226.01  5083.3  226.14  5107.7  225.53  5135.1  226.32
  5206.1  226.00  5300.0  227.00  5335.5  228.18  5356.4  228.02  5415.1  229.33
  5471.5  229.37  5535.8  230.42  5687.1  232.72  5823.2  235.43  5836.7  236.32
#Mann=6,-1,0
  3604.1    0.04       0  4355.5    0.05       0  4638.0    0.12       0
  5002.5    0.05       0  5007.0    0.12       0  5535.8    0.04       0
Bank Sta=5002.5,5007
Exp/Cntr=0.3,0.1

Type RM Length L Ch R = 1,3299,367,367,367
BEGIN DESCRIPTION:
TRIB 14 TO FIFTEENMILE CREEK 3.0
END DESCRIPTION:
XS GIS Cut Line= 3
      2469975.00     13530225.00      2468425.00     13529425.00
      2468039.00     13529544.31
#Sta/Elev= 30
  3261.8  239.71  3320.0  238.72  3358.7  236.86  3419.4  235.38  3618.9  233.38
  3812.7  234.78  3840.5  234.07  3966.4  234.25  4047.4  234.25  4181.7  233.53
  4272.3  233.78  4380.1  232.72  4449.6  232.09  4538.0  229.68  4643.3  226.62
  4707.5  225.79  4792.3  224.71  4887.0  225.12  4947.9  224.14  4975.7  224.81
  5001.0  223.39  5001.3  222.89  5005.6  223.39  5027.6  225.24  5060.3  224.78
  5087.7  225.82  5142.1  226.28  5278.5  228.86  5364.4  231.05  5410.1  230.19
#Mann=11,-1,0
  3261.8    0.04       0  3966.4    0.05       0  4047.4    0.04       0
  4181.7    0.05       0  4380.1    0.12       0  4538.0    0.05       0
  4707.5    0.12       0  5001.0    0.05       0  5005.6    0.12       0
  5142.1    0.04       0  5278.5    0.12       0
Bank Sta=5001,5005.6
Exp/Cntr=0.3,0.1

Type RM Length L Ch R = 1,2932,627,627,627
BEGIN DESCRIPTION:
Mapping XS db51494e
END DESCRIPTION:
XS GIS Cut Line= 3
      2469493.20     13529431.96      2468802.01     13529192.71
      2468168.48     13529148.52
#Sta/Elev= 30
  4131.4  231.77  4354.2  230.78  4473.5  227.68  4598.2  225.87  4616.3  226.23
  4683.1  224.76  4691.7  225.02  4700.9  224.25  4732.7  223.55  4764.4  223.52
  4796.2  225.00  4817.3  223.21  4960.1  223.77  4987.8  222.75  4988.1  222.25
  4992.1  222.25  4992.4  222.75  5010.2  222.79  5020.2  223.75  5045.4  224.21
  5070.3  223.28  5130.5  223.70  5200.7  223.21  5371.1  226.46  5391.1  227.54
  5401.1  226.98  5461.3  227.93  5476.5  228.87  5481.5  228.38  5497.9  228.73
#Mann=4,-1,0
  4131.4    0.04       0  4683.1    0.12       0  4987.8    0.05       0
  4992.4    0.12       0
Bank Sta=4987.8,4992.4
Exp/Cntr=0.3,0.1

Type RM Length L Ch R = 1,2305,340,340,340
BEGIN DESCRIPTION:
Mapping XS 3a166607
END DESCRIPTION:
XS GIS Cut Line= 4
      2469689.99     13529341.60      2469168.89     13528889.63
      2468700.98     13528746.06      2468365.96     13528916.23
#Sta/Elev= 30
  3983.6  233.59  4133.9  230.44  4232.7  226.60  4517.0  224.61  4658.1  221.25
  4704.9  221.63  4710.2  220.94  4855.3  222.24  4865.8  221.86  4873.8  220.57
  4897.1  221.62  4928.5  221.19  4944.5  222.16  4959.9  221.23  4991.3  221.67
  5001.7  221.55  5012.8  219.10  5013.2  218.60  5017.6  219.10  5042.7  222.14
  5075.0  222.50  5085.9  221.44  5106.3  222.59  5162.0  222.92  5241.3  223.62
  5373.7  224.88  5412.6  226.20  5450.0  226.32  5484.9  228.25  5538.6  228.64
#Mann=6,-1,0
  3983.6    0.04       0  4517.0    0.12       0  5012.8    0.05       0
  5017.6    0.12       0  5162.0    0.05       0  5241.3    0.12       0
Bank Sta=5012.8,5017.6
Exp/Cntr=0.3,0.1

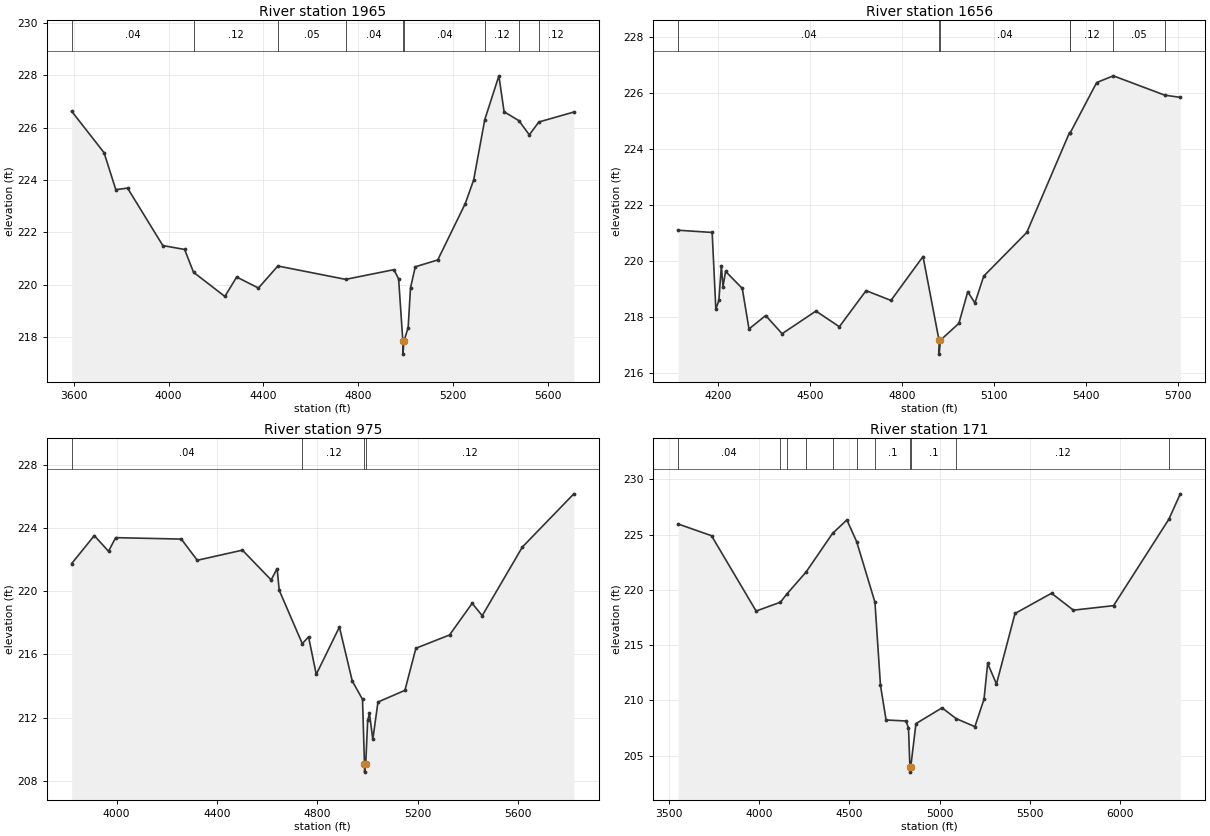
Type RM Length L Ch R = 1,1965,309,309,309
BEGIN DESCRIPTION:
Mapping XS 6a640b98
END DESCRIPTION:
XS GIS Cut Line= 4
      2470064.49     13529298.69      2469275.23     13528522.74
      2468711.61     13528480.21      2468419.57     13528814.73
#Sta/Elev= 30
  3591.9  226.62  3728.5  225.04  3778.0  223.63  3827.5  223.69  3976.0  221.50
  4068.0  221.35  4105.5  220.48  4237.6  219.56  4287.2  220.30  4379.0  219.88
  4460.8  220.72  4746.5  220.21  4949.6  220.58  4969.7  220.23  4987.4  217.86
  4987.7  217.36  4992.2  217.86  5009.8  218.37  5019.8  219.89  5039.9  220.69
  5134.5  220.95  5250.5  223.10  5285.9  224.00  5332.7  226.30  5392.2  227.97
  5414.1  226.60  5476.6  226.26  5520.4  225.72  5560.6  226.21  5708.0  226.59
#Mann=9,-1,0
  3591.9    0.04       0  4105.5    0.12       0  4460.8    0.05       0
  4746.5    0.04       0  4987.4    0.04       0  4992.2    0.04       0
  5332.7    0.12       0  5476.6    0.05       0  5560.6    0.12       0
Bank Sta=4987.4,4992.2
Exp/Cntr=0.3,0.1

Type RM Length L Ch R = 1,1656,681,681,681
BEGIN DESCRIPTION:
Mapping XS 4eb08d80
END DESCRIPTION:
XS GIS Cut Line= 3
      2469776.74     13527902.47      2468637.17     13528400.45
      2468423.44     13528731.29
#Sta/Elev= 30
  4069.8  221.09  4180.8  221.01  4192.8  218.27  4202.7  218.58  4210.8  219.82
  4216.2  219.07  4224.5  219.62  4279.0  219.01  4300.9  217.56  4355.4  218.04
  4408.9  217.39  4519.1  218.20  4595.5  217.64  4682.7  218.93  4763.8  218.58
  4868.4  220.15  4920.5  217.16  4920.9  216.66  4925.3  217.16  4985.3  217.76
  5014.2  218.89  5037.6  218.49  5066.4  219.45  5206.7  221.01  5346.0  224.58
  5348.7  224.58  5434.6  226.37  5488.9  226.61  5656.3  225.92  5707.3  225.84
#Mann=7,-1,0
  4069.8    0.04       0  4920.5    0.04       0  4925.3    0.04       0
  5346.0    0.05       0  5348.7    0.12       0  5488.9    0.05       0
  5656.3    0.12       0
Bank Sta=4920.5,4925.3
Exp/Cntr=0.3,0.1

Type RM Length L Ch R = 1,975,804,804,804
BEGIN DESCRIPTION:
Mapping XS 6e6d705a
END DESCRIPTION:
XS GIS Cut Line= 5
      2468980.62     13527332.95      2468615.58     13527717.15
      2468367.86     13527881.04      2468235.10     13528482.58
      2468219.48     13529039.86
#Sta/Elev= 30
  3821.0  221.74  3911.2  223.51  3967.9  222.52  3996.2  223.38  4257.9  223.29
  4321.4  221.95  4501.3  222.59  4615.6  220.71  4639.4  221.42  4648.0  220.05
  4739.8  216.68  4764.7  217.11  4795.4  214.74  4887.6  217.73  4938.8  214.32
  4979.7  213.16  4987.5  209.06  4987.9  208.56  4992.4  209.06  5000.2  211.83
  5007.3  212.27  5020.7  210.63  5041.2  212.99  5148.6  213.73  5192.3  216.39
  5326.4  217.23  5416.5  219.23  5456.5  218.45  5616.6  222.79  5821.5  226.15
#Mann=4,-1,0
  3821.0    0.04       0  4739.8    0.12       0  4987.5    0.05       0
  4992.4    0.12       0
Bank Sta=4987.5,4992.4
Exp/Cntr=0.3,0.1

Type RM Length L Ch R = 1,171,0,0,0
BEGIN DESCRIPTION:
Mapping XS 5a294996
END DESCRIPTION:
XS GIS Cut Line= 4
      2468558.06     13527106.39      2467896.56     13527758.62
      2467761.68     13528261.89      2467964.15     13529580.74
#Sta/Elev= 30
  3550.0  225.97  3735.1  224.91  3982.5  218.09  4117.2  218.89  4151.8  219.61
  4259.3  221.62  4406.3  225.12  4485.6  226.34  4540.0  224.37  4641.3  218.89
  4671.9  211.37  4703.0  208.23  4812.5  208.14  4827.2  207.54  4835.1  204.01
  4835.5  203.51  4840.0  204.01  4868.6  207.90  5013.3  209.33  5091.8  208.35
  5195.4  207.63  5246.0  210.11  5266.2  213.35  5315.1  211.49  5417.9  217.87
  5620.3  219.70  5741.7  218.17  5964.3  218.58  6270.7  226.40  6334.3  228.70
#Mann=11,-1,0
  3550.0    0.04       0  4117.2    0.05       0  4151.8    0.12       0
  4259.3    0.04       0  4406.3    0.12       0  4540.0    0.05       0
  4641.3     0.1       0  4835.1    0.05       0  4840.0     0.1       0
  5091.8    0.12       0  6270.7    0.04       0
Bank Sta=4835.1,4840
Exp/Cntr=0.3,0.1

Chan Stop Cuts=-1