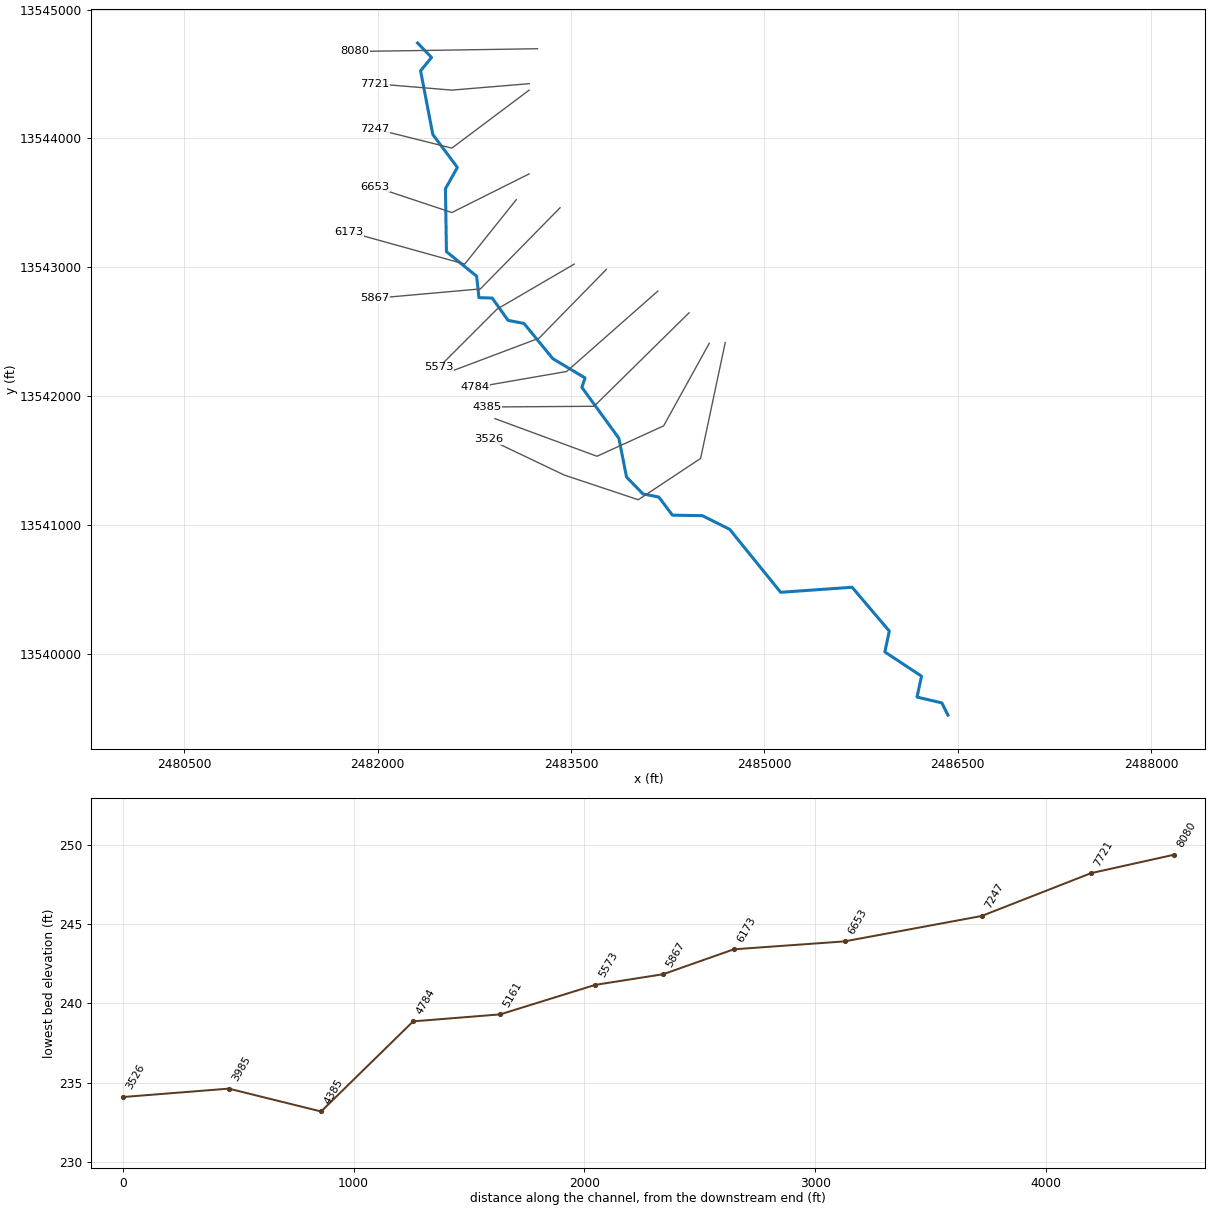
--- TRIB 14 TO TWELVEMILE CREEK.prj (project) ---

Proj Title=TRIB 14 TO TWELVEMILE CREEK Base Level Engineering
Current Plan=p01
Default Exp/Contr=0.3,0.1
English Units
Geom File=g01
Flow File=f01
Plan File=p01
Y Axis Title=Elevation
X Axis Title(PF)=Main Channel Distance
X Axis Title(XS)=Station
BEGIN DESCRIPTION:
TRIB 14 TO TWELVEMILE CREEK
END DESCRIPTION:
DSS Export Rating Curves= 0
DSS Export Rating Curve Sorted= 0
DSS Export Volume Flow Curves= 0
DXF OffsetX= 0
DXF OffsetY= 0
DXF ScaleX= 1
DXF ScaleY= 10

--- TRIB 14 TO TWELVEMILE CREEK.p01 (plan) ---

Plan Title=Multiple Run
Short Identifier=Multiple
Geom File=g01
Flow File=f01
Subcritical Flow
K Sum by GR= 0
Std Step Tol= 0.01
Critical Tol= 0.01
Num of Std Step Trials= 20
Max Error Tol= 0.3
Flow Tol Ratio= 0.001
Split Flow NTrial= 30
Split Flow Tol= 0.02
Split Flow Ratio= 0.02
Log Output Level= 0
Friction Slope Method= 1
Unsteady Friction Slope Method= 2
Unsteady Bridges Friction Slope Method= 1
Parabolic Critical Depth
Global Vel Dist=  1 , 1 , 1
Global Log Level= 0
CheckData=True
Encroach Param= -1, 0, 0, 0
BEGIN DESCRIPTION:
Multiple Run
END DESCRIPTION:

--- TRIB 14 TO TWELVEMILE CREEK.f01 (steady flow) ---

Flow Title=Multiple
Number of Profiles=7
Profile Names=10-year,25-year,50-year,1pct_min,100-year,1pct_plu,500-year
River Rch & RM= TRIB 14 TO TWELV,Reach-1,8080
     690    1110    1489     966    1927    3845    3194
Boundary for River Rch & Prof#=TRIB 14 TO TWELV,Reach-1,1
Up Type=0
Dn Type=3
Dn Slope=0.005
Boundary for River Rch & Prof#=TRIB 14 TO TWELV,Reach-1,2
Up Type=0
Dn Type=3
Dn Slope=0.005
Boundary for River Rch & Prof#=TRIB 14 TO TWELV,Reach-1,3
Up Type=0
Dn Type=3
Dn Slope=0.005
Boundary for River Rch & Prof#=TRIB 14 TO TWELV,Reach-1,4
Up Type=0
Dn Type=3
Dn Slope=0.005
Boundary for River Rch & Prof#=TRIB 14 TO TWELV,Reach-1,5
Up Type=0
Dn Type=3
Dn Slope=0.005
Boundary for River Rch & Prof#=TRIB 14 TO TWELV,Reach-1,6
Up Type=0
Dn Type=3
Dn Slope=0.005
Boundary for River Rch & Prof#=TRIB 14 TO TWELV,Reach-1,7
Up Type=0
Dn Type=3
Dn Slope=0.005

--- TRIB 14 TO TWELVEMILE CREEK.g01 (geometry) ---

Geom Title=Existing Conditions

River Reach=TRIB 14 TO TWELV,Reach-1
Reach XY= 30
      2482309.18     13544740.82      2482417.46     13544628.33
      2482332.34     13544525.10      2482427.24     13544030.93
      2482617.71     13543775.09      2482525.51     13543609.79
      2482532.98     13543121.65      2482767.19     13542931.21
      2482785.48     13542764.49      2482888.35     13542761.36
      2483011.35     13542588.26      2483134.81     13542564.49
      2483358.25     13542291.46      2483608.61     13542141.67
      2483584.32     13542068.34      2483871.24     13541673.44
      2483930.52     13541372.57      2484058.25     13541241.46
      2484181.19     13541217.14      2484286.83     13541076.62
      2484519.07     13541072.76      2484731.06     13540966.86
      2485126.62     13540478.12      2485681.19     13540517.19
      2485969.89     13540177.29      2485935.18     13540015.29
      2486219.91     13539827.31      2486185.03     13539664.94
      2486377.69     13539619.73      2486425.00     13539525.00

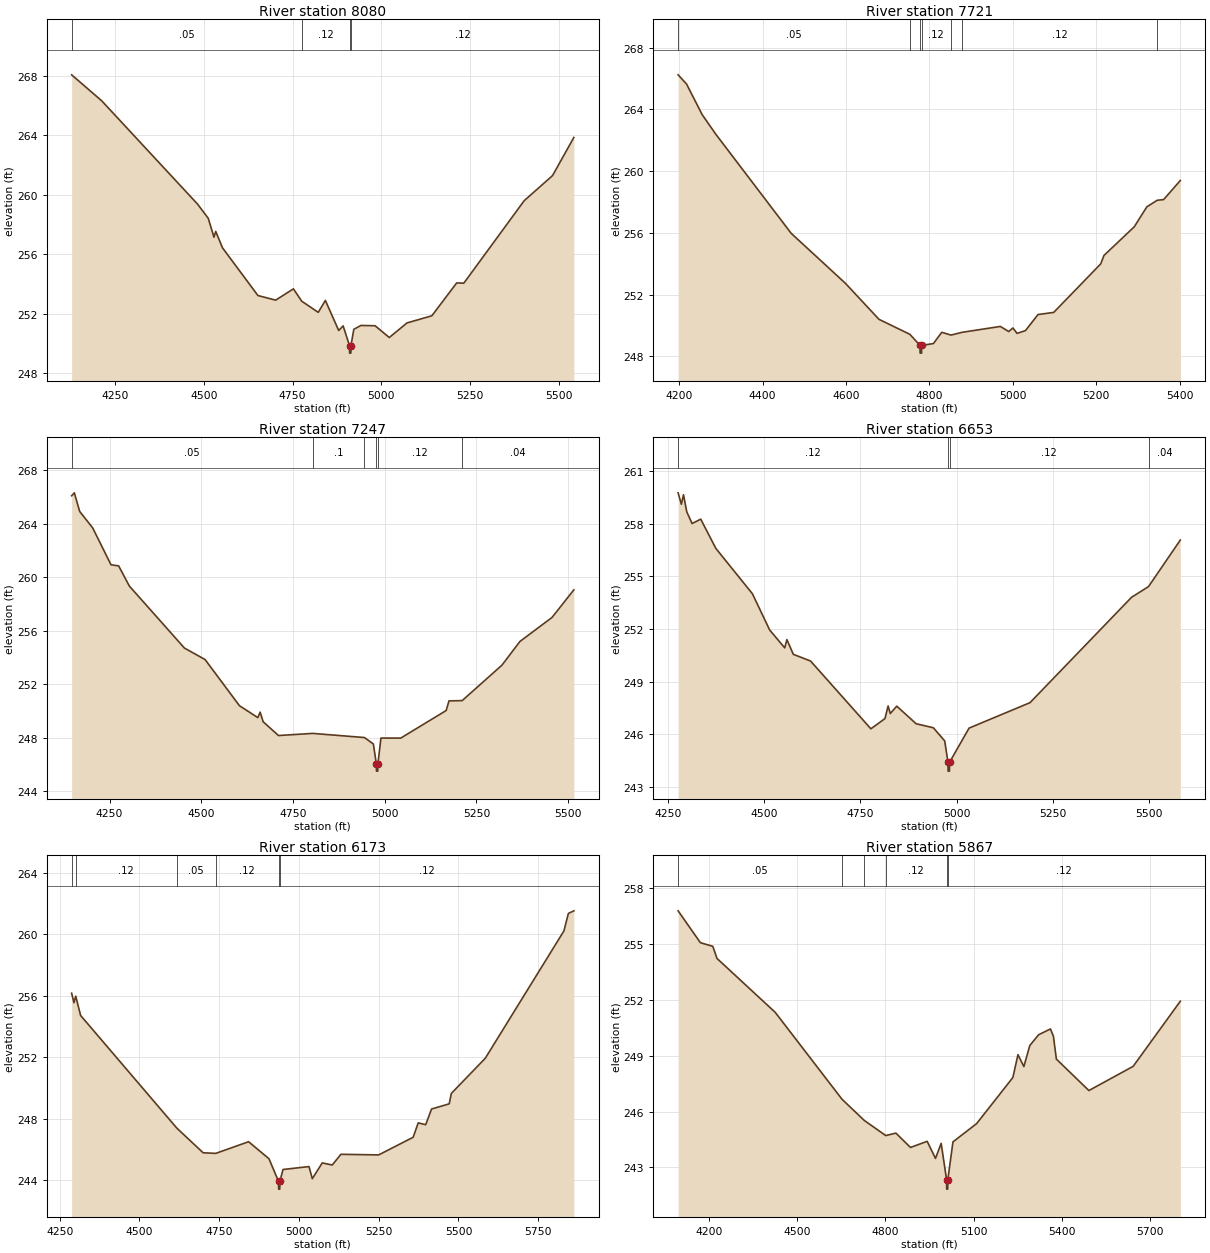
Type RM Length L Ch R = 1,8080,359,359,359
BEGIN DESCRIPTION:
TRIB 14 TO TWELVEMILE CREEK 9.0
END DESCRIPTION:
XS GIS Cut Line= 3
      2483239.86     13544696.19      2482484.94     13544684.57
      2481825.02     13544675.00
#Sta/Elev= 30
  4127.6  268.06  4212.5  266.31  4482.5  259.37  4512.5  258.42  4528.6  257.15
  4533.6  257.54  4552.5  256.44  4652.5  253.23  4702.5  252.92  4752.5  253.68
  4775.8  252.85  4822.5  252.10  4842.5  252.90  4880.1  250.88  4892.6  251.19
  4910.6  249.86  4910.8  249.36  4914.3  249.36  4914.6  249.86  4922.6  250.96
  4942.6  251.22  4982.6  251.20  5022.6  250.41  5072.6  251.39  5142.6  251.87
  5212.6  254.08  5232.6  254.06  5402.6  259.60  5482.6  261.29  5542.6  263.85
#Mann=4,-1,0
  4127.6    0.05       0  4775.8    0.12       0  4910.6    0.05       0
  4914.6    0.12       0
Bank Sta=4910.6,4914.6
Exp/Cntr=0.3,0.1

Type RM Length L Ch R = 1,7721,474,474,474
BEGIN DESCRIPTION:
TRIB 14 TO TWELVEMILE CREEK 8.0
END DESCRIPTION:
XS GIS Cut Line= 3
      2483175.04     13544425.00      2482575.00     13544375.00
      2481975.00     13544425.00
#Sta/Elev= 30
  4197.3  266.24  4217.4  265.65  4255.0  263.66  4287.7  262.39  4468.3  255.97
  4598.7  252.72  4679.0  250.39  4753.0  249.42  4777.4  248.70  4777.6  248.20
  4781.1  248.20  4781.4  248.70  4809.5  248.82  4829.5  249.55  4851.7  249.37
  4878.6  249.55  4970.0  249.93  4990.1  249.60  5000.1  249.83  5010.1  249.48
  5030.2  249.66  5060.3  250.70  5098.0  250.84  5210.8  253.99  5218.4  254.53
  5291.1  256.39  5321.2  257.68  5346.2  258.11  5361.4  258.15  5401.5  259.39
#Mann=7,-1,0
  4197.3    0.05       0  4753.0    0.12       0  4777.4    0.05       0
  4781.4    0.12       0  4851.7     0.1       0  4878.6    0.12       0
  5346.2    0.05       0
Bank Sta=4777.4,4781.4
Exp/Cntr=0.3,0.1

Type RM Length L Ch R = 1,7247,594,594,594
BEGIN DESCRIPTION:
TRIB 14 TO TWELVEMILE CREEK 7.0
END DESCRIPTION:
XS GIS Cut Line= 3
      2483175.01     13544375.01      2482575.00     13543925.00
      2481974.98     13544075.00
#Sta/Elev= 30
  4146.8  266.08  4154.1  266.30  4168.7  264.91  4204.1  263.68  4254.1  260.92
  4274.9  260.84  4304.1  259.33  4454.1  254.70  4510.4  253.84  4604.1  250.39
  4654.1  249.50  4660.4  249.91  4668.7  249.19  4710.4  248.16  4803.6  248.32
  4944.7  248.01  4969.0  247.53  4977.3  246.00  4977.5  245.50  4981.0  245.50
  4981.3  246.00  4989.6  247.97  5043.7  247.97  5167.4  250.03  5175.1  250.75
  5211.0  250.77  5319.4  253.42  5368.4  255.19  5456.0  256.99  5515.3  259.05
#Mann=6,-1,0
  4146.8    0.05       0  4803.6     0.1       0  4944.7    0.12       0
  4977.3    0.05       0  4981.3    0.12       0  5211.0    0.04       0
Bank Sta=4977.3,4981.3
Exp/Cntr=0.3,0.1

Type RM Length L Ch R = 1,6653,480,480,480
BEGIN DESCRIPTION:
TRIB 14 TO TWELVEMILE CREEK 6.0
END DESCRIPTION:
XS GIS Cut Line= 3
      2483175.00     13543725.00      2482575.00     13543425.00
      2481974.97     13543625.01
#Sta/Elev= 30
  4276.9  259.75  4285.3  259.10  4290.9  259.64  4299.3  258.67  4313.2  258.00
  4335.6  258.25  4374.7  256.59  4469.8  254.00  4514.5  251.94  4553.6  250.92
  4559.2  251.39  4576.0  250.55  4620.7  250.17  4777.2  246.31  4813.6  246.89
  4821.9  247.61  4827.5  247.18  4844.3  247.60  4894.6  246.60  4939.3  246.37
  4968.8  245.62  4977.3  244.40  4977.6  243.90  4981.1  243.90  4981.3  244.40
  5032.0  246.35  5190.2  247.80  5453.7  253.80  5497.7  254.41  5580.2  257.06
#Mann=4,-1,0
  4276.9    0.12       0  4977.3    0.05       0  4981.3    0.12       0
  5497.7    0.04       0
Bank Sta=4977.3,4981.3
Exp/Cntr=0.3,0.1

Type RM Length L Ch R = 1,6173,306,306,306
BEGIN DESCRIPTION:
TRIB 14 TO TWELVEMILE CREEK 5.0
END DESCRIPTION:
XS GIS Cut Line= 3
      2483075.03     13543525.03      2482675.00     13543025.00
      2481775.03     13543274.99
#Sta/Elev= 30
  4287.3  256.17  4294.5  255.55  4300.1  255.98  4315.4  254.72  4616.9  247.38
  4699.5  245.77  4739.1  245.73  4842.0  246.49  4906.0  245.38  4936.0  243.90
  4936.3  243.40  4939.8  243.40  4940.0  243.90  4950.0  244.68  5031.4  244.87
  5041.8  244.08  5073.0  245.11  5104.1  244.97  5131.6  245.67  5249.9  245.63
  5357.9  246.78  5373.9  247.72  5397.3  247.60  5415.5  248.62  5471.0  248.96
  5477.7  249.64  5584.1  251.93  5830.6  260.23  5844.6  261.37  5861.7  261.54
#Mann=6,-1,0
  4287.3    0.05       0  4300.1    0.12       0  4616.9    0.05       0
  4739.1    0.12       0  4936.0    0.05       0  4940.0    0.12       0
Bank Sta=4936,4940
Exp/Cntr=0.3,0.1

Type RM Length L Ch R = 1,5867,294,294,294
BEGIN DESCRIPTION:
Mapping XS 14b16cfc
END DESCRIPTION:
XS GIS Cut Line= 3
      2483414.77     13543462.11      2482796.33     13542832.42
      2481975.48     13542759.33
#Sta/Elev= 30
  4095.7  256.79  4171.3  255.08  4213.7  254.88  4227.9  254.23  4425.9  251.33
  4652.8  246.66  4728.6  245.52  4801.3  244.71  4835.9  244.84  4885.5  244.07
  4942.1  244.40  4970.4  243.48  4989.7  244.29  5008.2  242.33  5008.4  241.83
  5011.9  241.83  5012.2  242.33  5029.8  244.37  5110.1  245.35  5233.4  247.83
  5250.7  249.06  5270.8  248.42  5290.9  249.55  5321.0  250.13  5361.1  250.44
  5371.2  250.05  5381.2  248.82  5491.7  247.13  5642.2  248.43  5802.4  251.93
#Mann=6,-1,0
  4095.7    0.05       0  4652.8    0.12       0  4728.6    0.05       0
  4801.3    0.12       0  5008.2    0.05       0  5012.2    0.12       0
Bank Sta=5008.2,5012.2
Exp/Cntr=0.3,0.1

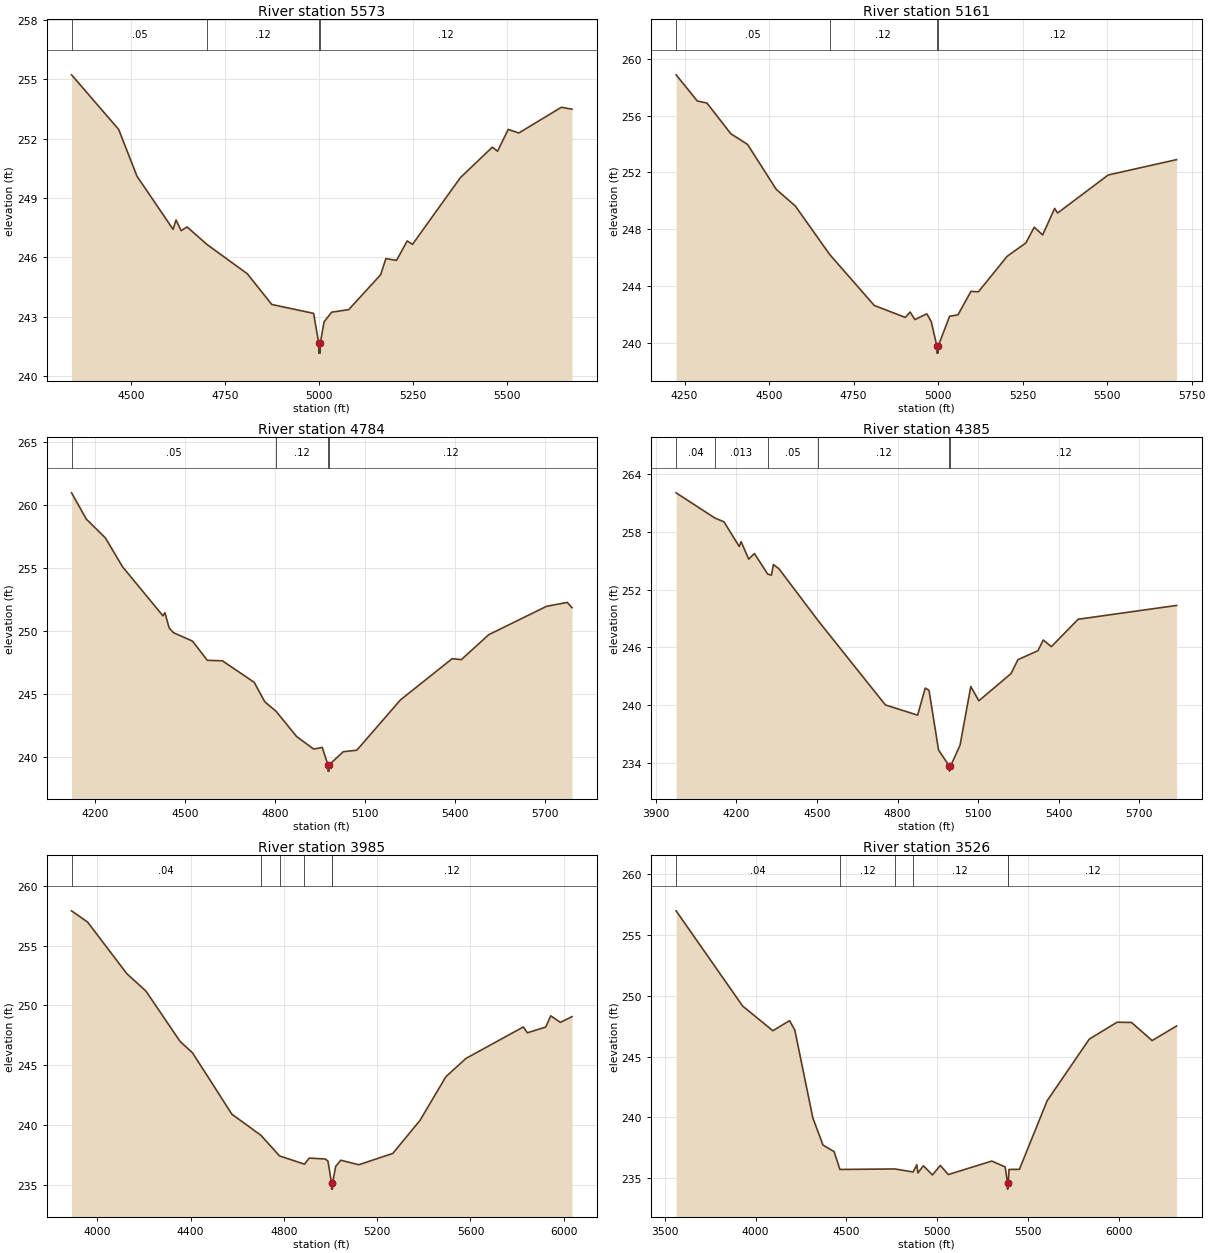
Type RM Length L Ch R = 1,5573,412,412,412
BEGIN DESCRIPTION:
TRIB 14 TO TWELVEMILE CREEK 4.0
END DESCRIPTION:
XS GIS Cut Line= 3
      2483525.00     13543025.00      2482925.00     13542675.00
      2482475.02     13542225.02
#Sta/Elev= 30
  4342.1  255.23  4467.4  252.47  4516.2  250.10  4612.1  247.42  4620.0  247.89
  4633.6  247.35  4649.3  247.54  4702.5  246.65  4809.7  245.17  4874.6  243.62
  4985.9  243.17  4999.6  241.66  4999.8  241.16  5003.3  241.16  5003.6  241.66
  5013.6  242.74  5033.8  243.23  5079.2  243.36  5164.0  245.12  5178.1  245.94
  5206.4  245.85  5234.7  246.83  5248.9  246.66  5376.1  250.03  5461.0  251.57
  5475.1  251.37  5503.4  252.47  5531.7  252.29  5644.8  253.59  5673.1  253.49
#Mann=4,-1,0
  4342.1    0.05       0  4702.5    0.12       0  4999.6    0.05       0
  5003.6    0.12       0
Bank Sta=4999.6,5003.6
Exp/Cntr=0.3,0.1

Type RM Length L Ch R = 1,5161,377,377,377
BEGIN DESCRIPTION:
Mapping XS aeef9f5e
END DESCRIPTION:
XS GIS Cut Line= 3
      2483774.61     13542984.25      2483251.73     13542450.11
      2482565.83     13542191.50
#Sta/Elev= 30
  4224.9  258.86  4287.7  257.02  4316.0  256.88  4386.8  254.72  4436.2  253.97
  4521.1  250.81  4577.6  249.64  4679.3  246.23  4811.1  242.65  4903.0  241.81
  4917.1  242.19  4931.2  241.66  4966.5  242.06  4979.6  241.52  4996.3  239.80
  4996.6  239.30  5000.1  239.30  5000.3  239.80  5033.9  241.89  5058.7  241.99
  5097.1  243.64  5119.1  243.61  5204.4  246.11  5259.4  247.04  5284.3  248.15
  5309.2  247.61  5344.7  249.47  5353.6  249.15  5503.2  251.82  5705.4  252.90
#Mann=4,-1,0
  4224.9    0.05       0  4679.3    0.12       0  4996.3    0.05       0
  5000.3    0.12       0
Bank Sta=4996.3,5000.3
Exp/Cntr=0.3,0.1

Type RM Length L Ch R = 1,4784,399,399,399
BEGIN DESCRIPTION:
Mapping XS 2816c486
END DESCRIPTION:
XS GIS Cut Line= 3
      2484173.77     13542815.56      2483465.37     13542191.49
      2482751.39     13542067.81
#Sta/Elev= 30
  4122.3  260.93  4171.7  258.84  4235.3  257.35  4292.2  255.07  4426.9  251.18
  4433.6  251.42  4447.8  250.21  4462.0  249.84  4525.6  249.17  4574.9  247.65
  4625.2  247.61  4731.4  245.90  4766.5  244.36  4804.9  243.59  4872.8  241.60
  4929.7  240.61  4958.2  240.74  4977.1  239.36  4977.3  238.86  4980.8  238.86
  4981.1  239.36  5028.4  240.40  5073.5  240.52  5219.0  244.51  5391.5  247.78
  5421.8  247.70  5513.3  249.68  5706.1  251.93  5775.1  252.24  5791.0  251.82
#Mann=4,-1,0
  4122.3    0.05       0  4804.9    0.12       0  4977.1    0.05       0
  4981.1    0.12       0
Bank Sta=4977.1,4981.1
Exp/Cntr=0.3,0.1

Type RM Length L Ch R = 1,4385,400,400,400
BEGIN DESCRIPTION:
Mapping XS 581911d1
END DESCRIPTION:
XS GIS Cut Line= 3
      2484415.53     13542646.89      2483679.01     13541921.62
      2482848.50     13541916.01
#Sta/Elev= 30
  3975.2  262.02  4119.5  259.41  4153.7  259.01  4210.3  256.46  4217.3  256.96
  4245.6  255.15  4266.9  255.73  4316.4  253.60  4330.4  253.49  4337.6  254.59
  4358.7  254.14  4504.6  248.76  4754.7  240.04  4874.9  238.98  4903.2  241.79
  4917.3  241.55  4952.8  235.37  4993.2  233.68  4993.4  233.18  4997.2  233.68
  5032.9  235.87  5072.9  241.95  5102.9  240.47  5222.9  243.29  5248.4  244.73
  5322.9  245.66  5342.9  246.77  5372.9  246.08  5472.9  248.92  5839.4  250.35
#Mann=6,-1,0
  3975.2    0.04       0  4119.5   0.013       0  4316.4    0.05       0
  4504.6    0.12       0  4993.2    0.05       0  4997.2    0.12       0
Bank Sta=4993.2,4997.2
Exp/Cntr=0.3,0.1

Type RM Length L Ch R = 1,3985,459,459,459
BEGIN DESCRIPTION:
Mapping XS 1574666d
END DESCRIPTION:
XS GIS Cut Line= 4
      2484572.95     13542410.76      2484218.75     13541769.82
      2483701.50     13541533.69      2482909.35     13541825.83
#Sta/Elev= 30
  3890.0  257.92  3958.8  256.98  4127.2  252.65  4208.5  251.21  4355.1  246.99
  4409.0  246.02  4577.4  240.89  4701.6  239.13  4781.6  237.40  4888.3  236.71
  4908.8  237.22  4977.9  237.14  4989.2  236.96  5004.4  235.12  5004.7  234.62
  5008.2  234.62  5008.4  235.12  5022.2  236.52  5044.1  237.04  5121.1  236.66
  5267.0  237.61  5383.4  240.37  5494.5  244.03  5580.5  245.56  5826.7  248.20
  5843.8  247.71  5922.6  248.19  5943.9  249.13  5985.3  248.58  6035.2  249.06
#Mann=6,-1,0
  3890.0    0.04       0  4701.6    0.12       0  4781.6   0.013       0
  4888.3    0.12       0  5004.4    0.05       0  5008.4    0.12       0
Bank Sta=5004.4,5008.4
Exp/Cntr=0.3,0.1

Type RM Length L Ch R = 1,3526,0,0,0
BEGIN DESCRIPTION:
Mapping XS 70e27d8c
END DESCRIPTION:
XS GIS Cut Line= 5
      2484696.63     13542416.33      2484505.48     13541516.82
      2484021.97     13541196.36      2483448.50     13541387.51
      2482859.07     13541668.19
#Sta/Elev= 30
  3561.7  257.00  3928.2  249.16  4094.7  247.13  4186.7  247.96  4215.6  247.19
  4314.8  239.96  4370.7  237.72  4432.0  237.18  4464.1  235.71  4766.6  235.75
  4867.5  235.50  4887.8  236.10  4893.8  235.42  4923.9  236.01  4973.8  235.26
  5017.2  236.04  5061.4  235.29  5300.6  236.40  5374.4  235.92  5387.7  234.59
  5387.9  234.09  5391.7  234.59  5395.5  235.71  5452.9  235.72  5605.8  241.37
  5837.9  246.44  5990.9  247.83  6070.5  247.81  6184.1  246.32  6318.7  247.52
#Mann=6,-1,0
  3561.7    0.04       0  4464.1    0.12       0  4766.6   0.013       0
  4867.5    0.12       0  5387.7    0.05       0  5391.7    0.12       0
Bank Sta=5387.7,5391.7
Exp/Cntr=0.3,0.1

Chan Stop Cuts=-1