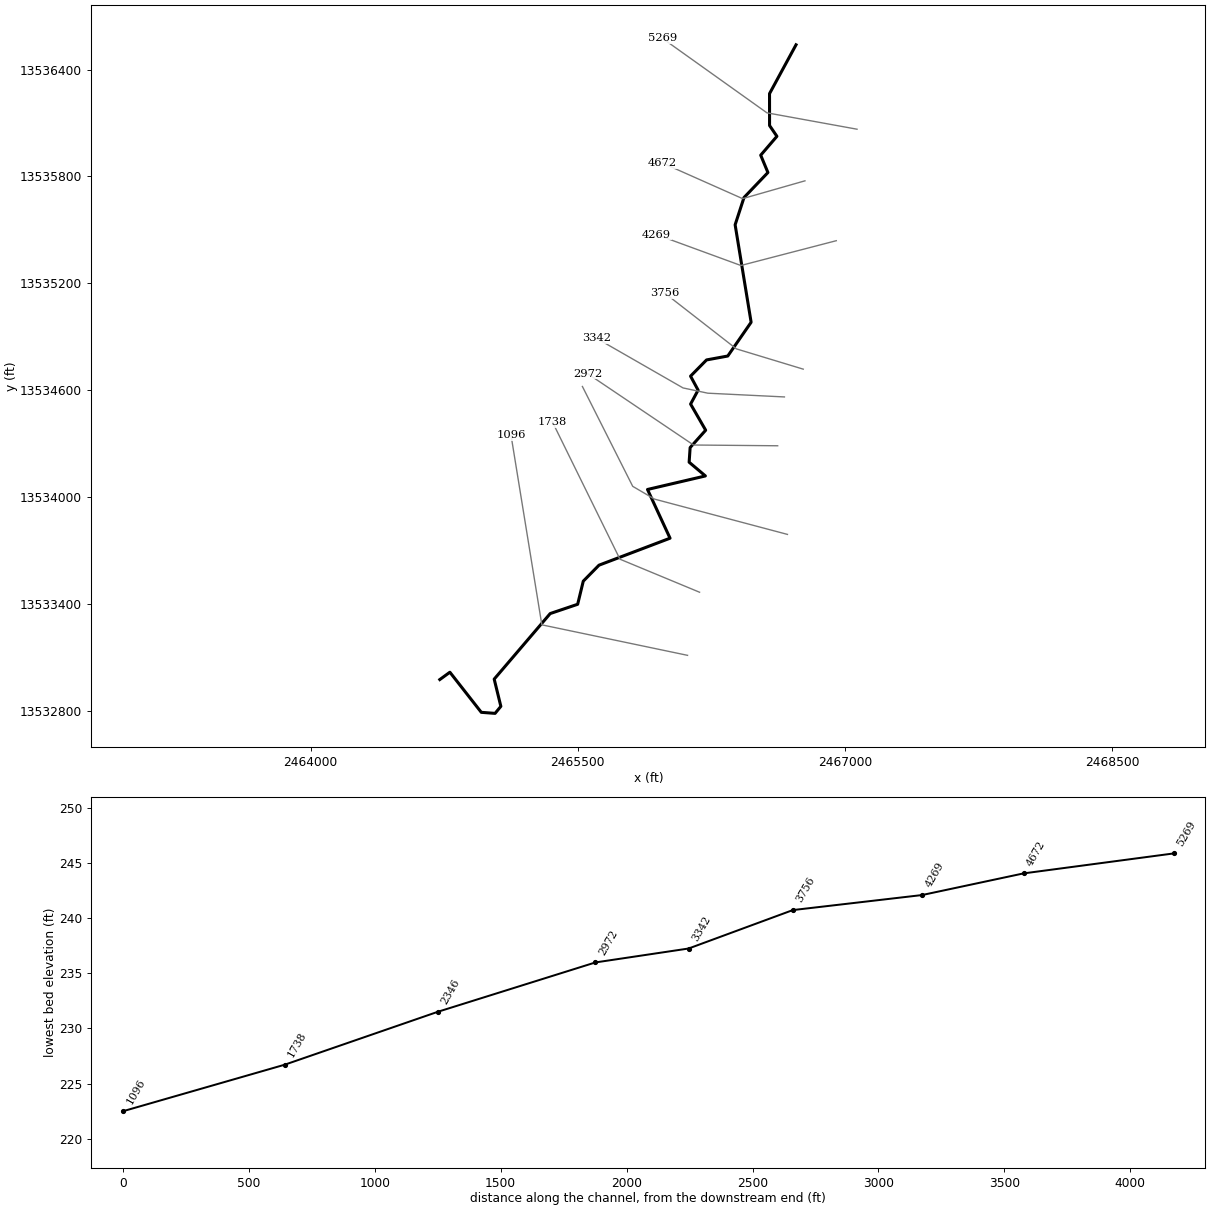
--- TRIB 15 TO FIFTEENMILE CREEK.prj (project) ---

Proj Title=TRIB 15 TO FIFTEENMILE CREEK Base Level Engineering
Current Plan=p01
Default Exp/Contr=0.3,0.1
English Units
Geom File=g01
Flow File=f01
Plan File=p01
Y Axis Title=Elevation
X Axis Title(PF)=Main Channel Distance
X Axis Title(XS)=Station
BEGIN DESCRIPTION:
TRIB 15 TO FIFTEENMILE CREEK
END DESCRIPTION:
DSS Export Rating Curves= 0
DSS Export Rating Curve Sorted= 0
DSS Export Volume Flow Curves= 0
DXF OffsetX= 0
DXF OffsetY= 0
DXF ScaleX= 1
DXF ScaleY= 10

--- TRIB 15 TO FIFTEENMILE CREEK.p01 (plan) ---

Plan Title=Multiple Run
Short Identifier=Multiple
Geom File=g01
Flow File=f01
Subcritical Flow
K Sum by GR= 0
Std Step Tol= 0.01
Critical Tol= 0.01
Num of Std Step Trials= 20
Max Error Tol= 0.3
Flow Tol Ratio= 0.001
Split Flow NTrial= 30
Split Flow Tol= 0.02
Split Flow Ratio= 0.02
Log Output Level= 0
Friction Slope Method= 1
Unsteady Friction Slope Method= 2
Unsteady Bridges Friction Slope Method= 1
Parabolic Critical Depth
Global Vel Dist=  1 , 1 , 1
Global Log Level= 0
CheckData=True
Encroach Param= -1, 0, 0, 0
BEGIN DESCRIPTION:
Multiple Run
END DESCRIPTION:

--- TRIB 15 TO FIFTEENMILE CREEK.f01 (steady flow) ---

Flow Title=Multiple
Number of Profiles=7
Profile Names=10-year,25-year,50-year,1pct_min,100-year,1pct_plu,500-year
River Rch & RM= TRIB 15 TO FIFTE,Reach-1,5269
     643    1036    1390     902    1800    3592    2991
Boundary for River Rch & Prof#=TRIB 15 TO FIFTE,Reach-1,1
Up Type=0
Dn Type=3
Dn Slope=0.005
Boundary for River Rch & Prof#=TRIB 15 TO FIFTE,Reach-1,2
Up Type=0
Dn Type=3
Dn Slope=0.005
Boundary for River Rch & Prof#=TRIB 15 TO FIFTE,Reach-1,3
Up Type=0
Dn Type=3
Dn Slope=0.005
Boundary for River Rch & Prof#=TRIB 15 TO FIFTE,Reach-1,4
Up Type=0
Dn Type=3
Dn Slope=0.005
Boundary for River Rch & Prof#=TRIB 15 TO FIFTE,Reach-1,5
Up Type=0
Dn Type=3
Dn Slope=0.005
Boundary for River Rch & Prof#=TRIB 15 TO FIFTE,Reach-1,6
Up Type=0
Dn Type=3
Dn Slope=0.005
Boundary for River Rch & Prof#=TRIB 15 TO FIFTE,Reach-1,7
Up Type=0
Dn Type=3
Dn Slope=0.005

--- TRIB 15 TO FIFTEENMILE CREEK.g01 (geometry) ---

Geom Title=Existing Conditions

River Reach=TRIB 15 TO FIFTE,Reach-1
Reach XY= 30
      2466725.00     13536538.71      2466576.20     13536264.50
      2466576.39     13536085.43      2466617.67     13536024.90
      2466526.68     13535918.95      2466567.18     13535821.59
      2466432.86     13535681.17      2466383.08     13535528.30
      2466472.86     13534980.97      2466341.79     13534791.44
      2466222.54     13534769.48      2466132.81     13534678.42
      2466175.22     13534600.00      2466133.07     13534521.69
      2466217.70     13534374.92      2466130.40     13534277.37
      2466124.89     13534195.26      2466216.23     13534118.15
      2465891.09     13534042.17      2466017.67     13533768.62
      2465618.81     13533617.15      2465530.52     13533527.44
      2465499.01     13533397.67      2465344.73     13533345.51
      2465030.40     13532977.43      2465067.77     13532824.62
      2465035.39     13532785.16      2464957.97     13532791.05
      2464781.67     13533016.23      2464725.00     13532975.00

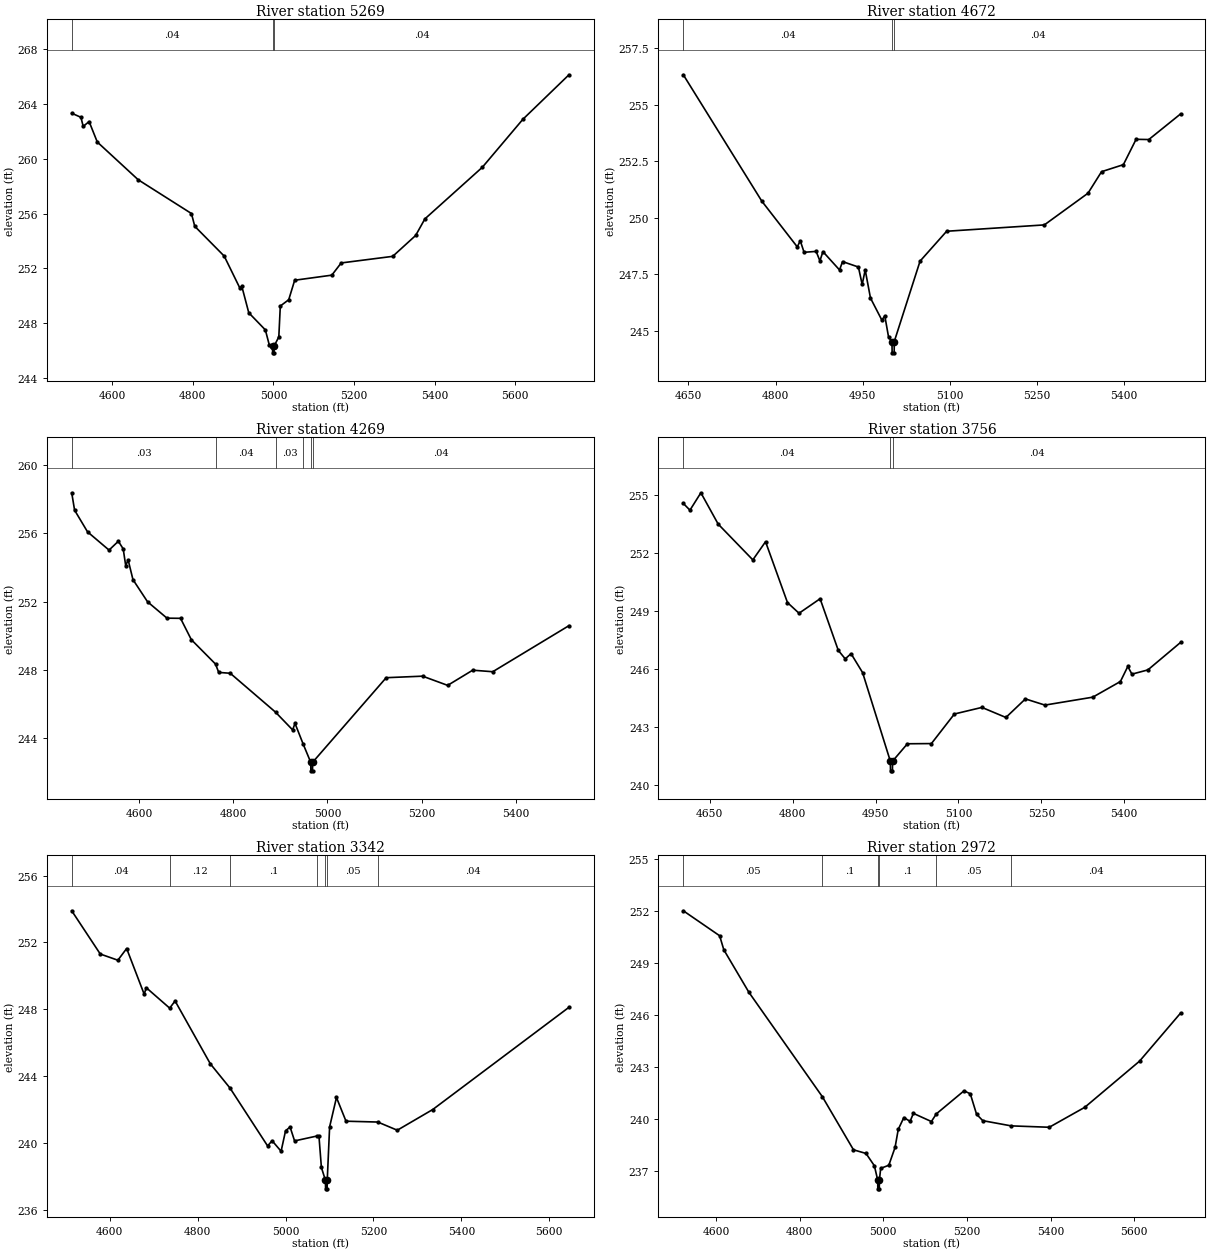
Type RM Length L Ch R = 1,5269,597,597,597
BEGIN DESCRIPTION:
TRIB 15 TO FIFTEENMILE CREEK 9.0
END DESCRIPTION:
XS GIS Cut Line= 3
      2467067.49     13536064.80      2466561.56     13536156.79
      2465975.00     13536575.00
#Sta/Elev= 30
  4499.2  263.31  4522.1  263.01  4527.7  262.35  4542.4  262.70  4562.7  261.21
  4664.3  258.46  4796.5  256.00  4804.7  255.07  4877.8  252.90  4916.5  250.58
  4921.6  250.69  4938.8  248.77  4980.0  247.52  4989.6  246.44  4997.8  246.35
  4998.0  245.85  5001.5  245.85  5001.8  246.35  5013.4  247.01  5017.1  249.26
  5038.0  249.72  5052.8  251.14  5145.0  251.51  5168.3  252.40  5296.2  252.88
  5353.1  254.40  5376.1  255.61  5518.7  259.37  5619.5  262.87  5733.8  266.11
#Mann=3,-1,0
  4499.2    0.04       0  4997.8    0.04       0  5001.8    0.04       0
Bank Sta=4997.8,5001.8
Exp/Cntr=0.3,0.1

Type RM Length L Ch R = 1,4672,403,403,403
BEGIN DESCRIPTION:
TRIB 15 TO FIFTEENMILE CREEK 8.0
END DESCRIPTION:
XS GIS Cut Line= 3
      2466775.04     13535775.01      2466425.00     13535675.00
      2465974.99     13535875.01
#Sta/Elev= 30
  4641.2  256.32  4776.4  250.74  4837.5  248.72  4842.7  248.99  4849.2  248.48
  4870.0  248.52  4876.5  248.10  4881.7  248.51  4910.3  247.70  4915.5  248.07
  4942.8  247.83  4949.3  247.06  4954.5  247.70  4963.6  246.46  4983.1  245.49
  4988.3  245.67  4994.8  244.73  5000.6  244.54  5000.9  244.04  5004.4  244.04
  5004.6  244.54  5049.0  248.09  5094.8  249.41  5263.1  249.69  5338.3  251.09
  5361.6  252.04  5399.2  252.35  5421.1  253.47  5443.0  253.46  5497.7  254.59
#Mann=3,-1,0
  4641.2    0.04       0  5000.6    0.04       0  5004.6    0.04       0
Bank Sta=5000.6,5004.6
Exp/Cntr=0.3,0.1

Type RM Length L Ch R = 1,4269,513,513,513
BEGIN DESCRIPTION:
Mapping XS 9f68bd5c
END DESCRIPTION:
XS GIS Cut Line= 3
      2466950.93     13535438.87      2466415.33     13535299.69
      2465942.97     13535472.61
#Sta/Elev= 30
  4456.6  258.38  4462.7  257.36  4490.2  256.09  4535.9  255.02  4555.7  255.54
  4566.0  255.09  4571.3  254.11  4576.5  254.44  4586.7  253.29  4617.7  251.99
  4659.0  251.03  4687.8  251.02  4710.7  249.77  4762.1  248.34  4768.9  247.85
  4793.4  247.80  4889.6  245.52  4925.9  244.48  4931.0  244.86  4948.6  243.63
  4964.4  242.58  4964.7  242.08  4968.2  242.08  4968.4  242.58  5124.7  247.54
  5202.0  247.63  5255.3  247.09  5308.5  247.98  5351.1  247.89  5513.0  250.59
#Mann=6,-1,0
  4456.6    0.03       0  4762.1    0.04       0  4889.6    0.03       0
  4948.6    0.04       0  4964.4    0.04       0  4968.4    0.04       0
Bank Sta=4964.4,4968.4
Exp/Cntr=0.3,0.1

Type RM Length L Ch R = 1,3756,414,414,414
BEGIN DESCRIPTION:
Mapping XS f1f2af39
END DESCRIPTION:
XS GIS Cut Line= 3
      2466765.39     13534717.72      2466390.02     13534831.59
      2465989.70     13535143.42
#Sta/Elev= 30
  4602.2  254.55  4614.2  254.20  4634.0  255.10  4665.3  253.48  4728.0  251.63
  4751.0  252.57  4790.7  249.42  4811.6  248.87  4849.7  249.62  4882.6  246.95
  4895.2  246.51  4905.7  246.78  4926.6  245.80  4976.8  241.22  4977.1  240.72
  4980.6  240.72  4980.8  241.22  5007.7  242.12  5051.1  242.13  5092.7  243.66
  5142.5  244.00  5185.9  243.48  5221.2  244.44  5256.5  244.12  5343.1  244.53
  5393.1  245.34  5406.5  246.12  5413.9  245.72  5442.8  245.94  5501.9  247.36
#Mann=3,-1,0
  4602.2    0.04       0  4976.8    0.04       0  4980.8    0.04       0
Bank Sta=4976.8,4980.8
Exp/Cntr=0.3,0.1

Type RM Length L Ch R = 1,3342,370,370,370
BEGIN DESCRIPTION:
Mapping XS e84a77c9
END DESCRIPTION:
XS GIS Cut Line= 4
      2466659.90     13534561.70      2466229.77     13534582.78
      2466090.61     13534612.30      2465606.22     13534890.30
#Sta/Elev= 30
  4513.4  253.89  4578.4  251.30  4618.4  250.93  4638.4  251.63  4678.2  248.90
  4683.2  249.28  4736.3  248.06  4748.6  248.49  4828.7  244.73  4873.7  243.27
  4959.1  239.81  4969.4  240.12  4989.8  239.49  5000.0  240.72  5010.3  240.94
  5020.5  240.11  5072.6  240.41  5076.0  240.38  5081.5  238.52  5090.8  237.74
  5091.0  237.24  5094.5  237.24  5094.8  237.74  5100.2  240.95  5115.8  242.71
  5137.5  241.29  5209.8  241.24  5254.2  240.75  5334.9  241.99  5644.8  248.11
#Mann=7,-1,0
  4513.4    0.04       0  4736.3    0.12       0  4873.7     0.1       0
  5072.6    0.05       0  5090.8    0.05       0  5094.8    0.05       0
  5209.8    0.04       0
Bank Sta=5090.8,5094.8
Exp/Cntr=0.3,0.1

Type RM Length L Ch R = 1,2972,626,626,626
BEGIN DESCRIPTION:
Mapping XS cd51d074
END DESCRIPTION:
XS GIS Cut Line= 3
      2466621.93     13534287.58      2466149.65     13534291.80
      2465555.03     13534692.43
#Sta/Elev= 30
  4521.7  252.01  4608.6  250.57  4618.6  249.76  4678.6  247.31  4854.3  241.29
  4928.7  238.23  4958.7  238.02  4978.7  237.31  4986.7  236.48  4986.9  235.98
  4990.4  235.98  4990.7  236.48  4993.8  237.16  5013.2  237.34  5028.2  238.37
  5035.8  239.41  5049.2  240.09  5064.1  239.87  5072.0  240.33  5115.1  239.86
  5126.8  240.30  5193.1  241.63  5208.1  241.46  5223.1  240.28  5238.0  239.91
  5305.8  239.61  5397.0  239.53  5481.9  240.68  5612.9  243.34  5711.0  246.11
#Mann=6,-1,0
  4521.7    0.05       0  4854.3     0.1       0  4986.7    0.05       0
  4990.7     0.1       0  5126.8    0.05       0  5305.8    0.04       0
Bank Sta=4986.7,4990.7
Exp/Cntr=0.3,0.1

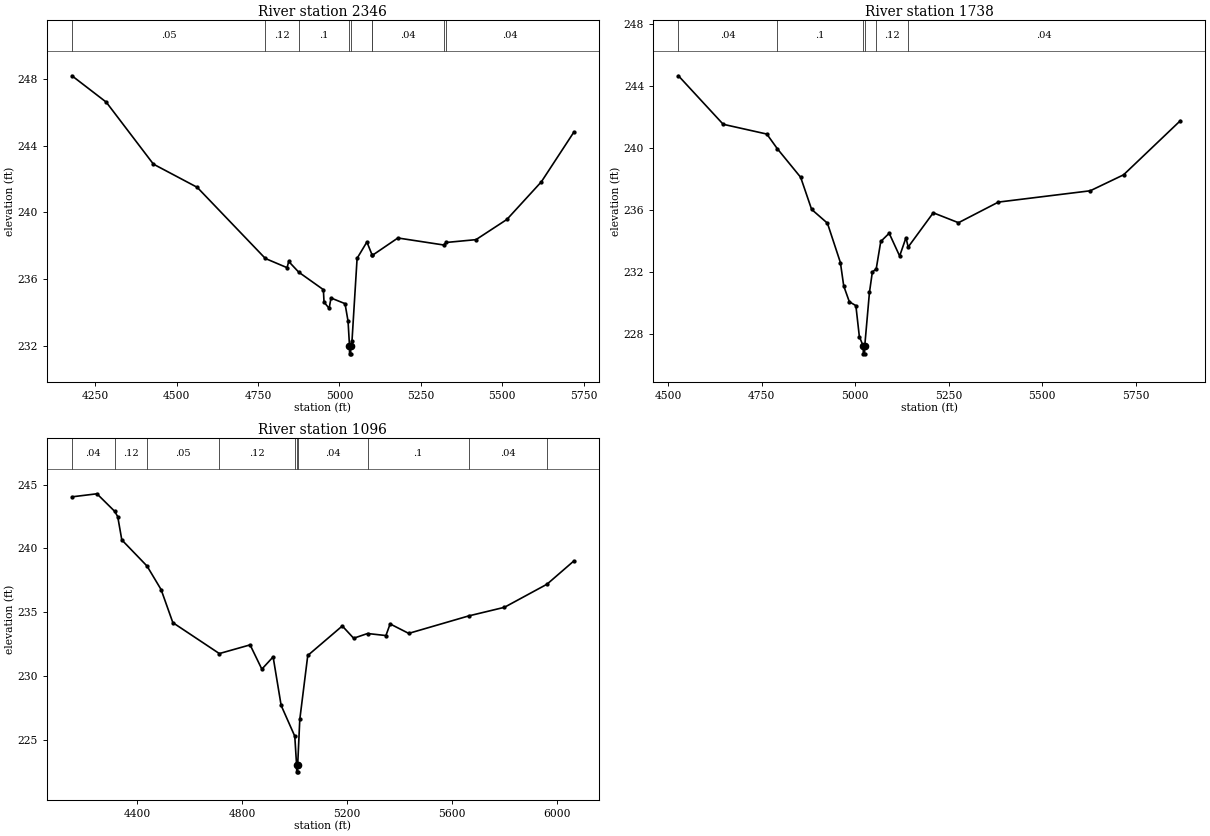
Type RM Length L Ch R = 1,2346,608,608,608
BEGIN DESCRIPTION:
Mapping XS 9eb2ab88
END DESCRIPTION:
XS GIS Cut Line= 4
      2466676.81     13533789.96      2465930.36     13533988.17
      2465808.06     13534059.86      2465525.70     13534620.37
#Sta/Elev= 30
  4178.4  248.19  4283.7  246.61  4428.6  242.89  4563.1  241.50  4772.5  237.23
  4839.1  236.68  4844.3  237.05  4875.0  236.41  4950.7  235.36  4952.7  234.61
  4968.4  234.24  4974.2  234.86  5017.2  234.52  5026.5  233.47  5030.9  232.01
  5031.1  231.51  5034.6  231.51  5034.9  232.01  5038.7  232.31  5054.3  237.24
  5084.4  238.22  5100.8  237.42  5101.3  237.42  5179.6  238.46  5320.1  238.04
  5327.5  238.19  5419.5  238.36  5514.3  239.57  5620.3  241.83  5720.1  244.81
#Mann=9,-1,0
  4178.4    0.05       0  4772.5    0.12       0  4875.0     0.1       0
  5030.9    0.05       0  5034.9     0.1       0  5100.8    0.05       0
  5101.3    0.04       0  5320.1    0.05       0  5327.5    0.04       0
Bank Sta=5030.9,5034.9
Exp/Cntr=0.3,0.1

Type RM Length L Ch R = 1,1738,642,642,642
BEGIN DESCRIPTION:
Mapping XS 3d6ef5f2
END DESCRIPTION:
XS GIS Cut Line= 3
      2466183.41     13533465.23      2465736.37     13533650.80
      2465357.46     13534421.24
#Sta/Elev= 30
  4527.0  244.66  4646.8  241.53  4763.5  240.90  4791.7  239.95  4854.0  238.11
  4883.3  236.04  4925.6  235.15  4960.3  232.61  4969.2  231.10  4984.2  230.08
  5001.7  229.83  5011.0  227.83  5021.4  227.22  5021.6  226.72  5025.1  226.72
  5025.4  227.22  5038.0  230.68  5045.8  232.00  5056.1  232.20  5068.3  233.97
  5090.8  234.50  5118.8  233.03  5135.7  234.21  5141.6  233.61  5208.7  235.82
  5276.2  235.18  5382.9  236.51  5628.6  237.24  5717.8  238.27  5869.6  241.76
#Mann=6,-1,0
  4527.0    0.04       0  4791.7     0.1       0  5021.4    0.05       0
  5025.4     0.1       0  5056.1    0.12       0  5141.6    0.04       0
Bank Sta=5021.4,5025.4
Exp/Cntr=0.3,0.1

Type RM Length L Ch R = 1,1096,0,0,0
BEGIN DESCRIPTION:
TRIB 15 TO FIFTEENMILE CREEK 2.0
END DESCRIPTION:
XS GIS Cut Line= 3
      2466115.90     13533111.01      2465297.88     13533282.22
      2465124.89     13534346.61
#Sta/Elev= 30
  4150.3  244.04  4245.6  244.28  4313.1  242.91  4324.9  242.49  4340.4  240.67
  4436.7  238.62  4490.3  236.78  4535.1  234.19  4712.4  231.77  4829.7  232.45
  4874.5  230.55  4917.5  231.51  4948.1  227.71  5000.1  225.30  5007.1  223.01
  5007.4  222.51  5010.9  222.51  5011.1  223.01  5019.2  226.61  5049.6  231.62
  5181.3  233.93  5224.6  232.97  5277.8  233.34  5347.7  233.18  5363.7  234.09
  5434.6  233.35  5663.8  234.72  5799.4  235.39  5962.0  237.20  6064.4  239.02
#Mann=10,-1,0
  4150.3    0.04       0  4313.1    0.12       0  4436.7    0.05       0
  4712.4    0.12       0  5000.1    0.04       0  5007.1    0.05       0
  5011.1    0.04       0  5277.8     0.1       0  5663.8    0.04       0
  5962.0    0.05       0
Bank Sta=5007.1,5011.1
Exp/Cntr=0.3,0.1

Chan Stop Cuts=-1