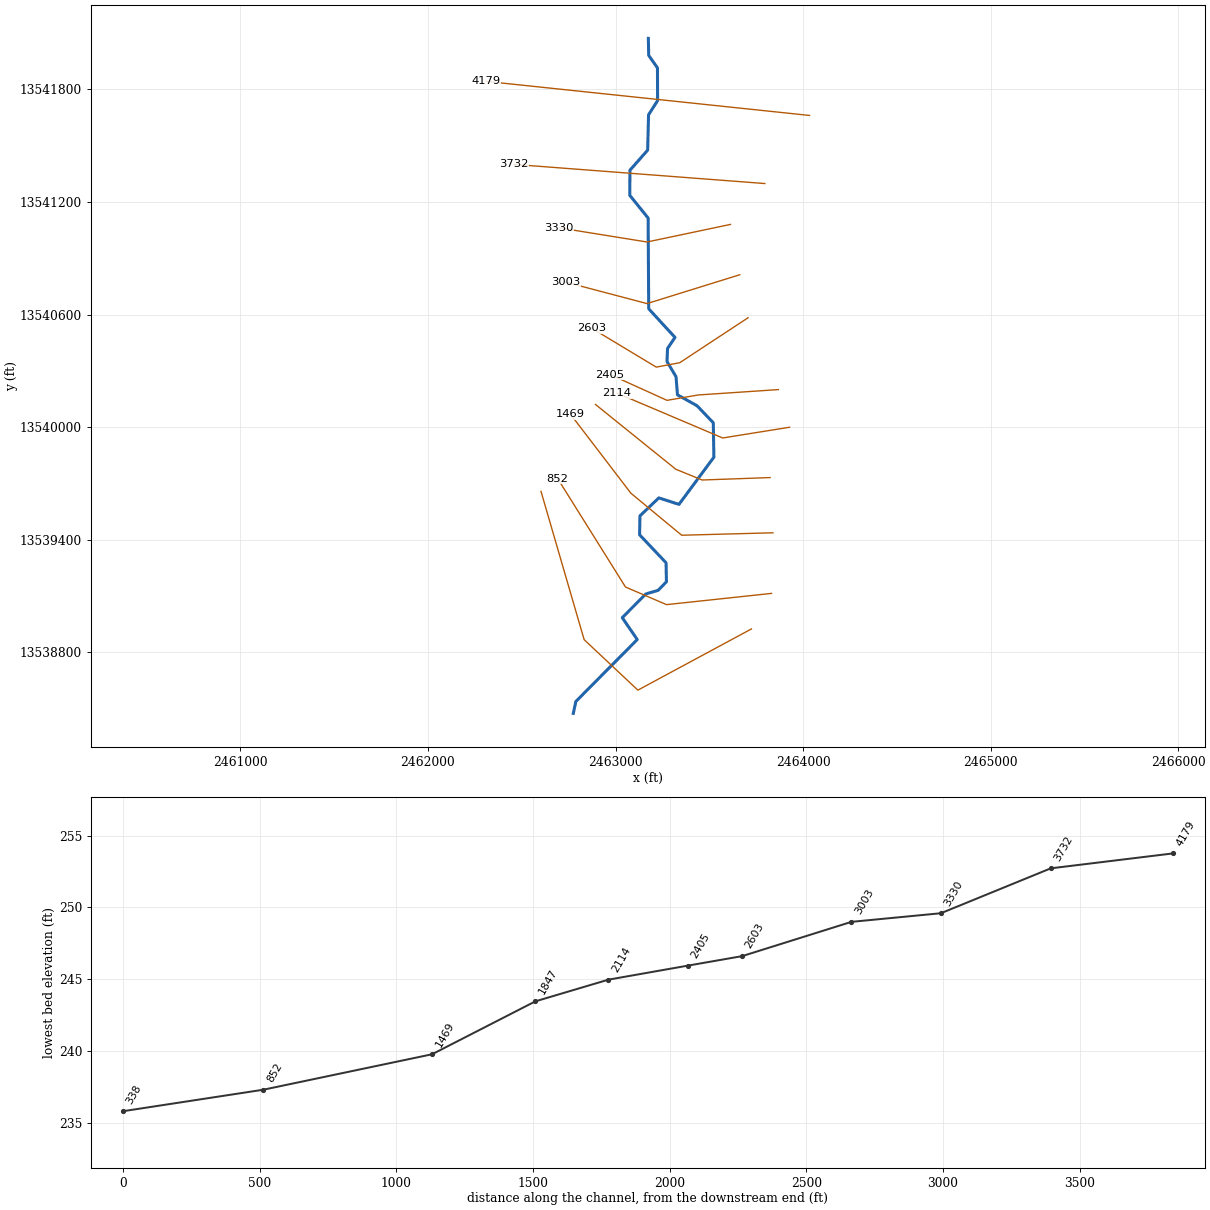
--- TRIB 16 TO FIFTEENMILE CREEK.prj (project) ---

Proj Title=TRIB 16 TO FIFTEENMILE CREEK Base Level Engineering
Current Plan=p01
Default Exp/Contr=0.3,0.1
English Units
Geom File=g01
Flow File=f01
Plan File=p01
Y Axis Title=Elevation
X Axis Title(PF)=Main Channel Distance
X Axis Title(XS)=Station
BEGIN DESCRIPTION:
TRIB 16 TO FIFTEENMILE CREEK
END DESCRIPTION:
DSS Export Rating Curves= 0
DSS Export Rating Curve Sorted= 0
DSS Export Volume Flow Curves= 0
DXF OffsetX= 0
DXF OffsetY= 0
DXF ScaleX= 1
DXF ScaleY= 10

--- TRIB 16 TO FIFTEENMILE CREEK.p01 (plan) ---

Plan Title=Multiple Run
Short Identifier=Multiple
Geom File=g01
Flow File=f01
Subcritical Flow
K Sum by GR= 0
Std Step Tol= 0.01
Critical Tol= 0.01
Num of Std Step Trials= 20
Max Error Tol= 0.3
Flow Tol Ratio= 0.001
Split Flow NTrial= 30
Split Flow Tol= 0.02
Split Flow Ratio= 0.02
Log Output Level= 0
Friction Slope Method= 1
Unsteady Friction Slope Method= 2
Unsteady Bridges Friction Slope Method= 1
Parabolic Critical Depth
Global Vel Dist=  1 , 1 , 1
Global Log Level= 0
CheckData=True
Encroach Param= -1, 0, 0, 0
BEGIN DESCRIPTION:
Multiple Run
END DESCRIPTION:

--- TRIB 16 TO FIFTEENMILE CREEK.f01 (steady flow) ---

Flow Title=Multiple
Number of Profiles=7
Profile Names=10-year,25-year,50-year,1pct_min,100-year,1pct_plu,500-year
River Rch & RM= TRIB 16 TO FIFTE,Reach-1,4179
     738    1203    1627    1065    2125    4239    3588
River Rch & RM= TRIB 16 TO FIFTE,Reach-1,3732
     916    1509    2054    1353    2699    5385    4613
Boundary for River Rch & Prof#=TRIB 16 TO FIFTE,Reach-1,1
Up Type=0
Dn Type=3
Dn Slope=0.005
Boundary for River Rch & Prof#=TRIB 16 TO FIFTE,Reach-1,2
Up Type=0
Dn Type=3
Dn Slope=0.005
Boundary for River Rch & Prof#=TRIB 16 TO FIFTE,Reach-1,3
Up Type=0
Dn Type=3
Dn Slope=0.005
Boundary for River Rch & Prof#=TRIB 16 TO FIFTE,Reach-1,4
Up Type=0
Dn Type=3
Dn Slope=0.005
Boundary for River Rch & Prof#=TRIB 16 TO FIFTE,Reach-1,5
Up Type=0
Dn Type=3
Dn Slope=0.005
Boundary for River Rch & Prof#=TRIB 16 TO FIFTE,Reach-1,6
Up Type=0
Dn Type=3
Dn Slope=0.005
Boundary for River Rch & Prof#=TRIB 16 TO FIFTE,Reach-1,7
Up Type=0
Dn Type=3
Dn Slope=0.005

--- TRIB 16 TO FIFTEENMILE CREEK.g01 (geometry) ---

Geom Title=Existing Conditions

River Reach=TRIB 16 TO FIFTE,Reach-1
Reach XY= 30
      2463175.00     13542071.97      2463177.09     13541980.87
      2463223.80     13541914.50      2463224.48     13541740.22
      2463176.22     13541664.49      2463171.45     13541476.47
      2463077.06     13541369.14      2463076.04     13541235.44
      2463173.94     13541114.56      2463177.06     13540630.85
      2463317.20     13540478.42      2463277.37     13540419.11
      2463274.61     13540350.00      2463322.64     13540269.02
      2463330.42     13540172.33      2463434.68     13540114.22
      2463521.47     13540023.55      2463524.62     13539840.16
      2463338.40     13539588.53      2463231.04     13539623.35
      2463130.39     13539527.44      2463128.46     13539426.50
      2463269.61     13539277.42      2463271.63     13539176.28
      2463227.58     13539130.74      2463161.80     13539111.36
      2463035.96     13538985.00      2463116.03     13538868.33
      2462788.47     13538538.27      2462775.00     13538475.00

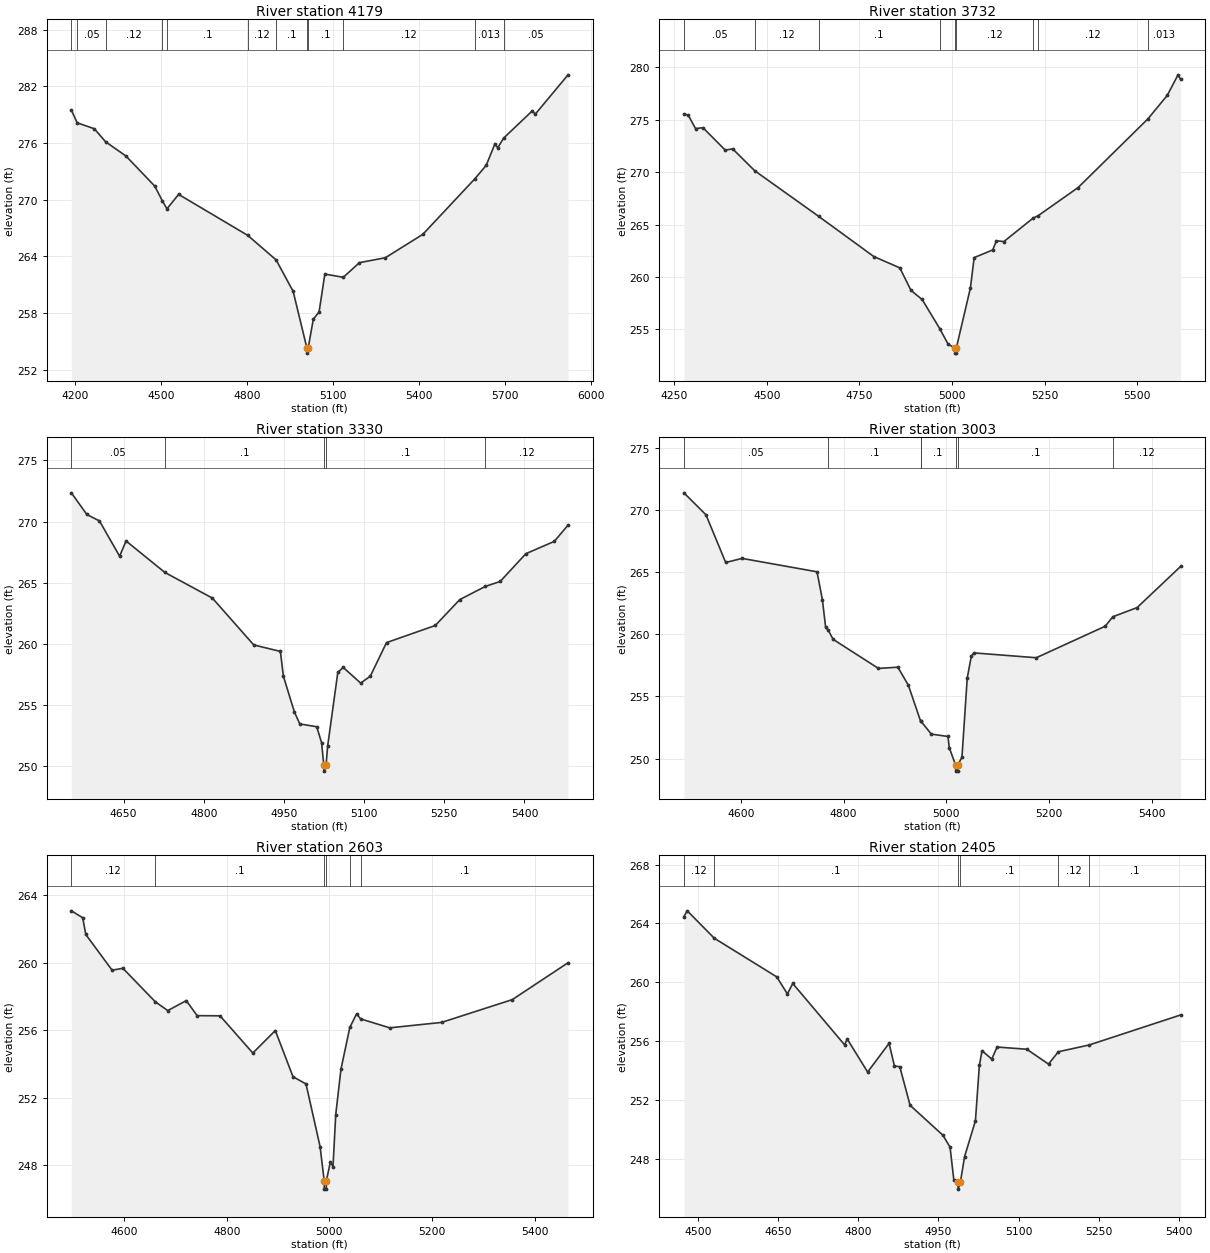
Type RM Length L Ch R = 1,4179,447,447,447
BEGIN DESCRIPTION:
LGII4591
END DESCRIPTION:
XS GIS Cut Line= 2
      2464034.53     13541661.08      2462311.05     13541842.50
#Sta/Elev= 30
  4186.0  279.50  4206.2  278.15  4266.0  277.52  4305.4  276.14  4376.6  274.63
  4477.1  271.44  4503.7  269.87  4519.5  269.04  4560.2  270.57  4801.3  266.23
  4900.4  263.63  4959.8  260.30  5008.1  254.26  5008.3  253.76  5012.1  254.26
  5030.2  257.35  5050.3  258.12  5070.4  262.13  5134.8  261.79  5191.0  263.34
  5281.5  263.86  5412.3  266.34  5594.7  272.25  5633.5  273.65  5663.6  275.90
  5673.7  275.50  5693.9  276.52  5794.4  279.42  5804.5  279.06  5919.0  283.23
#Mann=12,-1,0
  4186.0   0.013       0  4206.2    0.05       0  4305.4    0.12       0
  4503.7    0.05       0  4519.5     0.1       0  4801.3    0.12       0
  4900.4     0.1       0  5008.1    0.05       0  5012.1     0.1       0
  5134.8    0.12       0  5594.7   0.013       0  5693.9    0.05       0
Bank Sta=5008.1,5012.1
Exp/Cntr=0.3,0.1

Type RM Length L Ch R = 1,3732,402,402,402
BEGIN DESCRIPTION:
LGII4590
END DESCRIPTION:
XS GIS Cut Line= 2
      2463796.35     13541298.24      2462459.24     13541400.23
#Sta/Elev= 30
  4276.4  275.55  4287.8  275.45  4307.8  274.16  4327.9  274.24  4388.1  272.10
  4408.1  272.22  4467.7  270.13  4639.8  265.79  4789.2  261.94  4859.4  260.86
  4889.5  258.71  4919.6  257.84  4967.0  255.07  4989.8  253.57  5007.8  253.22
  5008.0  252.72  5011.7  252.72  5012.0  253.22  5050.0  258.95  5060.0  261.84
  5110.2  262.57  5120.2  263.45  5140.3  263.37  5219.6  265.62  5232.8  265.84
  5340.8  268.53  5529.3  275.09  5581.5  277.33  5610.5  279.29  5617.4  278.86
#Mann=9,-1,0
  4276.4    0.05       0  4467.7    0.12       0  4639.8     0.1       0
  4967.0    0.12       0  5007.8    0.05       0  5012.0    0.12       0
  5219.6     0.1       0  5232.8    0.12       0  5529.3   0.013       0
Bank Sta=5007.8,5012
Exp/Cntr=0.3,0.1

Type RM Length L Ch R = 1,3330,327,327,327
BEGIN DESCRIPTION:
Mapping XS 17f8f044
END DESCRIPTION:
XS GIS Cut Line= 3
      2463613.24     13541080.48      2463167.94     13540986.73
      2462699.64     13541062.18
#Sta/Elev= 30
  4552.2  272.35  4581.1  270.58  4604.8  270.05  4642.4  267.17  4654.6  268.41
  4727.1  265.84  4816.1  263.74  4893.5  259.91  4943.3  259.38  4948.9  257.36
  4969.4  254.44  4979.6  253.45  5011.3  253.22  5020.4  251.92  5024.5  250.09
  5024.8  249.59  5028.8  250.09  5031.7  251.62  5050.8  257.67  5060.9  258.07
  5093.5  256.79  5111.5  257.35  5141.9  260.10  5233.1  261.50  5279.0  263.62
  5327.0  264.70  5354.6  265.10  5402.6  267.37  5455.9  268.38  5481.6  269.71
#Mann=5,-1,0
  4552.2    0.05       0  4727.1     0.1       0  5024.5    0.05       0
  5028.8     0.1       0  5327.0    0.12       0
Bank Sta=5024.5,5028.8
Exp/Cntr=0.3,0.1

Type RM Length L Ch R = 1,3003,400,400,400
BEGIN DESCRIPTION:
Mapping XS 0a989a50
END DESCRIPTION:
XS GIS Cut Line= 3
      2463662.71     13540812.24      2463167.94     13540658.60
      2462733.06     13540773.18
#Sta/Elev= 30
  4488.8  271.40  4531.8  269.63  4570.2  265.79  4602.2  266.12  4748.2  265.04
  4758.7  262.78  4765.0  260.56  4769.6  260.37  4779.6  259.60  4867.9  257.26
  4905.7  257.36  4926.2  255.90  4949.9  253.03  4950.5  253.02  4970.9  251.97
  5003.4  251.78  5005.8  250.89  5018.1  249.49  5018.4  248.99  5022.1  248.99
  5022.4  249.49  5030.6  250.10  5040.9  256.49  5048.9  258.25  5054.0  258.51
  5175.4  258.12  5309.8  260.66  5324.6  261.42  5371.9  262.16  5456.6  265.47
#Mann=7,-1,0
  4488.8    0.05       0  4769.6     0.1       0  4949.9    0.05       0
  4950.5     0.1       0  5018.1    0.05       0  5022.4     0.1       0
  5324.6    0.12       0
Bank Sta=5018.1,5022.4
Exp/Cntr=0.3,0.1

Type RM Length L Ch R = 1,2603,198,198,198
BEGIN DESCRIPTION:
Mapping XS 074fbb08
END DESCRIPTION:
XS GIS Cut Line= 4
      2463706.99     13540583.08      2463342.42     13540343.50
      2463217.42     13540320.06      2462871.07     13540528.39
#Sta/Elev= 30
  4497.3  263.06  4519.4  262.65  4525.4  261.66  4576.6  259.55  4597.7  259.66
  4660.8  257.68  4685.1  257.16  4721.2  257.75  4742.3  256.86  4786.9  256.85
  4850.8  254.65  4894.6  255.98  4929.0  253.25  4954.4  252.82  4981.8  249.12
  4989.8  247.10  4990.1  246.60  4993.9  246.60  4994.1  247.10  5001.9  248.21
  5007.0  247.93  5012.3  251.00  5022.5  253.69  5039.7  256.16  5053.0  256.97
  5060.7  256.67  5117.4  256.14  5218.5  256.46  5356.4  257.81  5464.9  259.99
#Mann=6,-1,0
  4497.3    0.12       0  4660.8     0.1       0  4989.8    0.05       0
  4994.1     0.1       0  5039.7    0.12       0  5060.7     0.1       0
Bank Sta=4989.8,4994.1
Exp/Cntr=0.3,0.1

Type RM Length L Ch R = 1,2405,291,291,291
BEGIN DESCRIPTION:
Mapping XS 568b14d3
END DESCRIPTION:
XS GIS Cut Line= 4
      2463868.47     13540200.27      2463441.38     13540171.62
      2463274.71     13540142.98      2462971.17     13540280.48
#Sta/Elev= 30
  4473.2  264.47  4479.5  264.86  4530.0  263.00  4647.1  260.37  4667.1  259.21
  4677.1  259.92  4774.2  255.75  4779.2  256.14  4817.4  253.90  4857.5  255.85
  4867.6  254.31  4877.6  254.26  4896.9  251.64  4958.5  249.60  4971.8  248.79
  4978.8  246.58  4986.6  246.44  4986.9  245.94  4991.2  246.44  4999.0  248.15
  5019.3  250.59  5026.7  254.36  5031.7  255.35  5049.8  254.78  5059.9  255.60
  5115.5  255.45  5156.2  254.44  5174.7  255.28  5232.4  255.74  5403.6  257.78
#Mann=6,-1,0
  4473.2    0.12       0  4530.0     0.1       0  4986.6    0.05       0
  4991.2     0.1       0  5174.7    0.12       0  5232.4     0.1       0
Bank Sta=4986.6,4991.2
Exp/Cntr=0.3,0.1

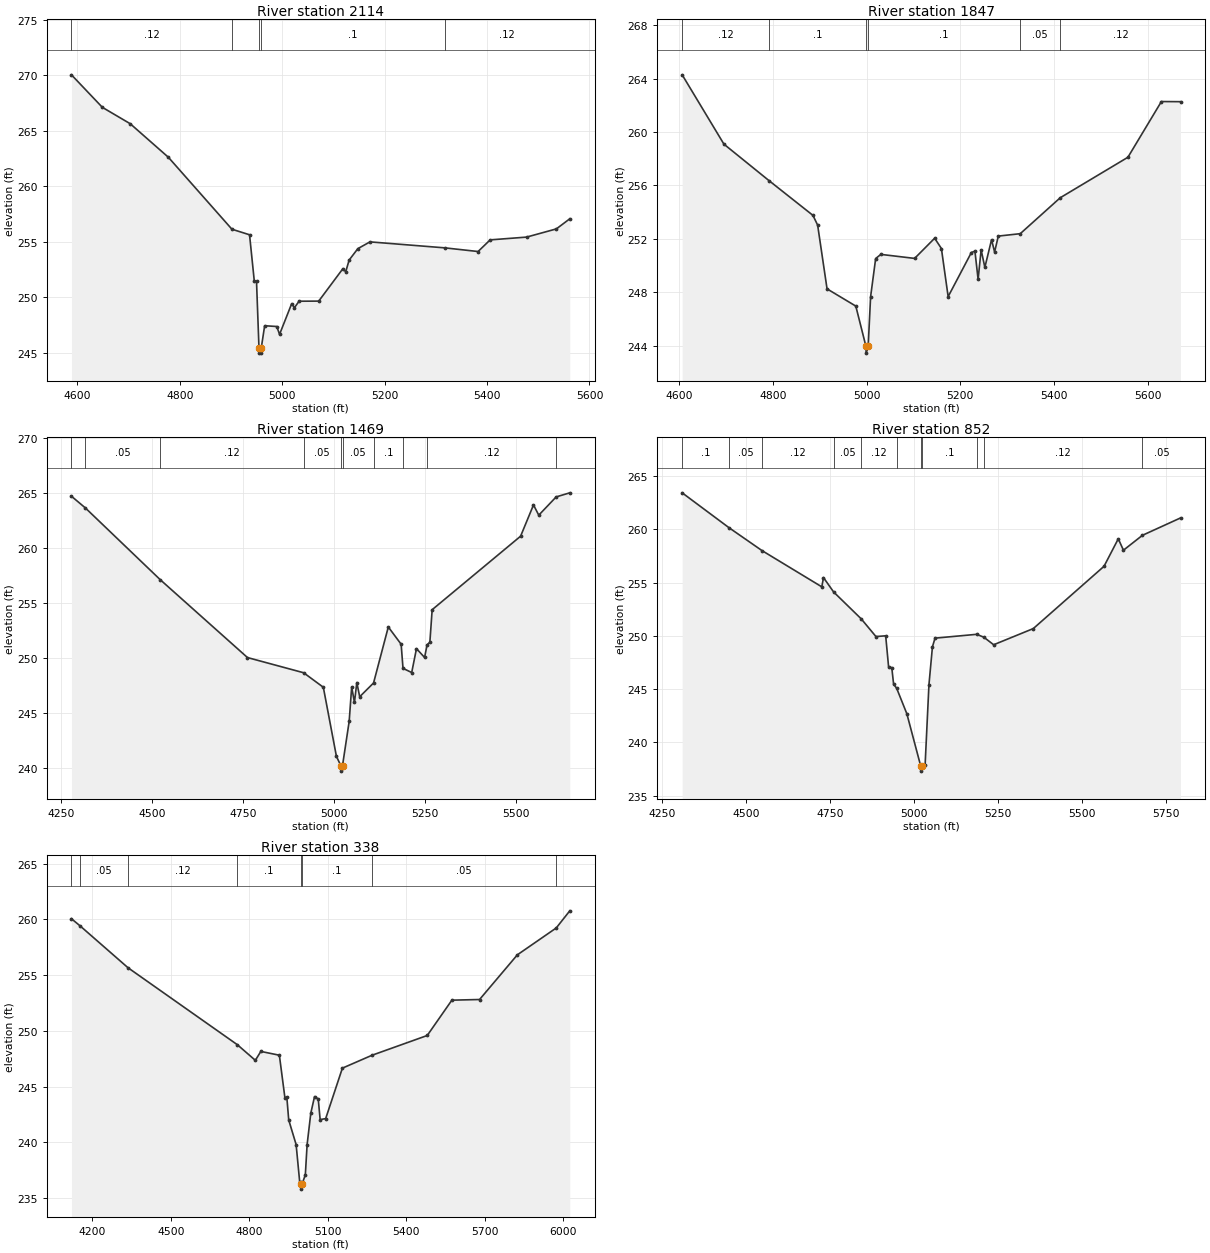
Type RM Length L Ch R = 1,2114,267,267,267
BEGIN DESCRIPTION:
Mapping XS 41497f6b
END DESCRIPTION:
XS GIS Cut Line= 3
      2463928.37     13539999.75      2463571.59     13539942.46
      2463008.28     13540181.28
#Sta/Elev= 30
  4588.4  270.05  4648.7  267.12  4703.2  265.64  4777.6  262.62  4901.8  256.13
  4936.2  255.63  4945.5  251.44  4949.8  251.44  4954.6  245.46  4954.9  244.96
  4958.9  244.96  4959.2  245.46  4965.7  247.43  4989.4  247.36  4994.8  246.65
  5018.5  249.42  5023.9  249.06  5032.9  249.64  5071.3  249.65  5118.6  252.58
  5124.0  252.29  5130.7  253.35  5147.7  254.38  5171.4  254.99  5317.7  254.45
  5382.5  254.12  5406.1  255.17  5477.2  255.42  5535.4  256.16  5561.6  257.07
#Mann=5,-1,0
  4588.4    0.12       0  4901.8     0.1       0  4954.6    0.05       0
  4959.2     0.1       0  5317.7    0.12       0
Bank Sta=4954.6,4959.2
Exp/Cntr=0.3,0.1

Type RM Length L Ch R = 1,1847,378,378,378
BEGIN DESCRIPTION:
Mapping XS 508ef700
END DESCRIPTION:
XS GIS Cut Line= 4
      2463824.15     13539731.52      2463462.21     13539718.50
      2463321.59     13539775.79      2462893.24     13540121.07
#Sta/Elev= 30
  4606.1  264.28  4695.3  259.09  4791.6  256.36  4885.4  253.76  4895.4  253.03
  4915.5  248.26  4976.9  246.97  4998.6  243.95  4998.9  243.45  5003.3  243.95
  5008.5  247.67  5019.3  250.53  5030.4  250.84  5102.5  250.54  5145.3  252.05
  5159.7  251.28  5174.1  247.68  5223.7  250.98  5231.3  251.08  5238.1  248.97
  5244.5  251.18  5252.5  249.87  5266.8  251.94  5273.3  251.02  5281.2  252.21
  5328.1  252.39  5413.5  255.08  5558.0  258.11  5629.5  262.28  5670.3  262.27
#Mann=6,-1,0
  4606.1    0.12       0  4791.6     0.1       0  4998.6    0.05       0
  5003.3     0.1       0  5328.1    0.05       0  5413.5    0.12       0
Bank Sta=4998.6,5003.3
Exp/Cntr=0.3,0.1

Type RM Length L Ch R = 1,1469,617,617,617
BEGIN DESCRIPTION:
Mapping XS 391bcb97
END DESCRIPTION:
XS GIS Cut Line= 4
      2463839.85     13539437.25      2463352.84     13539424.23
      2463082.00     13539648.19      2462759.57     13540069.43
#Sta/Elev= 30
  4278.9  264.74  4317.0  263.68  4522.7  257.16  4762.5  250.08  4916.8  248.70
  4970.9  247.38  5006.9  241.10  5018.9  240.26  5019.3  239.76  5023.6  240.26
  5041.9  244.28  5048.8  247.41  5056.4  246.00  5062.9  247.81  5070.8  246.52
  5108.9  247.77  5149.4  252.86  5184.7  251.29  5189.8  249.10  5213.7  248.72
  5226.8  250.89  5249.1  250.09  5256.0  251.24  5263.6  251.47  5269.9  254.43
  5512.9  261.11  5548.3  263.95  5562.8  263.02  5610.6  264.68  5648.0  265.05
#Mann=10,-1,0
  4278.9    0.12       0  4317.0    0.05       0  4522.7    0.12       0
  4916.8    0.05       0  5018.9    0.05       0  5023.6    0.05       0
  5108.9     0.1       0  5189.8    0.05       0  5256.0    0.12       0
  5610.6    0.03       0
Bank Sta=5018.9,5023.6
Exp/Cntr=0.3,0.1

Type RM Length L Ch R = 1,852,514,514,514
BEGIN DESCRIPTION:
Mapping XS ca6550f7
END DESCRIPTION:
XS GIS Cut Line= 4
      2463831.99     13539114.33      2463272.11     13539054.44
      2463053.36     13539148.19      2462691.36     13539726.34
#Sta/Elev= 30
  4309.0  263.43  4447.7  260.17  4546.3  258.01  4724.6  254.60  4729.6  255.47
  4759.7  254.12  4842.0  251.59  4885.7  249.93  4914.7  250.00  4923.3  247.11
  4932.9  247.00  4938.3  245.46  4947.4  245.07  4977.7  242.68  5018.8  237.79
  5019.2  237.29  5023.6  237.79  5032.1  237.88  5043.5  245.41  5053.9  248.97
  5061.6  249.78  5185.4  250.14  5206.8  249.87  5236.1  249.16  5354.1  250.68
  5564.6  256.53  5607.0  259.11  5622.4  258.04  5678.9  259.44  5792.2  261.07
#Mann=11,-1,0
  4309.0     0.1       0  4447.7    0.05       0  4546.3    0.12       0
  4759.7    0.05       0  4842.0    0.12       0  4947.4     0.1       0
  5018.8    0.05       0  5023.6     0.1       0  5185.4    0.05       0
  5206.8    0.12       0  5678.9    0.05       0
Bank Sta=5018.8,5023.6
Exp/Cntr=0.3,0.1

Type RM Length L Ch R = 1,338,0,0,0
BEGIN DESCRIPTION:
TRIB 16 TO FIFTEENMILE CREEK 1.0
END DESCRIPTION:
XS GIS Cut Line= 4
      2463724.97     13538924.99      2463119.20     13538598.80
      2462832.74     13538867.89      2462602.70     13539657.83
#Sta/Elev= 30
  4120.7  260.06  4153.6  259.42  4336.8  255.66  4754.6  248.75  4823.2  247.35
  4844.2  248.15  4915.0  247.81  4936.5  243.93  4943.4  244.07  4950.7  242.00
  4979.0  239.79  4992.8  236.40  4997.6  236.29  4998.0  235.79  5002.4  236.29
  5014.2  237.07  5021.0  239.79  5035.2  242.62  5049.4  244.10  5063.5  243.88
  5070.8  242.03  5091.9  242.12  5155.8  246.65  5269.3  247.81  5479.9  249.58
  5574.0  252.75  5679.8  252.81  5824.2  256.82  5972.7  259.23  6024.5  260.77
#Mann=8,-1,0
  4120.7    0.12       0  4153.6    0.05       0  4336.8    0.12       0
  4754.6     0.1       0  4997.6    0.05       0  5002.4     0.1       0
  5269.3    0.05       0  5972.7    0.03       0
Bank Sta=4997.6,5002.4
Exp/Cntr=0.3,0.1

Chan Stop Cuts=-1