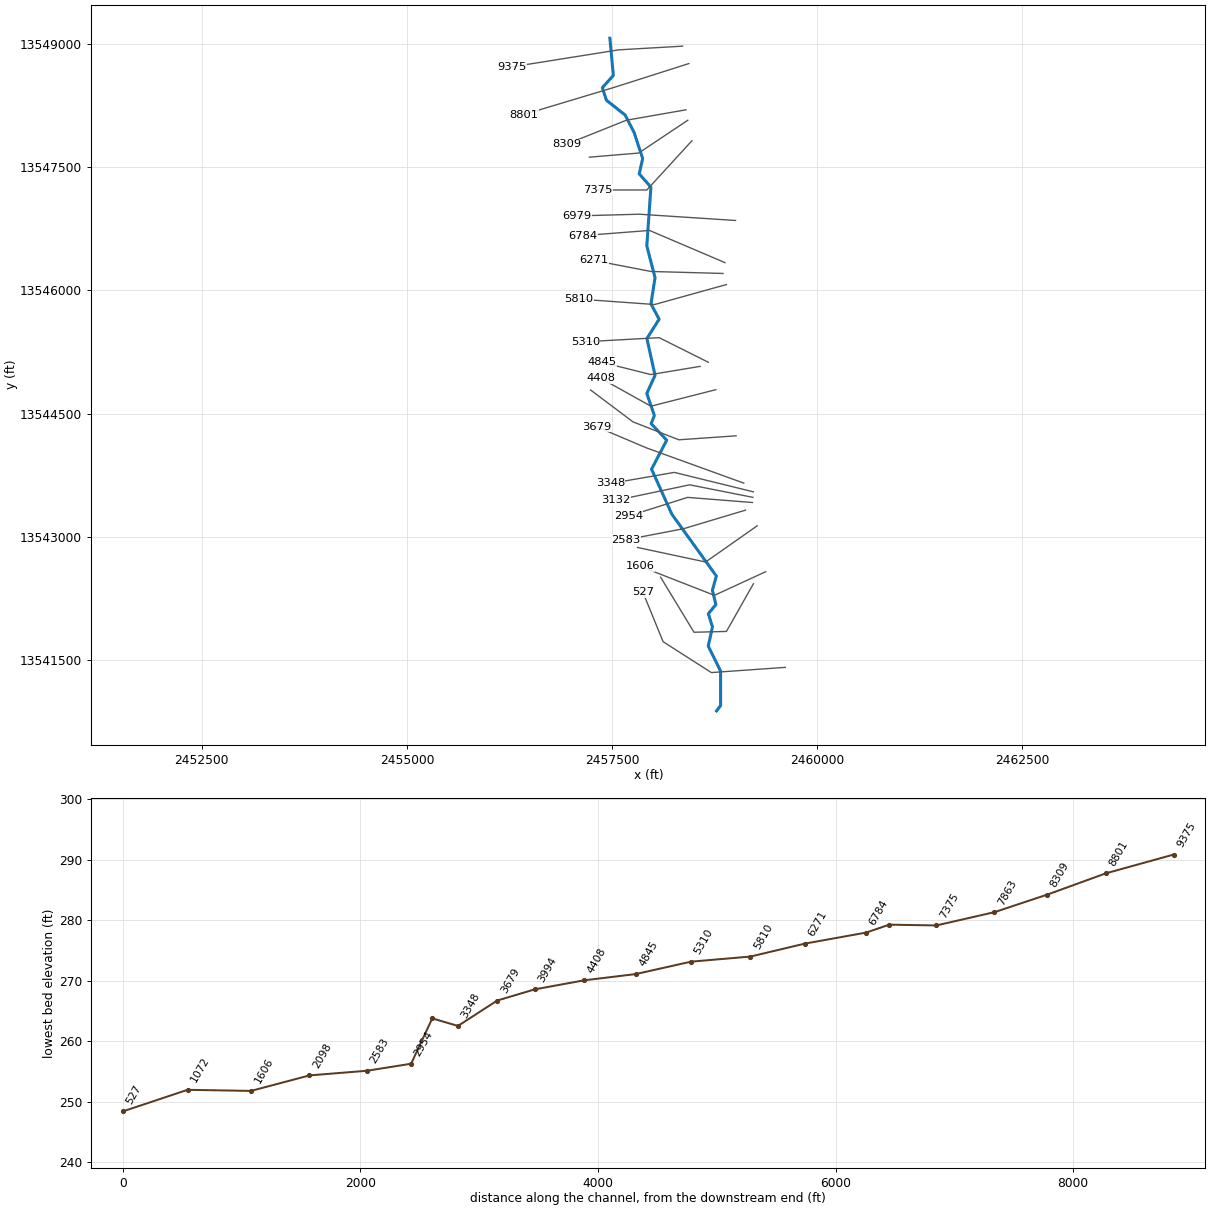
--- TRIB 17 TO FIFTEENMILE CREEK.prj (project) ---

Proj Title=TRIB 17 TO FIFTEENMILE CREEK Base Level Engineering
Current Plan=p01
Default Exp/Contr=0.3,0.1
English Units
Geom File=g01
Flow File=f01
Plan File=p01
BEGIN DESCRIPTION:
TRIB 17 TO FIFTEENMILE CREEK
END DESCRIPTION:

--- TRIB 17 TO FIFTEENMILE CREEK.p01 (plan) ---

Plan Title=Multiple Run
Short Identifier=Multiple
Geom File=g01
Flow File=f01
Subcritical Flow
K Sum by GR= 0
Std Step Tol= 0.01
Critical Tol= 0.01
Num of Std Step Trials= 20
Max Error Tol= 0.3
Flow Tol Ratio= 0.001
Split Flow NTrial= 30
Split Flow Tol= 0.02
Split Flow Ratio= 0.02
Log Output Level= 0
Friction Slope Method= 1
Unsteady Friction Slope Method= 2
Unsteady Bridges Friction Slope Method= 1
Parabolic Critical Depth
Global Vel Dist=  1 , 1 , 1
Global Log Level= 0
CheckData=True
Encroach Param= -1, 0, 0, 0
BEGIN DESCRIPTION:
Multiple Run
END DESCRIPTION:

--- TRIB 17 TO FIFTEENMILE CREEK.f01 (steady flow) ---

Flow Title=Multiple
Number of Profiles=7
Profile Names=10-year,25-year,50-year,1pct_min,100-year,1pct_plu,500-year
River Rch & RM= TRIB 17 TO FIFTE,Reach-1,9375
     568     913    1224     794    1585    3162    2630
River Rch & RM= TRIB 17 TO FIFTE,Reach-1,6979
     846    1392    1894    1248    2489    4967    4255
River Rch & RM= TRIB 17 TO FIFTE,Reach-1,6271
    1031    1711    2343    1551    3094    6173    5341
River Rch & RM= TRIB 17 TO FIFTE,Reach-1,2583
    1119    1864    2557    1694    3381    6745    5855
Boundary for River Rch & Prof#=TRIB 17 TO FIFTE,Reach-1,1
Up Type=0
Dn Type=3
Dn Slope=0.005
Boundary for River Rch & Prof#=TRIB 17 TO FIFTE,Reach-1,2
Up Type=0
Dn Type=3
Dn Slope=0.005
Boundary for River Rch & Prof#=TRIB 17 TO FIFTE,Reach-1,3
Up Type=0
Dn Type=3
Dn Slope=0.005
Boundary for River Rch & Prof#=TRIB 17 TO FIFTE,Reach-1,4
Up Type=0
Dn Type=3
Dn Slope=0.005
Boundary for River Rch & Prof#=TRIB 17 TO FIFTE,Reach-1,5
Up Type=0
Dn Type=3
Dn Slope=0.005
Boundary for River Rch & Prof#=TRIB 17 TO FIFTE,Reach-1,6
Up Type=0
Dn Type=3
Dn Slope=0.005
Boundary for River Rch & Prof#=TRIB 17 TO FIFTE,Reach-1,7
Up Type=0
Dn Type=3
Dn Slope=0.005

--- TRIB 17 TO FIFTEENMILE CREEK.g01 (geometry) ---

Geom Title=Existing Conditions

River Reach=TRIB 17 TO FIFTE,Reach-1
Reach XY= 30
      2457475.00     13549075.00      2457517.01     13548621.66
      2457382.87     13548471.78      2457432.85     13548318.81
      2457661.39     13548138.24      2457771.24     13547923.44
      2457874.51     13547609.78      2457832.80     13547421.58
      2457974.99     13547259.64      2457925.07     13546545.03
      2458025.28     13546154.82      2457975.80     13545835.70
      2458075.50     13545649.97      2457926.20     13545414.50
      2458025.50     13544964.83      2457924.82     13544745.13
      2458017.44     13544475.00      2457978.16     13544376.65
      2458167.69     13544175.10      2457983.05     13543821.71
      2458230.54     13543272.58      2458773.04     13542519.11
      2458724.61     13542345.13      2458767.19     13542171.59
      2458675.25     13542059.78      2458725.40     13541900.00
      2458674.54     13541664.82      2458824.75     13541359.78
      2458824.64     13540940.15      2458775.00     13540875.00

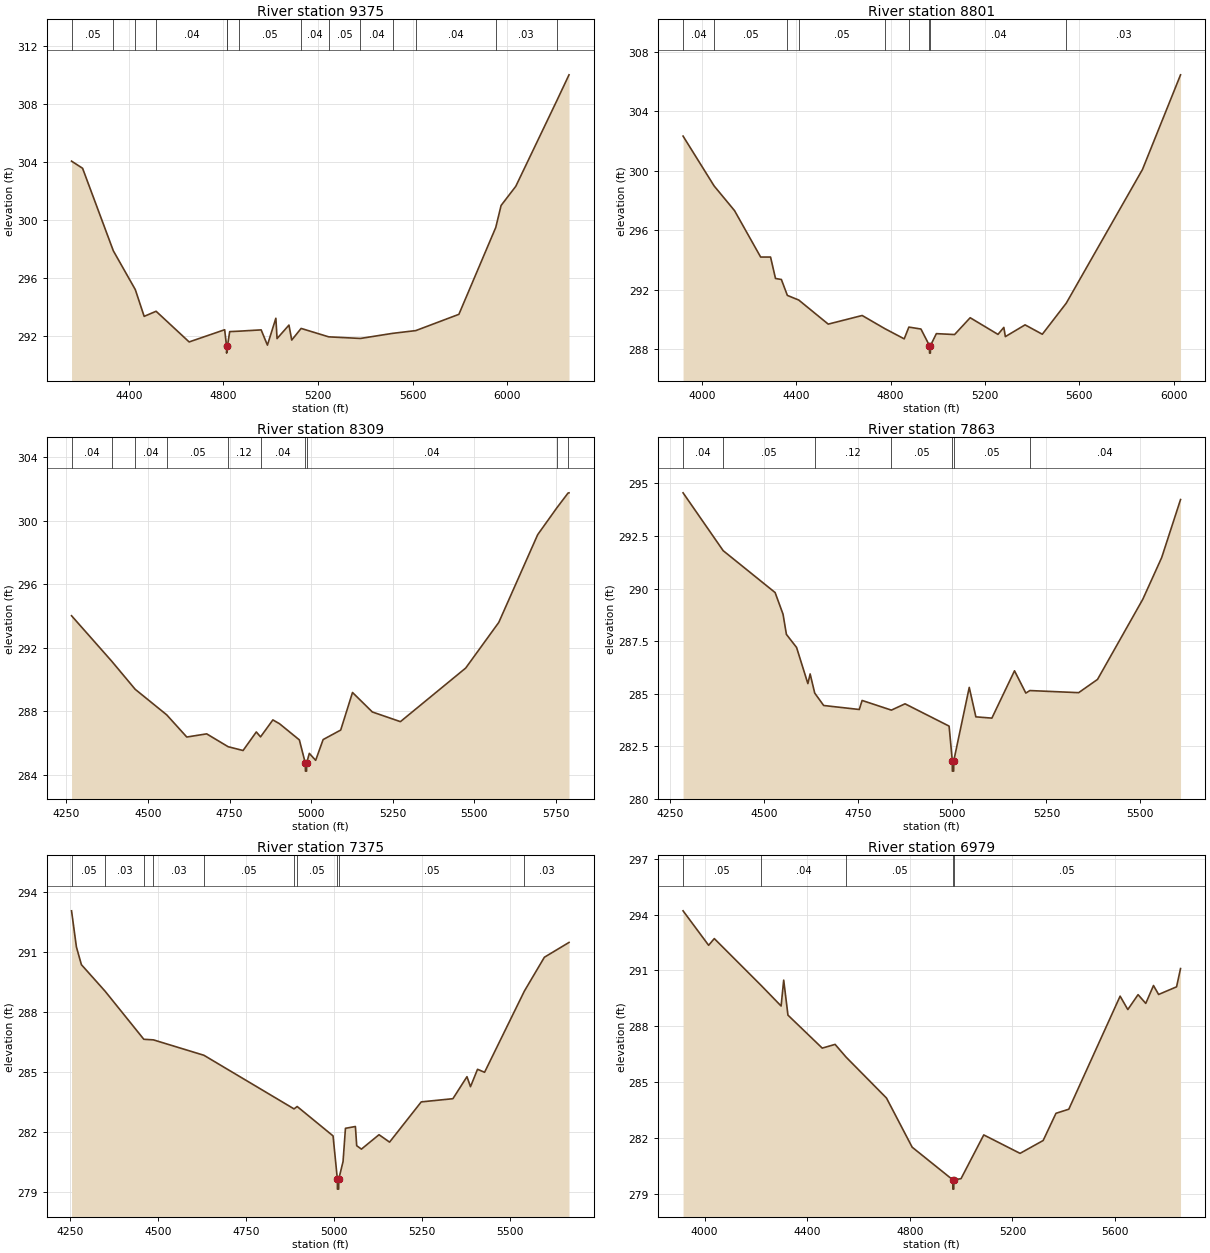
Type RM Length L Ch R = 1,9375,574,574,574
BEGIN DESCRIPTION:
TRIB 17 TO FIFTEENMILE CREEK 17.0
END DESCRIPTION:
XS GIS Cut Line= 3
      2458361.66     13548978.17      2457584.05     13548933.48
      2456275.04     13548725.01
#Sta/Elev= 30
  4157.5  304.06  4204.2  303.57  4334.3  297.89  4427.3  295.22  4464.7  293.38
  4515.2  293.73  4655.0  291.62  4805.2  292.46  4813.2  291.35  4813.5  290.85
  4817.2  291.35  4826.5  292.33  4865.7  292.36  4959.6  292.45  4986.1  291.40
  5021.8  293.25  5026.9  291.85  5077.2  292.78  5089.0  291.75  5128.7  292.55
  5245.6  291.97  5379.5  291.86  5515.4  292.21  5613.7  292.40  5796.1  293.52
  5952.1  299.50  5974.6  301.01  6036.8  302.33  6210.0  308.21  6261.9  310.00
#Mann=14,-1,0
  4157.5    0.05       0  4334.3    0.04       0  4427.3    0.05       0
  4515.2    0.04       0  4813.2    0.05       0  4817.2    0.04       0
  4865.7    0.05       0  5128.7    0.04       0  5245.6    0.05       0
  5379.5    0.04       0  5515.4    0.05       0  5613.7    0.04       0
  5952.1    0.03       0  6210.0    0.04       0
Bank Sta=4813.2,4817.2
Exp/Cntr=0.3,0.1

Type RM Length L Ch R = 1,8801,492,492,492
BEGIN DESCRIPTION:
TRIB 17 TO FIFTEENMILE CREEK 16.0
END DESCRIPTION:
XS GIS Cut Line= 3
      2458438.16     13548766.15      2457525.00     13548475.00
      2456424.12     13548144.05
#Sta/Elev= 30
  3920.5  302.32  4052.1  298.97  4138.6  297.31  4249.2  294.19  4291.2  294.19
  4312.2  292.75  4337.1  292.68  4362.5  291.61  4410.6  291.30  4535.6  289.68
  4679.5  290.26  4775.0  289.38  4857.6  288.69  4877.3  289.48  4928.5  289.35
  4964.7  288.23  4965.0  287.73  4968.5  287.73  4968.7  288.23  4993.8  289.04
  5071.1  288.98  5137.1  290.11  5254.9  288.99  5279.7  289.46  5286.2  288.84
  5369.7  289.63  5442.8  289.00  5544.3  291.09  5867.3  300.08  6028.5  306.44
#Mann=9,-1,0
  3920.5    0.04       0  4052.1    0.05       0  4362.5    0.04       0
  4410.6    0.05       0  4775.0    0.12       0  4877.3    0.04       0
  4964.7    0.04       0  4968.7    0.04       0  5544.3    0.03       0
Bank Sta=4964.7,4968.7
Exp/Cntr=0.3,0.1

Type RM Length L Ch R = 1,8309,446,446,446
BEGIN DESCRIPTION:
TRIB 17 TO FIFTEENMILE CREEK 15.0
END DESCRIPTION:
XS GIS Cut Line= 3
      2458403.16     13548202.38      2457675.00     13548075.00
      2456945.15     13547782.48
#Sta/Elev= 30
  4265.5  294.02  4389.2  291.14  4460.7  289.38  4557.3  287.77  4618.9  286.37
  4679.9  286.57  4745.7  285.76  4791.5  285.52  4832.1  286.69  4845.1  286.38
  4882.9  287.45  4903.2  287.21  4964.1  286.19  4982.4  284.72  4982.7  284.22
  4986.2  284.22  4986.4  284.72  4994.6  285.34  5014.1  284.90  5037.0  286.21
  5090.9  286.81  5127.1  289.18  5187.9  287.95  5274.0  287.34  5474.2  290.72
  5575.7  293.60  5694.9  299.13  5754.3  300.84  5788.2  301.76  5791.0  301.77
#Mann=10,-1,0
  4265.5    0.04       0  4389.2    0.05       0  4460.7    0.04       0
  4557.3    0.05       0  4745.7    0.12       0  4845.1    0.04       0
  4982.4    0.04       0  4986.4    0.04       0  5754.3    0.03       0
  5788.2    0.04       0
Bank Sta=4982.4,4986.4
Exp/Cntr=0.3,0.1

Type RM Length L Ch R = 1,7863,488,488,488
BEGIN DESCRIPTION:
TRIB 17 TO FIFTEENMILE CREEK 14.0
END DESCRIPTION:
XS GIS Cut Line= 3
      2458424.98     13548074.98      2457825.00     13547675.00
      2457224.96     13547625.00
#Sta/Elev= 30
  4283.6  294.55  4390.3  291.80  4528.4  289.81  4549.5  288.78  4558.5  287.82
  4585.5  287.20  4615.6  285.48  4621.6  285.94  4633.8  285.03  4657.6  284.44
  4752.3  284.25  4759.8  284.68  4837.7  284.22  4874.0  284.52  4991.2  283.46
  4999.7  281.82  4999.9  281.32  5003.4  281.32  5003.7  281.82  5044.8  285.30
  5062.4  283.90  5105.0  283.84  5165.2  286.09  5195.3  285.03  5206.1  285.15
  5335.8  285.05  5386.0  285.68  5506.4  289.49  5556.6  291.47  5606.8  294.23
#Mann=7,-1,0
  4283.6    0.04       0  4390.3    0.05       0  4633.8    0.12       0
  4837.7    0.05       0  4999.7    0.05       0  5003.7    0.05       0
  5206.1    0.04       0
Bank Sta=4999.7,5003.7
Exp/Cntr=0.3,0.1

Type RM Length L Ch R = 1,7375,396,396,396
BEGIN DESCRIPTION:
TRIB 17 TO FIFTEENMILE CREEK 13.0
END DESCRIPTION:
XS GIS Cut Line= 3
      2458474.98     13547824.98      2457925.00     13547225.00
      2457325.01     13547225.00
#Sta/Elev= 30
  4254.1  293.04  4267.9  291.24  4282.1  290.35  4349.6  289.02  4459.5  286.62
  4486.9  286.59  4630.4  285.82  4886.5  283.14  4895.4  283.26  4997.4  281.79
  5009.6  279.63  5009.8  279.13  5013.3  279.13  5013.6  279.63  5025.8  280.51
  5032.6  282.17  5060.9  282.26  5064.6  281.30  5078.0  281.13  5128.0  281.85
  5158.0  281.48  5248.0  283.49  5338.0  283.65  5378.0  284.75  5388.0  284.25
  5408.0  285.12  5428.0  284.97  5541.2  289.03  5598.0  290.72  5668.0  291.46
#Mann=10,-1,0
  4254.1    0.05       0  4349.6    0.03       0  4459.5    0.12       0
  4486.9    0.03       0  4630.4    0.05       0  4886.5    0.12       0
  4895.4    0.05       0  5009.6    0.05       0  5013.6    0.05       0
  5541.2    0.03       0
Bank Sta=5009.6,5013.6
Exp/Cntr=0.3,0.1

Type RM Length L Ch R = 1,6979,195,195,195
BEGIN DESCRIPTION:
Mapping XS edfec126
END DESCRIPTION:
XS GIS Cut Line= 3
      2459006.53     13546853.33      2457832.96     13546929.72
      2457069.50     13546908.89
#Sta/Elev= 30
  3915.8  294.20  4015.5  292.35  4037.6  292.71  4219.9  290.20  4298.1  289.09
  4308.2  290.48  4324.8  288.60  4458.5  286.83  4508.6  287.03  4551.2  286.35
  4709.0  284.15  4809.2  281.51  4967.5  279.76  4967.8  279.26  4971.4  279.26
  4971.7  279.76  4999.6  279.82  5088.3  282.17  5229.9  281.18  5319.9  281.87
  5369.9  283.33  5419.9  283.55  5620.0  289.62  5650.0  288.90  5690.0  289.70
  5720.0  289.23  5750.1  290.19  5770.1  289.71  5840.1  290.12  5855.6  291.10
#Mann=5,-1,0
  3915.8    0.05       0  4219.9    0.04       0  4551.2    0.05       0
  4967.5    0.05       0  4971.7    0.05       0
Bank Sta=4967.5,4971.7
Exp/Cntr=0.3,0.1

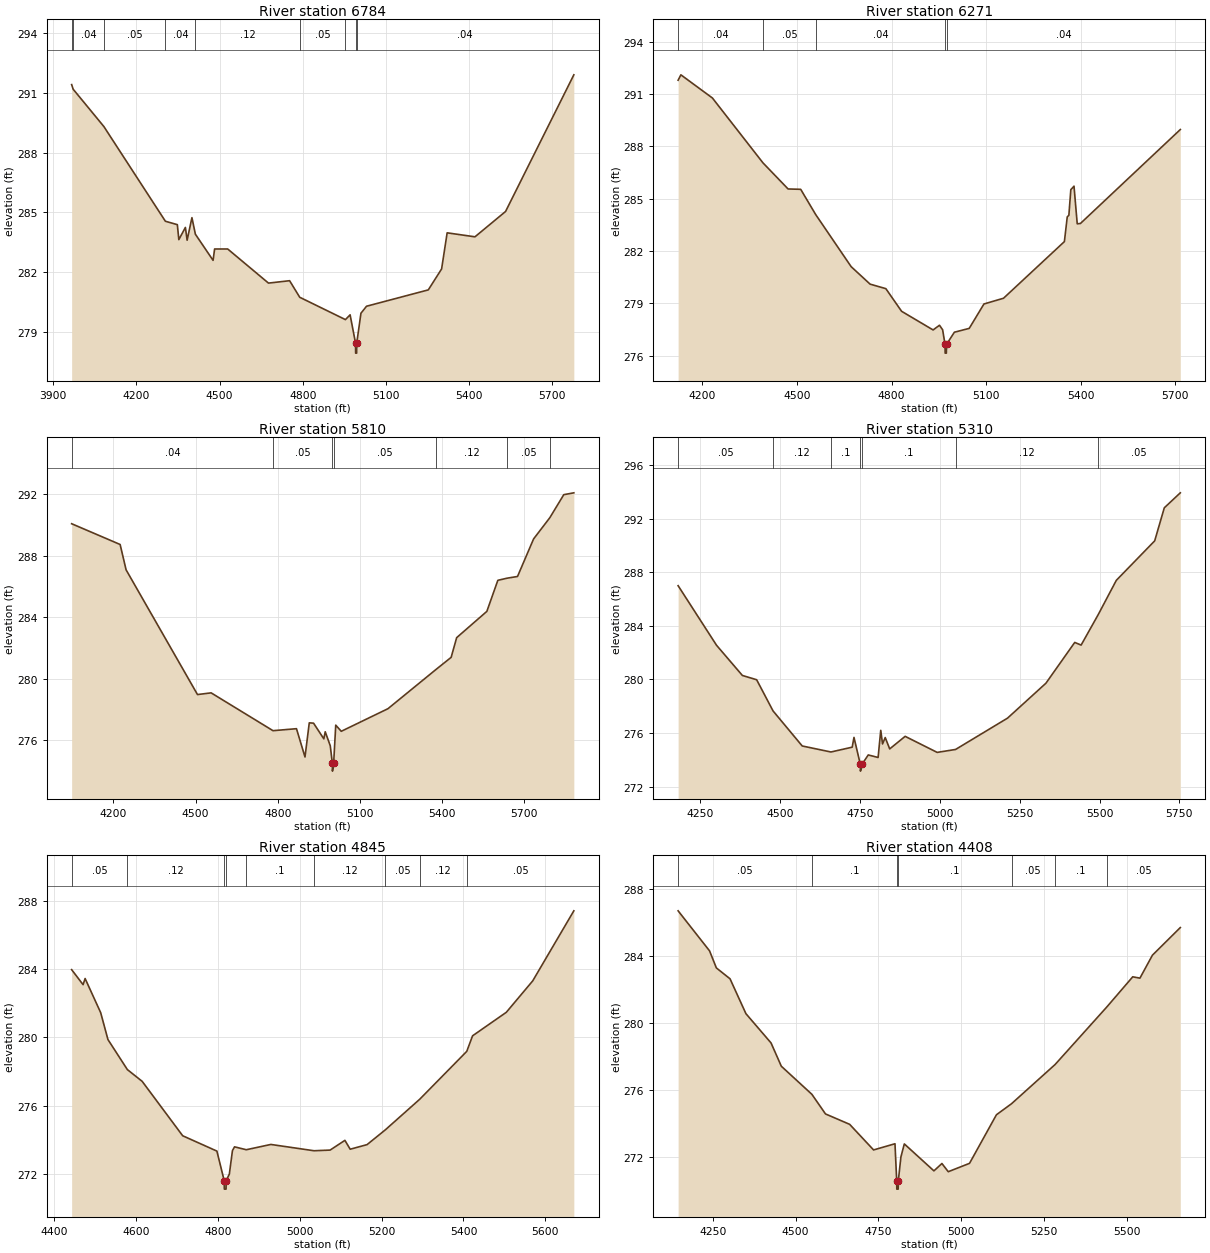
Type RM Length L Ch R = 1,6784,513,513,513
BEGIN DESCRIPTION:
Mapping XS 32d2cb83
END DESCRIPTION:
XS GIS Cut Line= 3
      2458878.13     13546339.43      2457957.96     13546731.80
      2457149.50     13546669.34
#Sta/Elev= 30
  3966.6  291.41  3972.0  291.18  4082.7  289.31  4304.7  284.56  4347.8  284.39
  4353.2  283.64  4376.8  284.25  4383.1  283.61  4400.4  284.74  4412.9  283.91
  4476.7  282.60  4482.2  283.17  4529.4  283.17  4676.5  281.46  4752.7  281.58
  4789.2  280.75  4954.0  279.63  4970.9  279.87  4990.5  278.45  4990.8  277.95
  4994.5  277.95  4994.8  278.45  5010.0  279.95  5030.1  280.30  5252.9  281.12
  5300.9  282.17  5320.9  283.98  5421.2  283.78  5531.6  285.05  5777.8  291.90
#Mann=9,-1,0
  3966.6    0.05       0  3972.0    0.04       0  4082.7    0.05       0
  4304.7    0.04       0  4412.9    0.12       0  4789.2    0.05       0
  4954.0    0.04       0  4990.5    0.04       0  4994.8    0.04       0
Bank Sta=4990.5,4994.8
Exp/Cntr=0.3,0.1

Type RM Length L Ch R = 1,6271,461,461,461
BEGIN DESCRIPTION:
Mapping XS 92dda0e1
END DESCRIPTION:
XS GIS Cut Line= 3
      2458853.76     13546207.50      2457975.32     13546231.80
      2457273.95     13546367.21
#Sta/Elev= 30
  4123.0  291.80  4131.8  292.11  4231.8  290.78  4392.1  287.06  4471.9  285.56
  4511.9  285.54  4559.5  284.09  4672.0  281.10  4732.0  280.10  4782.0  279.84
  4832.0  278.54  4931.9  277.47  4952.1  277.74  4962.1  277.48  4969.8  276.64
  4970.1  276.14  4974.0  276.14  4974.4  276.64  4999.4  277.34  5046.5  277.56
  5093.2  278.96  5155.3  279.29  5348.4  282.54  5357.5  283.96  5362.6  284.05
  5368.8  285.52  5378.9  285.72  5389.1  283.56  5399.3  283.58  5716.1  288.97
#Mann=5,-1,0
  4123.0    0.04       0  4392.1    0.05       0  4559.5    0.04       0
  4969.8    0.04       0  4974.4    0.04       0
Bank Sta=4969.8,4974.4
Exp/Cntr=0.3,0.1

Type RM Length L Ch R = 1,5810,500,500,500
BEGIN DESCRIPTION:
Mapping XS aba341b1
END DESCRIPTION:
XS GIS Cut Line= 3
      2458895.46     13546072.08      2458020.46     13545829.02
      2457098.44     13545894.88
#Sta/Elev= 30
  4047.9  290.08  4224.8  288.73  4246.6  287.08  4507.1  278.97  4556.9  279.08
  4782.7  276.62  4868.3  276.75  4899.4  274.91  4915.0  277.13  4930.6  277.11
  4968.1  276.09  4973.2  276.55  4991.6  275.64  4999.3  274.49  4999.6  273.99
  5003.9  274.49  5011.6  276.98  5031.7  276.58  5202.1  278.05  5375.9  280.58
  5432.7  281.39  5452.8  282.67  5563.0  284.38  5603.1  286.40  5637.4  286.54
  5674.9  286.65  5733.5  289.09  5792.7  290.47  5843.7  291.97  5880.4  292.09
#Mann=7,-1,0
  4047.9    0.04       0  4782.7    0.05       0  4999.3    0.05       0
  5003.9    0.05       0  5375.9    0.12       0  5637.4    0.05       0
  5792.7    0.12       0
Bank Sta=4999.3,5003.9
Exp/Cntr=0.3,0.1

Type RM Length L Ch R = 1,5310,465,465,465
BEGIN DESCRIPTION:
TRIB 17 TO FIFTEENMILE CREEK 9.0
END DESCRIPTION:
XS GIS Cut Line= 3
      2458674.97     13545125.02      2458075.00     13545425.00
      2457174.97     13545375.00
#Sta/Elev= 30
  4180.7  287.01  4300.9  282.56  4381.9  280.30  4426.6  279.98  4477.9  277.65
  4569.2  275.03  4659.1  274.58  4725.7  274.94  4731.3  275.67  4751.2  273.65
  4751.6  273.15  4756.1  273.65  4776.0  274.36  4806.8  274.17  4815.1  276.20
  4820.7  275.18  4829.1  275.66  4843.1  274.81  4891.5  275.75  4991.7  274.55
  5049.4  274.77  5212.0  277.11  5332.2  279.72  5422.4  282.77  5442.4  282.57
  5495.5  284.83  5552.6  287.41  5672.7  290.36  5702.8  292.83  5752.9  293.95
#Mann=7,-1,0
  4180.7    0.05       0  4477.9    0.12       0  4659.1     0.1       0
  4751.2    0.05       0  4756.1     0.1       0  5049.4    0.12       0
  5495.5    0.05       0
Bank Sta=4751.2,4756.1
Exp/Cntr=0.3,0.1

Type RM Length L Ch R = 1,4845,437,437,437
BEGIN DESCRIPTION:
TRIB 17 TO FIFTEENMILE CREEK 8.0
END DESCRIPTION:
XS GIS Cut Line= 3
      2458574.97     13545075.00      2457975.00     13544975.00
      2457375.01     13545125.00
#Sta/Elev= 30
  4442.9  283.97  4470.8  283.09  4475.8  283.45  4513.8  281.45  4531.6  279.87
  4579.0  278.11  4615.2  277.42  4714.1  274.23  4797.7  273.33  4815.5  271.60
  4815.9  271.10  4820.1  271.10  4820.4  271.60  4828.1  271.98  4835.7  273.36
  4840.8  273.58  4869.5  273.41  4929.5  273.72  5035.1  273.35  5074.3  273.39
  5110.4  273.96  5123.3  273.44  5164.5  273.71  5208.8  274.57  5293.1  276.37
  5408.1  279.18  5422.2  280.09  5504.7  281.47  5569.1  283.31  5669.6  287.42
#Mann=9,-1,0
  4442.9    0.05       0  4579.0    0.12       0  4815.5    0.05       0
  4820.4    0.12       0  4869.5     0.1       0  5035.1    0.12       0
  5208.8    0.05       0  5293.1    0.12       0  5408.1    0.05       0
Bank Sta=4815.5,4820.4
Exp/Cntr=0.3,0.1

Type RM Length L Ch R = 1,4408,414,414,414
BEGIN DESCRIPTION:
Mapping XS 65710fea
END DESCRIPTION:
XS GIS Cut Line= 3
      2458766.96     13544790.82      2457975.32     13544589.44
      2457364.22     13544929.71
#Sta/Elev= 30
  4145.5  286.68  4240.4  284.29  4261.0  283.27  4302.3  282.62  4350.2  280.54
  4426.1  278.79  4457.1  277.40  4549.5  275.72  4590.5  274.55  4663.4  273.93
  4735.7  272.40  4800.3  272.77  4805.5  270.56  4805.8  270.06  4810.0  270.06
  4810.4  270.56  4818.2  271.98  4828.5  272.76  4917.9  271.15  4942.0  271.59
  4961.2  271.10  5025.4  271.60  5106.6  274.50  5152.2  275.16  5283.7  277.50
  5440.0  280.94  5518.2  282.74  5539.9  282.66  5577.6  284.03  5661.8  285.68
#Mann=7,-1,0
  4145.5    0.05       0  4549.5     0.1       0  4805.5    0.05       0
  4810.4     0.1       0  5152.2    0.05       0  5283.7     0.1       0
  5440.0    0.05       0
Bank Sta=4805.5,4810.4
Exp/Cntr=0.3,0.1

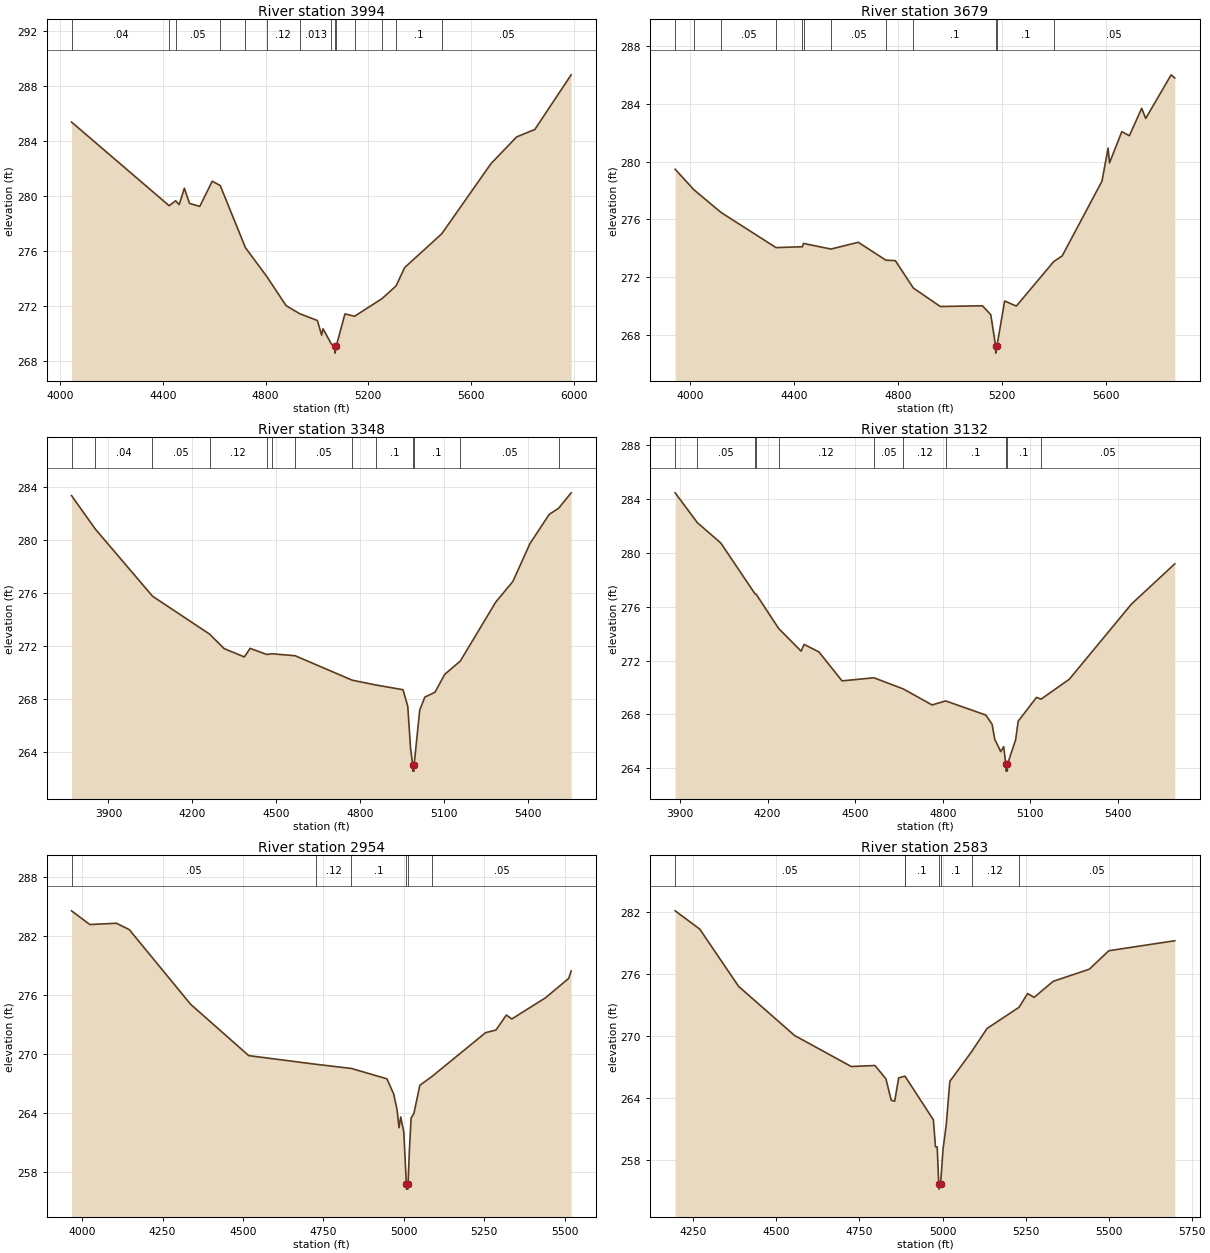
Type RM Length L Ch R = 1,3994,315,315,315
BEGIN DESCRIPTION:
Mapping XS aede9126
END DESCRIPTION:
XS GIS Cut Line= 4
      2459013.51     13544228.33      2458315.60     13544179.72
      2457756.57     13544398.47      2457239.63     13544787.04
#Sta/Elev= 30
  4044.1  285.36  4424.5  279.28  4450.0  279.64  4463.6  279.36  4483.7  280.55
  4503.7  279.45  4543.8  279.23  4592.3  281.06  4623.4  280.75  4721.8  276.23
  4804.4  274.15  4880.1  272.02  4933.5  271.43  5002.1  270.94  5018.5  269.88
  5023.9  270.34  5056.5  269.23  5070.3  269.07  5070.7  268.57  5075.4  269.07
  5109.4  271.42  5147.1  271.25  5253.9  272.53  5308.5  273.45  5342.2  274.79
  5486.6  277.24  5678.5  282.34  5778.4  284.28  5849.2  284.82  5990.7  288.79
#Mann=14,-1,0
  4044.1    0.04       0  4424.5   0.013       0  4450.0    0.05       0
  4623.4    0.12       0  4721.8   0.013       0  4804.4    0.12       0
  4933.5   0.013       0  5056.5     0.1       0  5070.3    0.03       0
  5075.4     0.1       0  5147.1    0.05       0  5253.9   0.013       0
  5308.5     0.1       0  5486.6    0.05       0
Bank Sta=5070.3,5075.4
Exp/Cntr=0.3,0.1

Type RM Length L Ch R = 1,3679,331,331,331
BEGIN DESCRIPTION:
Mapping XS fabab06c
END DESCRIPTION:
XS GIS Cut Line= 3
      2459107.31     13543651.92      2457926.71     13544079.02
      2457312.09     13544339.45
#Sta/Elev= 30
  3941.4  279.47  4012.8  278.06  4118.4  276.47  4329.7  274.04  4431.4  274.10
  4435.4  274.33  4541.1  273.94  4646.1  274.41  4752.4  273.17  4788.7  273.14
  4858.1  271.24  4962.0  269.96  5124.3  270.01  5156.2  269.39  5174.9  267.23
  5175.3  266.73  5180.0  267.23  5209.6  270.34  5254.6  269.99  5398.4  273.07
  5431.2  273.47  5584.1  278.64  5607.8  280.93  5613.2  279.91  5660.5  282.07
  5689.6  281.79  5737.0  283.69  5752.6  282.99  5850.4  286.01  5864.4  285.79
#Mann=12,-1,0
  3941.4    0.05       0  4012.8    0.04       0  4118.4    0.05       0
  4329.7    0.12       0  4431.4    0.05       0  4435.4    0.12       0
  4541.1    0.05       0  4752.4    0.12       0  4858.1     0.1       0
  5174.9    0.05       0  5180.0     0.1       0  5398.4    0.05       0
Bank Sta=5174.9,5180
Exp/Cntr=0.3,0.1

Type RM Length L Ch R = 1,3348,216,216,216
BEGIN DESCRIPTION:
Mapping XS c153627d
END DESCRIPTION:
XS GIS Cut Line= 3
      2459224.51     13543545.52      2458260.93     13543782.51
      2457479.88     13543647.12
#Sta/Elev= 30
  3768.3  283.38  3853.6  280.84  4057.6  275.77  4261.5  272.90  4313.6  271.80
  4385.7  271.17  4406.3  271.82  4465.5  271.36  4485.0  271.41  4567.5  271.26
  4771.2  269.41  4855.4  269.05  4952.7  268.69  4969.6  267.44  4979.7  264.23
  4987.3  263.03  4987.7  262.53  4992.0  262.53  4992.4  263.03  5012.4  267.15
  5030.5  268.13  5067.0  268.50  5101.5  269.85  5157.3  270.86  5284.2  275.33
  5345.1  276.88  5406.0  279.74  5474.9  281.96  5508.5  282.42  5553.3  283.59
#Mann=13,-1,0
  3768.3    0.05       0  3853.6    0.04       0  4057.6    0.05       0
  4261.5    0.12       0  4465.5    0.05       0  4485.0    0.12       0
  4567.5    0.05       0  4771.2    0.12       0  4855.4     0.1       0
  4987.3    0.05       0  4992.4     0.1       0  5157.3    0.05       0
  5508.5    0.03       0
Bank Sta=4987.3,4992.4
Exp/Cntr=0.3,0.1

Type RM Length L Ch R = 1,3132,178,178,178
BEGIN DESCRIPTION:
Mapping XS 1c27b6f4
END DESCRIPTION:
XS GIS Cut Line= 3
      2459218.40     13543478.32      2458447.54     13543631.11
      2457541.30     13543440.13
#Sta/Elev= 30
  3883.2  284.47  3959.3  282.25  4039.6  280.74  4157.2  276.95  4160.9  276.93
  4237.6  274.39  4314.8  272.70  4325.0  273.20  4376.0  272.64  4455.0  270.49
  4564.2  270.72  4665.0  269.89  4763.6  268.70  4810.2  269.00  4947.6  267.95
  4969.3  267.26  4978.2  266.16  4998.7  265.23  5008.8  265.60  5016.5  264.28
  5016.9  263.78  5021.3  263.78  5021.7  264.28  5049.8  266.11  5058.6  267.49
  5121.3  269.26  5136.9  269.13  5233.7  270.61  5446.8  276.20  5595.2  279.19
#Mann=11,-1,0
  3883.2    0.04       0  3959.3    0.05       0  4157.2    0.04       0
  4160.9    0.05       0  4237.6    0.12       0  4564.2    0.05       0
  4665.0    0.12       0  4810.2     0.1       0  5016.5    0.05       0
  5021.7     0.1       0  5136.9    0.05       0
Bank Sta=5016.5,5021.7
Exp/Cntr=0.3,0.1

Type RM Length L Ch R = 1,2954,371,371,371
BEGIN DESCRIPTION:
Mapping XS 6abacaa3
END DESCRIPTION:
XS GIS Cut Line= 3
      2459214.08     13543415.32      2458422.39     13543477.82
      2457699.21     13543248.90
#Sta/Elev= 30
  3967.0  284.52  4023.9  283.13  4106.5  283.26  4146.6  282.61  4337.2  275.04
  4517.8  269.83  4727.5  268.95  4836.8  268.53  4947.2  267.48  4968.2  265.94
  4978.7  264.35  4984.9  262.52  4990.1  263.61  4999.7  262.06  5007.6  256.79
  5008.0  256.29  5012.4  256.29  5012.8  256.79  5017.2  260.38  5022.4  263.50
  5031.1  263.97  5049.5  266.82  5086.5  267.70  5253.8  272.16  5286.1  272.43
  5318.4  273.95  5335.3  273.55  5440.2  275.70  5512.2  277.67  5519.7  278.42
#Mann=6,-1,0
  3967.0    0.05       0  4727.5    0.12       0  4836.8     0.1       0
  5007.6    0.05       0  5012.8     0.1       0  5086.5    0.05       0
Bank Sta=5007.6,5012.8
Exp/Cntr=0.3,0.1

Type RM Length L Ch R = 1,2583,485,485,485
BEGIN DESCRIPTION:
Mapping XS 459d631a
END DESCRIPTION:
XS GIS Cut Line= 3
      2459128.06     13543322.07      2458374.63     13543096.38
      2457669.92     13542961.00
#Sta/Elev= 30
  4195.1  282.12  4269.1  280.35  4386.2  274.79  4554.6  270.03  4725.3  267.02
  4796.6  267.12  4829.7  265.82  4845.5  263.75  4856.0  263.65  4868.0  265.92
  4886.3  266.08  4887.3  266.07  4972.5  261.85  4978.8  259.23  4984.0  259.23
  4988.7  255.63  4989.2  255.13  4994.1  255.63  5001.6  259.03  5011.1  261.33
  5022.0  265.58  5087.5  268.46  5134.0  270.71  5230.5  272.77  5256.2  274.10
  5275.9  273.73  5333.0  275.28  5442.0  276.46  5500.6  278.25  5699.2  279.22
#Mann=7,-1,0
  4195.1    0.05       0  4886.3    0.12       0  4887.3     0.1       0
  4988.7    0.05       0  4994.1     0.1       0  5087.5    0.12       0
  5230.5    0.05       0
Bank Sta=4988.7,4994.1
Exp/Cntr=0.3,0.1

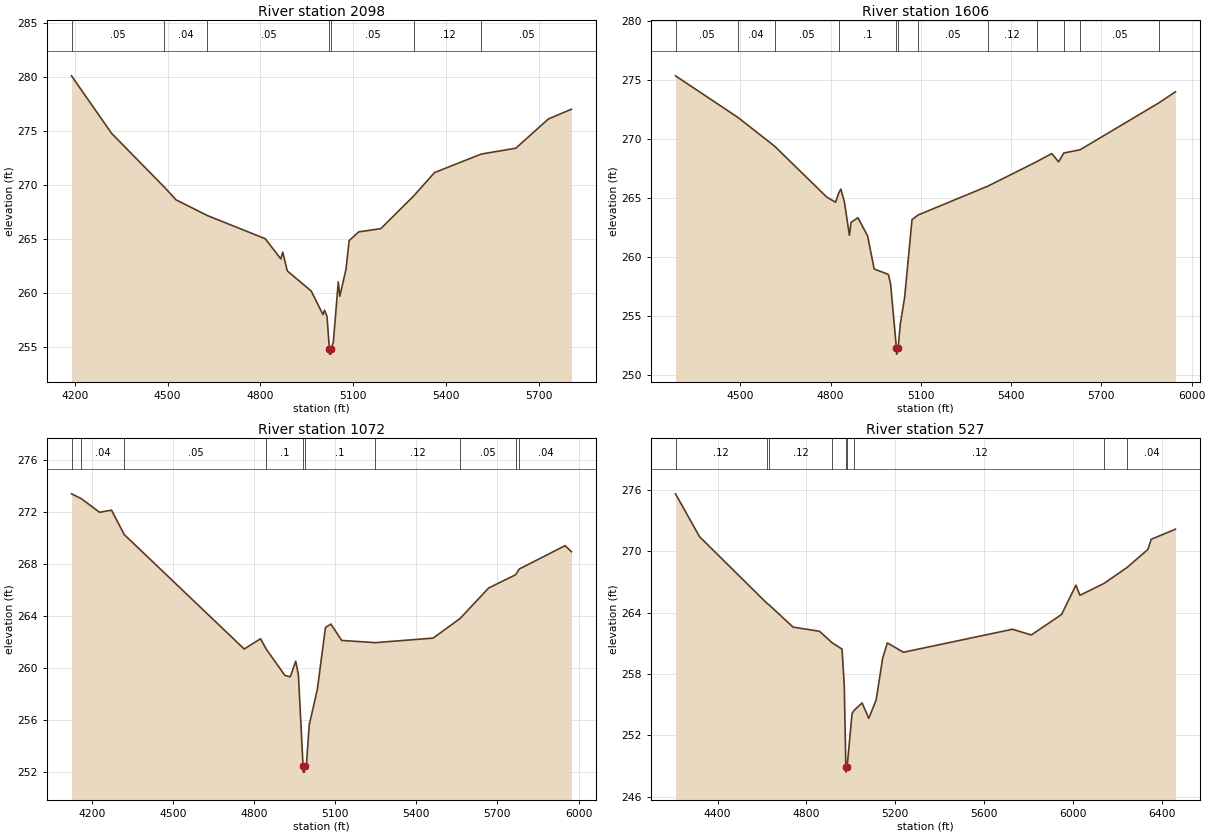
Type RM Length L Ch R = 1,2098,492,492,492
BEGIN DESCRIPTION:
Mapping XS c3ef80c7
END DESCRIPTION:
XS GIS Cut Line= 3
      2459270.49     13543131.12      2458641.99     13542690.13
      2457812.15     13542867.21
#Sta/Elev= 30
  4189.6  280.11  4319.0  274.79  4490.1  269.80  4527.3  268.64  4628.9  267.18
  4815.8  265.04  4866.3  263.17  4872.4  263.80  4887.2  262.06  4964.5  260.20
  5002.5  258.02  5007.6  258.42  5015.6  257.85  5023.2  254.86  5023.6  254.36
  5028.2  254.36  5028.6  254.86  5036.1  255.48  5052.0  261.05  5057.1  259.72
  5077.0  262.23  5087.2  264.86  5117.9  265.67  5189.5  265.97  5295.6  268.99
  5363.3  271.16  5514.2  272.87  5625.8  273.41  5731.4  276.12  5805.9  277.02
#Mann=7,-1,0
  4189.6    0.05       0  4490.1    0.04       0  4628.9    0.05       0
  5023.2    0.05       0  5028.6    0.05       0  5295.6    0.12       0
  5514.2    0.05       0
Bank Sta=5023.2,5028.6
Exp/Cntr=0.3,0.1

Type RM Length L Ch R = 1,1606,534,534,534
BEGIN DESCRIPTION:
Mapping XS f2148b22
END DESCRIPTION:
XS GIS Cut Line= 3
      2459374.61     13542572.07      2458749.63     13542283.88
      2457843.40     13542638.04
#Sta/Elev= 30
  4284.9  275.39  4492.5  271.86  4614.1  269.43  4788.4  265.09  4816.9  264.68
  4827.1  265.45  4834.3  265.79  4846.1  264.71  4862.8  261.87  4868.3  262.97
  4891.2  263.36  4923.2  261.82  4945.2  259.01  4992.1  258.56  4999.6  257.76
  5019.1  252.30  5019.6  251.80  5024.7  252.30  5031.8  254.34  5046.4  256.63
  5070.8  263.20  5091.6  263.60  5322.9  266.04  5485.0  268.11  5535.2  268.80
  5557.9  268.10  5575.4  268.85  5629.2  269.12  5891.3  273.10  5946.1  274.04
#Mann=12,-1,0
  4284.9    0.05       0  4492.5    0.04       0  4614.1    0.05       0
  4827.1     0.1       0  5019.1    0.05       0  5024.7     0.1       0
  5091.6    0.05       0  5322.9    0.12       0  5485.0    0.05       0
  5575.4    0.04       0  5629.2    0.05       0  5891.3    0.04       0
Bank Sta=5019.1,5024.7
Exp/Cntr=0.3,0.1

Type RM Length L Ch R = 1,1072,545,545,545
BEGIN DESCRIPTION:
TRIB 17 TO FIFTEENMILE CREEK 1.0
END DESCRIPTION:
XS GIS Cut Line= 4
      2459225.01     13542425.02      2458895.81     13541843.76
      2458500.79     13541833.76      2458093.16     13542505.03
#Sta/Elev= 30
  4125.3  273.41  4161.3  273.04  4228.8  271.99  4273.2  272.15  4320.3  270.27
  4763.8  261.46  4824.1  262.25  4845.9  261.43  4914.2  259.43  4934.2  259.32
  4954.2  260.52  4964.2  259.48  4981.3  252.48  4981.8  251.98  4986.5  251.98
  4987.0  252.48  4994.2  252.65  5004.2  255.62  5034.2  258.35  5064.2  263.12
  5084.2  263.38  5124.2  262.12  5248.8  261.95  5462.3  262.30  5562.0  263.81
  5667.7  266.16  5767.4  267.18  5780.9  267.62  5950.4  269.42  5973.8  268.95
#Mann=10,-1,0
  4125.3    0.05       0  4161.3    0.04       0  4320.3    0.05       0
  4845.9     0.1       0  4981.3    0.05       0  4987.0     0.1       0
  5248.8    0.12       0  5562.0    0.05       0  5767.4    0.12       0
  5780.9    0.04       0
Bank Sta=4981.3,4987
Exp/Cntr=0.3,0.1

Type RM Length L Ch R = 1,527,0,0,0
BEGIN DESCRIPTION:
4825
END DESCRIPTION:
XS GIS Cut Line= 4
      2459612.82     13541405.84      2458711.69     13541342.38
      2458123.63     13541718.91      2457878.24     13542319.69
#Sta/Elev= 30
  4210.7  275.64  4318.8  271.45  4620.4  264.97  4632.8  264.76  4739.8  262.60
  4859.2  262.19  4915.6  261.07  4960.4  260.45  4970.4  256.91  4977.6  248.91
  4978.0  248.41  4983.3  248.91  5005.5  254.15  5016.4  254.49  5050.6  255.18
  5080.7  253.67  5114.1  255.48  5143.3  259.57  5164.4  261.05  5237.1  260.14
  5727.6  262.39  5812.3  261.83  5948.5  263.83  6013.4  266.70  6031.5  265.71
  6141.2  266.89  6245.0  268.46  6337.4  270.20  6352.2  271.19  6461.3  272.18
#Mann=9,-1,0
  4210.7    0.12       0  4620.4    0.05       0  4632.8    0.12       0
  4915.6    0.05       0  4977.6    0.05       0  4983.3    0.05       0
  5016.4    0.12       0  6141.2    0.05       0  6245.0    0.04       0
Bank Sta=4977.6,4983.3
Exp/Cntr=0.3,0.1

Chan Stop Cuts=-1