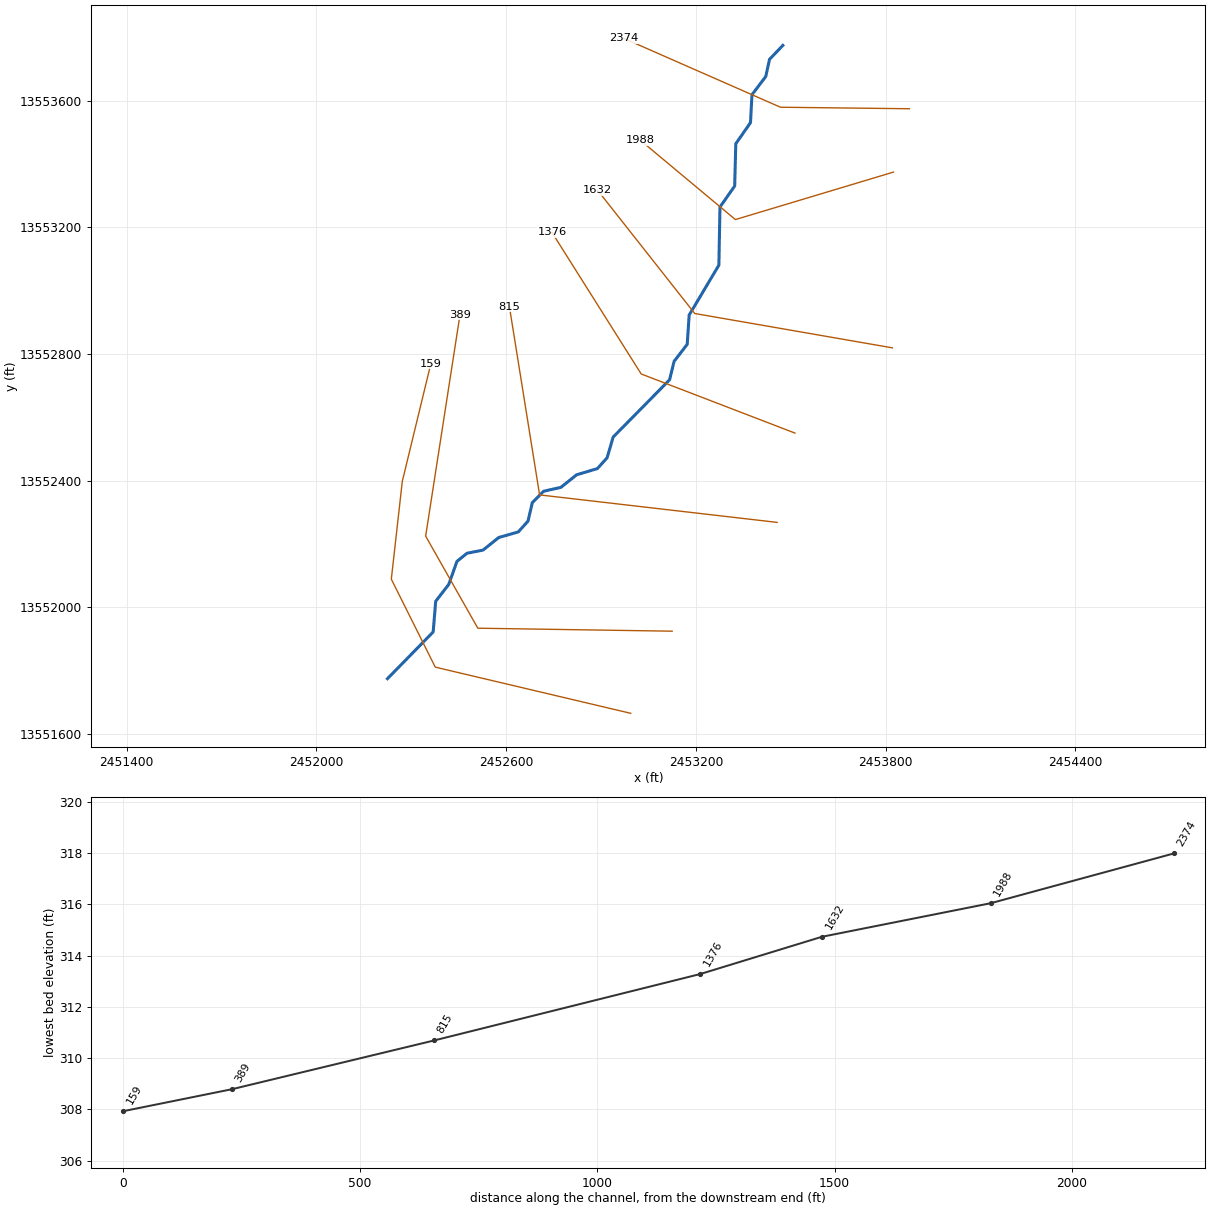
--- TRIB 18 TO FIFTEENMILE CREEK.prj (project) ---

Proj Title=TRIB 18 TO FIFTEENMILE CREEK Base Level Engineering
Current Plan=p01
Default Exp/Contr=0.3,0.1
English Units
Geom File=g01
Flow File=f01
Plan File=p01
BEGIN DESCRIPTION:
TRIB 18 TO FIFTEENMILE CREEK
END DESCRIPTION:

--- TRIB 18 TO FIFTEENMILE CREEK.p01 (plan) ---

Plan Title=Multiple Run
Short Identifier=Multiple
Geom File=g01
Flow File=f01
Subcritical Flow
K Sum by GR= 0
Std Step Tol= 0.01
Critical Tol= 0.01
Num of Std Step Trials= 20
Max Error Tol= 0.3
Flow Tol Ratio= 0.001
Split Flow NTrial= 30
Split Flow Tol= 0.02
Split Flow Ratio= 0.02
Log Output Level= 0
Friction Slope Method= 1
Unsteady Friction Slope Method= 2
Unsteady Bridges Friction Slope Method= 1
Parabolic Critical Depth
Global Vel Dist=  1 , 1 , 1
Global Log Level= 0
CheckData=True
Encroach Param= -1, 0, 0, 0
BEGIN DESCRIPTION:
Multiple Run
END DESCRIPTION:

--- TRIB 18 TO FIFTEENMILE CREEK.f01 (steady flow) ---

Flow Title=Multiple
Number of Profiles=7
Profile Names=10-year,25-year,50-year,1pct_min,100-year,1pct_plu,500-year
River Rch & RM= TRIB 18 TO FIFTE,Reach-1,2374
     450     715     949     612    1221    2437    2000
Boundary for River Rch & Prof#=TRIB 18 TO FIFTE,Reach-1,1
Up Type=0
Dn Type=3
Dn Slope=0.005
Boundary for River Rch & Prof#=TRIB 18 TO FIFTE,Reach-1,2
Up Type=0
Dn Type=3
Dn Slope=0.005
Boundary for River Rch & Prof#=TRIB 18 TO FIFTE,Reach-1,3
Up Type=0
Dn Type=3
Dn Slope=0.005
Boundary for River Rch & Prof#=TRIB 18 TO FIFTE,Reach-1,4
Up Type=0
Dn Type=3
Dn Slope=0.005
Boundary for River Rch & Prof#=TRIB 18 TO FIFTE,Reach-1,5
Up Type=0
Dn Type=3
Dn Slope=0.005
Boundary for River Rch & Prof#=TRIB 18 TO FIFTE,Reach-1,6
Up Type=0
Dn Type=3
Dn Slope=0.005
Boundary for River Rch & Prof#=TRIB 18 TO FIFTE,Reach-1,7
Up Type=0
Dn Type=3
Dn Slope=0.005

--- TRIB 18 TO FIFTEENMILE CREEK.g01 (geometry) ---

Geom Title=Existing Conditions

River Reach=TRIB 18 TO FIFTE,Reach-1
Reach XY= 30
      2453475.00     13553775.00      2453432.91     13553731.15
      2453420.93     13553676.69      2453377.44     13553619.45
      2453372.64     13553530.98      2453326.23     13553464.49
      2453322.73     13553330.94      2453276.22     13553264.49
      2453272.76     13553080.93      2453178.83     13552923.42
      2453172.67     13552830.97      2453131.14     13552777.17
      2453116.86     13552718.94      2452938.64     13552538.20
      2452919.25     13552472.46      2452888.57     13552438.47
      2452822.84     13552418.89      2452773.24     13552379.20
      2452718.66     13552366.97      2452683.05     13552331.31
      2452669.24     13552272.49      2452638.56     13552238.48
      2452576.76     13552220.80      2452527.16     13552181.11
      2452476.42     13552171.14      2452444.62     13552145.48
      2452418.85     13552072.85      2452377.45     13552019.44
      2452369.48     13551922.57      2452225.00     13551775.00

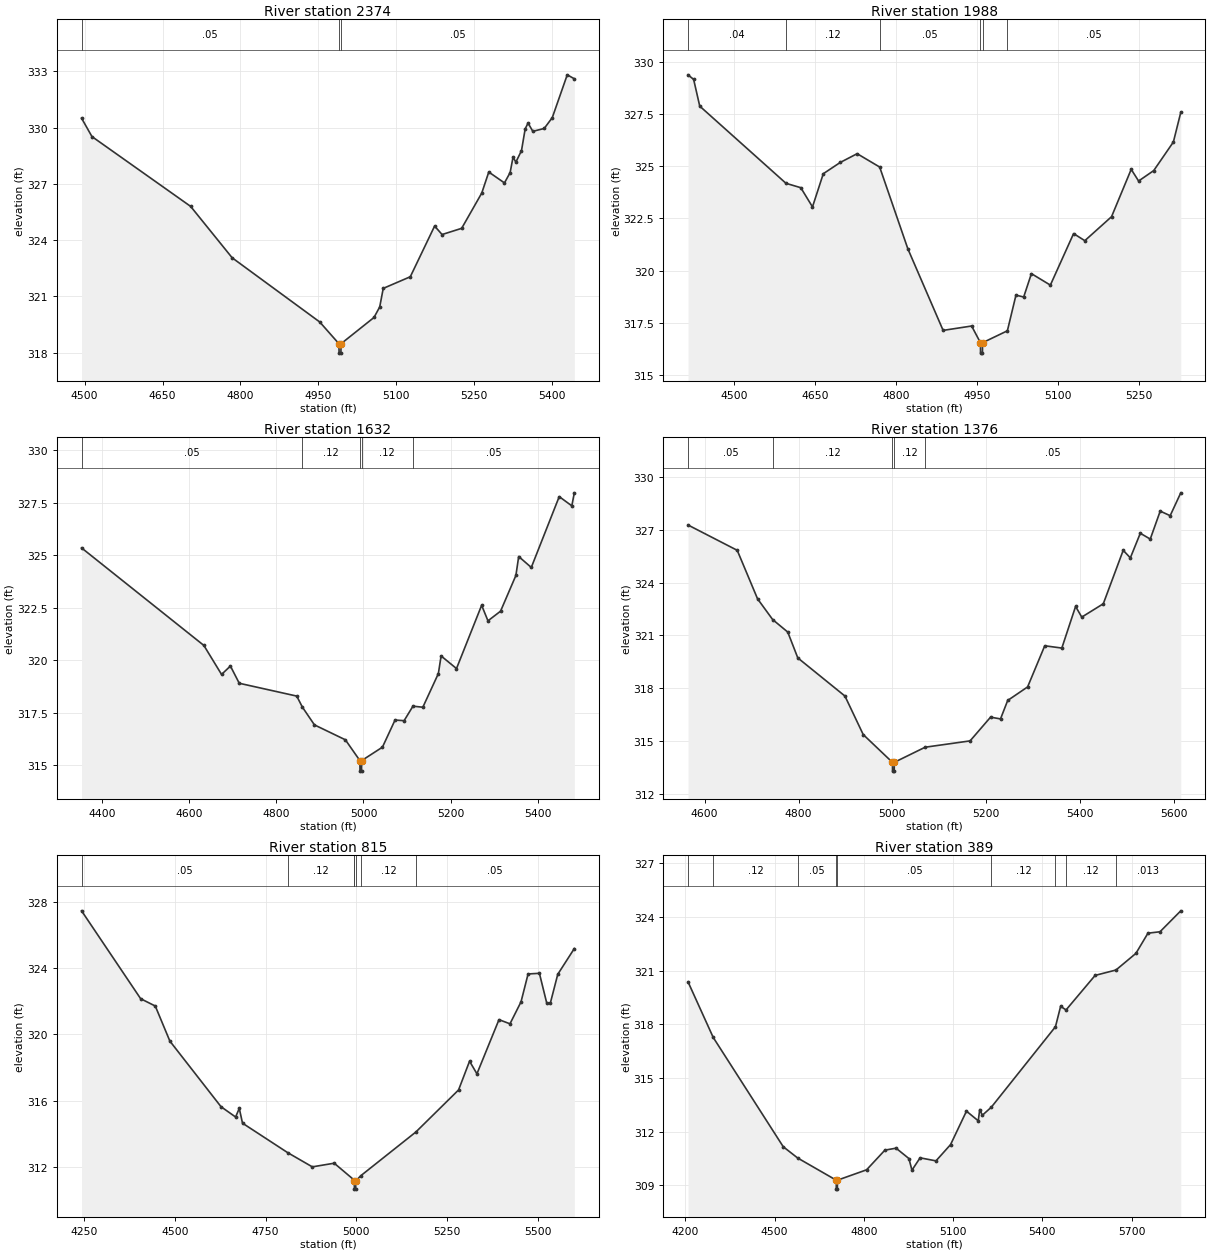
Type RM Length L Ch R = 1,2374,386,386,386
BEGIN DESCRIPTION:
TRIB 18 TO FIFTEENMILE CREEK 5.0
END DESCRIPTION:
XS GIS Cut Line= 3
      2453874.98     13553575.00      2453467.53     13553579.76
      2452971.87     13553797.37
#Sta/Elev= 30
  4494.1  330.50  4514.1  329.52  4704.1  325.80  4784.1  323.06  4952.7  319.64
  4989.7  318.48  4990.0  317.98  4993.5  317.98  4993.7  318.48  5057.2  319.88
  5068.2  320.44  5075.0  321.43  5127.1  322.05  5173.9  324.75  5188.3  324.30
  5226.0  324.63  5264.7  326.51  5278.2  327.63  5308.4  327.05  5319.3  327.60
  5324.9  328.42  5330.4  328.16  5341.2  328.77  5348.3  329.93  5353.8  330.24
  5363.0  329.80  5384.9  329.95  5400.5  330.53  5429.3  332.81  5442.9  332.60
#Mann=3,-1,0
  4494.1    0.05       0  4989.7    0.05       0  4993.7    0.05       0
Bank Sta=4989.7,4993.7
Exp/Cntr=0.3,0.1

Type RM Length L Ch R = 1,1988,356,356,356
BEGIN DESCRIPTION:
TRIB 18 TO FIFTEENMILE CREEK 4.0
END DESCRIPTION:
XS GIS Cut Line= 3
      2453824.98     13553374.99      2453325.00     13553225.00
      2453025.00     13553475.00
#Sta/Elev= 30
  4414.8  329.38  4425.2  329.16  4436.5  327.88  4596.2  324.18  4623.6  323.97
  4645.3  323.05  4665.3  324.64  4696.7  325.18  4728.0  325.60  4769.7  324.96
  4821.9  321.04  4887.2  317.13  4940.0  317.34  4956.3  316.54  4956.5  316.04
  4960.0  316.04  4960.3  316.54  5006.2  317.11  5022.1  318.82  5036.4  318.73
  5050.7  319.85  5085.8  319.30  5128.8  321.77  5149.6  321.43  5199.1  322.58
  5235.5  324.85  5249.2  324.29  5277.2  324.79  5313.6  326.16  5327.3  327.58
#Mann=6,-1,0
  4414.8    0.04       0  4596.2    0.12       0  4769.7    0.05       0
  4956.3    0.05       0  4960.3    0.05       0  5006.2    0.05       0
Bank Sta=4956.3,4960.3
Exp/Cntr=0.3,0.1

Type RM Length L Ch R = 1,1632,256,256,256
BEGIN DESCRIPTION:
Mapping XS eb4ba233
END DESCRIPTION:
XS GIS Cut Line= 3
      2453821.42     13552819.82      2453196.40     13552928.33
      2452889.12     13553317.85
#Sta/Elev= 30
  4353.2  325.35  4633.8  320.71  4674.4  319.33  4694.7  319.73  4715.0  318.91
  4846.9  318.30  4859.7  317.78  4887.5  316.93  4958.5  316.22  4991.8  315.23
  4992.0  314.73  4995.5  314.73  4995.8  315.23  5043.5  315.87  5072.4  317.16
  5093.2  317.13  5113.5  317.82  5136.2  317.77  5171.8  319.37  5178.1  320.21
  5213.4  319.61  5271.1  322.62  5285.6  321.88  5314.5  322.34  5349.7  324.04
  5356.1  324.94  5385.0  324.42  5449.1  327.79  5478.0  327.35  5483.7  327.97
#Mann=5,-1,0
  4353.2    0.05       0  4859.7    0.12       0  4991.8    0.05       0
  4995.8    0.12       0  5113.5    0.05       0
Bank Sta=4991.8,4995.8
Exp/Cntr=0.3,0.1

Type RM Length L Ch R = 1,1376,561,561,561
BEGIN DESCRIPTION:
Mapping XS 0f479217
END DESCRIPTION:
XS GIS Cut Line= 3
      2453513.28     13552550.71      2453027.13     13552737.36
      2452745.00     13553184.44
#Sta/Elev= 30
  4564.7  327.28  4669.5  325.84  4712.8  323.08  4745.0  321.90  4777.1  321.19
  4798.5  319.72  4898.9  317.55  4937.8  315.36  5000.0  313.78  5000.3  313.28
  5003.8  313.28  5004.0  313.78  5069.7  314.64  5165.4  315.00  5209.0  316.35
  5230.2  316.25  5245.5  317.30  5287.9  318.07  5324.4  320.41  5360.8  320.28
  5390.1  322.65  5403.2  322.04  5449.1  322.80  5491.5  325.84  5506.7  325.41
  5527.9  326.81  5549.1  326.48  5570.3  328.07  5591.5  327.81  5614.1  329.11
#Mann=5,-1,0
  4564.7    0.05       0  4745.0    0.12       0  5000.0    0.05       0
  5004.0    0.12       0  5069.7    0.05       0
Bank Sta=5000,5004
Exp/Cntr=0.3,0.1

Type RM Length L Ch R = 1,815,426,426,426
BEGIN DESCRIPTION:
Mapping XS 1ad0af4c
END DESCRIPTION:
XS GIS Cut Line= 3
      2453456.83     13552268.61      2452705.95     13552355.41
      2452610.47     13552950.01
#Sta/Elev= 30
  4243.0  327.44  4405.9  322.15  4446.2  321.71  4486.4  319.60  4627.4  315.65
  4667.6  315.03  4677.7  315.55  4686.6  314.66  4810.8  312.89  4879.0  312.03
  4939.4  312.25  4993.6  311.25  4994.8  311.19  4995.1  310.69  4998.6  310.69
  4998.8  311.19  5012.8  311.50  5164.5  314.13  5282.1  316.66  5312.4  318.39
  5332.7  317.63  5393.5  320.89  5423.8  320.64  5454.2  321.96  5473.7  323.64
  5504.9  323.68  5525.1  321.89  5535.3  321.91  5555.5  323.62  5601.1  325.17
#Mann=7,-1,0
  4243.0    0.05       0  4810.8    0.12       0  4993.6    0.05       0
  4994.8    0.05       0  4998.8    0.05       0  5012.8    0.12       0
  5164.5    0.05       0
Bank Sta=4994.8,4998.8
Exp/Cntr=0.3,0.1

Type RM Length L Ch R = 1,389,230,230,230
BEGIN DESCRIPTION:
TRIB 18 TO FIFTEENMILE CREEK 1.0
END DESCRIPTION:
XS GIS Cut Line= 4
      2453125.00     13551925.00      2452510.64     13551934.41
      2452345.71     13552225.21      2452454.22     13552923.98
#Sta/Elev= 30
  4209.1  320.38  4293.8  317.27  4529.1  311.16  4577.6  310.53  4707.2  309.29
  4707.4  308.79  4710.9  308.79  4711.2  309.29  4809.2  309.87  4870.7  310.97
  4908.2  311.08  4951.4  310.50  4961.6  309.85  4989.0  310.54  5042.4  310.37
  5091.4  311.28  5144.8  313.15  5184.4  312.61  5189.4  313.24  5198.1  312.92
  5228.3  313.37  5443.9  317.87  5461.2  319.01  5479.5  318.81  5577.2  320.74
  5647.1  321.04  5714.2  321.97  5754.7  323.10  5795.2  323.18  5865.0  324.35
#Mann=9,-1,0
  4209.1    0.05       0  4293.8    0.12       0  4577.6    0.05       0
  4707.2    0.05       0  4711.2    0.05       0  5228.3    0.12       0
  5443.9    0.05       0  5479.5    0.12       0  5647.1   0.013       0
Bank Sta=4707.2,4711.2
Exp/Cntr=0.3,0.1

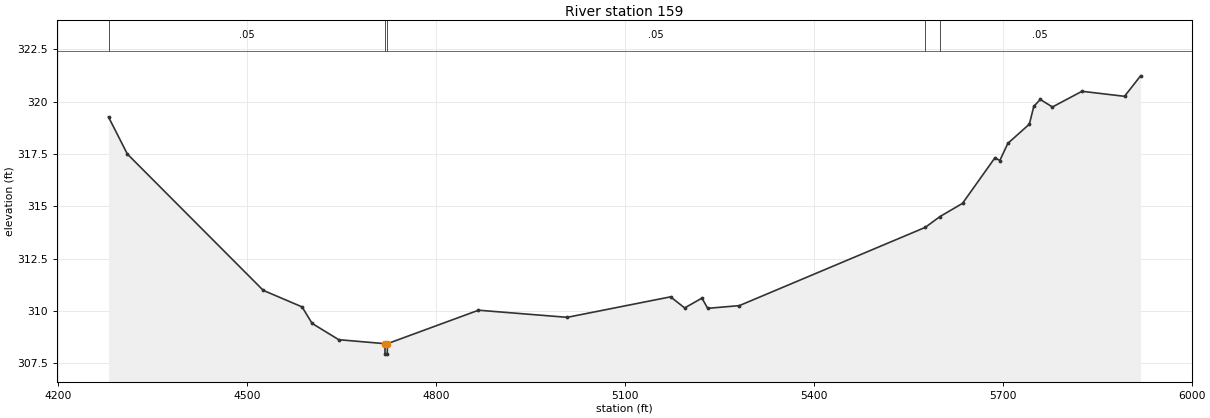
Type RM Length L Ch R = 1,159,0,0,0
BEGIN DESCRIPTION:
4826
END DESCRIPTION:
XS GIS Cut Line= 5
      2452994.09     13551665.63      2452376.04     13551811.46
      2452237.15     13552089.24      2452271.88     13552398.26
      2452362.15     13552769.79
#Sta/Elev= 30
  4280.0  319.27  4309.9  317.50  4525.7  310.98  4587.3  310.19  4603.3  309.40
  4645.6  308.62  4718.9  308.43  4719.1  307.93  4722.6  307.93  4722.9  308.43
  4867.5  310.03  5008.4  309.69  5172.5  310.67  5194.9  310.14  5222.4  310.61
  5231.4  310.12  5281.7  310.25  5576.8  313.99  5600.4  314.51  5636.1  315.14
  5687.6  317.32  5695.4  317.19  5708.1  318.01  5742.3  318.93  5749.3  319.78
  5759.6  320.11  5778.9  319.75  5825.8  320.50  5893.4  320.26  5918.9  321.24
#Mann=5,-1,0
  4280.0    0.05       0  4718.9    0.05       0  4722.9    0.05       0
  5576.8    0.12       0  5600.4    0.05       0
Bank Sta=4718.9,4722.9
Exp/Cntr=0.3,0.1

Chan Stop Cuts=-1