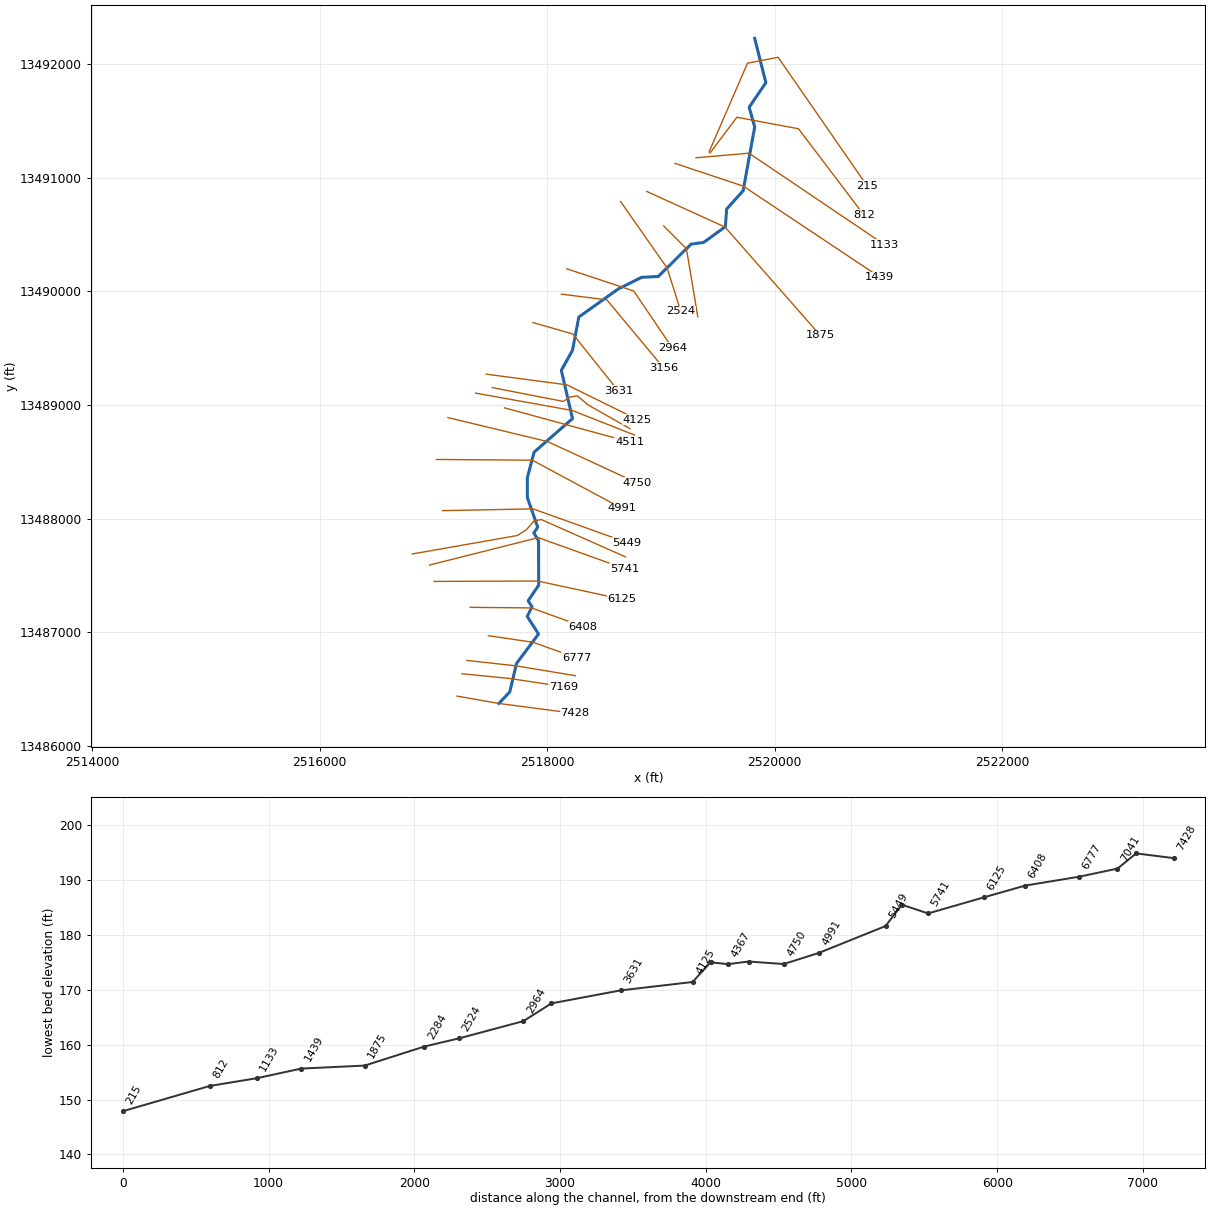
--- TRIB 1_1 TO FIFTEENMILE CREEK.prj (project) ---

Proj Title=TRIB 1_1 TO FIFTEENMILE CREEK Base Level Engineering
Current Plan=p01
Default Exp/Contr=0.3,0.1
English Units
Geom File=g01
Flow File=f01
Plan File=p01
Y Axis Title=Elevation
X Axis Title(PF)=Main Channel Distance
X Axis Title(XS)=Station
BEGIN DESCRIPTION:
TRIB 1_1 TO FIFTEENMILE CREEK
END DESCRIPTION:
DSS Export Rating Curves= 0
DSS Export Rating Curve Sorted= 0
DSS Export Volume Flow Curves= 0
DXF OffsetX= 0
DXF OffsetY= 0
DXF ScaleX= 1
DXF ScaleY= 10

--- TRIB 1_1 TO FIFTEENMILE CREEK.p01 (plan) ---

Plan Title=Multiple Run
Short Identifier=Multiple
Geom File=g01
Flow File=f01
Subcritical Flow
K Sum by GR= 0
Std Step Tol= 0.01
Critical Tol= 0.01
Num of Std Step Trials= 20
Max Error Tol= 0.3
Flow Tol Ratio= 0.001
Split Flow NTrial= 30
Split Flow Tol= 0.02
Split Flow Ratio= 0.02
Log Output Level= 0
Friction Slope Method= 1
Unsteady Friction Slope Method= 2
Unsteady Bridges Friction Slope Method= 1
Parabolic Critical Depth
Global Vel Dist=  1 , 1 , 1
Global Log Level= 0
CheckData=True
Encroach Param= -1, 0, 0, 0
BEGIN DESCRIPTION:
Multiple Run
END DESCRIPTION:

--- TRIB 1_1 TO FIFTEENMILE CREEK.f01 (steady flow) ---

Flow Title=Multiple
Number of Profiles=7
Profile Names=10-year,25-year,50-year,1pct_min,100-year,1pct_plu,500-year
River Rch & RM= TRIB 1_1 TO FIFT,Reach-1,7428
     469     735     968     619    1234    2462    1981
Boundary for River Rch & Prof#=TRIB 1_1 TO FIFT,Reach-1,1
Up Type=0
Dn Type=3
Dn Slope=0.005
Boundary for River Rch & Prof#=TRIB 1_1 TO FIFT,Reach-1,2
Up Type=0
Dn Type=3
Dn Slope=0.005
Boundary for River Rch & Prof#=TRIB 1_1 TO FIFT,Reach-1,3
Up Type=0
Dn Type=3
Dn Slope=0.005
Boundary for River Rch & Prof#=TRIB 1_1 TO FIFT,Reach-1,4
Up Type=0
Dn Type=3
Dn Slope=0.005
Boundary for River Rch & Prof#=TRIB 1_1 TO FIFT,Reach-1,5
Up Type=0
Dn Type=3
Dn Slope=0.005
Boundary for River Rch & Prof#=TRIB 1_1 TO FIFT,Reach-1,6
Up Type=0
Dn Type=3
Dn Slope=0.005
Boundary for River Rch & Prof#=TRIB 1_1 TO FIFT,Reach-1,7
Up Type=0
Dn Type=3
Dn Slope=0.005

--- TRIB 1_1 TO FIFTEENMILE CREEK.g01 (geometry) ---

Geom Title=Existing Conditions
Program Version=4.10

River Reach=TRIB 1_1 TO FIFT,Reach-1
Reach XY= 30
        2517575.       13486375.      2517671.51     13486476.45
      2517730.83      13486727.3       2517924.3      13486985.7
      2517825.02     13487140.36      2517867.16     13487225.09
      2517833.01     13487278.33       2517925.5     13487414.79
      2517924.82     13487805.02      2517882.79      13487875.1
      2517917.21      13487924.9      2517826.22     13488185.51
      2517825.52     13488359.78      2517885.35     13488585.12
      2518223.04     13488880.88      2518124.71     13489304.83
      2518222.75     13489480.93      2518278.61     13489773.52
       2518622.7     13490019.17      2518830.93     13490122.75
      2518977.45     13490130.47      2519265.21     13490414.48
      2519377.42     13490430.54       2519567.3     13490568.53
      2519578.75     13490723.47        2519724.     13490885.29
      2519825.28     13491445.18      2519776.97     13491619.11
      2519923.81      13491835.5        2519825.       13492225.

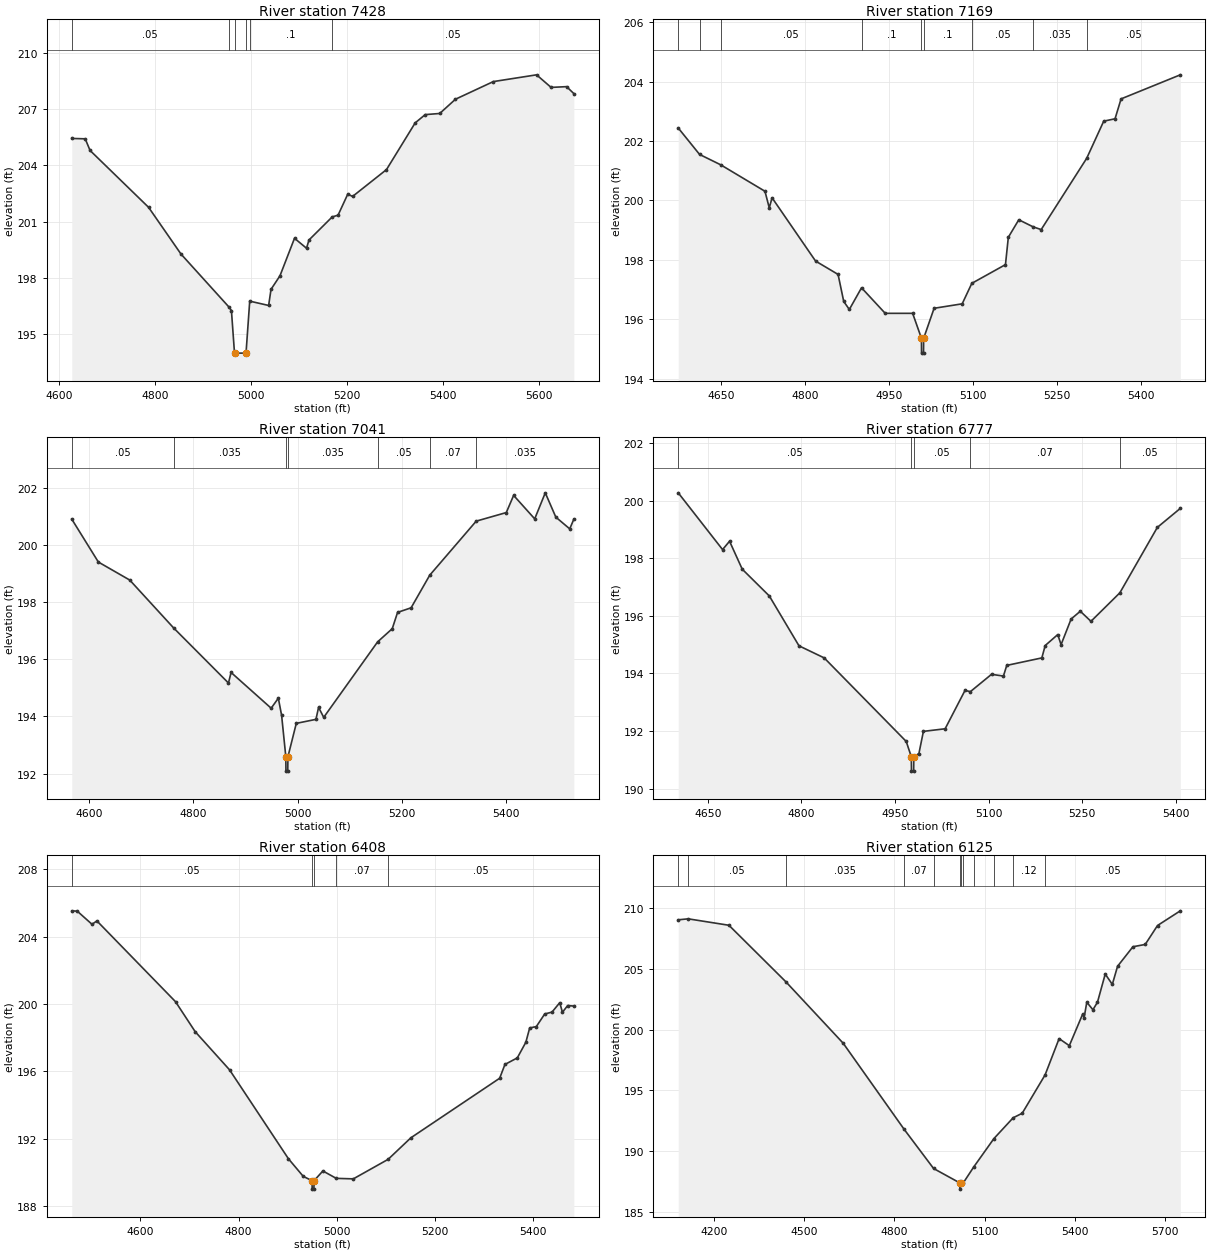
Type RM Length L Ch R = 1 ,7428    ,259,259,259
BEGIN DESCRIPTION:
Mapping XS d0968c19
END DESCRIPTION:
XS GIS Cut Line= 3
      2517207.46     13486439.75        2517575.       13486375.
      2518242.01     13486287.66
#Sta/Elev= 30
  4626.8  205.44  4654.8  205.42  4664.9   204.8  4786.8  201.77  4854.3  199.28
  4953.4  196.48  4959.4  196.27  4965.8     194  4989.8     194  4997.5  196.77
  5036.9  196.54  5041.9   197.4  5060.5  198.12  5090.8  200.12  5115.8  199.59
    5121  200.03  5169.4  201.26  5181.5  201.35  5201.7  202.47  5211.8  202.35
  5282.4  203.78  5342.2  206.27  5363.1  206.71  5393.3  206.77  5426.1  207.53
    5505  208.47    5595  208.83  5625.3  208.16  5657.6   208.2  5672.7  207.83
#Mann= 6 ,-1 , 0
  4626.8     .05       0  4953.4      .1       0  4965.8     .05       0
  4989.8     .07       0  4997.5      .1       0  5169.4     .05       0
Bank Sta=4965.8,4989.8
XS Rating Curve= 0 ,0
Exp/Cntr=0.3,0.1

Type RM Length L Ch R = 1 ,7169    ,128,128,128
BEGIN DESCRIPTION:
Mapping XS 8ea2885d
END DESCRIPTION:
XS GIS Cut Line= 3
      2517250.88     13486636.28      2517667.51     13486595.05
      2518140.26     13486523.49
#Sta/Elev= 30
  4574.1  202.44  4612.2  201.55    4650   201.2    4729  200.31  4736.7  199.75
  4741.7  200.09  4819.4  197.96  4859.6  197.51  4869.7   196.6  4879.7  196.33
  4901.5  197.06  4943.8   196.2  4992.8   196.2  5008.5  195.36  5008.7  194.86
  5012.2  194.86  5012.5  195.36  5031.1  196.37  5081.3  196.52  5098.5  197.21
  5158.6  197.84  5163.7  198.76  5182.4  199.35  5208.2  199.11  5222.4  199.02
  5303.7  201.42  5334.1  202.67  5354.3  202.75  5365.1  203.42  5470.9  204.23
#Mann= 9 ,-1 , 0
  4574.1     .05       0  4612.2    .035       0    4650     .05       0
  4901.5      .1       0  5008.5     .05       0  5012.5      .1       0
  5098.5     .05       0  5208.2    .035       0  5303.7     .05       0
Bank Sta=5008.5,5012.5
XS Rating Curve= 0 ,0
Exp/Cntr=0.3,0.1

Type RM Length L Ch R = 1 ,7041    ,264,264,264
BEGIN DESCRIPTION:
Mapping XS 65c342c9
END DESCRIPTION:
XS GIS Cut Line= 3
      2517294.24     13486753.47       2517726.1     13486705.73
      2518249.15     13486618.92
#Sta/Elev= 30
  4566.2   200.9  4617.3   199.4  4677.6  198.77  4761.7   197.1  4867.3  195.17
  4872.3  195.54  4949.3  194.29  4963.1  194.64  4969.4  194.04  4977.5  192.59
  4977.7  192.09  4981.2  192.09  4981.5  192.59  4997.6  193.76  5035.4   193.9
  5040.4  194.32  5050.3  193.97  5153.9  196.61    5182  197.07  5192.2  197.64
  5218.2   197.8    5254  198.94  5343.3  200.83  5401.1  201.13  5415.2  201.73
  5455.7  200.91    5476  201.82  5496.3  200.97    5523  200.56  5530.9   200.9
#Mann= 7 ,-1 , 0
  4566.2     .05       0  4761.7    .035       0  4977.5    .035       0
  4981.5    .035       0  5153.9     .05       0    5254     .07       0
  5343.3    .035       0
Bank Sta=4977.5,4981.5
XS Rating Curve= 0 ,0
Exp/Cntr=0.3,0.1

Type RM Length L Ch R = 1 ,6777    ,369,369,369
BEGIN DESCRIPTION:
Mapping XS f50512aa
END DESCRIPTION:
XS GIS Cut Line= 3
      2517483.63     13486970.88      2517874.27     13486913.58
      2518259.68     13486775.56
#Sta/Elev= 30
  4602.8  200.27  4673.8   198.3    4685  198.59  4705.3  197.62  4748.7  196.69
  4796.2  194.96  4836.6  194.54    4968  191.64  4976.1  191.11  4976.4  190.61
  4979.9  190.61  4980.1  191.11  4988.3  191.22  4995.5  191.99  5030.3  192.08
  5062.1  193.41  5070.8  193.37  5104.6  193.97  5123.7  193.91    5129  194.28
  5185.2  194.54  5190.6  194.97  5210.7  195.35    5216     195  5232.1  195.89
  5246.8  196.16  5263.9  195.81  5310.2   196.8  5370.2  199.07    5407  199.73
#Mann= 5 ,-1 , 0
  4602.8     .05       0  4976.1     .05       0  4980.1     .05       0
  5070.8     .07       0  5310.2     .05       0
Bank Sta=4976.1,4980.1
XS Rating Curve= 0 ,0
Exp/Cntr=0.3,0.1

Type RM Length L Ch R = 1 ,6408    ,283,283,283
BEGIN DESCRIPTION:
TRIB TO TRIB TO FIFTEENMILE CREEK 13.0
END DESCRIPTION:
XS GIS Cut Line= 3
      2517323.84     13487220.27      2517863.32     13487215.13
      2518316.84     13487050.15
#Sta/Elev= 30
  4460.5  205.54  4471.7  205.52  4501.7  204.74  4511.7  204.94  4671.7  200.14
  4711.7  198.36  4781.7  196.09  4901.7   190.8  4931.7  189.76  4949.7   189.5
  4949.9     189  4953.4     189  4953.7   189.5  4971.7  190.08  4998.9  189.64
  5033.7  189.61  5104.5  190.77  5150.8  192.05  5331.6  195.59  5342.3  196.41
  5367.5   196.8  5384.9  197.73  5392.7  198.58  5406.2  198.66  5423.3  199.41
  5438.1  199.52  5453.9  200.08  5459.4  199.51    5470  199.91  5482.6  199.88
#Mann= 5 ,-1 , 0
  4460.5     .05       0  4949.7     .05       0  4953.7     .05       0
  4998.9     .07       0  5104.5     .05       0
Bank Sta=4949.7,4953.7
XS Rating Curve= 0 ,0
Exp/Cntr=0.3,0.1

Type RM Length L Ch R = 1 ,6125    ,384,384,384
BEGIN DESCRIPTION:
Mapping XS 64b76195
END DESCRIPTION:
XS GIS Cut Line= 3
      2517006.36     13487448.29      2517916.05     13487451.76
      2518659.08     13487292.04
#Sta/Elev= 30
  4080.9  209.05  4114.1  209.13  4249.5   208.6  4438.6  203.95  4629.5  198.88
  4831.8   191.8  4930.1  188.56  5018.2  187.36  5018.5  186.86  5022.2  187.36
  5029.5   187.4    5064   188.7  5130.6  191.02  5194.8  192.74  5224.8  193.11
  5300.9  196.27  5347.5  199.26  5381.5  198.68  5425.7  201.27  5430.8     201
  5439.6  202.26    5460  201.64  5475.1  202.26  5500.9  204.58  5524.5  203.73
  5541.9  205.22    5593  206.83  5633.9  207.02  5674.8  208.58  5750.6  209.79
#Mann= 12 ,-1 , 0
  4080.9     .07       0  4114.1     .05       0  4438.6    .035       0
  4831.8     .07       0  4930.1     .05       0  5018.2     .05       0
  5022.2     .05       0  5029.5     .07       0    5064     .12       0
  5130.6     .05       0  5194.8     .12       0  5300.9     .05       0
Bank Sta=5018.2,5022.2
XS Rating Curve= 0 ,0
Exp/Cntr=0.3,0.1

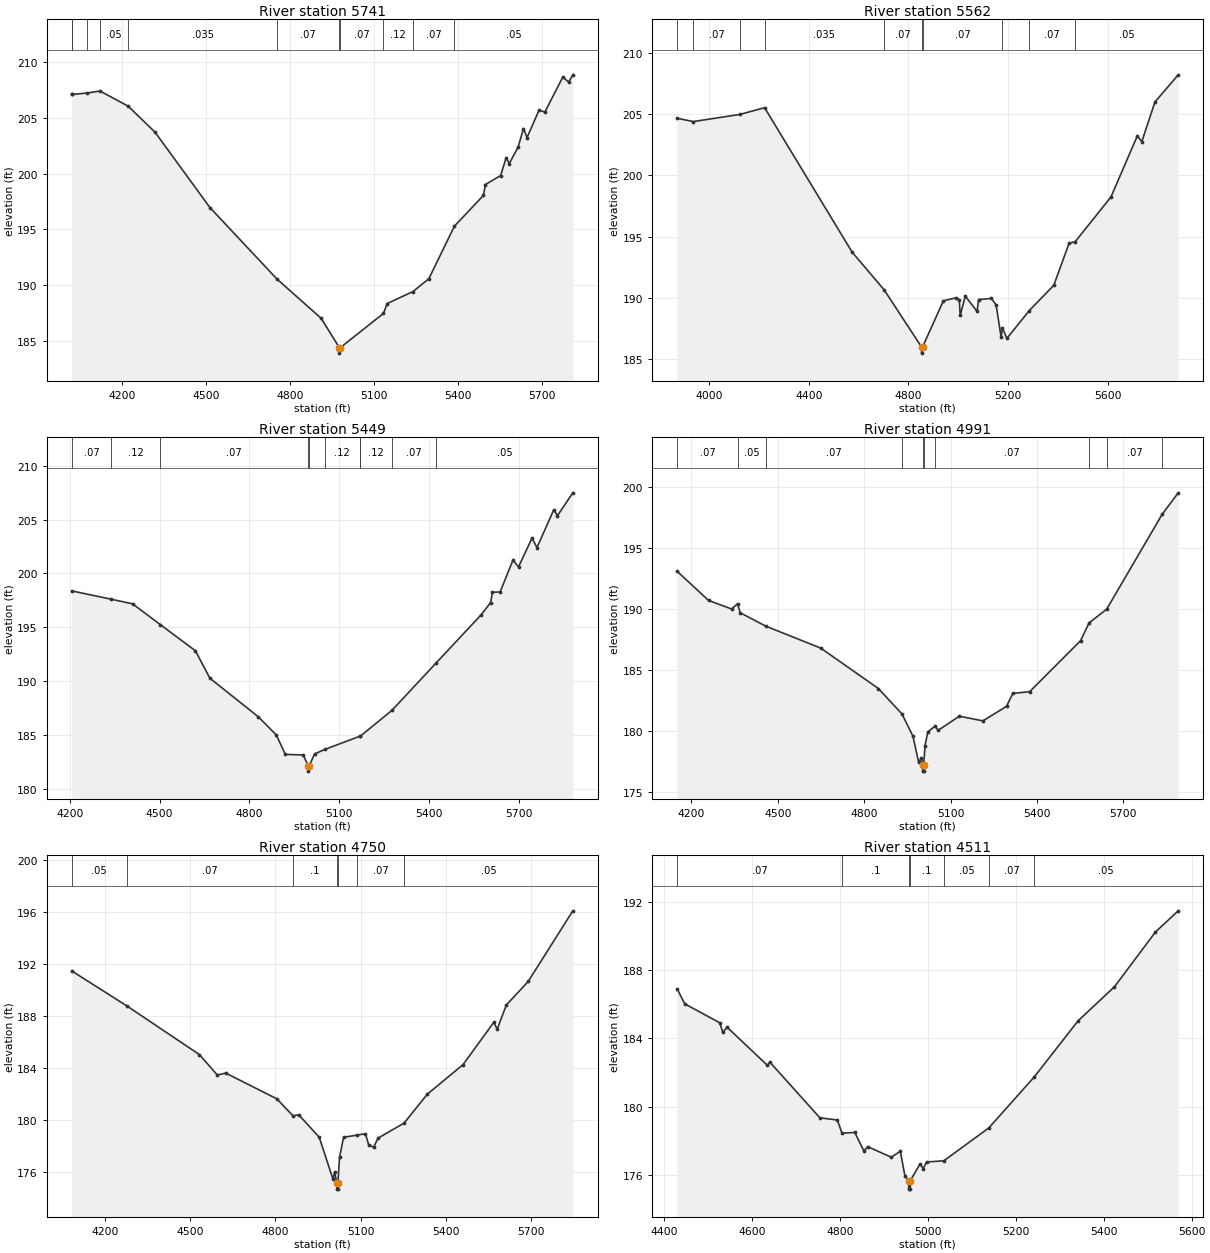
Type RM Length L Ch R = 1 ,5741    ,179,179,179
BEGIN DESCRIPTION:
Mapping XS 249bc658
END DESCRIPTION:
XS GIS Cut Line= 3
      2516966.37     13487592.73      2517922.65     13487833.36
      2518678.87     13487561.49
#Sta/Elev= 30
  4020.6  207.09  4021.1  207.09  4075.9  207.22  4121.7   207.4  4222.4  206.04
  4318.2  203.71  4514.2  196.96  4753.9  190.55  4911.1  187.05  4976.2  184.42
  4976.4  183.92  4980.2  184.42  5134.1  187.48  5147.3  188.36  5239.7  189.44
  5296.1  190.59  5387.6   195.3  5491.1  198.05    5498  199.02  5552.6  199.83
  5572.4  201.44  5583.3   200.9  5614.9  202.38  5634.1  204.04  5646.8  203.23
  5689.3  205.67  5710.5  205.52  5774.3  208.64  5795.6  208.21  5810.3  208.85
#Mann= 11 ,-1 , 0
  4020.6     .07       0  4021.1     .05       0  4075.9     .07       0
  4121.7     .05       0  4222.4    .035       0  4753.9     .07       0
  4976.2     .05       0  4980.2     .07       0  5134.1     .12       0
  5239.7     .07       0  5387.6     .05       0
Bank Sta=4976.2,4980.2
XS Rating Curve= 0 ,0
Exp/Cntr=0.3,0.1

Type RM Length L Ch R = 1 ,5562    ,113,113,113
BEGIN DESCRIPTION:
Mapping XS 69188688
END DESCRIPTION:
XS GIS Cut Line= 6
      2516813.24      13487689.6      2517738.27     13487852.11
       2517816.4     13487902.11      2517885.15     13487980.23
      2517947.65     13487992.73      2518688.25     13487664.62
#Sta/Elev= 30
  3871.7  204.66  3936.3  204.39  4123.4  204.97  4222.7  205.52  4574.1  193.74
  4702.4  190.67  4852.5  186.01  4852.8  185.51  4856.5  186.01  4940.1  189.77
  4989.4  190.02  5003.7  189.87  5007.6  188.59    5028  190.16  5075.4  188.91
  5081.3  189.88    5133  189.97    5152  189.42  5171.9  186.79  5176.8  187.57
  5194.9  186.71  5284.9  188.98  5383.1  191.04  5444.6  194.47  5468.8  194.59
  5612.5  198.24  5718.1  203.21  5736.4  202.76  5789.2  205.99  5882.5   208.2
#Mann= 10 ,-1 , 0
  3871.7     .05       0  3936.3     .07       0  4123.4     .05       0
  4222.7    .035       0  4702.4     .07       0  4852.5     .05       0
  4856.5     .07       0  5176.8     .12       0  5284.9     .07       0
  5468.8     .05       0
Bank Sta=4852.5,4856.5
XS Rating Curve= 0 ,0
Exp/Cntr=0.3,0.1

Type RM Length L Ch R = 1 ,5449    ,458,458,458
BEGIN DESCRIPTION:
Mapping XS 218ebedf
END DESCRIPTION:
XS GIS Cut Line= 3
      2517082.04     13488070.86      2517875.77     13488086.48
      2518703.32     13487789.82
#Sta/Elev= 30
  4206.5  198.38  4339.3   197.6  4409.5  197.18  4502.5  195.24  4619.5  192.81
  4667.7  190.26  4829.6  186.67  4889.6  184.98  4919.6  183.18  4979.6  183.12
  4995.5  182.12  4995.7  181.62  4999.5  182.12  5017.5  183.22  5051.7  183.64
  5168.1  184.86  5170.5  184.88  5275.9  187.28  5422.8  191.67  5573.2  196.15
  5605.1   197.3  5611.3  198.26  5636.8  198.28  5679.4  201.23  5698.3  200.62
  5743.2  203.29  5759.8  202.41    5816  205.93  5828.2  205.38  5879.5   207.5
#Mann= 10 ,-1 , 0
  4206.5     .07       0  4339.3     .12       0  4502.5     .07       0
  4995.5     .05       0  4999.5     .07       0  5051.7     .12       0
  5168.1     .07       0  5170.5     .12       0  5275.9     .07       0
  5422.8     .05       0
Bank Sta=4995.5,4999.5
XS Rating Curve= 0 ,0
Exp/Cntr=0.3,0.1

Type RM Length L Ch R = 1 ,4991    ,241,241,241
BEGIN DESCRIPTION:
Mapping XS 32536253
END DESCRIPTION:
XS GIS Cut Line= 3
      2517025.78     13488520.86      2517869.52     13488514.61
      2518659.73     13488089.83
#Sta/Elev= 30
  4150.2   193.1  4259.4  190.71  4339.4  190.01  4360.1  190.44  4369.4   189.7
  4458.4   188.6  4649.4   186.8  4849.4  183.49  4931.2  181.41  4969.4  179.59
  4989.2  177.45  4999.1  177.82  5002.8  177.22    5003  176.72  5006.5  176.72
  5006.8  177.22  5011.5   178.8    5021  179.94  5047.3  180.42  5056.9  180.06
  5130.6  181.22  5212.6  180.84  5294.5  182.03  5316.4  183.09  5374.8  183.23
  5551.8  187.41  5581.4  188.87  5642.4  189.99  5835.3  197.77  5891.1  199.53
#Mann= 10 ,-1 , 0
  4150.2     .07       0  4360.1     .05       0  4458.4     .07       0
  4931.2      .1       0  5002.8     .05       0  5006.8      .1       0
  5047.3     .07       0  5581.4     .05       0  5642.4     .07       0
  5835.3     .05       0
Bank Sta=5002.8,5006.8
XS Rating Curve= 0 ,0
Exp/Cntr=0.3,0.1

Type RM Length L Ch R = 1 ,4750    ,239,239,239
BEGIN DESCRIPTION:
Mapping XS e0a907be
END DESCRIPTION:
XS GIS Cut Line= 3
       2517127.9     13488889.25      2518006.33     13488677.46
      2518787.61     13488316.33
#Sta/Elev= 30
  4082.7  191.47  4275.6   188.8  4532.3  185.04  4595.3  183.47  4624.9  183.62
  4804.9  181.64  4861.5  180.34  4882.1  180.41  4954.1  178.69  5002.7  175.45
  5008.2  176.02  5015.9   175.2  5016.1   174.7  5019.6   174.7  5019.9   175.2
  5025.6  177.15  5039.9  178.68  5088.8  178.86    5117  178.96  5128.4  178.09
  5145.8  177.92  5161.1  178.62  5253.2  179.78  5334.8     182  5460.5  184.27
  5568.7  187.52  5580.7  186.99  5612.8  188.85  5689.8  190.66    5847  196.09
#Mann= 7 ,-1 , 0
  4082.7     .05       0  4275.6     .07       0  4861.5      .1       0
  5015.9     .05       0  5019.9      .1       0  5088.8     .07       0
  5253.2     .05       0
Bank Sta=5015.9,5019.9
XS Rating Curve= 0 ,0
Exp/Cntr=0.3,0.1

Type RM Length L Ch R = 1 ,4511    ,144,144,144
BEGIN DESCRIPTION:
TRIB TO TRIB TO FIFTEENMILE CREEK 9.0
END DESCRIPTION:
XS GIS Cut Line= 3
      2517624.97     13488975.01        2518175.       13488825.
      2518724.99       13488675.
#Sta/Elev= 30
  4429.3   186.9  4446.6  186.02  4526.1  184.91    4533  184.37  4543.4  184.64
  4634.9  182.41  4640.1  182.61  4754.1  179.34  4793.8  179.21  4804.5  178.44
  4833.6  178.48  4854.3  177.39  4862.9  177.65  4916.5  177.03  4937.2  177.38
  4947.6  175.94    4956  175.66  4956.2  175.16  4959.7  175.16    4960  175.66
  4982.1  176.64  4989.1  176.36  4996.8  176.75  5036.1  176.82  5138.7  178.75
  5241.4  181.72  5341.5  185.02  5424.4  187.02  5517.7  190.23  5569.5  191.47
#Mann= 7 ,-1 , 0
  4429.3     .07       0  4804.5      .1       0    4956     .05       0
    4960      .1       0  5036.1     .05       0  5138.7     .07       0
  5241.4     .05       0
Bank Sta=4956,4960
XS Rating Curve= 0 ,0
Exp/Cntr=0.3,0.1

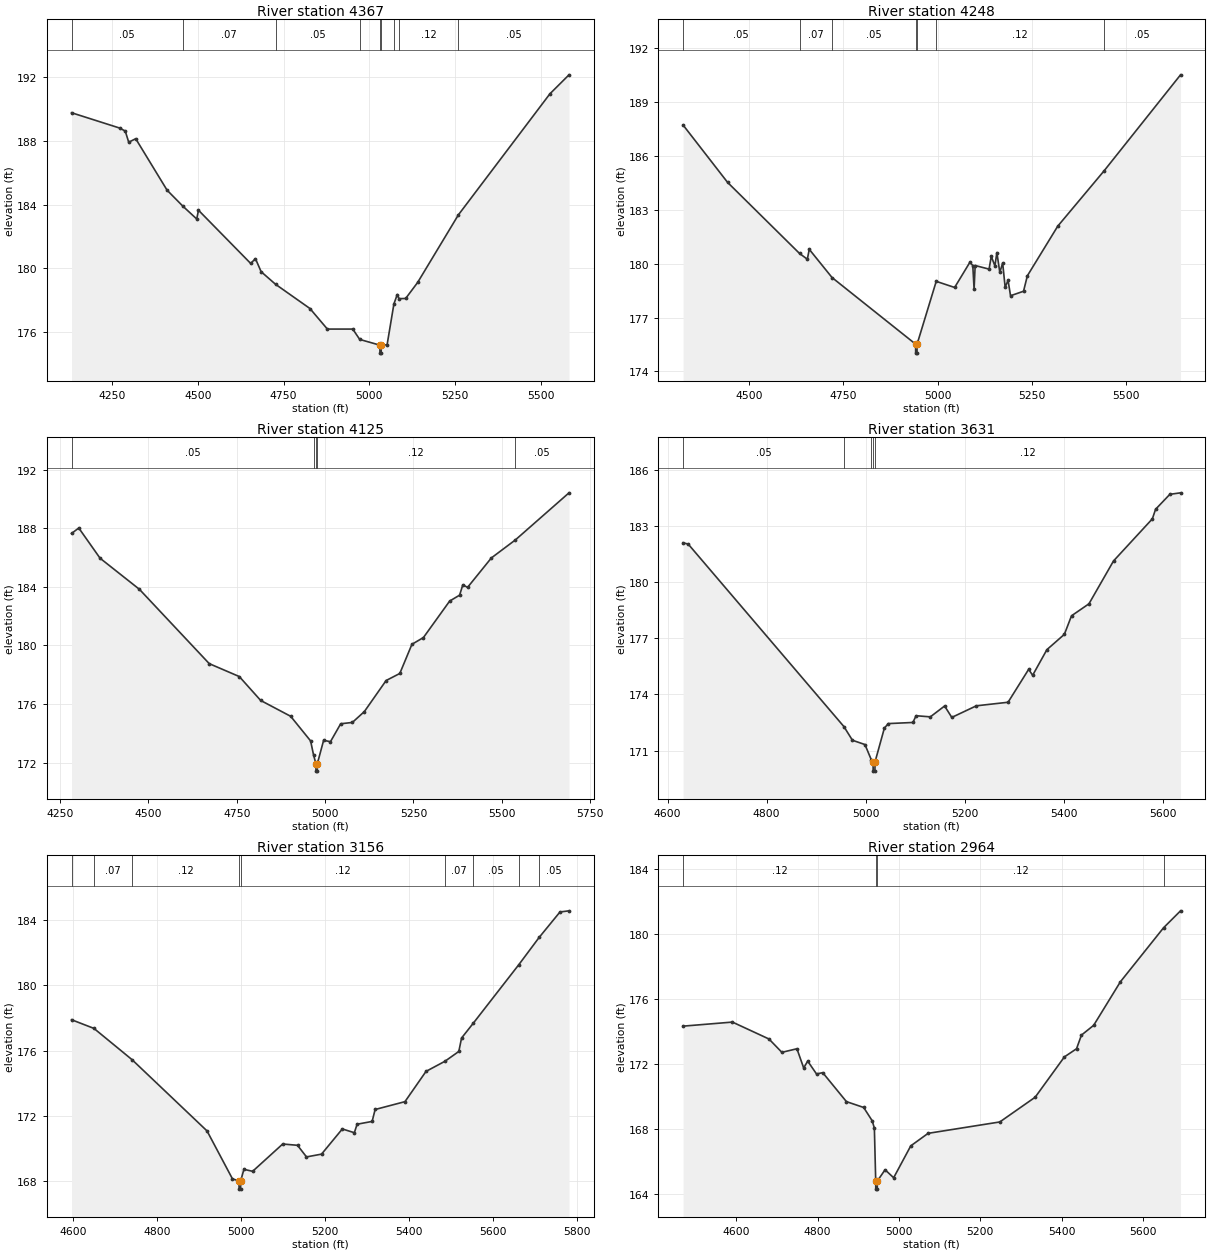
Type RM Length L Ch R = 1 ,4367    ,119,119,119
BEGIN DESCRIPTION:
Mapping XS 583140fc
END DESCRIPTION:
XS GIS Cut Line= 3
      2517370.89     13489104.54       2518221.6     13488951.76
      2518766.72     13488736.49
#Sta/Elev= 30
  4131.6  189.77  4271.7  188.81  4288.2  188.62  4298.3  187.92  4318.7  188.14
  4410.1  184.91  4456.4   183.9  4496.6   183.1  4501.7  183.65  4653.9  180.31
  4667.8  180.61  4684.4  179.79  4726.5     179  4826.7  177.48  4877.5  176.19
  4951.5  176.19  4971.8  175.54  5030.6  175.18  5030.8  174.68  5034.3  174.68
  5034.6  175.18  5051.6   175.2  5071.5  177.77  5081.3  178.36  5086.4   178.1
  5105.7  178.11  5140.8  179.12  5259.5  183.36  5526.4  190.96    5582  192.15
#Mann= 9 ,-1 , 0
  4131.6     .05       0  4456.4     .07       0  4726.5     .05       0
  4971.8     .12       0  5030.6     .05       0  5034.6     .12       0
  5071.5      .1       0  5086.4     .12       0  5259.5     .05       0
Bank Sta=5030.6,5034.6
XS Rating Curve= 0 ,0
Exp/Cntr=0.3,0.1

Type RM Length L Ch R = 1 ,4248    ,123,123,123
BEGIN DESCRIPTION:
Mapping XS 67fc2195
END DESCRIPTION:
XS GIS Cut Line= 6
      2517516.74     13489153.15      2518141.74     13489031.62
      2518200.77     13489069.82      2518266.74     13489080.23
      2518360.49     13489000.37      2518728.55     13488792.04
#Sta/Elev= 30
    4324   187.7  4442.3  184.51  4633.4  180.56  4654.1  180.24  4659.2  180.79
  4719.8  179.22  4941.7  175.52  4941.9  175.02  4945.4  175.02  4945.7  175.52
  4996.5  179.01  5045.4  178.67  5085.9  180.07  5093.6  179.89  5097.1  178.57
  5099.9  179.89  5136.9  179.69  5142.7   180.4  5152.4  179.87  5157.6  180.61
  5165.4  179.51    5173  180.03  5179.6  178.68  5187.3  179.07  5193.9  178.21
  5228.4  178.46  5238.6  179.32  5319.4  182.08  5442.3  185.15  5645.5  190.49
#Mann= 7 ,-1 , 0
    4324     .05       0  4633.4     .07       0  4719.8     .05       0
  4941.7     .05       0  4945.7     .05       0  4996.5     .12       0
  5442.3     .05       0
Bank Sta=4941.7,4945.7
XS Rating Curve= 0 ,0
Exp/Cntr=0.3,0.1

Type RM Length L Ch R = 1 ,4125    ,494,494,494
BEGIN DESCRIPTION:
Mapping XS 25f2696d
END DESCRIPTION:
XS GIS Cut Line= 3
      2517464.65     13489271.21      2518172.99     13489177.46
      2518794.53      13488871.9
#Sta/Elev= 30
  4282.8  187.64  4303.3  188.01  4363.5  185.95  4474.8  183.83  4672.3  178.76
  4757.3  177.88  4817.8  176.25  4902.6  175.17    4959  173.49  4967.3  172.54
    4974  171.93  4974.3  171.43  4977.8  171.43    4978  171.93  4995.8  173.53
  5015.2  173.44  5044.1  174.66  5077.1  174.75    5111  175.49  5172.6  177.61
  5211.3  178.09  5245.6  180.08  5278.1  180.54  5352.4  183.03  5380.4  183.43
  5389.6  184.14  5402.9  183.96  5470.3  185.97  5538.3   187.2  5689.9  190.41
#Mann= 5 ,-1 , 0
  4282.8     .05       0  4967.3     .12       0    4974     .05       0
    4978     .12       0  5538.3     .05       0
Bank Sta=4974,4978
XS Rating Curve= 0 ,0
Exp/Cntr=0.3,0.1

Type RM Length L Ch R = 1 ,3631    ,475,475,475
BEGIN DESCRIPTION:
TRIB TO TRIB TO FIFTEENMILE CREEK 7.0
END DESCRIPTION:
XS GIS Cut Line= 3
      2517875.04     13489724.99        2518225.       13489625.
      2518625.01     13489124.98
#Sta/Elev= 30
  4631.2   182.1  4641.6  182.03  4955.9  172.28  4973.1  171.55  4998.4  171.32
    5011  170.52  5014.8   170.4    5015   169.9  5018.5   169.9  5018.8   170.4
  5037.6   172.2  5045.6  172.44  5095.2   172.5  5101.6  172.86  5130.4   172.8
  5159.2  173.38  5173.7  172.77  5223.3  173.39  5287.3  173.58  5328.9  175.34
  5336.9  175.02  5365.7  176.39    5401  177.21  5415.4   178.2  5450.6  178.84
  5500.2  181.13  5578.6  183.38  5585.1  183.89  5613.9  184.69  5635.5  184.77
#Mann= 5 ,-1 , 0
  4631.2     .05       0  4955.9     .07       0    5011     .12       0
  5014.8     .05       0  5018.8     .12       0
Bank Sta=5014.8,5018.8
XS Rating Curve= 0 ,0
Exp/Cntr=0.3,0.1

Type RM Length L Ch R = 1 ,3156    ,192,192,192
BEGIN DESCRIPTION:
TRIB TO TRIB TO FIFTEENMILE CREEK 6.0
END DESCRIPTION:
XS GIS Cut Line= 3
      2518124.97       13489975.        2518525.       13489925.
      2519025.02     13489324.97
#Sta/Elev= 30
  4596.6  177.89  4649.9  177.36  4740.5  175.45  4919.1  171.09  4979.6  168.16
  4995.2  168.03  4995.5  167.53    4999  167.53  4999.2  168.03  5006.9  168.74
  5027.7  168.62  5099.3  170.29  5134.5  170.21  5155.9   169.5  5191.7  169.67
  5241.2  171.21  5269.8  170.98  5276.4   171.5  5312.1  171.67  5319.3   172.4
  5390.3  172.88  5440.4  174.73  5485.5  175.35  5518.5  175.95    5525  176.77
    5553  177.68  5661.4  181.26  5709.6  182.92  5759.3  184.48  5780.8  184.55
#Mann= 9 ,-1 , 0
  4596.6     .05       0  4649.9     .07       0  4740.5     .12       0
  4995.2     .05       0  4999.2     .12       0  5485.5     .07       0
    5553     .05       0  5661.4     .07       0  5709.6     .05       0
Bank Sta=4995.2,4999.2
XS Rating Curve= 0 ,0
Exp/Cntr=0.3,0.1

Type RM Length L Ch R = 1 ,2964    ,440,440,440
BEGIN DESCRIPTION:
TRIB TO TRIB TO FIFTEENMILE CREEK 1.2
END DESCRIPTION:
XS GIS Cut Line= 3
      2518173.48     13490197.64      2518761.32     13490003.26
      2519099.87     13489503.24
#Sta/Elev= 30
  4469.5  174.32  4590.8  174.57  4680.7  173.53  4712.4  172.71  4749.4  172.93
    4766  171.75  4775.9  172.17  4797.6  171.38  4812.9  171.46  4871.1  169.68
  4913.5  169.32  4934.5   168.5  4939.8  168.05  4943.1   164.8  4943.3   164.3
  4946.8   164.3  4947.1   164.8  4966.1  165.49  4987.2     165  5029.3  166.96
  5071.9  167.73  5248.2  168.43  5335.1  169.95    5407  172.43  5436.8  172.93
  5448.9  173.77  5478.9  174.37  5544.7  177.05  5650.8  180.37  5692.5  181.41
#Mann= 4 ,-1 , 0
  4469.5     .12       0  4943.1     .05       0  4947.1     .12       0
  5650.8     .05       0
Bank Sta=4943.1,4947.1
XS Rating Curve= 0 ,0
Exp/Cntr=0.3,0.1

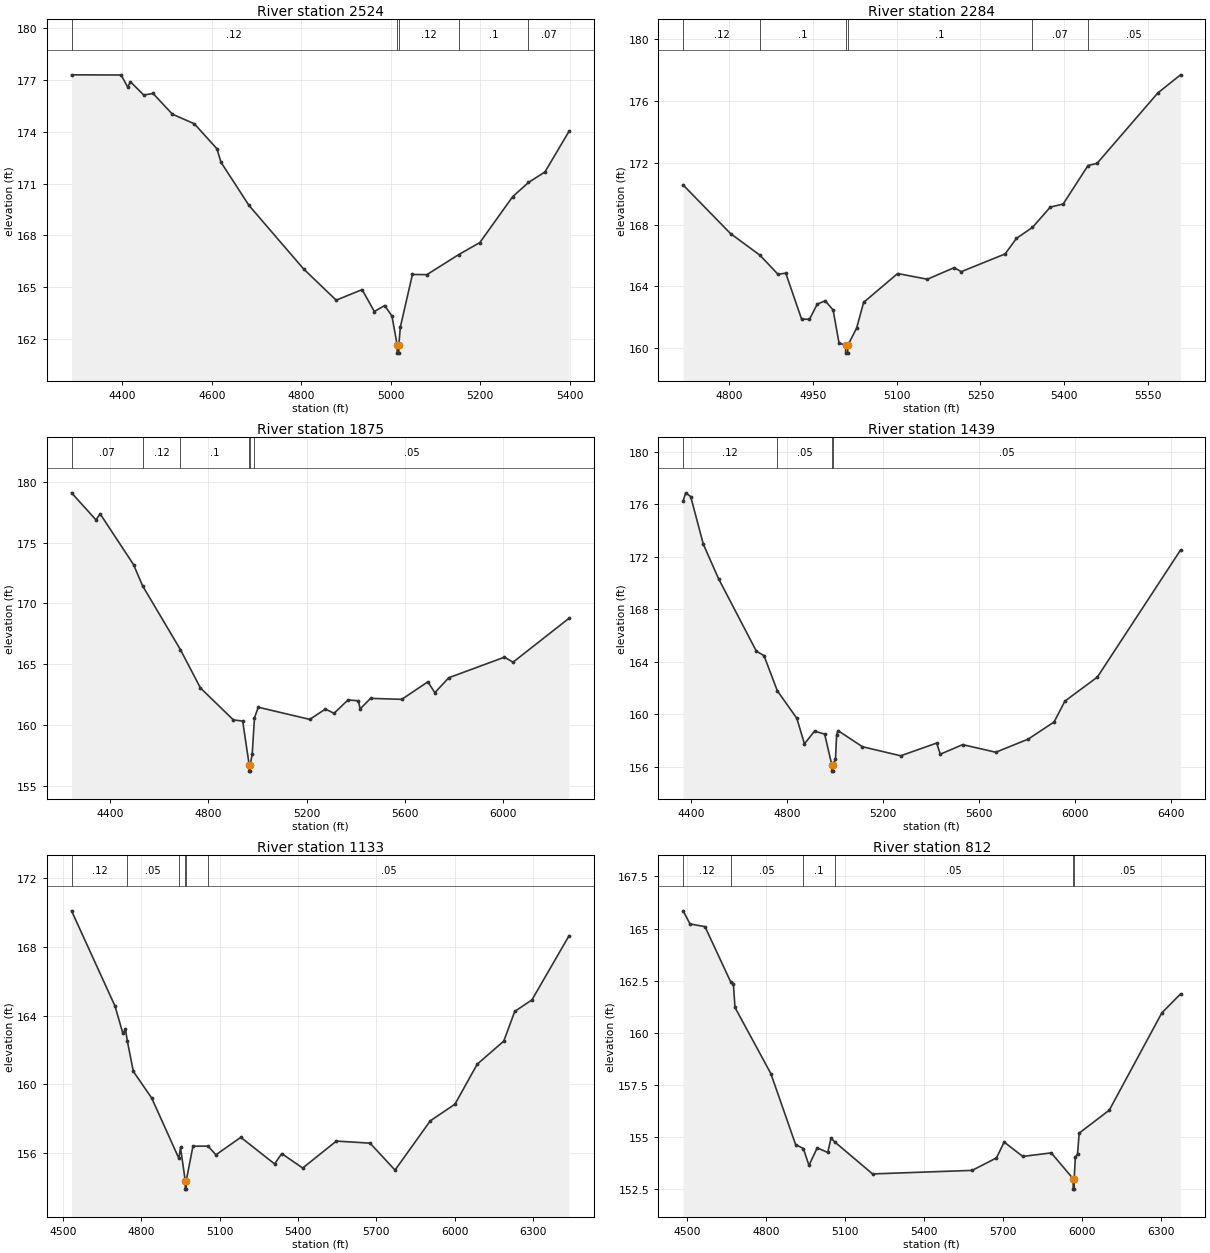
Type RM Length L Ch R = 1 ,2524    ,240,240,240
BEGIN DESCRIPTION:
TRIB TO TRIB TO FIFTEENMILE CREEK 5.0
END DESCRIPTION:
XS GIS Cut Line= 3
      2518645.73     13490789.76      2519055.02     13490204.96
      2519174.99     13489825.05
#Sta/Elev= 30
  4286.2   177.3    4397  177.29  4411.8  176.59  4417.9   176.9  4447.6  176.13
  4468.5  176.22  4511.7  175.02  4560.9  174.46  4611.5  173.01  4620.2  172.24
    4683  169.73  4805.1  166.05  4877.9  164.24  4935.9  164.85  4963.3  163.58
  4986.4  163.93  5002.6  163.32  5014.1  161.67  5014.4  161.17  5017.9  161.17
  5018.1  161.67  5021.4  162.68  5048.4  165.73  5080.8  165.72  5151.8  166.88
  5199.2  167.58  5272.6  170.24  5307.9  171.06  5344.7  171.67  5398.4  174.02
#Mann= 5 ,-1 , 0
  4286.2     .12       0  5014.1     .05       0  5018.1     .12       0
  5151.8      .1       0  5307.9     .07       0
Bank Sta=5014.1,5018.1
XS Rating Curve= 0 ,0
Exp/Cntr=0.3,0.1

Type RM Length L Ch R = 1 ,2284    ,409,409,409
BEGIN DESCRIPTION:
TRIB TO TRIB TO FIFTEENMILE CREEK 4.0
END DESCRIPTION:
XS GIS Cut Line= 3
      2519024.98     13490575.02        2519225.       13490375.
      2519325.01     13489774.95
#Sta/Elev= 30
  4717.4  170.57  4802.3  167.42    4855  166.02  4887.1  164.79  4901.3  164.85
  4929.6  161.88  4943.7  161.86  4957.8  162.85    4972  163.06  4986.1  162.47
  4996.7  160.33  5008.4  160.17  5008.7  159.67  5012.2  159.67  5012.4  160.17
  5028.2  161.29  5040.8  162.96  5101.7  164.83  5154.9  164.46    5203  165.21
  5215.7  164.95  5294.3   166.1  5314.6  167.11  5343.3  167.82  5375.4  169.14
  5398.2  169.33  5442.8  171.83    5459  171.97    5568  176.54  5608.6  177.71
#Mann= 6 ,-1 , 0
  4717.4     .12       0    4855      .1       0  5008.4     .05       0
  5012.4      .1       0  5343.3     .07       0  5442.8     .05       0
Bank Sta=5008.4,5012.4
XS Rating Curve= 0 ,0
Exp/Cntr=0.3,0.1

Type RM Length L Ch R = 1 ,1875    ,436,436,436
BEGIN DESCRIPTION:
TRIB TO TRIB TO FIFTEENMILE CREEK 0.0
END DESCRIPTION:
XS GIS Cut Line= 3
      2518875.07     13490879.11      2519564.65     13490564.88
      2520402.79     13489611.79
#Sta/Elev= 30
  4242.2  179.11  4341.5  176.89  4359.1  177.37  4494.9   173.2  4531.9  171.45
  4685.6  166.21  4767.4  163.05  4901.5  160.42  4939.7  160.32  4966.2   156.7
  4966.5   156.2    4970   156.2  4970.2   156.7  4978.4   157.6  4987.7  160.59
  5003.2  161.46  5212.9  160.46  5276.8  161.31  5311.9  160.96  5368.8  162.06
  5411.5  161.99  5418.1  161.32  5460.8  162.19    5588  162.11  5694.2  163.55
  5722.7  162.66  5779.6  163.89  6006.4  165.58  6041.5  165.17  6269.2  168.78
#Mann= 6 ,-1 , 0
  4242.2     .07       0  4531.9     .12       0  4685.6      .1       0
  4966.2     .05       0  4970.2      .1       0  4987.7     .05       0
Bank Sta=4966.2,4970.2
XS Rating Curve= 0 ,0
Exp/Cntr=0.3,0.1

Type RM Length L Ch R = 1 ,1439    ,306,306,306
BEGIN DESCRIPTION:
TRIB TO TRIB TO FIFTEENMILE CREEK 2.0
END DESCRIPTION:
XS GIS Cut Line= 3
      2519124.99       13491125.        2519725.       13490925.
      2520925.01     13490124.99
#Sta/Elev= 30
    4367  176.25  4377.6  176.87  4398.6  176.58  4451.3  172.95  4514.6  170.33
  4672.7  164.79  4704.3  164.46  4759.8  161.78  4841.4  159.67    4873  157.73
  4915.1   158.7  4957.3  158.47  4986.9  156.15  4987.2  155.65  4990.7  155.65
  4990.9  156.15  5002.5  156.54    5007  158.37    5013  158.74  5115.1  157.51
  5274.4  156.82  5424.6  157.79  5439.6  156.94  5532.8  157.67    5671  157.09
  5806.2  158.09  5914.4   159.4  5959.4  160.99  6094.7  162.82  6441.7  172.51
#Mann= 4 ,-1 , 0
    4367     .12       0  4759.8     .05       0  4986.9     .05       0
  4990.9     .05       0
Bank Sta=4986.9,4990.9
XS Rating Curve= 0 ,0
Exp/Cntr=0.3,0.1

Type RM Length L Ch R = 1 ,1133    ,321,321,321
BEGIN DESCRIPTION:
TRIB TO TRIB TO FIFTEENMILE CREEK 1.1
END DESCRIPTION:
XS GIS Cut Line= 3
      2519309.08     13491174.27      2519775.11     13491214.95
      2520967.07     13490410.36
#Sta/Elev= 30
  4532.2  170.11  4698.7  164.56  4728.9  162.97  4738.9  163.22  4745.6  162.55
    4769  160.75  4839.3   159.2  4943.6  155.68  4949.7  156.32  4967.8  154.39
    4968  153.89  4971.5  153.89  4971.8  154.39  4997.4  156.39  5055.1   156.4
  5085.4  155.89  5180.8  156.91  5310.1  155.36  5337.7  155.96    5418  155.12
  5546.9  156.69  5675.9  156.57  5771.7     155  5906.7  157.87  6001.3  158.84
  6086.5  161.17  6188.4  162.52  6230.5  164.25  6296.3  164.92  6438.1  168.65
#Mann= 6 ,-1 , 0
  4532.2     .12       0  4745.6     .05       0  4943.6      .1       0
  4967.8     .05       0  4971.8      .1       0  5055.1     .05       0
Bank Sta=4967.8,4971.8
XS Rating Curve= 0 ,0
Exp/Cntr=0.3,0.1

Type RM Length L Ch R = 1 ,812     ,597,597,597
BEGIN DESCRIPTION:
Mapping XS 096f47a0
END DESCRIPTION:
XS GIS Cut Line= 4
      2519434.64     13491218.51      2519669.03     13491531.04
       2520210.7     13491429.48      2520783.62     13490674.27
#Sta/Elev= 30
  4483.8  165.85    4510  165.22  4566.9  165.09  4664.4  162.44  4674.6  162.36
  4680.9  161.21  4816.9  158.04  4911.1  154.63  4940.6  154.44  4961.9  153.63
  4993.1  154.47  5033.1  154.25  5045.7  154.94  5059.4  154.76  5203.4  153.22
  5581.8  153.39  5674.3  153.99  5703.4  154.75  5774.1  154.06  5882.2  154.23
  5965.5  152.99  5965.8  152.49  5969.3  152.49  5969.5  152.99  5973.8  154.02
  5982.1  154.18  5988.4  155.18  6102.7  156.28  6302.4  160.95  6373.5  161.86
#Mann= 6 ,-1 , 0
  4483.8     .12       0  4664.4     .05       0  4940.6      .1       0
  5059.4     .05       0  5965.5     .05       0  5969.5     .05       0
Bank Sta=5965.5,5969.5
XS Rating Curve= 0 ,0
Exp/Cntr=0.3,0.1

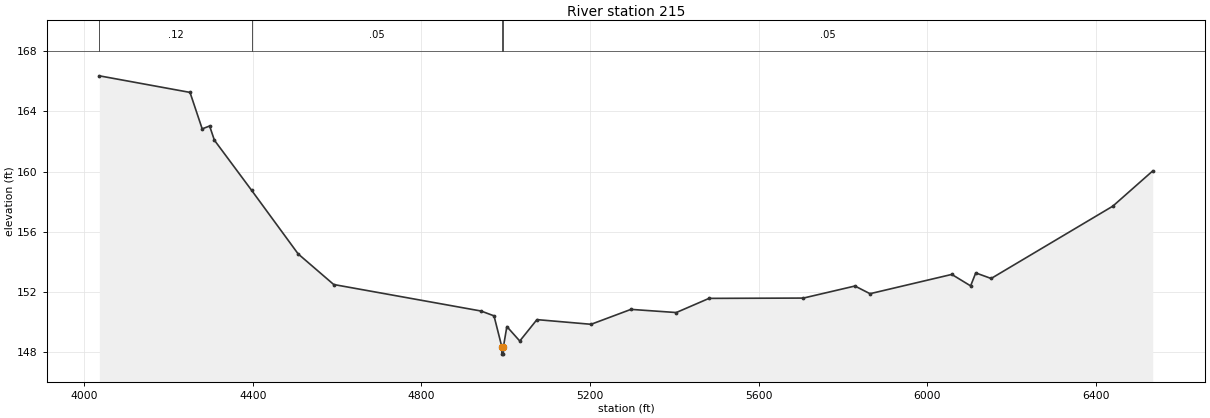
Type RM Length L Ch R = 1 ,215     ,0,0,0
BEGIN DESCRIPTION:
TRIB TO TRIB TO FIFTEENMILE CREEK 1.0
END DESCRIPTION:
XS GIS Cut Line= 4
      2519423.56     13491225.03       2519762.1     13492006.27
      2520031.19     13492058.36      2520812.41     13490929.93
#Sta/Elev= 30
  4036.3  166.35  4251.3  165.25  4280.2  162.83  4297.8  163.02  4309.1  162.08
  4397.7  158.74  4507.8  154.53  4592.1   152.5  4941.6  150.74  4972.2  150.42
  4990.6  148.38  4990.8  147.88  4994.3  147.88  4994.6  148.38  5002.7  149.71
  5033.3  148.75    5074  150.17  5202.4  149.86    5297  150.85  5404.4  150.64
  5482.1  151.58  5705.8   151.6  5828.1   152.4  5863.9  151.89  6057.8  153.17
  6102.4  152.41  6114.6  153.27  6151.1   152.9  6439.6   157.7  6534.3  160.04
#Mann= 4 ,-1 , 0
  4036.3     .12       0  4397.7     .05       0  4990.6     .05       0
  4994.6     .05       0
Bank Sta=4990.6,4994.6
XS Rating Curve= 0 ,0
Exp/Cntr=0.3,0.1

Chan Stop Cuts=-1
Use User Specified Reach Order=0
Composite Channel Slope=5