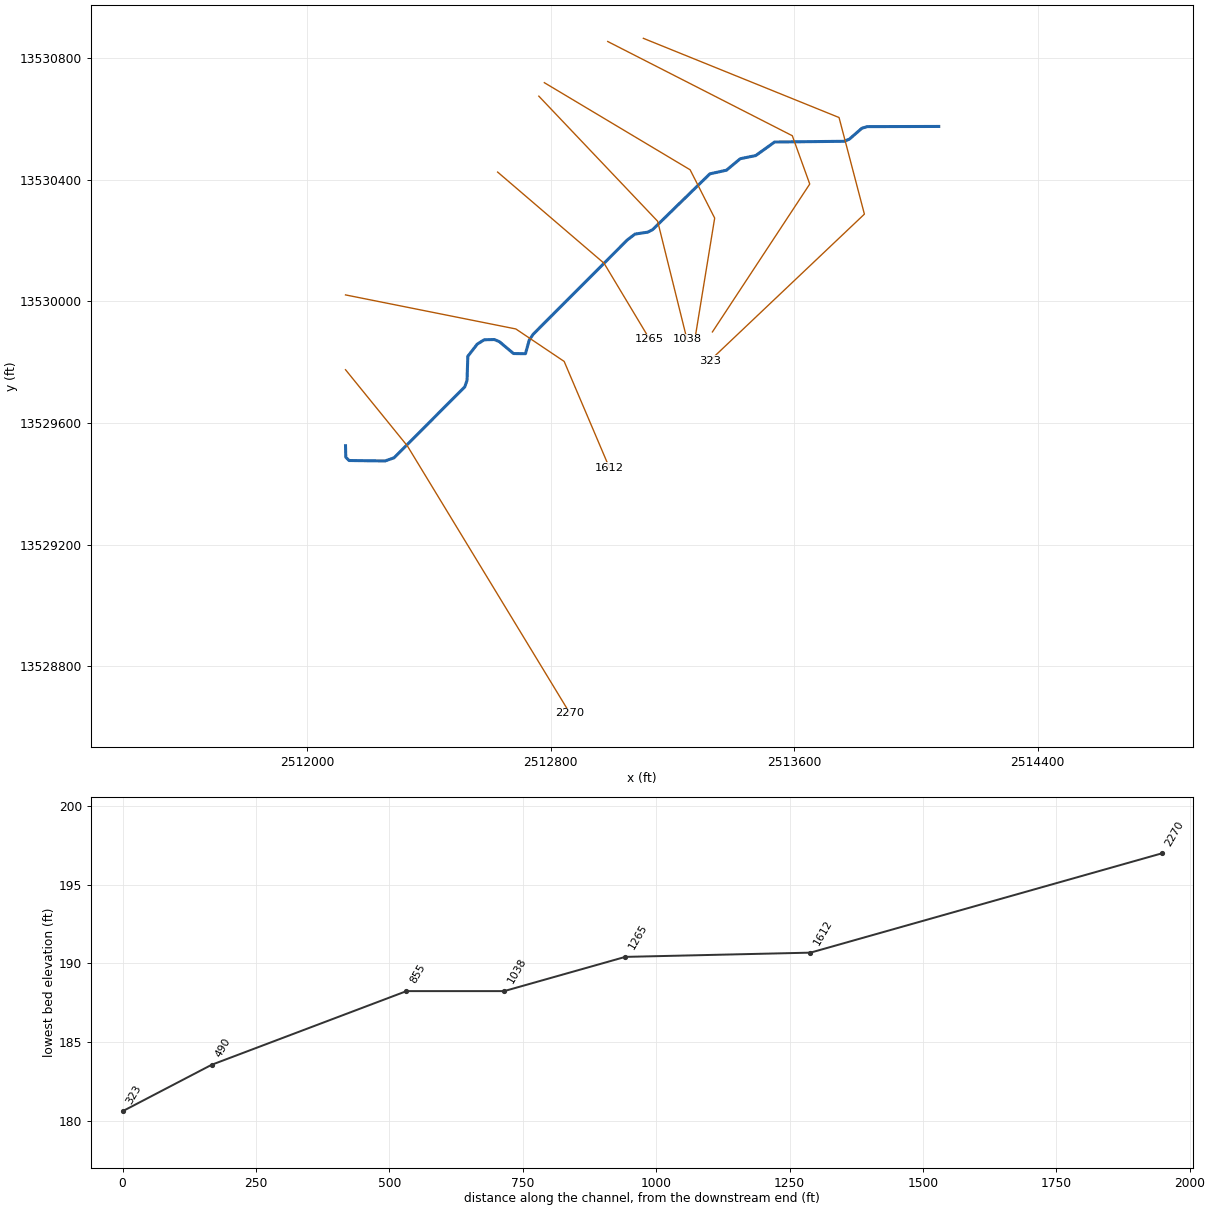
--- TRIB 2 TO BOGGY BRANCH.prj (project) ---

Proj Title=TRIB 2 TO BOGGY BRANCH Base Level Engineering
Current Plan=p01
Default Exp/Contr=0.3,0.1
English Units
Geom File=g01
Flow File=f01
Plan File=p01
BEGIN DESCRIPTION:
TRIB 2 TO BOGGY BRANCH
END DESCRIPTION:

--- TRIB 2 TO BOGGY BRANCH.p01 (plan) ---

Plan Title=Multiple Run
Short Identifier=Multiple
Geom File=g01
Flow File=f01
Subcritical Flow
K Sum by GR= 0
Std Step Tol= 0.01
Critical Tol= 0.01
Num of Std Step Trials= 20
Max Error Tol= 0.3
Flow Tol Ratio= 0.001
Split Flow NTrial= 30
Split Flow Tol= 0.02
Split Flow Ratio= 0.02
Log Output Level= 0
Friction Slope Method= 1
Unsteady Friction Slope Method= 2
Unsteady Bridges Friction Slope Method= 1
Parabolic Critical Depth
Global Vel Dist=  1 , 1 , 1
Global Log Level= 0
CheckData=True
Encroach Param= -1, 0, 0, 0
BEGIN DESCRIPTION:
Multiple Run
END DESCRIPTION:

--- TRIB 2 TO BOGGY BRANCH.f01 (steady flow) ---

Flow Title=Multiple
Number of Profiles=7
Profile Names=10-year,25-year,50-year,1pct_min,100-year,1pct_plu,500-year
River Rch & RM= TRIB 2 TO BOGGY ,Reach-1,2270
     516     818    1087     701    1398    2790    2284
River Rch & RM= TRIB 2 TO BOGGY ,Reach-1,1612
     538     854    1135     732    1460    2913    2385
Boundary for River Rch & Prof#=TRIB 2 TO BOGGY ,Reach-1,1
Up Type=0
Dn Type=3
Dn Slope=0.005
Boundary for River Rch & Prof#=TRIB 2 TO BOGGY ,Reach-1,2
Up Type=0
Dn Type=3
Dn Slope=0.005
Boundary for River Rch & Prof#=TRIB 2 TO BOGGY ,Reach-1,3
Up Type=0
Dn Type=3
Dn Slope=0.005
Boundary for River Rch & Prof#=TRIB 2 TO BOGGY ,Reach-1,4
Up Type=0
Dn Type=3
Dn Slope=0.005
Boundary for River Rch & Prof#=TRIB 2 TO BOGGY ,Reach-1,5
Up Type=0
Dn Type=3
Dn Slope=0.005
Boundary for River Rch & Prof#=TRIB 2 TO BOGGY ,Reach-1,6
Up Type=0
Dn Type=3
Dn Slope=0.005
Boundary for River Rch & Prof#=TRIB 2 TO BOGGY ,Reach-1,7
Up Type=0
Dn Type=3
Dn Slope=0.005

--- TRIB 2 TO BOGGY BRANCH.g01 (geometry) ---

Geom Title=Existing Conditions

River Reach=TRIB 2 TO BOGGY ,Reach-1
Reach XY= 30
      2512125.00     13529525.00      2512125.84     13529487.43
      2512136.44     13529476.41      2512255.00     13529474.92
      2512284.80     13529485.47      2512517.14     13529718.83
      2512524.47     13529740.22      2512527.08     13529819.34
      2512557.87     13529858.97      2512580.83     13529873.46
      2512614.27     13529874.27      2512630.95     13529867.15
      2512677.10     13529828.22      2512716.52     13529827.64
      2512729.13     13529872.84      2512741.73     13529891.42
      2513051.53     13530201.98      2513076.65     13530221.02
      2513118.95     13530227.53      2513134.68     13530235.78
      2513322.70     13530419.17      2513377.19     13530431.10
      2513422.80     13530468.92      2513473.26     13530479.19
      2513535.50     13530523.80      2513764.50     13530526.22
      2513781.06     13530533.14      2513822.67     13530569.25
      2513840.22     13530574.48      2514075.00     13530575.00

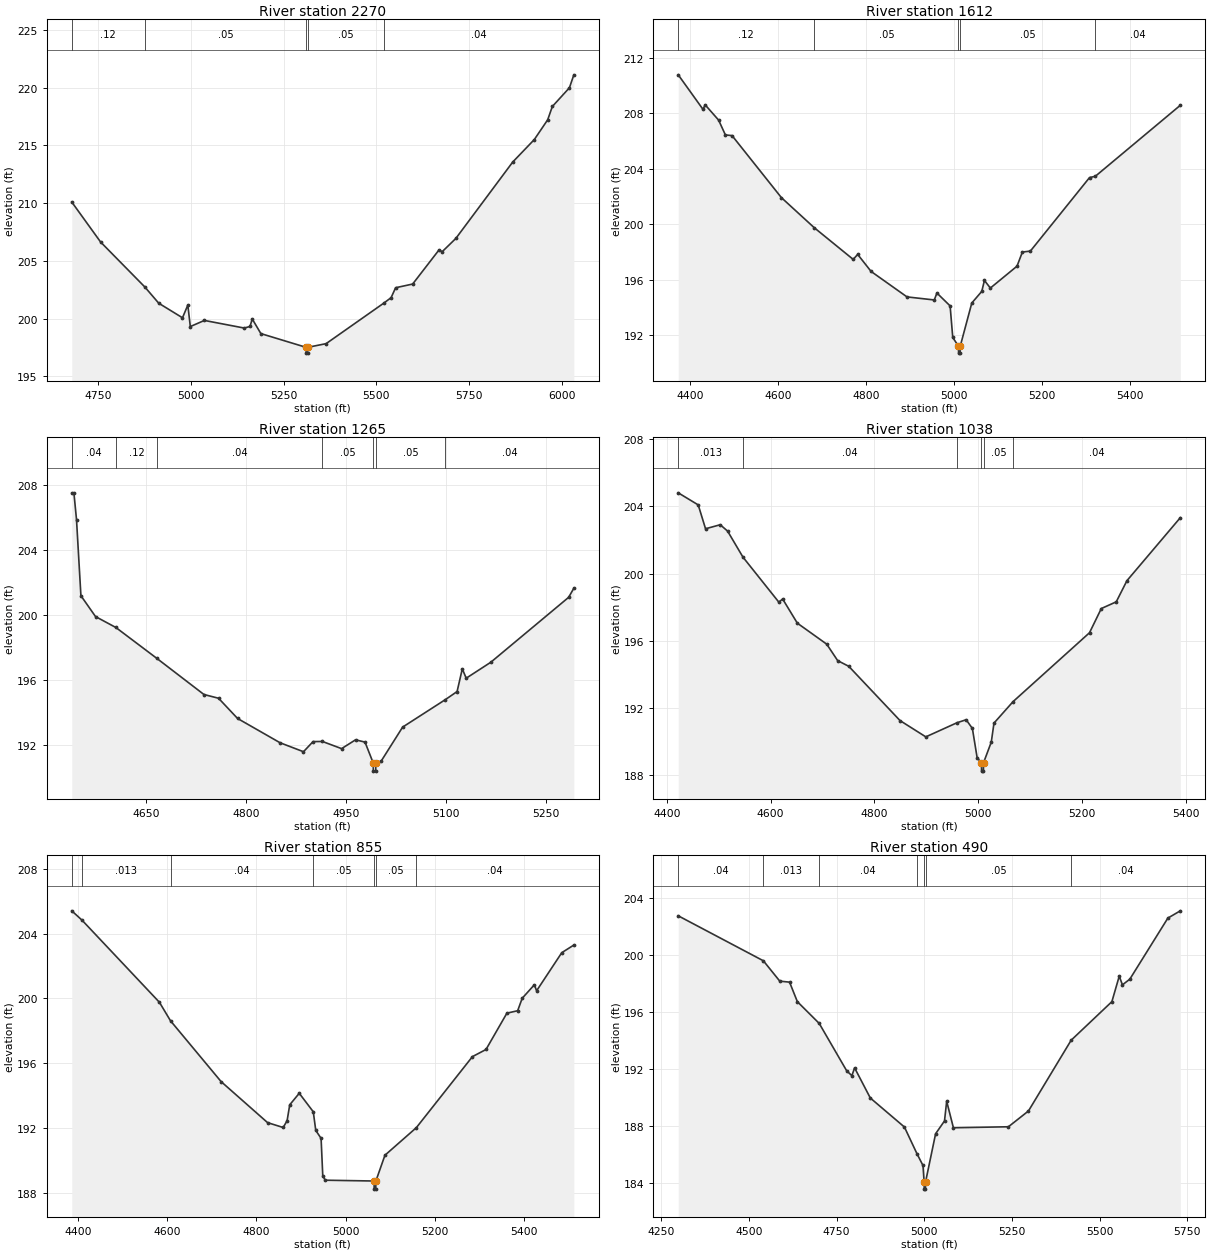
Type RM Length L Ch R = 1,2270,658,658,658
BEGIN DESCRIPTION:
TRIB 2 TO BOGGY BRANCH 4.0
END DESCRIPTION:
XS GIS Cut Line= 3
      2512124.99     13529775.01      2512328.39     13529524.28
      2512862.73     13528644.84
#Sta/Elev= 30
  4679.8  210.09  4757.4  206.63  4876.4  202.74  4914.0  201.33  4977.9  200.07
  4992.3  201.17  4999.0  199.31  5036.9  199.84  5144.3  199.18  5159.8  199.32
  5165.7  199.97  5189.0  198.70  5310.9  197.51  5311.1  197.01  5314.6  197.01
  5314.9  197.51  5364.6  197.83  5519.6  201.33  5539.6  201.81  5551.8  202.67
  5597.7  202.99  5668.8  205.95  5677.2  205.79  5714.0  206.94  5867.1  213.55
  5925.3  215.50  5961.3  217.21  5973.8  218.36  6019.8  219.98  6031.7  221.10
#Mann=5,-1,0
  4679.8    0.12       0  4876.4    0.05       0  5310.9    0.05       0
  5314.9    0.05       0  5519.6    0.04       0
Bank Sta=5310.9,5314.9
Exp/Cntr=0.3,0.1

Type RM Length L Ch R = 1,1612,347,347,347
BEGIN DESCRIPTION:
Mapping XS 75b8b308
END DESCRIPTION:
XS GIS Cut Line= 4
      2512124.97     13530021.04      2512684.90     13529909.06
      2512843.75     13529802.28      2512992.17     13529453.36
#Sta/Elev= 30
  4372.8  210.79  4429.0  208.30  4434.1  208.62  4464.6  207.52  4480.0  206.45
  4495.2  206.40  4607.4  201.92  4682.0  199.75  4770.6  197.46  4780.8  197.82
  4811.3  196.59  4893.0  194.75  4955.0  194.53  4961.0  195.03  4991.0  194.10
  4997.0  191.82  5010.0  191.19  5010.3  190.69  5013.8  190.69  5014.0  191.19
  5040.3  194.31  5063.0  195.15  5069.0  195.94  5082.5  195.39  5143.1  196.97
  5155.3  197.99  5173.5  198.06  5308.0  203.37  5321.1  203.46  5514.4  208.59
#Mann=5,-1,0
  4372.8    0.12       0  4682.0    0.05       0  5010.0    0.05       0
  5014.0    0.05       0  5321.1    0.04       0
Bank Sta=5010,5014
Exp/Cntr=0.3,0.1

Type RM Length L Ch R = 1,1265,227,227,227
BEGIN DESCRIPTION:
TRIB 2 TO BOGGY BRANCH 2.0
END DESCRIPTION:
XS GIS Cut Line= 3
      2512625.04     13530424.97      2512975.00     13530125.00
      2513125.01     13529874.98
#Sta/Elev= 30
  4539.1  207.49  4542.3  207.49  4546.2  205.85  4552.8  201.18  4574.7  199.90
  4605.2  199.23  4666.8  197.33  4737.2  195.12  4759.1  194.89  4787.6  193.65
  4851.3  192.16  4886.4  191.61  4900.7  192.23  4914.7  192.24  4943.5  191.80
  4964.4  192.34  4978.6  192.20  4990.9  190.92  4991.1  190.42  4994.6  190.42
  4994.9  190.92  5002.9  191.04  5035.0  193.12  5098.8  194.80  5116.6  195.30
  5124.4  196.69  5130.3  196.12  5167.2  197.10  5283.8  201.08  5291.6  201.64
#Mann=7,-1,0
  4539.1    0.04       0  4605.2    0.12       0  4666.8    0.04       0
  4914.7    0.05       0  4990.9    0.05       0  4994.9    0.05       0
  5098.8    0.04       0
Bank Sta=4990.9,4994.9
Exp/Cntr=0.3,0.1

Type RM Length L Ch R = 1,1038,183,183,183
BEGIN DESCRIPTION:
Mapping XS 497dcee1
END DESCRIPTION:
XS GIS Cut Line= 3
      2512760.44     13530674.66      2513151.04     13530263.22
      2513247.39     13529875.22
#Sta/Elev= 30
  4422.2  204.81  4460.7  204.09  4474.8  202.67  4503.1  202.91  4517.3  202.53
  4546.9  200.98  4616.0  198.30  4623.3  198.49  4651.6  197.05  4708.2  195.80
  4729.3  194.82  4750.7  194.48  4849.4  191.25  4899.1  190.28  4959.1  191.12
  4976.8  191.30  4988.8  190.78  4998.0  189.03  5006.3  188.74  5006.5  188.24
  5010.0  188.24  5010.3  188.74  5025.2  189.97  5030.4  191.10  5067.2  192.38
  5214.4  196.48  5237.1  197.92  5265.9  198.32  5286.5  199.58  5389.3  203.33
#Mann=6,-1,0
  4422.2   0.013       0  4546.9    0.04       0  4959.1    0.05       0
  5006.3    0.05       0  5010.3    0.05       0  5067.2    0.04       0
Bank Sta=5006.3,5010.3
Exp/Cntr=0.3,0.1

Type RM Length L Ch R = 1,855,365,365,365
BEGIN DESCRIPTION:
Mapping XS d51fb44b
END DESCRIPTION:
XS GIS Cut Line= 4
      2512778.63     13530718.96      2513257.81     13530432.49
      2513338.54     13530273.64      2513276.05     13529890.87
#Sta/Elev= 30
  4386.5  205.40  4409.6  204.82  4582.8  199.76  4607.6  198.62  4720.9  194.87
  4825.0  192.34  4859.9  192.04  4868.7  192.46  4874.6  193.44  4895.9  194.15
  4927.3  193.01  4932.9  191.86  4944.8  191.37  4948.6  189.05  4954.2  188.79
  5063.5  188.74  5063.7  188.24  5067.2  188.24  5067.5  188.74  5087.8  190.33
  5158.1  192.03  5283.7  196.41  5314.1  196.85  5360.9  199.09  5385.0  199.24
  5395.2  200.01  5422.4  200.84  5427.4  200.47  5483.8  202.82  5510.8  203.29
#Mann=7,-1,0
  4386.5    0.04       0  4409.6   0.013       0  4607.6    0.04       0
  4927.3    0.05       0  5063.5    0.05       0  5067.5    0.05       0
  5158.1    0.04       0
Bank Sta=5063.5,5067.5
Exp/Cntr=0.3,0.1

Type RM Length L Ch R = 1,490,167,167,167
BEGIN DESCRIPTION:
Mapping XS bef23881
END DESCRIPTION:
XS GIS Cut Line= 4
      2512986.98     13530854.37      2513593.75     13530544.47
      2513651.04     13530385.62      2513331.15     13529899.28
#Sta/Elev= 30
  4298.2  202.75  4541.1  199.59  4587.9  198.16  4615.8  198.09  4638.0  196.72
  4700.4  195.19  4778.8  191.86  4793.6  191.52  4801.3  192.07  4846.2  189.95
  4943.5  187.91  4979.0  186.05  4996.4  185.21  4999.7  184.05  5000.0  183.55
  5003.5  183.55  5003.7  184.05  5032.4  187.44  5057.8  188.34  5064.0  189.72
  5083.2  187.86  5240.1  187.93  5297.3  189.04  5419.1  194.01  5535.3  196.72
  5556.3  198.51  5565.4  197.90  5586.5  198.30  5695.0  202.59  5730.5  203.10
#Mann=7,-1,0
  4298.2    0.04       0  4541.1   0.013       0  4700.4    0.04       0
  4979.0    0.05       0  4999.7    0.05       0  5003.7    0.05       0
  5419.1    0.04       0
Bank Sta=4999.7,5003.7
Exp/Cntr=0.3,0.1

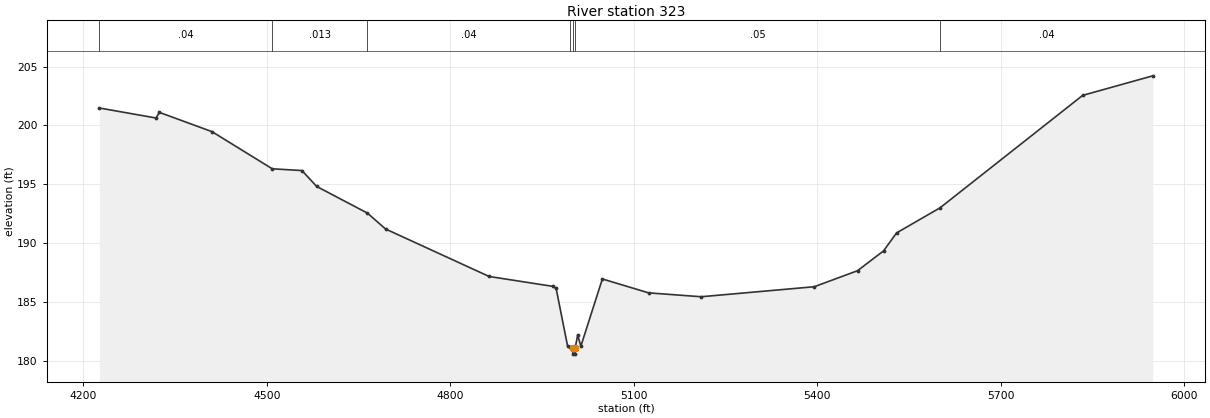
Type RM Length L Ch R = 1,323,0,0,0
BEGIN DESCRIPTION:
Mapping XS 4085a35f
END DESCRIPTION:
XS GIS Cut Line= 4
      2513104.15     13530864.79      2513747.40     13530604.37
      2513830.73     13530286.66      2513322.92     13529804.89
#Sta/Elev= 30
  4226.0  201.48  4318.7  200.63  4324.1  201.11  4410.3  199.47  4508.7  196.32
  4557.3  196.17  4581.4  194.82  4664.3  192.56  4694.0  191.21  4863.4  187.18
  4967.7  186.34  4972.9  186.16  4991.7  181.26  4996.2  181.17  5000.0  181.09
  5000.3  180.59  5003.8  180.59  5004.0  181.09  5008.1  182.22  5013.3  181.26
  5048.5  186.97  5124.1  185.79  5210.0  185.46  5395.0  186.31  5465.7  187.67
  5508.2  189.35  5529.6  190.88  5600.7  193.01  5833.8  202.55  5948.4  204.21
#Mann=7,-1,0
  4226.0    0.04       0  4508.7   0.013       0  4664.3    0.04       0
  4996.2    0.05       0  5000.0    0.05       0  5004.0    0.05       0
  5600.7    0.04       0
Bank Sta=5000,5004
Exp/Cntr=0.3,0.1

Chan Stop Cuts=-1