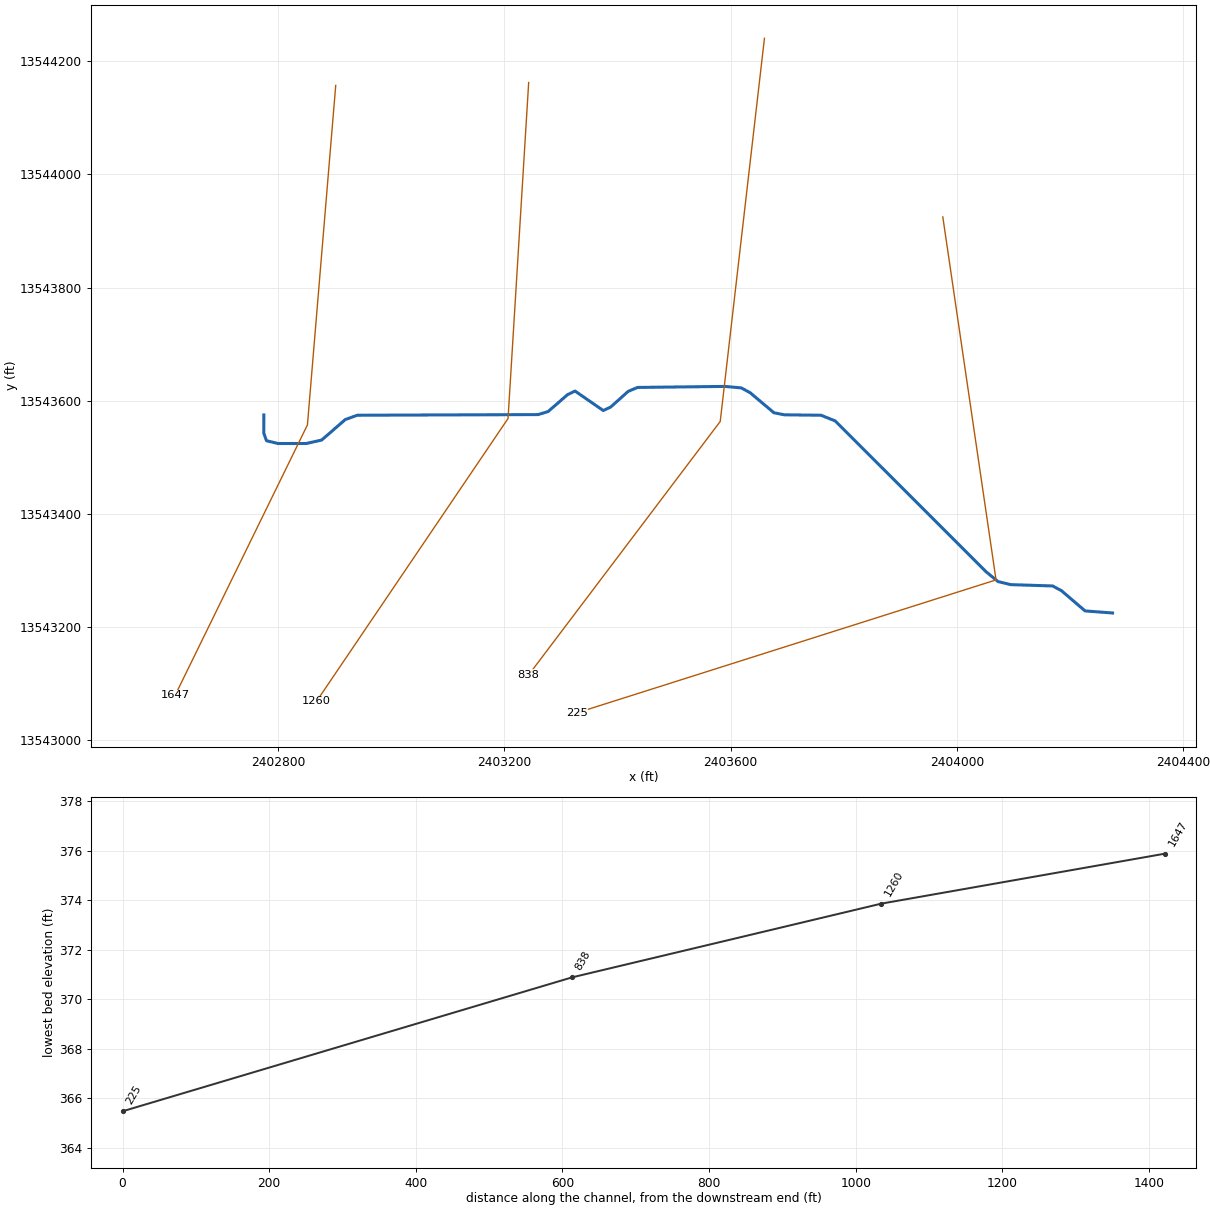
--- TRIB 2 TO BUTLER CREEK.prj (project) ---

Proj Title=TRIB 2 TO BUTLER CREEK Base Level Engineering
Current Plan=p01
Default Exp/Contr=0.3,0.1
English Units
Geom File=g01
Flow File=f01
Plan File=p01
BEGIN DESCRIPTION:
TRIB 2 TO BUTLER CREEK
END DESCRIPTION:

--- TRIB 2 TO BUTLER CREEK.p01 (plan) ---

Plan Title=Multiple Run
Short Identifier=Multiple
Geom File=g01
Flow File=f01
Subcritical Flow
K Sum by GR= 0
Std Step Tol= 0.01
Critical Tol= 0.01
Num of Std Step Trials= 20
Max Error Tol= 0.3
Flow Tol Ratio= 0.001
Split Flow NTrial= 30
Split Flow Tol= 0.02
Split Flow Ratio= 0.02
Log Output Level= 0
Friction Slope Method= 1
Unsteady Friction Slope Method= 2
Unsteady Bridges Friction Slope Method= 1
Parabolic Critical Depth
Global Vel Dist=  1 , 1 , 1
Global Log Level= 0
CheckData=True
Encroach Param= -1, 0, 0, 0
BEGIN DESCRIPTION:
Multiple Run
END DESCRIPTION:

--- TRIB 2 TO BUTLER CREEK.f01 (steady flow) ---

Flow Title=Multiple
Number of Profiles=7
Profile Names=10-year,25-year,50-year,1pct_min,100-year,1pct_plu,500-year
River Rch & RM= TRIB 2 TO BUTLER,Reach-1,1647
     362     573     759     488     975    1945    1588
Boundary for River Rch & Prof#=TRIB 2 TO BUTLER,Reach-1,1
Up Type=0
Dn Type=3
Dn Slope=0.005
Boundary for River Rch & Prof#=TRIB 2 TO BUTLER,Reach-1,2
Up Type=0
Dn Type=3
Dn Slope=0.005
Boundary for River Rch & Prof#=TRIB 2 TO BUTLER,Reach-1,3
Up Type=0
Dn Type=3
Dn Slope=0.005
Boundary for River Rch & Prof#=TRIB 2 TO BUTLER,Reach-1,4
Up Type=0
Dn Type=3
Dn Slope=0.005
Boundary for River Rch & Prof#=TRIB 2 TO BUTLER,Reach-1,5
Up Type=0
Dn Type=3
Dn Slope=0.005
Boundary for River Rch & Prof#=TRIB 2 TO BUTLER,Reach-1,6
Up Type=0
Dn Type=3
Dn Slope=0.005
Boundary for River Rch & Prof#=TRIB 2 TO BUTLER,Reach-1,7
Up Type=0
Dn Type=3
Dn Slope=0.005

--- TRIB 2 TO BUTLER CREEK.g01 (geometry) ---

Geom Title=Existing Conditions

River Reach=TRIB 2 TO BUTLER,Reach-1
Reach XY= 30
      2402775.00     13543575.00      2402774.92     13543542.99
      2402779.68     13543529.51      2402799.92     13543524.54
      2402849.92     13543524.53      2402877.28     13543530.66
      2402918.94     13543566.86      2402940.21     13543574.48
      2403259.84     13543575.65      2403277.45     13543581.00
      2403311.84     13543610.93      2403325.10     13543617.21
      2403374.90     13543582.79      2403388.16     13543589.07
      2403418.81     13543616.56      2403435.43     13543623.63
      2403590.18     13543625.43      2403619.06     13543622.74
      2403634.65     13543614.15      2403676.60     13543578.86
      2403695.10     13543575.25      2403759.78     13543574.48
      2403784.79     13543564.48      2404051.48     13543297.88
      2404072.57     13543280.52      2404095.05     13543275.12
      2404169.08     13543272.77      2404184.74     13543264.38
      2404226.51     13543228.64      2404275.00     13543225.00

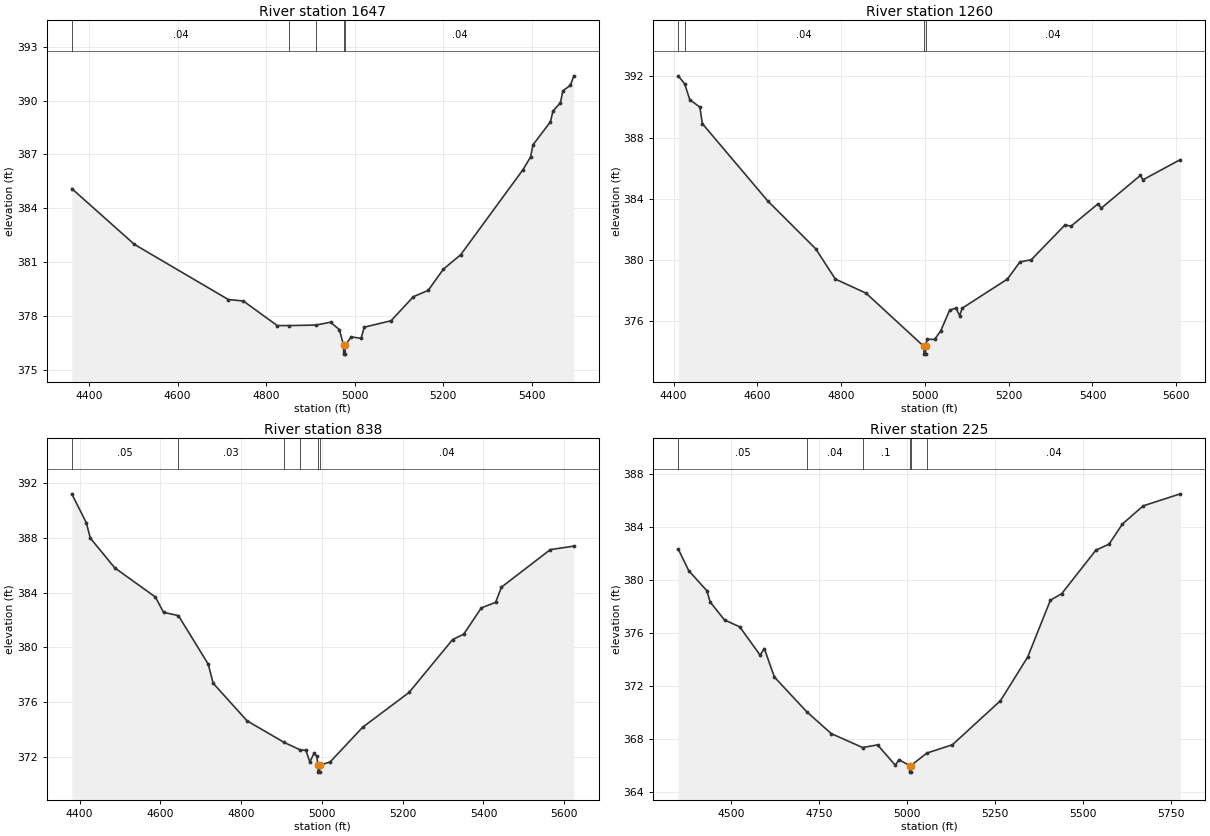
Type RM Length L Ch R = 1,1647,387,387,387
BEGIN DESCRIPTION:
TRIB 2 TO BUTLER CREEK 3.0
END DESCRIPTION:
XS GIS Cut Line= 3
      2402902.08     13544157.35      2402852.08     13543557.34
      2402618.30     13543079.56
#Sta/Elev= 30
  4361.0  385.10  4502.6  381.99  4714.6  378.92  4748.5  378.84  4825.0  377.47
  4852.2  377.47  4913.2  377.50  4945.4  377.66  4965.5  377.24  4974.8  376.38
  4975.1  375.88  4978.6  375.88  4978.8  376.38  4992.0  376.84  5014.6  376.76
  5021.4  377.38  5082.1  377.74  5132.7  379.08  5166.1  379.43  5200.2  380.61
  5239.6  381.42  5380.3  386.16  5397.2  386.86  5402.8  387.54  5442.2  388.82
  5447.8  389.42  5464.7  389.88  5470.3  390.55  5487.2  390.85  5495.0  391.38
#Mann=5,-1,0
  4361.0    0.04       0  4852.2    0.05       0  4913.2    0.04       0
  4974.8    0.04       0  4978.8    0.04       0
Bank Sta=4974.8,4978.8
Exp/Cntr=0.3,0.1

Type RM Length L Ch R = 1,1260,422,422,422
BEGIN DESCRIPTION:
Mapping XS 2db52f4a
END DESCRIPTION:
XS GIS Cut Line= 3
      2403243.10     13544162.53      2403206.64     13543568.73
      2402868.13     13543068.77
#Sta/Elev= 30
  4411.1  392.03  4426.4  391.51  4438.7  390.47  4462.7  389.99  4468.7  388.91
  4624.5  383.87  4739.2  380.74  4786.2  378.76  4859.5  377.84  4997.7  374.36
  4998.0  373.86  5001.5  373.86  5001.7  374.36  5005.4  374.83  5023.3  374.82
  5038.2  375.40  5059.2  376.74  5074.2  376.86  5083.0  376.38  5089.1  376.86
  5197.0  378.76  5226.9  379.88  5253.9  380.02  5334.7  382.30  5348.7  382.21
  5412.7  383.66  5421.1  383.39  5514.5  385.53  5520.5  385.24  5609.8  386.56
#Mann=4,-1,0
  4411.1    0.05       0  4426.4    0.04       0  4997.7    0.04       0
  5001.7    0.04       0
Bank Sta=4997.7,5001.7
Exp/Cntr=0.3,0.1

Type RM Length L Ch R = 1,838,613,613,613
BEGIN DESCRIPTION:
Mapping XS 54b661e6
END DESCRIPTION:
XS GIS Cut Line= 3
      2403659.77     13544240.65      2403581.64     13543563.53
      2403243.09     13543115.60
#Sta/Elev= 30
  4380.7  391.22  4416.6  389.11  4426.7  387.98  4487.1  385.81  4587.7  383.68
  4607.9  382.56  4644.7  382.32  4718.6  378.77  4730.7  377.38  4814.6  374.63
  4906.1  373.06  4946.6  372.50  4960.2  372.48  4970.2  371.62  4980.3  372.25
  4987.4  372.04  4990.4  371.38  4990.6  370.88  4994.1  370.88  4994.4  371.38
  5020.6  371.63  5101.3  374.17  5215.7  376.70  5323.7  380.57  5351.0  380.96
  5394.7  382.88  5430.1  383.29  5444.6  384.40  5565.4  387.14  5623.8  387.40
#Mann=6,-1,0
  4380.7    0.05       0  4644.7    0.03       0  4906.1    0.05       0
  4946.6    0.04       0  4990.4    0.04       0  4994.4    0.04       0
Bank Sta=4990.4,4994.4
Exp/Cntr=0.3,0.1

Type RM Length L Ch R = 1,225,0,0,0
BEGIN DESCRIPTION:
TRIB 2 TO BUTLER CREEK 1.0
END DESCRIPTION:
XS GIS Cut Line= 3
      2403975.00     13543925.01      2404069.08     13543283.47
      2403328.26     13543048.48
#Sta/Elev= 30
  4350.8  382.33  4380.7  380.69  4431.7  379.19  4441.8  378.31  4482.2  376.97
  4525.4  376.45  4583.3  374.31  4595.2  374.81  4623.7  372.66  4715.3  370.04
  4785.4  368.38  4874.3  367.33  4916.8  367.53  4967.3  365.99  4977.4  366.41
  5007.7  365.97  5008.0  365.47  5011.5  365.47  5011.7  365.97  5056.7  366.91
  5129.4  367.54  5265.8  370.87  5342.9  374.16  5407.5  378.46  5439.8  378.96
  5536.6  382.24  5574.1  382.70  5612.0  384.22  5670.9  385.59  5776.4  386.50
#Mann=6,-1,0
  4350.8    0.05       0  4715.3    0.04       0  4874.3     0.1       0
  5007.7    0.05       0  5011.7     0.1       0  5056.7    0.04       0
Bank Sta=5007.7,5011.7
Exp/Cntr=0.3,0.1

Chan Stop Cuts=-1