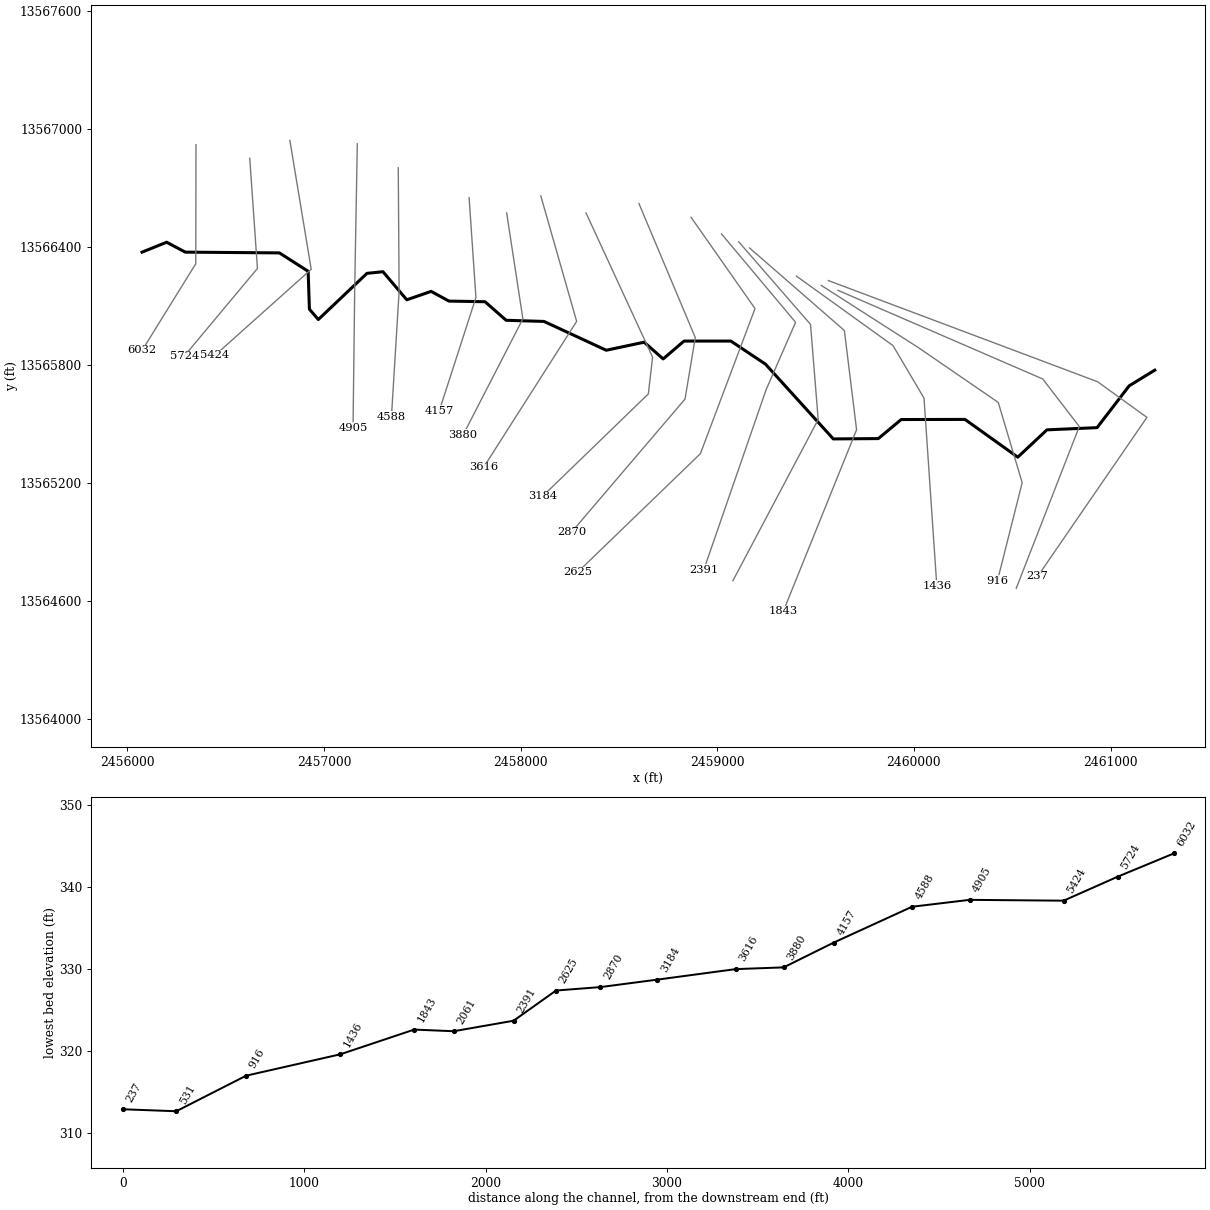
--- TRIB 2 TO COTTONWOOD CREEK.prj (project) ---

Proj Title=TRIB 2 TO COTTONWOOD CREEK Base Level Engineering
Current Plan=p01
Default Exp/Contr=0.3,0.1
English Units
Geom File=g01
Flow File=f01
Plan File=p01
BEGIN DESCRIPTION:
TRIB 2 TO COTTONWOOD CREEK
END DESCRIPTION:

--- TRIB 2 TO COTTONWOOD CREEK.p01 (plan) ---

Plan Title=Multiple Run
Short Identifier=Multiple
Geom File=g01
Flow File=f01
Subcritical Flow
K Sum by GR= 0
Std Step Tol= 0.01
Critical Tol= 0.01
Num of Std Step Trials= 20
Max Error Tol= 0.3
Flow Tol Ratio= 0.001
Split Flow NTrial= 30
Split Flow Tol= 0.02
Split Flow Ratio= 0.02
Log Output Level= 0
Friction Slope Method= 1
Unsteady Friction Slope Method= 2
Unsteady Bridges Friction Slope Method= 1
Parabolic Critical Depth
Global Vel Dist=  1 , 1 , 1
Global Log Level= 0
CheckData=True
Encroach Param= -1, 0, 0, 0
BEGIN DESCRIPTION:
Multiple Run
END DESCRIPTION:

--- TRIB 2 TO COTTONWOOD CREEK.f01 (steady flow) ---

Flow Title=Multiple
Number of Profiles=7
Profile Names=10-year,25-year,50-year,1pct_min,100-year,1pct_plu,500-year
River Rch & RM= TRIB 2 TO COTTON,Reach-1,6032
     596     961    1290     839    1675    3342    2795
River Rch & RM= TRIB 2 TO COTTON,Reach-1,2061
     723    1179    1594    1044    2083    4156    3523
Boundary for River Rch & Prof#=TRIB 2 TO COTTON,Reach-1,1
Up Type=0
Dn Type=3
Dn Slope=0.005
Boundary for River Rch & Prof#=TRIB 2 TO COTTON,Reach-1,2
Up Type=0
Dn Type=3
Dn Slope=0.005
Boundary for River Rch & Prof#=TRIB 2 TO COTTON,Reach-1,3
Up Type=0
Dn Type=3
Dn Slope=0.005
Boundary for River Rch & Prof#=TRIB 2 TO COTTON,Reach-1,4
Up Type=0
Dn Type=3
Dn Slope=0.005
Boundary for River Rch & Prof#=TRIB 2 TO COTTON,Reach-1,5
Up Type=0
Dn Type=3
Dn Slope=0.005
Boundary for River Rch & Prof#=TRIB 2 TO COTTON,Reach-1,6
Up Type=0
Dn Type=3
Dn Slope=0.005
Boundary for River Rch & Prof#=TRIB 2 TO COTTON,Reach-1,7
Up Type=0
Dn Type=3
Dn Slope=0.005

--- TRIB 2 TO COTTONWOOD CREEK.g01 (geometry) ---

Geom Title=Existing Conditions

River Reach=TRIB 2 TO COTTON,Reach-1
Reach XY= 30
      2456075.00     13566375.00      2456200.00     13566425.47
      2456295.03     13566375.08      2456773.45     13566371.25
      2456919.64     13566277.70      2456926.05     13566085.09
      2456971.38     13566032.47      2457218.83     13566267.24
      2457300.12     13566275.54      2457421.33     13566132.70
      2457545.04     13566175.58      2457635.50     13566126.22
      2457819.14     13566122.93      2457926.47     13566028.55
      2458119.06     13566022.74      2458435.50     13565876.19
      2458628.42     13565917.18      2458725.00     13565832.11
      2458830.85     13565922.92      2459069.14     13565922.94
      2459245.47     13565805.37      2459590.16     13565425.38
      2459819.14     13565427.07      2459935.44     13565523.94
      2460259.79     13565524.49      2460528.33     13565332.59
      2460676.46     13565471.46      2460931.48     13565482.69
      2461094.83     13565695.39      2461225.00     13565775.00

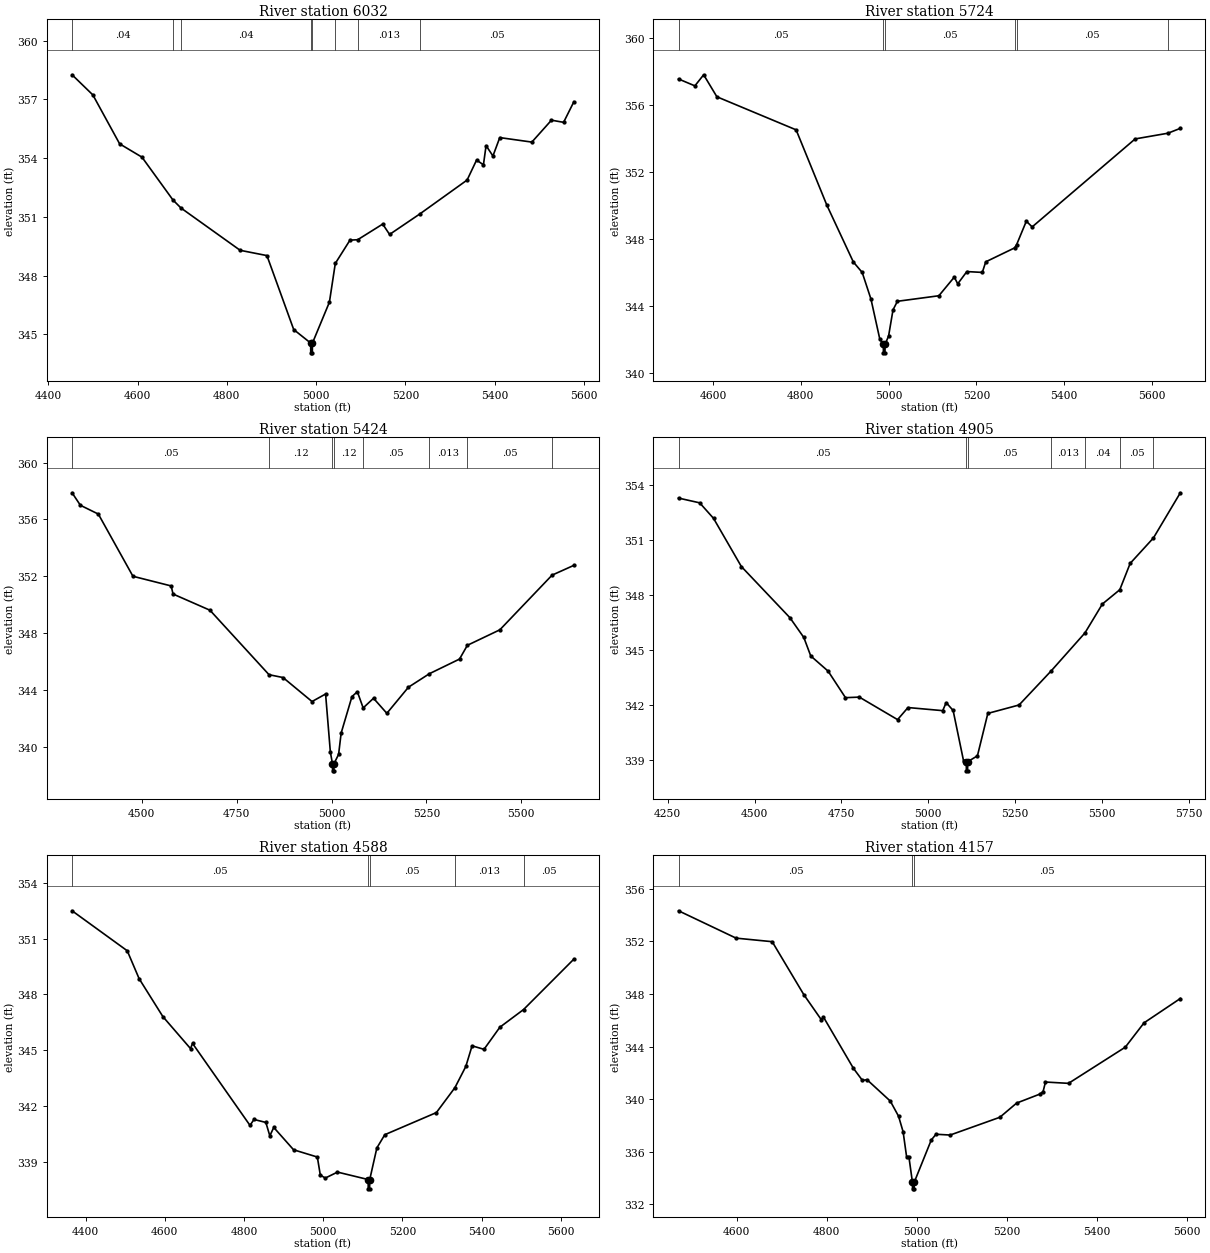
Type RM Length L Ch R = 1,6032,308,308,308
BEGIN DESCRIPTION:
TRIB 2 TO COTTONWOOD CREEK 8.0
END DESCRIPTION:
XS GIS Cut Line= 3
      2456349.26     13566921.58      2456348.21     13566316.16
      2456075.02     13565875.03
#Sta/Elev= 30
  4453.2  358.26  4499.8  357.23  4559.8  354.73  4609.8  354.05  4679.3  351.86
  4697.3  351.45  4829.8  349.29  4889.8  349.02  4949.8  345.24  4987.8  344.55
  4988.0  344.05  4991.5  344.05  4991.8  344.55  5029.8  346.64  5043.0  348.62
  5075.9  349.81  5093.1  349.83  5149.2  350.63  5164.6  350.10  5231.9  351.14
  5338.3  352.88  5359.5  353.90  5374.9  353.66  5380.8  354.64  5396.2  354.11
  5411.5  355.05  5483.4  354.82  5527.3  355.94  5554.5  355.83  5577.5  356.88
#Mann=8,-1,0
  4453.2    0.04       0  4679.3   0.013       0  4697.3    0.04       0
  4987.8    0.04       0  4991.8    0.04       0  5043.0    0.05       0
  5093.1   0.013       0  5231.9    0.05       0
Bank Sta=4987.8,4991.8
Exp/Cntr=0.3,0.1

Type RM Length L Ch R = 1,5724,300,300,300
BEGIN DESCRIPTION:
Mapping XS 8a331210
END DESCRIPTION:
XS GIS Cut Line= 3
      2456622.70     13566852.07      2456661.76     13566292.21
      2456289.28     13565846.09
#Sta/Elev= 30
  4521.8  357.54  4559.0  357.13  4579.0  357.79  4609.1  356.48  4789.5  354.51
  4859.7  350.01  4919.8  346.64  4939.9  346.02  4959.9  344.43  4980.0  342.05
  4988.0  341.73  4988.3  341.23  4991.8  341.23  4992.0  341.73  5000.0  342.23
  5010.1  343.79  5020.1  344.30  5114.5  344.63  5149.6  345.74  5157.4  345.34
  5178.2  346.07  5213.4  346.02  5221.2  346.65  5286.9  347.48  5291.6  347.68
  5313.6  349.07  5326.9  348.73  5561.4  353.97  5636.0  354.31  5664.2  354.60
#Mann=6,-1,0
  4521.8    0.05       0  4988.0    0.05       0  4992.0    0.05       0
  5286.9   0.013       0  5291.6    0.05       0  5636.0    0.04       0
Bank Sta=4988,4992
Exp/Cntr=0.3,0.1

Type RM Length L Ch R = 1,5424,519,519,519
BEGIN DESCRIPTION:
Mapping XS 08a7a2c9
END DESCRIPTION:
XS GIS Cut Line= 3
      2456826.68     13566943.28      2456935.20     13566287.87
      2456445.00     13565849.72
#Sta/Elev= 30
  4316.5  357.87  4338.4  356.99  4385.7  356.37  4476.9  351.99  4577.5  351.31
  4582.5  350.74  4679.7  349.60  4835.3  345.06  4872.2  344.86  4948.6  343.17
  4984.3  343.70  4996.9  339.61  5002.4  338.79  5002.7  338.29  5006.2  338.29
  5006.4  338.79  5018.6  339.45  5025.3  340.95  5053.8  343.52  5068.0  343.86
  5083.3  342.72  5110.6  343.40  5145.7  342.34  5202.6  344.18  5257.8  345.13
  5337.1  346.16  5357.8  347.13  5443.3  348.22  5580.9  352.07  5638.3  352.76
#Mann=8,-1,0
  4316.5    0.05       0  4835.3    0.12       0  5002.4    0.05       0
  5006.4    0.12       0  5083.3    0.05       0  5257.8   0.013       0
  5357.8    0.05       0  5580.9    0.04       0
Bank Sta=5002.4,5006.4
Exp/Cntr=0.3,0.1

Type RM Length L Ch R = 1,4905,317,317,317
BEGIN DESCRIPTION:
Mapping XS d332e433
END DESCRIPTION:
XS GIS Cut Line= 3
      2457169.57     13566925.86      2457156.55     13566196.72
      2457147.87     13565480.53
#Sta/Elev= 30
  4280.9  353.30  4341.8  353.04  4381.8  352.19  4461.8  349.56  4601.8  346.76
  4641.8  345.68  4661.8  344.67  4711.8  343.84  4761.8  342.39  4801.8  342.42
  4911.9  341.19  4941.9  341.85  5041.9  341.68  5051.9  342.12  5071.9  341.69
  5101.9  338.94  5109.9  338.89  5110.1  338.39  5113.6  338.39  5113.9  338.89
  5141.9  339.21  5171.9  341.53  5261.9  341.99  5355.2  343.87  5451.7  345.93
  5501.9  347.51  5552.0  348.29  5581.9  349.73  5648.9  351.12  5726.4  353.59
#Mann=7,-1,0
  4280.9    0.05       0  5109.9    0.05       0  5113.9    0.05       0
  5355.2   0.013       0  5451.7    0.04       0  5552.0    0.05       0
  5648.9    0.04       0
Bank Sta=5109.9,5113.9
Exp/Cntr=0.3,0.1

Type RM Length L Ch R = 1,4588,431,431,431
BEGIN DESCRIPTION:
Mapping XS 3df1cb00
END DESCRIPTION:
XS GIS Cut Line= 3
      2457377.90     13566804.32      2457382.24     13566175.02
      2457343.28     13565538.53
#Sta/Elev= 30
  4366.0  352.50  4505.3  350.35  4535.3  348.85  4595.3  346.81  4665.1  345.09
  4670.1  345.37  4815.3  340.96  4825.3  341.28  4855.3  341.12  4865.3  340.40
  4875.3  340.85  4925.3  339.65  4985.3  339.26  4992.8  338.29  5005.4  338.13
  5036.2  338.45  5113.6  338.05  5113.8  337.55  5117.3  337.55  5117.6  338.05
  5135.6  339.75  5155.6  340.46  5285.9  341.65  5332.7  342.99  5360.2  344.13
  5376.0  345.24  5406.1  345.05  5446.2  346.24  5506.0  347.19  5633.0  349.90
#Mann=5,-1,0
  4366.0    0.05       0  5113.6    0.05       0  5117.6    0.05       0
  5332.7   0.013       0  5506.0    0.05       0
Bank Sta=5113.6,5117.6
Exp/Cntr=0.3,0.1

Type RM Length L Ch R = 1,4157,277,277,277
BEGIN DESCRIPTION:
Mapping XS b5ef187f
END DESCRIPTION:
XS GIS Cut Line= 3
      2457738.14     13566652.49      2457772.87     13566144.64
      2457586.67     13565568.73
#Sta/Elev= 30
  4470.7  354.33  4598.5  352.25  4678.7  351.98  4748.8  347.96  4787.5  346.06
  4792.5  346.25  4859.1  342.35  4879.1  341.43  4889.2  341.49  4941.0  339.86
  4959.3  338.71  4969.4  337.53  4977.1  335.64  4982.2  335.64  4990.1  333.69
  4990.3  333.19  4993.8  333.19  4994.1  333.69  5031.9  336.90  5042.4  337.34
  5073.9  337.28  5184.2  338.63  5221.5  339.71  5273.6  340.40  5280.3  340.59
  5285.5  341.31  5336.7  341.21  5462.8  343.96  5504.4  345.81  5585.0  347.66
#Mann=3,-1,0
  4470.7    0.05       0  4990.1    0.05       0  4994.1    0.05       0
Bank Sta=4990.1,4994.1
Exp/Cntr=0.3,0.1

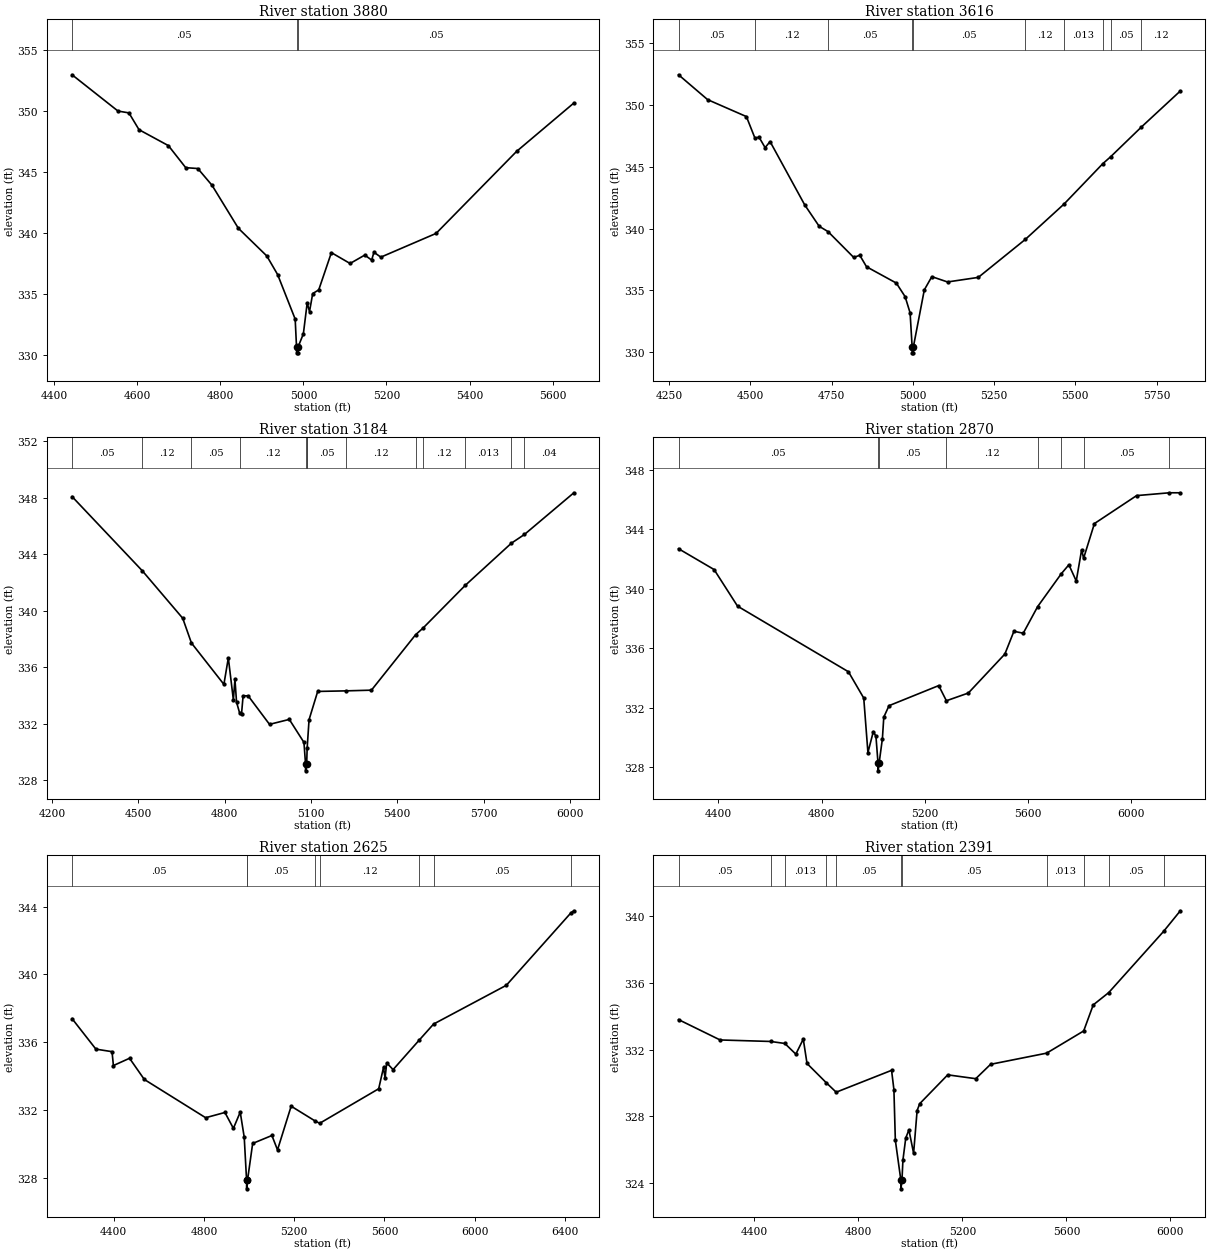
Type RM Length L Ch R = 1,3880,264,264,264
BEGIN DESCRIPTION:
Mapping XS b9f3e1c8
END DESCRIPTION:
XS GIS Cut Line= 3
      2457929.12     13566574.34      2458011.58     13566036.13
      2457707.75     13565445.82
#Sta/Elev= 30
  4442.8  353.00  4553.4  350.02  4579.7  349.87  4604.0  348.49  4674.8  347.18
  4716.5  345.37  4745.6  345.30  4779.9  343.92  4843.3  340.39  4911.7  338.12
  4937.8  336.59  4980.1  332.93  4983.3  330.66  4983.6  330.16  4987.1  330.16
  4987.3  330.66  4999.8  331.72  5009.0  334.26  5014.6  333.55  5022.3  335.03
  5036.8  335.33  5067.3  338.39  5112.3  337.50  5147.7  338.19  5164.2  337.78
  5169.8  338.42  5186.4  338.02  5319.4  339.97  5513.4  346.71  5651.2  350.68
#Mann=3,-1,0
  4442.8    0.05       0  4983.3    0.05       0  4987.3    0.05       0
Bank Sta=4983.3,4987.3
Exp/Cntr=0.3,0.1

Type RM Length L Ch R = 1,3616,432,432,432
BEGIN DESCRIPTION:
Mapping XS fe77ca72
END DESCRIPTION:
XS GIS Cut Line= 3
      2458102.74     13566661.10      2458285.02     13566023.11
      2457811.91     13565280.89
#Sta/Elev= 30
  4279.2  352.43  4368.7  350.42  4488.0  349.05  4514.1  347.32  4527.0  347.38
  4545.5  346.54  4560.8  347.03  4667.4  341.91  4711.9  340.18  4739.2  339.75
  4818.2  337.66  4836.7  337.84  4857.5  336.91  4949.2  335.59  4976.3  334.49
  4991.6  333.18  4997.8  330.45  4998.0  329.95  5001.5  329.95  5001.8  330.45
  5035.3  335.04  5058.4  336.11  5106.7  335.68  5201.4  336.05  5346.0  339.12
  5465.2  341.98  5584.3  345.24  5608.4  345.80  5703.3  348.21  5822.9  351.12
#Mann=10,-1,0
  4279.2    0.05       0  4514.1    0.12       0  4739.2    0.05       0
  4997.8    0.05       0  5001.8    0.05       0  5346.0    0.12       0
  5465.2   0.013       0  5584.3    0.12       0  5608.4    0.05       0
  5703.3    0.12       0
Bank Sta=4997.8,5001.8
Exp/Cntr=0.3,0.1

Type RM Length L Ch R = 1,3184,314,314,314
BEGIN DESCRIPTION:
Mapping XS a75032c2
END DESCRIPTION:
XS GIS Cut Line= 4
      2458332.77     13566574.31      2458671.31     13565840.82
      2458649.61     13565654.18      2458111.40     13565133.34
#Sta/Elev= 30
  4269.4  348.08  4514.0  342.82  4654.1  339.47  4684.4  337.72  4797.3  334.79
  4812.7  336.66  4830.2  333.70  4835.7  335.14  4841.3  333.53  4851.9  332.77
  4858.6  332.70  4864.1  333.98  4881.6  333.98  4955.9  331.96  5024.7  332.31
  5075.7  330.68  5081.1  329.17  5081.3  328.67  5085.1  329.17  5086.8  330.28
  5093.4  332.29  5123.4  334.29  5221.5  334.33  5310.3  334.38  5463.7  338.30
  5490.0  338.78  5636.1  341.79  5796.8  344.78  5842.3  345.40  6014.1  348.35
#Mann=13,-1,0
  4269.4    0.05       0  4514.0    0.12       0  4684.4    0.05       0
  4851.9    0.12       0  5081.1    0.05       0  5085.1    0.12       0
  5086.8    0.05       0  5221.5    0.12       0  5463.7    0.05       0
  5490.0    0.12       0  5636.1   0.013       0  5796.8    0.05       0
  5842.3    0.04       0
Bank Sta=5081.1,5085.1
Exp/Cntr=0.3,0.1

Type RM Length L Ch R = 1,2870,245,245,245
BEGIN DESCRIPTION:
Mapping XS 5ba2da87
END DESCRIPTION:
XS GIS Cut Line= 4
      2458601.86     13566622.06      2458888.32     13565940.64
      2458836.24     13565628.14      2458259.47     13564951.63
#Sta/Elev= 30
  4245.3  342.69  4383.1  341.29  4474.0  338.83  4903.8  334.42  4963.2  332.65
  4979.4  328.99  5000.3  330.40  5010.5  330.08  5018.6  328.26  5018.9  327.76
  5022.6  328.26  5035.5  329.92  5040.9  331.37  5061.2  332.14  5253.8  333.49
  5283.5  332.47  5368.6  332.99  5510.2  335.61  5545.3  337.14  5581.4  337.01
  5637.3  338.80  5729.0  341.01  5758.3  341.61  5786.9  340.52  5807.7  342.62
  5815.4  342.05  5857.3  344.38  6020.8  346.26  6148.0  346.45  6190.3  346.45
#Mann=8,-1,0
  4245.3    0.05       0  5018.6    0.05       0  5022.6    0.05       0
  5283.5    0.12       0  5637.3    0.05       0  5729.0   0.013       0
  5815.4    0.05       0  6148.0    0.04       0
Bank Sta=5018.6,5022.6
Exp/Cntr=0.3,0.1

Type RM Length L Ch R = 1,2625,234,234,234
BEGIN DESCRIPTION:
Mapping XS 3f4bac02
END DESCRIPTION:
XS GIS Cut Line= 4
      2458866.63     13566552.60      2459192.14     13566088.21
      2458914.36     13565350.37      2458289.71     13564747.40
#Sta/Elev= 30
  4215.5  337.39  4321.1  335.59  4392.6  335.44  4398.7  334.62  4470.2  335.05
  4535.6  333.80  4807.4  331.54  4892.9  331.85  4930.4  330.91  4960.7  331.87
  4978.4  330.39  4988.9  327.84  4989.1  327.34  4992.9  327.84  5015.8  330.02
  5101.1  330.49  5125.9  329.64  5186.4  332.22  5292.2  331.35  5312.8  331.21
  5574.3  333.25  5595.7  334.51  5602.6  333.88  5609.8  334.78  5638.1  334.38
  5754.4  336.13  5817.5  337.07  6140.0  339.36  6427.1  343.65  6439.2  343.76
#Mann=8,-1,0
  4215.5    0.05       0  4988.9    0.05       0  4992.9    0.05       0
  5292.2   0.013       0  5312.8    0.12       0  5754.4   0.013       0
  5817.5    0.05       0  6427.1    0.04       0
Bank Sta=4988.9,4992.9
Exp/Cntr=0.3,0.1

Type RM Length L Ch R = 1,2391,330,330,330
BEGIN DESCRIPTION:
Mapping XS d3bb88b8
END DESCRIPTION:
XS GIS Cut Line= 4
      2459021.88     13566467.44      2459398.39     13566018.34
      2459248.56     13565675.89      2458931.72     13564760.09
#Sta/Elev= 30
  4108.9  333.80  4268.7  332.58  4462.9  332.49  4517.5  332.37  4559.8  331.73
  4588.4  332.63  4602.8  331.17  4676.0  330.03  4714.9  329.45  4927.8  330.76
  4936.8  329.61  4942.3  326.57  4963.7  324.16  4963.9  323.66  4967.7  324.16
  4971.5  325.39  4982.4  326.71  4994.5  327.19  5012.5  325.79  5026.0  328.35
  5035.9  328.76  5143.7  330.49  5251.4  330.26  5308.4  331.12  5523.9  331.79
  5666.3  333.12  5703.0  334.68  5762.7  335.42  5973.2  339.08  6037.8  340.32
#Mann=11,-1,0
  4108.9    0.05       0  4462.9    0.04       0  4517.5   0.013       0
  4676.0    0.04       0  4714.9    0.05       0  4963.7    0.05       0
  4967.7    0.05       0  5523.9   0.013       0  5666.3    0.12       0
  5762.7    0.05       0  5973.2   0.013       0
Bank Sta=4963.7,4967.7
Exp/Cntr=0.3,0.1

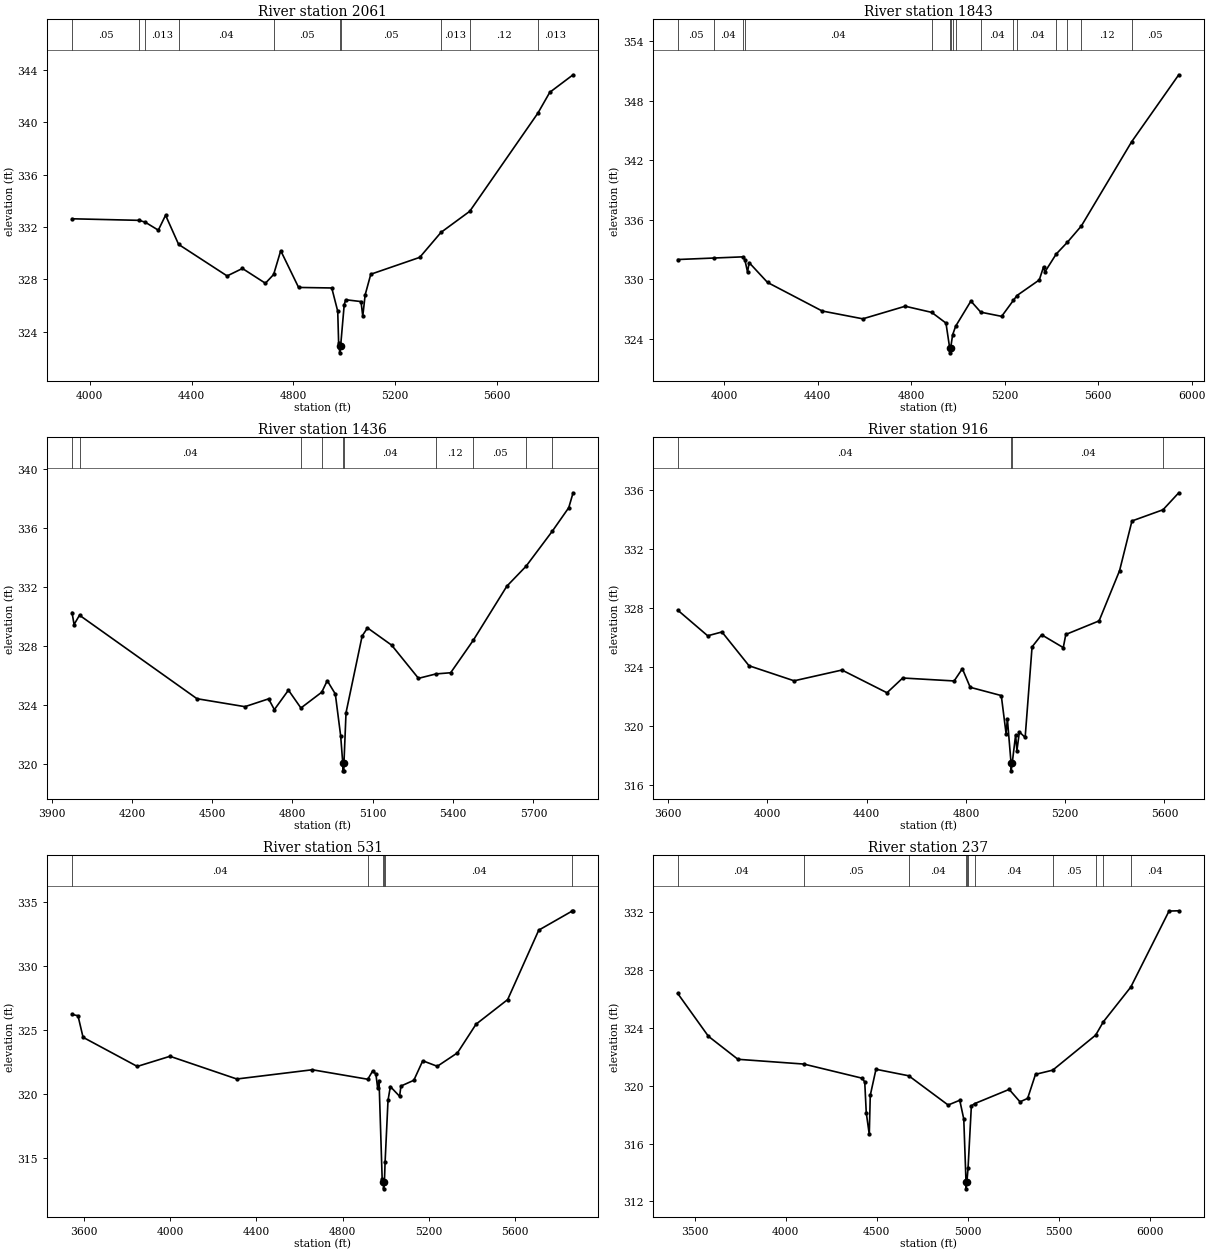
Type RM Length L Ch R = 1,2061,218,218,218
BEGIN DESCRIPTION:
Mapping XS 9801be9a
END DESCRIPTION:
XS GIS Cut Line= 4
      2459109.10     13566427.78      2459474.31     13566007.72
      2459513.32     13565523.98      2459079.66     13564704.36
#Sta/Elev= 30
  3930.4  332.63  4194.3  332.51  4217.9  332.37  4269.5  331.76  4298.0  332.90
  4349.3  330.67  4539.9  328.26  4600.1  328.83  4690.4  327.70  4722.7  328.37
  4750.6  330.19  4820.8  327.38  4951.2  327.34  4974.6  325.56  4978.1  323.17
  4981.7  322.88  4981.9  322.38  4985.9  322.88  5000.1  326.06  5005.8  326.44
  5066.2  326.30  5073.0  325.18  5082.5  326.82  5104.5  328.39  5296.9  329.68
  5380.5  331.59  5493.3  333.20  5761.3  340.71  5808.0  342.30  5899.6  343.64
#Mann=10,-1,0
  3930.4    0.05       0  4194.3    0.04       0  4217.9   0.013       0
  4349.3    0.04       0  4722.7    0.05       0  4981.7    0.05       0
  4985.9    0.05       0  5380.5   0.013       0  5493.3    0.12       0
  5761.3   0.013       0
Bank Sta=4981.7,4985.9
Exp/Cntr=0.3,0.1

Type RM Length L Ch R = 1,1843,407,407,407
BEGIN DESCRIPTION:
Mapping XS 6c5226c8
END DESCRIPTION:
XS GIS Cut Line= 4
      2459164.57     13566396.09      2459646.44     13565976.74
      2459708.63     13565471.89      2459335.91     13564548.75
#Sta/Elev= 30
  3801.9  331.99  3955.4  332.14  4080.8  332.26  4089.1  331.97  4100.7  330.72
  4107.4  331.68  4186.1  329.68  4419.7  326.80  4593.6  326.01  4774.9  327.28
  4888.3  326.66  4949.3  325.58  4965.1  323.08  4965.4  322.58  4969.4  323.08
  4977.8  324.40  4990.6  325.26  5055.9  327.80  5098.1  326.68  5187.4  326.26
  5237.6  327.87  5253.0  328.36  5348.4  329.93  5366.6  331.25  5372.5  330.74
  5420.7  332.54  5468.5  333.73  5528.2  335.37  5743.3  343.86  5944.9  350.62
#Mann=16,-1,0
  3801.9    0.05       0  3955.4    0.04       0  4080.8   0.013       0
  4089.1    0.04       0  4888.3    0.05       0  4965.1    0.05       0
  4969.4    0.05       0  4977.8    0.04       0  4990.6    0.05       0
  5098.1    0.04       0  5237.6    0.12       0  5253.0    0.04       0
  5420.7   0.013       0  5468.5    0.05       0  5528.2    0.12       0
  5743.3    0.05       0
Bank Sta=4965.1,4969.4
Exp/Cntr=0.3,0.1

Type RM Length L Ch R = 1,1436,520,520,520
BEGIN DESCRIPTION:
Mapping XS 802f11da
END DESCRIPTION:
XS GIS Cut Line= 4
      2459402.37     13566253.41      2459893.75     13565899.89
      2460051.51     13565632.48      2460116.54     13564678.81
#Sta/Elev= 30
  3976.5  330.30  3984.1  329.49  4004.4  330.12  4443.2  324.46  4622.3  323.92
  4710.8  324.45  4732.3  323.72  4784.9  325.04  4831.5  323.83  4909.2  324.90
  4929.9  325.68  4960.0  324.78  4980.0  321.94  4987.9  320.07  4988.2  319.57
  4991.9  319.57  4992.2  320.07  5000.0  323.51  5060.2  328.71  5080.2  329.26
  5170.4  328.09  5270.7  325.84  5335.9  326.14  5390.9  326.22  5475.3  328.42
  5600.8  332.09  5672.5  333.44  5771.1  335.83  5832.0  337.41  5848.2  338.42
#Mann=10,-1,0
  3976.5   0.013       0  4004.4    0.04       0  4831.5    0.05       0
  4909.2    0.04       0  4987.9    0.04       0  4992.2    0.04       0
  5335.9    0.12       0  5475.3    0.05       0  5672.5   0.013       0
  5771.1    0.05       0
Bank Sta=4987.9,4992.2
Exp/Cntr=0.3,0.1

Type RM Length L Ch R = 1,916,385,385,385
BEGIN DESCRIPTION:
Mapping XS 399fd629
END DESCRIPTION:
XS GIS Cut Line= 5
      2459529.17     13566205.87      2460023.45     13565889.18
      2460429.12     13565610.78      2460550.65     13565202.80
      2460424.78     13564703.67
#Sta/Elev= 30
  3638.4  327.85  3759.3  326.11  3816.8  326.37  3925.9  324.08  4107.6  323.06
  4300.4  323.79  4482.0  322.25  4545.4  323.25  4752.6  323.05  4785.7  323.88
  4817.4  322.62  4942.6  322.06  4962.0  319.48  4967.2  320.48  4982.1  317.46
  4982.4  316.96  4986.5  317.46  5000.4  319.39  5005.6  318.33  5015.6  319.60
  5038.8  319.22  5066.7  325.36  5105.1  326.18  5192.4  325.31  5202.7  326.20
  5336.8  327.12  5419.3  330.52  5469.3  333.89  5594.5  334.65  5657.9  335.80
#Mann=4,-1,0
  3638.4    0.04       0  4982.1    0.04       0  4986.5    0.04       0
  5594.5   0.013       0
Bank Sta=4982.1,4986.5
Exp/Cntr=0.3,0.1

Type RM Length L Ch R = 1,531,294,294,294
BEGIN DESCRIPTION:
Mapping XS 36c71b47
END DESCRIPTION:
XS GIS Cut Line= 4
      2459614.30     13566180.85      2460655.29     13565730.06
      2460841.18     13565488.40      2460520.53     13564665.88
#Sta/Elev= 30
  3546.2  326.22  3573.8  326.12  3597.3  324.44  3848.5  322.17  4000.2  322.96
  4309.8  321.19  4659.8  321.91  4916.8  321.17  4940.0  321.83  4954.5  321.57
  4962.7  320.46  4969.0  321.07  4983.5  313.38  4989.4  313.13  4989.7  312.63
  4993.8  313.13  4997.0  314.70  5010.6  319.53  5021.5  320.60  5064.3  319.84
  5070.5  320.64  5130.2  321.09  5171.6  322.61  5238.9  322.18  5332.6  323.23
  5418.5  325.46  5565.1  327.38  5709.1  332.79  5865.1  334.29  5868.3  334.30
#Mann=6,-1,0
  3546.2    0.04       0  4916.8    0.05       0  4989.4    0.04       0
  4993.8    0.05       0  4997.0    0.04       0  5865.1   0.013       0
Bank Sta=4989.4,4993.8
Exp/Cntr=0.3,0.1

Type RM Length L Ch R = 1,237,0,0,0
BEGIN DESCRIPTION:
Mapping XS 599cf271
END DESCRIPTION:
XS GIS Cut Line= 4
      2459565.15     13566230.50      2460934.12     13565716.12
      2461185.08     13565534.88      2460629.40     13564726.28
#Sta/Elev= 30
  3407.4  326.37  3576.1  323.41  3738.4  321.82  4100.5  321.49  4422.1  320.51
  4435.2  320.24  4443.5  318.13  4460.1  316.63  4465.5  319.33  4496.9  321.13
  4677.0  320.68  4893.4  318.66  4957.2  318.99  4979.3  317.69  4991.5  313.37
  4991.8  312.87  4996.5  313.37  5002.7  314.28  5021.0  318.60  5039.5  318.76
  5228.7  319.74  5288.3  318.88  5330.2  319.12  5373.4  320.78  5468.1  321.07
  5704.0  323.49  5746.2  324.41  5897.0  326.81  6107.0  332.06  6160.5  332.08
#Mann=11,-1,0
  3407.4    0.04       0  4100.5    0.05       0  4677.0    0.04       0
  4991.5    0.04       0  4996.5    0.04       0  5002.7    0.05       0
  5039.5    0.04       0  5468.1    0.05       0  5704.0    0.04       0
  5746.2    0.05       0  5897.0    0.04       0
Bank Sta=4991.5,4996.5
Exp/Cntr=0.3,0.1

Chan Stop Cuts=-1