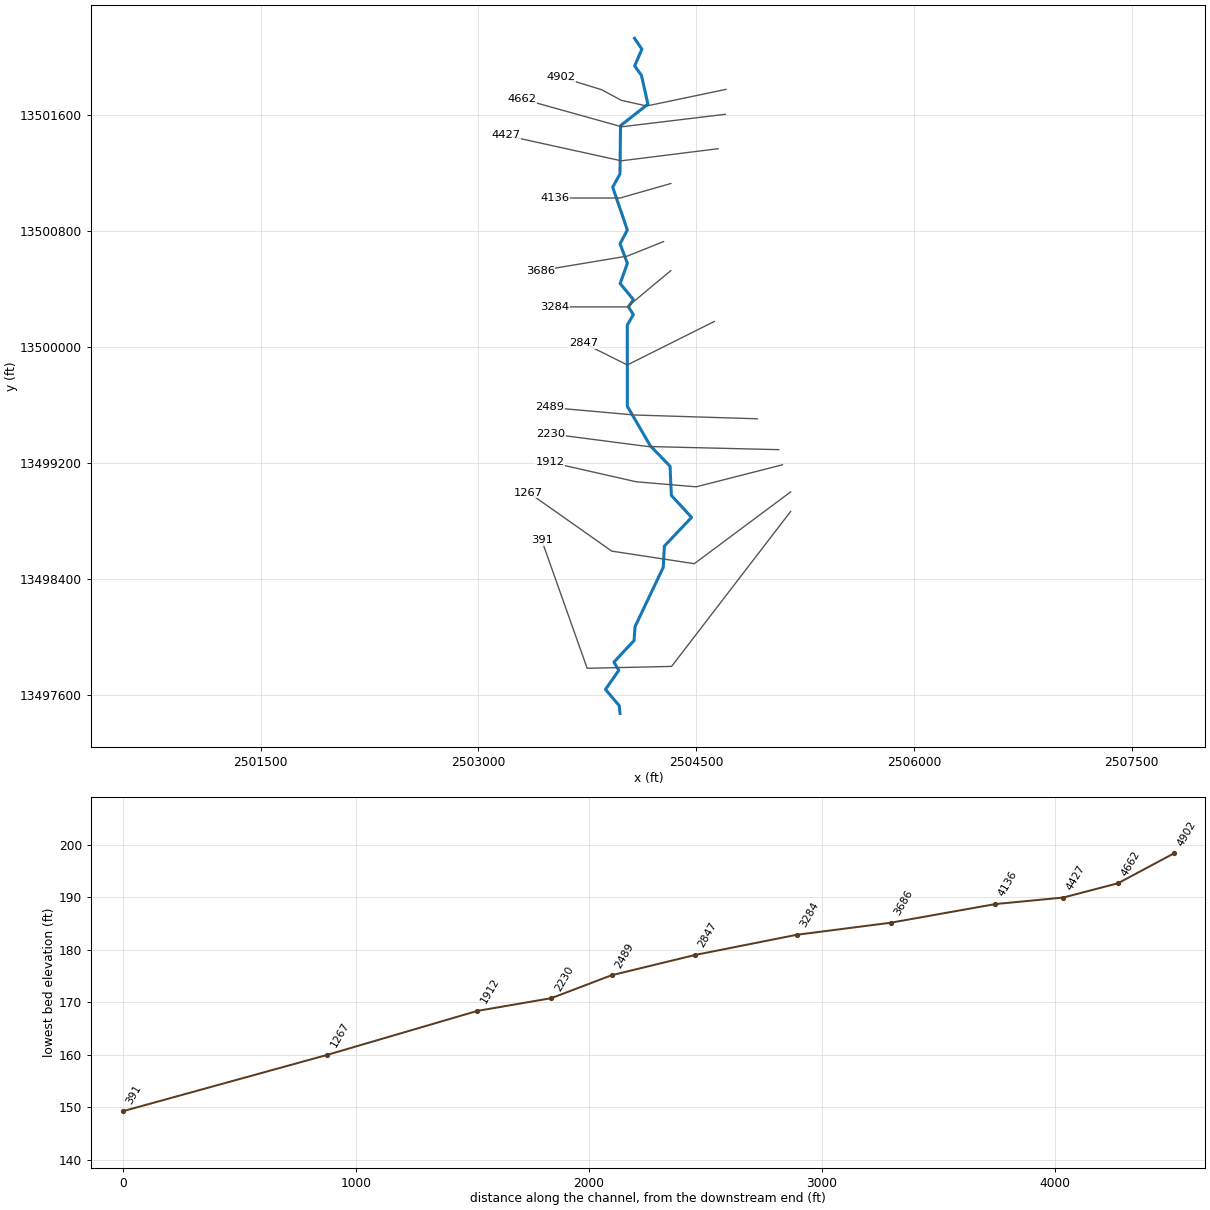
--- TRIB 2 TO EIGHTEENMILE CREEK.prj (project) ---

Proj Title=TRIB 2 TO EIGHTEENMILE CREEK Base Level Engineering
Current Plan=p01
Default Exp/Contr=0.3,0.1
English Units
Geom File=g01
Flow File=f01
Plan File=p01
Y Axis Title=Elevation
X Axis Title(PF)=Main Channel Distance
X Axis Title(XS)=Station
BEGIN DESCRIPTION:
TRIB 2 TO EIGHTEENMILE CREEK
END DESCRIPTION:
DSS Export Rating Curves= 0
DSS Export Rating Curve Sorted= 0
DSS Export Volume Flow Curves= 0
DXF OffsetX= 0
DXF OffsetY= 0
DXF ScaleX= 1
DXF ScaleY= 10

--- TRIB 2 TO EIGHTEENMILE CREEK.p01 (plan) ---

Plan Title=Multiple Run
Short Identifier=Multiple
Geom File=g01
Flow File=f01
Subcritical Flow
K Sum by GR= 0
Std Step Tol= 0.01
Critical Tol= 0.01
Num of Std Step Trials= 20
Max Error Tol= 0.3
Flow Tol Ratio= 0.001
Split Flow NTrial= 30
Split Flow Tol= 0.02
Split Flow Ratio= 0.02
Log Output Level= 0
Friction Slope Method= 1
Unsteady Friction Slope Method= 2
Unsteady Bridges Friction Slope Method= 1
Parabolic Critical Depth
Global Vel Dist=  1 , 1 , 1
Global Log Level= 0
CheckData=True
Encroach Param= -1, 0, 0, 0
BEGIN DESCRIPTION:
Multiple Run
END DESCRIPTION:

--- TRIB 2 TO EIGHTEENMILE CREEK.f01 (steady flow) ---

Flow Title=Multiple
Number of Profiles=7
Profile Names=10-year,25-year,50-year,1pct_min,100-year,1pct_plu,500-year
River Rch & RM= TRIB 2 TO EIGHTE,Reach-1,4902
     332     513     669     424     847    1689    1336
Boundary for River Rch & Prof#=TRIB 2 TO EIGHTE,Reach-1,1
Up Type=0
Dn Type=3
Dn Slope=0.005
Boundary for River Rch & Prof#=TRIB 2 TO EIGHTE,Reach-1,2
Up Type=0
Dn Type=3
Dn Slope=0.005
Boundary for River Rch & Prof#=TRIB 2 TO EIGHTE,Reach-1,3
Up Type=0
Dn Type=3
Dn Slope=0.005
Boundary for River Rch & Prof#=TRIB 2 TO EIGHTE,Reach-1,4
Up Type=0
Dn Type=3
Dn Slope=0.005
Boundary for River Rch & Prof#=TRIB 2 TO EIGHTE,Reach-1,5
Up Type=0
Dn Type=3
Dn Slope=0.005
Boundary for River Rch & Prof#=TRIB 2 TO EIGHTE,Reach-1,6
Up Type=0
Dn Type=3
Dn Slope=0.005
Boundary for River Rch & Prof#=TRIB 2 TO EIGHTE,Reach-1,7
Up Type=0
Dn Type=3
Dn Slope=0.005

--- TRIB 2 TO EIGHTEENMILE CREEK.g01 (geometry) ---

Geom Title=Existing Conditions
Program Version=4.10

River Reach=TRIB 2 TO EIGHTE,Reach-1
Reach XY= 30
        2504075.       13502125.       2504125.6     13502049.94
      2504075.77     13501935.69       2504122.7     13501869.07
      2504167.21     13501671.57      2503978.45     13501523.75
      2503974.46     13501190.21       2503924.6       13501100.
      2504025.28     13500804.82      2503975.11     13500709.61
      2504025.81       13500575.      2503975.61     13500435.62
      2504067.45       13500325.      2504033.04       13500275.
      2504066.73     13500221.79      2504024.89     13500150.12
      2504025.51     13499590.21      2504183.16     13499318.95
      2504319.54     13499177.45      2504328.54     13498976.46
      2504467.93       13498825.      2504280.47     13498627.45
      2504272.75     13498480.93      2504078.83     13498073.41
      2504071.39      13497976.5        2503933.     13497828.33
      2503966.98     13497771.67      2503874.89     13497640.36
      2503969.67     13497527.51        2503975.       13497475.

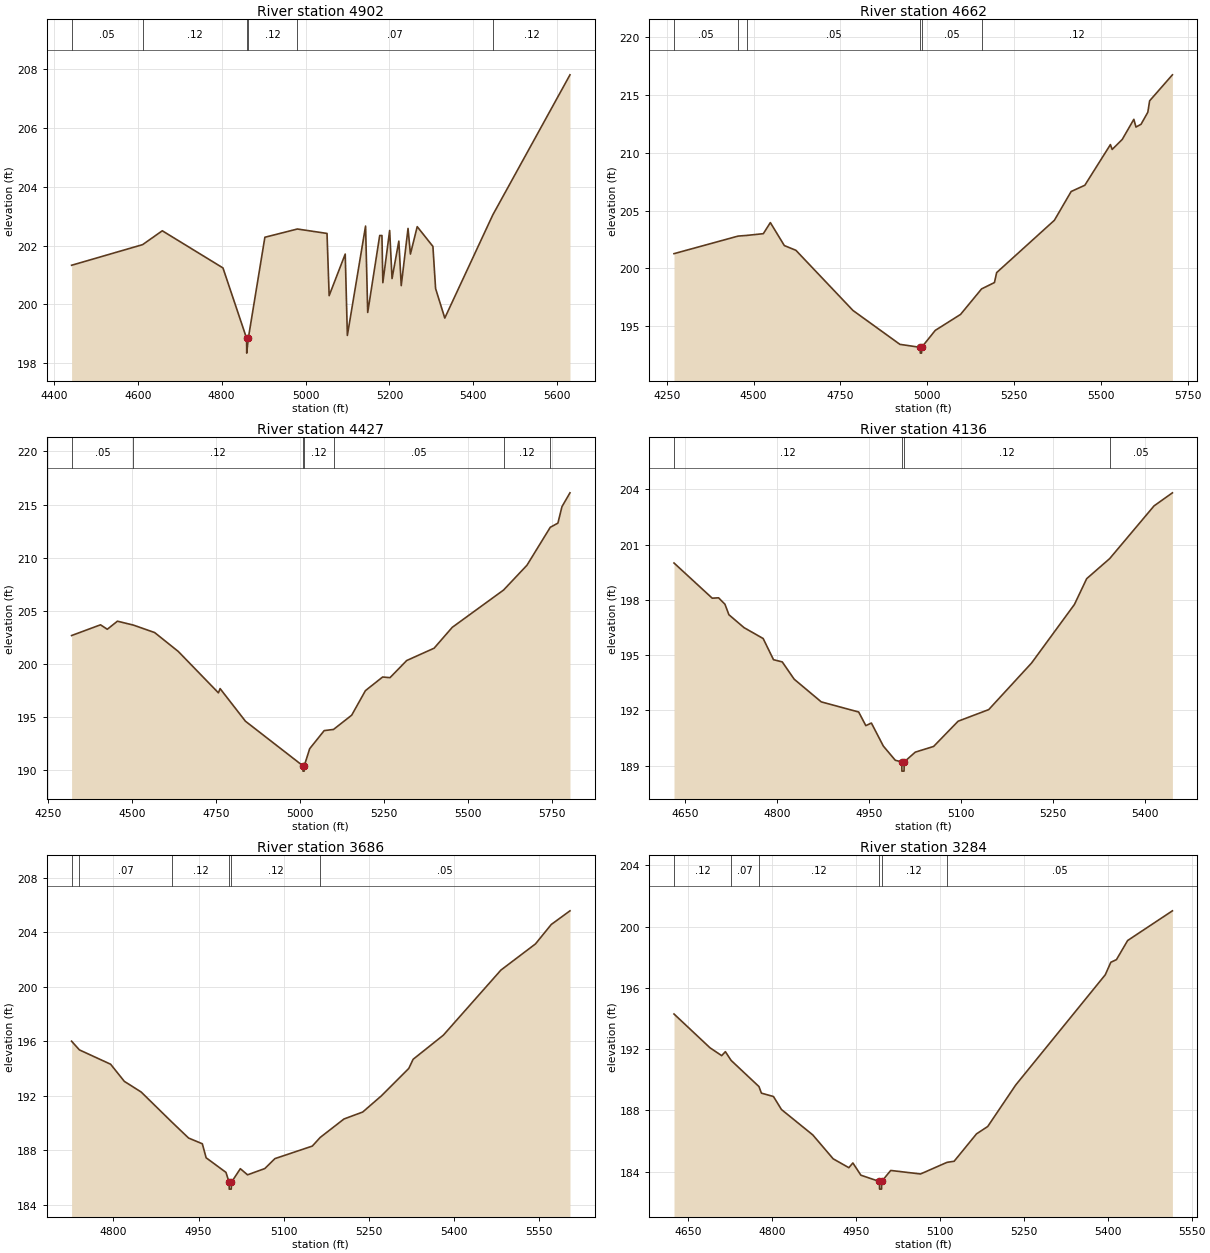
Type RM Length L Ch R = 1 ,4902    ,240,240,240
BEGIN DESCRIPTION:
Mapping XS a59ea316
END DESCRIPTION:
XS GIS Cut Line= 5
      2504705.26     13501773.56      2504158.35     13501658.97
      2503983.87     13501698.03      2503848.45     13501770.95
      2503565.11     13501858.34
#Sta/Elev= 30
  4442.4  201.33  4611.7  202.03  4658.6   202.5  4803.2  201.24  4859.6  198.85
  4859.8  198.35  4863.6  198.85  4903.1  202.28  4980.6  202.56  5051.2  202.41
  5056.3   200.3  5094.6  201.71  5099.7  198.95  5143.1  202.66  5148.2  199.73
  5176.8  202.34  5182.1  202.34  5184.3  200.74  5200.5  202.51  5206.2  200.88
  5222.4  202.15  5228.1  200.64  5244.3  202.58    5250  201.71  5266.2  202.64
  5303.6  201.97    5310  200.54  5331.9  199.54  5446.4  203.04  5630.3  207.79
#Mann= 6 ,-1 , 0
  4442.4     .05       0  4611.7     .12       0  4859.6     .05       0
  4863.6     .12       0  4980.6     .07       0  5446.4     .12       0
Bank Sta=4859.6,4863.6
XS Rating Curve= 0 ,0
Exp/Cntr=0.3,0.1

Type RM Length L Ch R = 1 ,4662    ,235,235,235
BEGIN DESCRIPTION:
TRIB 2 TO EIGHTEENMILE CREEK 8.0
END DESCRIPTION:
XS GIS Cut Line= 3
      2504700.06     13501601.68      2503986.47     13501515.74
      2503298.15     13501707.95
#Sta/Elev= 30
  4271.2  201.27  4455.4  202.79  4480.6  202.85  4528.1     203  4548.3  203.96
  4588.5  201.97  4621.8  201.56    4786  196.35  4920.9  193.42  4979.4  193.16
  4979.6  192.66  4983.1  192.66  4983.4  193.16  5022.6  194.63  5095.3  196.01
  5155.8  198.22  5192.8  198.77  5199.1  199.63  5365.2  204.16  5413.4  206.65
  5452.7  207.19  5526.3  210.71  5531.4  210.29  5560.4  211.16  5593.7   212.9
  5599.8  212.23  5614.4  212.47  5633.9  213.51  5639.1   214.5  5704.6  216.75
#Mann= 6 ,-1 , 0
  4271.2     .05       0  4455.4     .12       0  4480.6     .05       0
  4979.4     .05       0  4983.4     .05       0  5155.8     .12       0
Bank Sta=4979.4,4983.4
XS Rating Curve= 0 ,0
Exp/Cntr=0.3,0.1

Type RM Length L Ch R = 1 ,4427    ,291,291,291
BEGIN DESCRIPTION:
Mapping XS e465f411
END DESCRIPTION:
XS GIS Cut Line= 3
      2504650.57      13501364.7      2503983.87     13501281.36
      2503189.79      13501455.8
#Sta/Elev= 30
  4319.1  202.69  4405.3   203.7  4425.5  203.28  4455.7  204.04  4503.5  203.67
  4566.6  202.97  4637.1  201.19  4756.6   197.3  4761.6   197.7  4837.2  194.63
  5008.3  190.44  5008.6  189.94  5012.1  189.94  5012.3  190.44  5028.5  192.05
  5071.7  193.75  5099.5  193.86  5153.6   195.2  5194.6  197.51  5245.8  198.79
  5267.8  198.73  5317.5  200.34  5399.2   201.5  5453.2  203.46  5606.2  206.97
  5675.8   209.3  5745.3  212.87    5768  213.26  5780.1  214.81    5804  216.11
#Mann= 7 ,-1 , 0
  4319.1     .05       0  4503.5     .12       0  5008.3     .05       0
  5012.3     .12       0  5099.5     .05       0  5606.2     .12       0
  5745.3     .05       0
Bank Sta=5008.3,5012.3
XS Rating Curve= 0 ,0
Exp/Cntr=0.3,0.1

Type RM Length L Ch R = 1 ,4136    ,450,450,450
BEGIN DESCRIPTION:
TRIB 2 TO EIGHTEENMILE CREEK 7.0
END DESCRIPTION:
XS GIS Cut Line= 3
      2504324.99       13501125.        2503975.       13501025.
      2503524.99       13501025.
#Sta/Elev= 30
  4631.4     200  4693.8  198.09  4704.2  198.11  4714.6  197.76  4721.1  197.19
  4745.8  196.49    4777   195.9  4793.9  194.75  4808.2  194.63  4827.7  193.69
  4871.9  192.46    4933  191.91  4944.7  191.17  4953.8  191.31  4973.3  190.06
  4992.8  189.29  5003.4   189.2  5003.6   188.7  5007.1   188.7  5007.4   189.2
  5025.4  189.73  5055.4  190.04  5095.4  191.41  5145.4  192.04  5215.4  194.57
  5285.4  197.75  5305.4  199.15    5343  200.24  5415.4   203.1  5445.4  203.81
#Mann= 4 ,-1 , 0
  4631.4     .12       0  5003.4     .05       0  5007.4     .12       0
    5343     .05       0
Bank Sta=5003.4,5007.4
XS Rating Curve= 0 ,0
Exp/Cntr=0.3,0.1

Type RM Length L Ch R = 1 ,3686    ,402,402,402
BEGIN DESCRIPTION:
TRIB 2 TO EIGHTEENMILE CREEK 6.0
END DESCRIPTION:
XS GIS Cut Line= 3
        2504275.       13500725.        2504025.       13500625.
      2503425.03     13500525.01
#Sta/Elev= 30
  4726.5     196  4740.3  195.36  4795.2  194.31  4819.4  193.05    4849  192.27
  4903.6  190.04  4932.5  188.89  4956.7  188.47  4963.4  187.44  4998.3  186.37
  5003.9  185.64  5004.1  185.14  5007.6  185.14  5007.9  185.64  5023.6  186.64
  5036.3  186.19  5066.7  186.65  5084.5  187.38  5150.4   188.3  5164.1  188.93
  5206.1  190.29  5239.1   190.8    5272  191.99  5320.2     194  5327.8  194.67
    5381  196.44  5482.4  201.22  5543.2  203.14  5571.1  204.57    5604  205.57
#Mann= 6 ,-1 , 0
  4726.5     .12       0  4740.3     .07       0  4903.6     .12       0
  5003.9     .05       0  5007.9     .12       0  5164.1     .05       0
Bank Sta=5003.9,5007.9
XS Rating Curve= 0 ,0
Exp/Cntr=0.3,0.1

Type RM Length L Ch R = 1 ,3284    ,437,437,437
BEGIN DESCRIPTION:
TRIB 2 TO EIGHTEENMILE CREEK 5.0
END DESCRIPTION:
XS GIS Cut Line= 3
      2504324.99     13500524.99        2504025.       13500275.
        2503525.       13500275.
#Sta/Elev= 30
  4625.1  194.29  4689.5  192.08  4710.3  191.57  4716.9  191.83  4727.1  191.26
  4776.9  189.55  4781.3  189.12  4802.8   188.9  4817.1  188.05  4873.1  186.39
  4909.5  184.83  4937.5  184.25  4944.7  184.56    4959  183.76  4992.1  183.35
  4992.4  182.85  4995.9  182.85  4996.1  183.35  5012.3  184.07  5065.6  183.84
  5112.9   184.6  5125.6  184.67  5165.6  186.46  5185.6  186.94  5235.6  189.65
  5395.6  196.85  5405.6  197.67  5415.6  197.84  5435.6  199.09  5515.6  201.03
#Mann= 6 ,-1 , 0
  4625.1     .12       0  4727.1     .07       0  4776.9     .12       0
  4992.1     .05       0  4996.1     .12       0  5112.9     .05       0
Bank Sta=4992.1,4996.1
XS Rating Curve= 0 ,0
Exp/Cntr=0.3,0.1

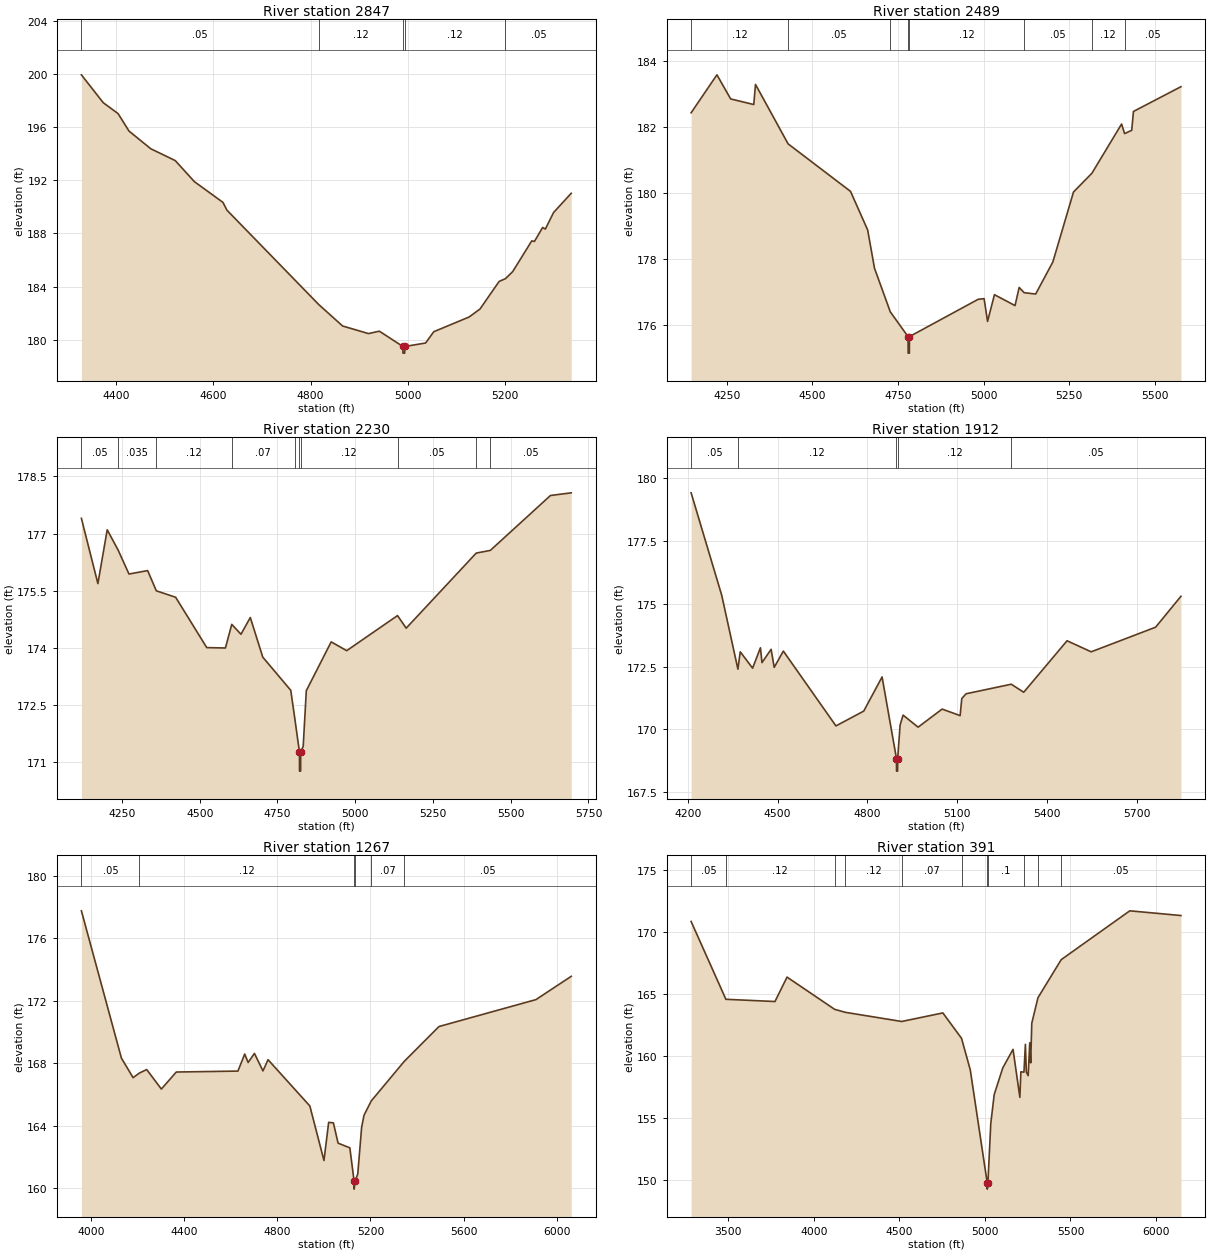
Type RM Length L Ch R = 1 ,2847    ,358,358,358
BEGIN DESCRIPTION:
TRIB 2 TO EIGHTEENMILE CREEK 4.0
END DESCRIPTION:
XS GIS Cut Line= 3
      2504624.97     13500174.98        2504025.       13499875.
      2503724.99       13500025.
#Sta/Elev= 30
  4329.2  199.93  4373.9  197.84  4404.6  197.01    4427   195.7  4471.7  194.37
    4522  193.48  4561.2   191.9  4619.9  190.34  4628.2  189.75  4816.6  182.66
  4865.8  181.04  4918.9  180.47  4941.3  180.65  4989.6   179.5  4989.8     179
  4993.3     179  4993.6   179.5  5036.3  179.76  5053.1  180.61  5125.8  181.72
  5148.1  182.32  5187.3  184.39  5200.3   184.6  5215.2  185.13  5254.3  187.44
  5259.9   187.4  5276.7  188.45  5282.3  188.33  5299.1  189.57  5335.4  191.02
#Mann= 5 ,-1 , 0
  4329.2     .05       0  4816.6     .12       0  4989.6     .05       0
  4993.6     .12       0  5200.3     .05       0
Bank Sta=4989.6,4993.6
XS Rating Curve= 0 ,0
Exp/Cntr=0.3,0.1

Type RM Length L Ch R = 1 ,2489    ,259,259,259
BEGIN DESCRIPTION:
Mapping XS f0d829fe
END DESCRIPTION:
XS GIS Cut Line= 3
       2504920.4     13499504.29      2504074.06     13499530.33
      2503492.43     13499582.42
#Sta/Elev= 30
  4145.6  182.42    4221  183.57  4261.1  182.84  4328.6  182.67  4333.6  183.28
  4428.8  181.48  4611.2  180.04  4661.3  178.87  4681.3  177.71  4727.4  176.39
  4779.3  175.64  4779.6  175.14  4783.1  175.14  4783.3  175.64    4984  176.77
  5001.4  176.79  5011.5   176.1  5031.6  176.91  5091.8  176.58  5103.8  177.13
  5118.5  176.97    5152  176.93  5202.2   177.9  5262.5  180.02  5316.4  180.59
    5403  182.08  5411.8  181.79  5432.6  181.89  5437.6  182.46  5576.3  183.21
#Mann= 8 ,-1 , 0
  4145.6     .12       0  4428.8     .05       0  4727.4     .12       0
  4779.3     .05       0  4783.3     .12       0  5118.5     .05       0
  5316.4     .12       0  5411.8     .05       0
Bank Sta=4779.3,4783.3
XS Rating Curve= 0 ,0
Exp/Cntr=0.3,0.1

Type RM Length L Ch R = 1 ,2230    ,318,318,318
BEGIN DESCRIPTION:
Mapping XS e7f57fb5
END DESCRIPTION:
XS GIS Cut Line= 3
      2505067.98     13499291.62      2504165.21     13499313.32
      2503498.84     13499399.86
#Sta/Elev= 30
  4119.6   177.4  4172.6  175.69  4202.6   177.1  4237.6  176.57  4272.6  175.94
  4332.6  176.03  4360.5   175.5  4422.7  175.33  4522.7  174.01  4582.7     174
  4603.1  174.62  4632.7  174.36  4662.7   174.8  4702.8  173.76  4792.8  172.89
  4805.1  172.19  4820.8  171.27    4821  170.77  4824.5  170.77  4824.8  171.27
  4832.8  171.42  4842.8  172.88  4922.8  174.16  4972.8  173.93  5136.1  174.85
    5164  174.52  5389.3  176.49  5434.6  176.56  5627.9     178  5694.6  178.07
#Mann= 10 ,-1 , 0
  4119.6     .05       0  4237.6    .035       0  4360.5     .12       0
  4603.1     .07       0  4805.1     .12       0  4820.8     .05       0
  4824.8     .12       0  5136.1     .05       0  5389.3    .035       0
  5434.6     .05       0
Bank Sta=4820.8,4824.8
XS Rating Curve= 0 ,0
Exp/Cntr=0.3,0.1

Type RM Length L Ch R = 1 ,1912    ,645,645,645
BEGIN DESCRIPTION:
Mapping XS dde0905e
END DESCRIPTION:
XS GIS Cut Line= 4
      2505094.07     13499187.46      2504499.41     13499035.54
      2504087.08     13499070.26      2503492.46     13499204.81
#Sta/Elev= 30
    4211  179.42  4313.3  175.34  4367.4   172.4  4375.2  173.09  4416.5  172.44
  4442.7  173.25  4447.9  172.66  4478.4  173.19  4488.7  172.47  4519.2  173.12
  4695.1  170.14    4788  170.73  4849.3  172.09  4897.4  168.84  4897.7  168.34
  4901.2  168.34  4901.4  168.84  4909.5  170.17  4919.5  170.57  4969.7  170.09
    5050  170.81  5110.2  170.55  5115.7  171.23  5130.2  171.42  5281.2   171.8
  5322.7  171.48  5467.6  173.53  5548.3  173.09  5763.6  174.07  5848.2   175.3
#Mann= 5 ,-1 , 0
    4211     .05       0  4367.4     .12       0  4897.4     .05       0
  4901.4     .12       0  5281.2     .05       0
Bank Sta=4897.4,4901.4
XS Rating Curve= 0 ,0
Exp/Cntr=0.3,0.1

Type RM Length L Ch R = 1 ,1267    ,876,876,876
BEGIN DESCRIPTION:
Mapping XS 64f66c87
END DESCRIPTION:
XS GIS Cut Line= 4
      2505150.45     13499000.82      2504486.39     13498506.03
      2503917.81     13498592.83      2503344.91     13498996.47
#Sta/Elev= 30
  3958.2  177.75  4130.1  168.33  4180.2  167.08    4207  167.37  4238.6   167.6
  4301.7  166.35  4365.8  167.44  4630.6   167.5  4659.8  168.59  4674.4  168.05
  4701.5  168.63  4738.2  167.51  4759.9  168.23  4939.5  165.27  5000.2  161.78
  5020.4  164.22  5040.6  164.19  5060.9  162.89  5111.4  162.59  5129.7  160.45
  5129.9  159.95  5133.7  160.45  5145.4  160.92    5162   163.9  5172.1  164.67
  5203.3  165.59  5345.6  168.13  5494.4  170.35  5910.7  172.07  6062.3  173.56
#Mann= 6 ,-1 , 0
  3958.2     .05       0    4207     .12       0  5129.7     .05       0
  5133.7     .12       0  5203.3     .07       0  5345.6     .05       0
Bank Sta=5129.7,5133.7
XS Rating Curve= 0 ,0
Exp/Cntr=0.3,0.1

Type RM Length L Ch R = 1 ,391     ,0,0,0
BEGIN DESCRIPTION:
TRIB 2 TO EIGHTEENMILE CREEK 1.0
END DESCRIPTION:
XS GIS Cut Line= 4
      2505150.46     13498866.28      2504330.14     13497798.56
      2503748.54     13497785.54      2503436.03     13498666.66
#Sta/Elev= 30
  3282.4  170.83  3485.7  164.55  3772.5  164.37  3843.2  166.34  4121.3  163.74
  4183.4   163.5  4513.5  162.76    4754  163.45  4863.1   161.4  4914.1  158.86
  5013.3  149.73  5013.5  149.23  5017.3  149.73  5034.1  154.54  5054.1  156.86
  5104.1  159.01  5164.1  160.51  5204.1  156.64  5209.9   158.7  5227.9  158.67
  5236.4  160.92  5241.9  158.68  5252.5  158.39  5261.9  161.04  5267.2  159.42
  5273.7  162.62  5309.9  164.68  5445.8  167.75  5846.6  171.69  6145.5  171.31
#Mann= 11 ,-1 , 0
  3282.4     .05       0  3485.7     .12       0  4121.3     .07       0
  4183.4     .12       0  4513.5     .07       0  4863.1      .1       0
  5013.3     .05       0  5017.3      .1       0  5227.9     .07       0
  5309.9     .12       0  5445.8     .05       0
Bank Sta=5013.3,5017.3
XS Rating Curve= 0 ,0
Exp/Cntr=0.3,0.1

Chan Stop Cuts=-1
Use User Specified Reach Order=0
Composite Channel Slope=5