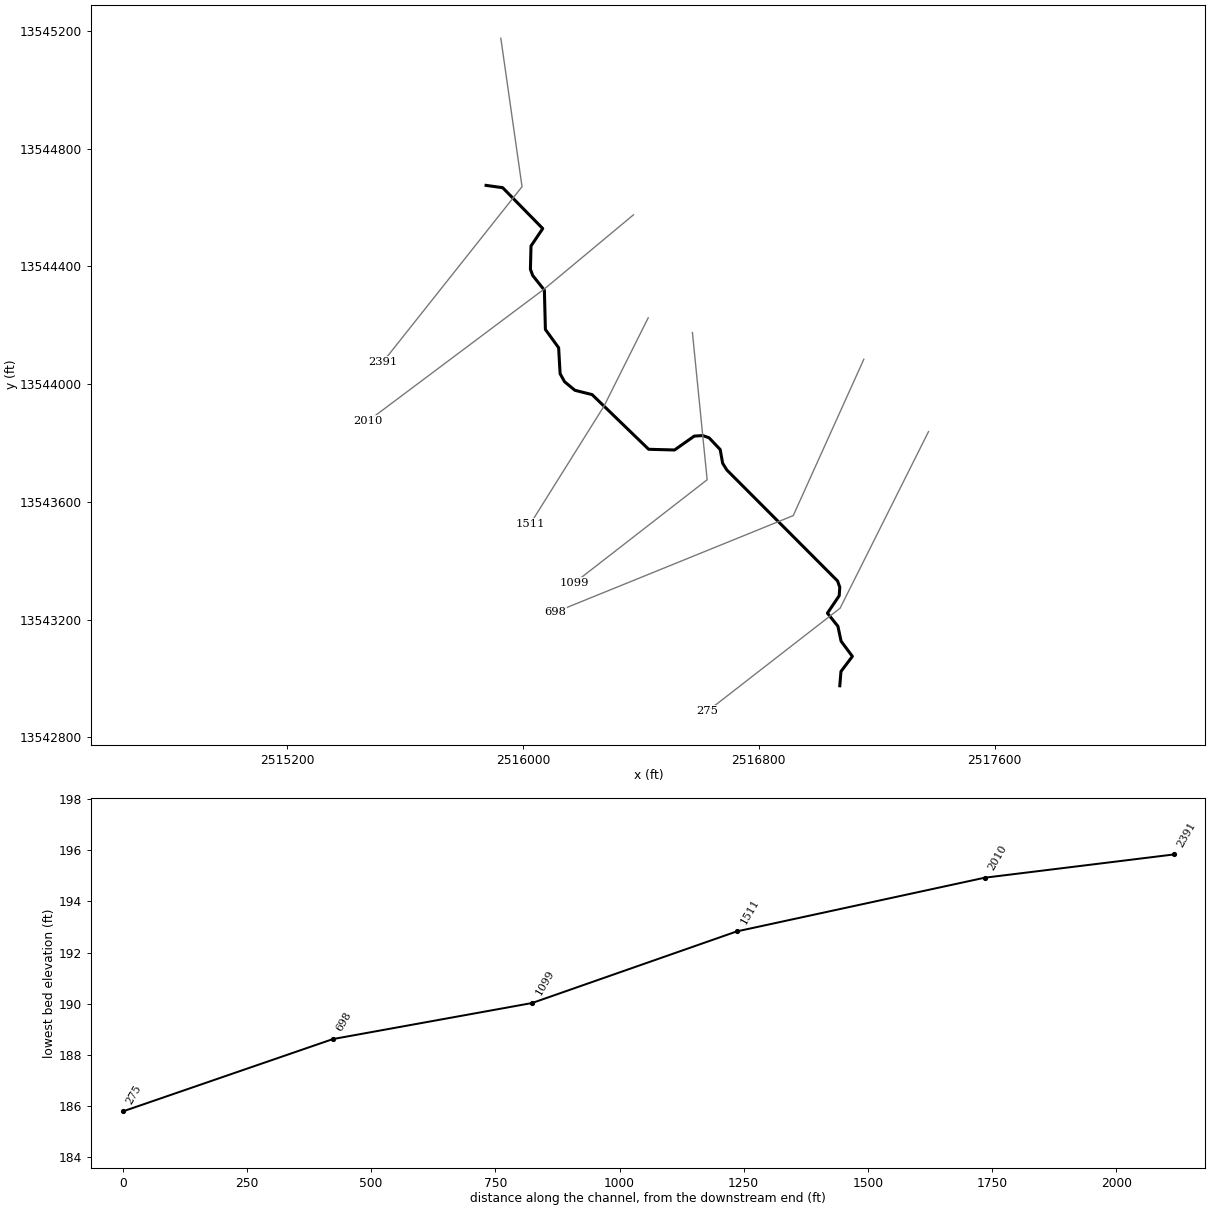
--- TRIB 2 TO FIVEMILE CREEK.prj (project) ---

Proj Title=TRIB 2 TO FIVEMILE CREEK Base Level Engineering
Current Plan=p01
Default Exp/Contr=0.3,0.1
English Units
Geom File=g01
Flow File=f01
Plan File=p01
BEGIN DESCRIPTION:
TRIB 2 TO FIVEMILE CREEK
END DESCRIPTION:

--- TRIB 2 TO FIVEMILE CREEK.p01 (plan) ---

Plan Title=Multiple Run
Short Identifier=Multiple
Geom File=g01
Flow File=f01
Subcritical Flow
K Sum by GR= 0
Std Step Tol= 0.01
Critical Tol= 0.01
Num of Std Step Trials= 20
Max Error Tol= 0.3
Flow Tol Ratio= 0.001
Split Flow NTrial= 30
Split Flow Tol= 0.02
Split Flow Ratio= 0.02
Log Output Level= 0
Friction Slope Method= 1
Unsteady Friction Slope Method= 2
Unsteady Bridges Friction Slope Method= 1
Parabolic Critical Depth
Global Vel Dist=  1 , 1 , 1
Global Log Level= 0
CheckData=True
Encroach Param= -1, 0, 0, 0
BEGIN DESCRIPTION:
Multiple Run
END DESCRIPTION:

--- TRIB 2 TO FIVEMILE CREEK.f01 (steady flow) ---

Flow Title=Multiple
Number of Profiles=7
Profile Names=10-year,25-year,50-year,1pct_min,100-year,1pct_plu,500-year
River Rch & RM= TRIB 2 TO FIVEMI,Reach-1,2391
     678    1095    1473     959    1914    3820    3197
Boundary for River Rch & Prof#=TRIB 2 TO FIVEMI,Reach-1,1
Up Type=0
Dn Type=3
Dn Slope=0.005
Boundary for River Rch & Prof#=TRIB 2 TO FIVEMI,Reach-1,2
Up Type=0
Dn Type=3
Dn Slope=0.005
Boundary for River Rch & Prof#=TRIB 2 TO FIVEMI,Reach-1,3
Up Type=0
Dn Type=3
Dn Slope=0.005
Boundary for River Rch & Prof#=TRIB 2 TO FIVEMI,Reach-1,4
Up Type=0
Dn Type=3
Dn Slope=0.005
Boundary for River Rch & Prof#=TRIB 2 TO FIVEMI,Reach-1,5
Up Type=0
Dn Type=3
Dn Slope=0.005
Boundary for River Rch & Prof#=TRIB 2 TO FIVEMI,Reach-1,6
Up Type=0
Dn Type=3
Dn Slope=0.005
Boundary for River Rch & Prof#=TRIB 2 TO FIVEMI,Reach-1,7
Up Type=0
Dn Type=3
Dn Slope=0.005

--- TRIB 2 TO FIVEMILE CREEK.g01 (geometry) ---

Geom Title=Existing Conditions

River Reach=TRIB 2 TO FIVEMI,Reach-1
Reach XY= 30
      2515875.00     13544675.00      2515931.21     13544667.24
      2516067.20     13544528.42      2516027.37     13544469.11
      2516025.39     13544390.28      2516033.09     13544368.97
      2516072.73     13544319.06      2516076.23     13544185.51
      2516121.14     13544123.40      2516126.10     13544035.33
      2516141.30     13544007.87      2516176.40     13543978.88
      2516234.66     13543964.21      2516426.50     13543778.46
      2516514.45     13543776.12      2516581.17     13543823.23
      2516609.79     13543825.10      2516631.34     13543817.64
      2516669.25     13543777.61      2516677.55     13543731.09
      2516691.66     13543708.34      2517067.50     13543331.05
      2517074.99     13543309.64      2517073.02     13543281.05
      2517033.07     13543221.69      2517068.64     13543177.28
      2517079.38     13543126.65      2517117.72     13543074.97
      2517079.00     13543023.64      2517075.00     13542975.00

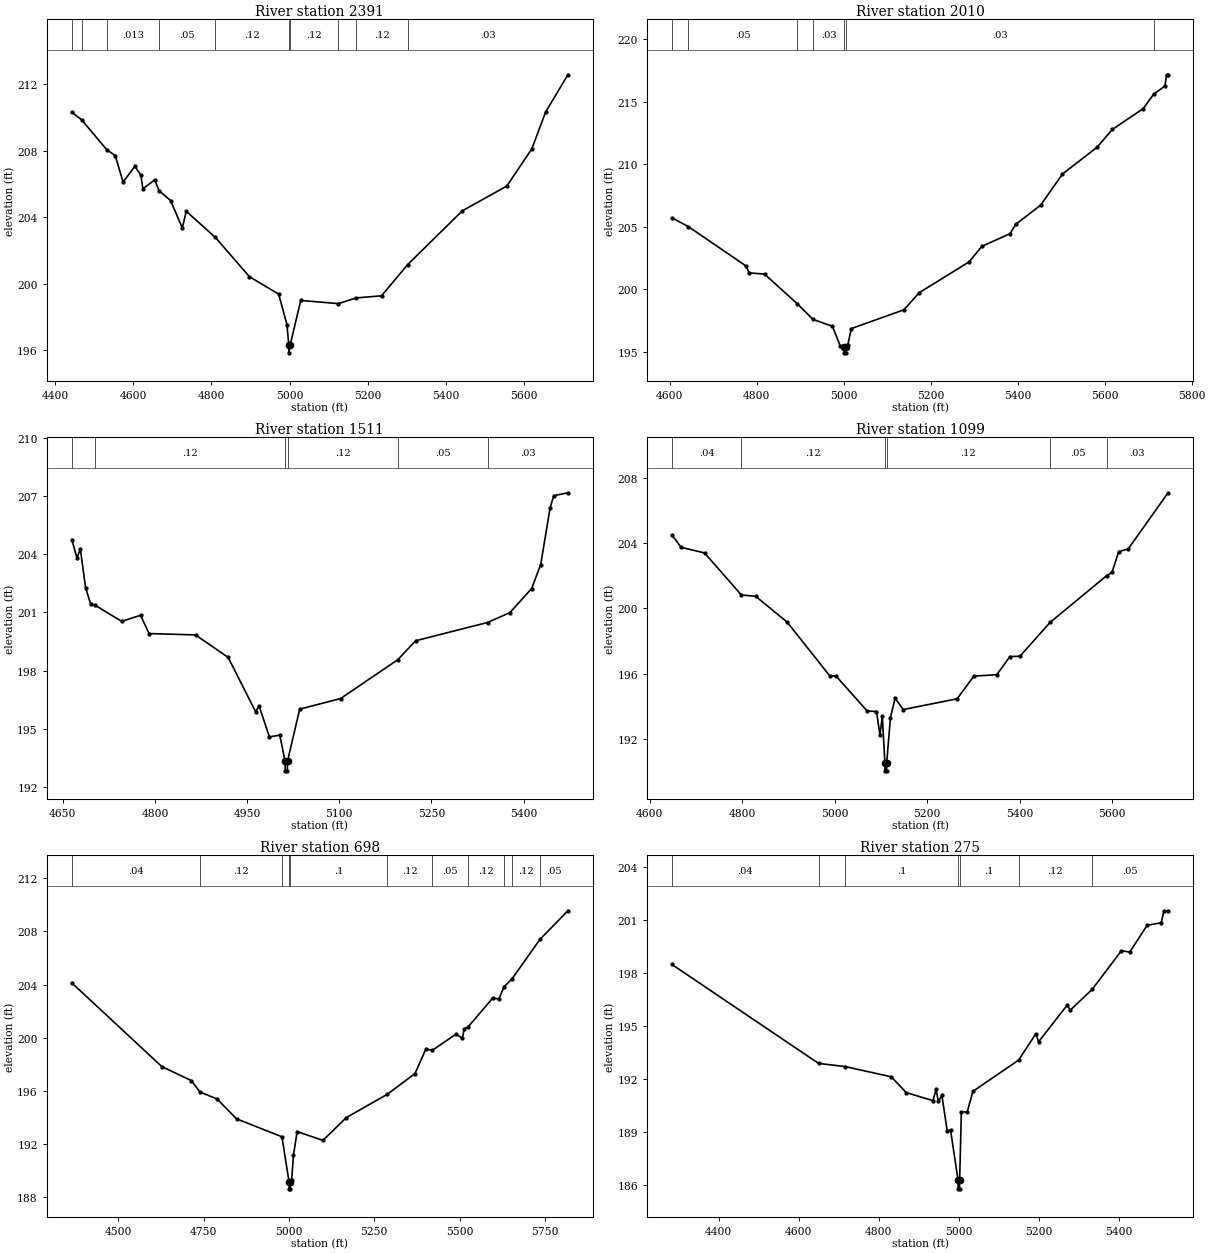
Type RM Length L Ch R = 1,2391,381,381,381
BEGIN DESCRIPTION:
TRIB 2 TO FIVEMILE CREEK 5.0
END DESCRIPTION:
XS GIS Cut Line= 3
      2515925.00     13545174.99      2515996.92     13544670.60
      2515524.99     13544074.99
#Sta/Elev= 30
  4442.7  210.30  4467.7  209.86  4532.3  208.05  4553.9  207.70  4574.0  206.11
  4604.3  207.06  4619.5  206.51  4624.7  205.70  4654.8  206.24  4666.0  205.59
  4695.5  205.00  4725.5  203.35  4735.6  204.35  4809.8  202.79  4897.2  200.42
  4972.1  199.37  4993.4  197.53  4997.8  196.34  4998.0  195.84  5001.8  196.34
  5028.6  198.99  5125.1  198.80  5169.7  199.14  5235.4  199.27  5301.9  201.14
  5442.1  204.38  5555.9  205.87  5620.0  208.11  5655.2  210.32  5712.1  212.56
#Mann=10,-1,0
  4442.7    0.04       0  4467.7    0.12       0  4532.3   0.013       0
  4666.0    0.05       0  4809.8    0.12       0  4997.8    0.05       0
  5001.8    0.12       0  5125.1    0.03       0  5169.7    0.12       0
  5301.9    0.03       0
Bank Sta=4997.8,5001.8
Exp/Cntr=0.3,0.1

Type RM Length L Ch R = 1,2010,499,499,499
BEGIN DESCRIPTION:
TRIB 2 TO FIVEMILE CREEK 4.0
END DESCRIPTION:
XS GIS Cut Line= 3
      2516374.99     13544574.99      2516075.00     13544325.00
      2515475.00     13543875.00
#Sta/Elev= 30
  4605.2  205.72  4642.8  205.02  4775.1  201.88  4782.9  201.32  4818.0  201.22
  4893.0  198.86  4929.6  197.60  4974.2  197.05  4992.4  195.44  5001.0  195.43
  5001.2  194.93  5004.7  194.93  5005.0  195.43  5009.2  195.54  5017.6  196.87
  5138.4  198.37  5173.8  199.74  5288.4  202.20  5317.6  203.44  5382.2  204.45
  5395.7  205.20  5453.0  206.74  5503.0  209.22  5582.2  211.35  5617.6  212.78
  5688.4  214.44  5712.7  215.60  5738.4  216.25  5742.6  217.15  5745.7  217.15
#Mann=7,-1,0
  4605.2    0.04       0  4642.8    0.05       0  4893.0    0.12       0
  4929.6    0.03       0  5001.0    0.03       0  5005.0    0.03       0
  5712.7    0.05       0
Bank Sta=5001,5005
Exp/Cntr=0.3,0.1

Type RM Length L Ch R = 1,1511,412,412,412
BEGIN DESCRIPTION:
TRIB 2 TO FIVEMILE CREEK 3.0
END DESCRIPTION:
XS GIS Cut Line= 3
      2516425.01     13544225.03      2516275.00     13543925.00
      2516025.02     13543525.03
#Sta/Elev= 30
  4664.8  204.76  4673.2  203.82  4678.8  204.26  4687.2  202.28  4695.6  201.42
  4702.2  201.38  4745.9  200.54  4776.6  200.85  4790.6  199.91  4866.1  199.84
  4919.2  198.68  4963.9  195.88  4969.5  196.18  4986.3  194.58  5003.2  194.67
  5011.8  193.33  5012.0  192.83  5015.5  192.83  5015.8  193.33  5035.6  196.01
  5102.2  196.56  5195.2  198.56  5224.3  199.54  5341.2  200.48  5377.6  200.99
  5413.0  202.23  5427.7  203.47  5443.0  206.39  5448.9  207.02  5471.9  207.17
#Mann=6,-1,0
  4664.8    0.04       0  4702.2    0.12       0  5011.8    0.05       0
  5015.8    0.12       0  5195.2    0.05       0  5341.2    0.03       0
Bank Sta=5011.8,5015.8
Exp/Cntr=0.3,0.1

Type RM Length L Ch R = 1,1099,401,401,401
BEGIN DESCRIPTION:
TRIB 2 TO FIVEMILE CREEK 2.0
END DESCRIPTION:
XS GIS Cut Line= 3
      2516575.00     13544175.03      2516625.00     13543675.00
      2516175.01     13543325.01
#Sta/Elev= 30
  4648.3  204.49  4668.4  203.74  4718.7  203.40  4798.4  200.82  4829.2  200.74
  4897.1  199.16  4990.0  195.84  5002.6  195.86  5070.4  193.70  5090.5  193.67
  5098.1  192.22  5103.1  193.40  5108.6  190.53  5108.9  190.03  5112.4  190.03
  5112.6  190.53  5120.7  193.30  5130.7  194.49  5148.3  193.79  5264.8  194.45
  5301.0  195.84  5350.8  195.93  5378.9  197.04  5400.6  197.06  5466.0  199.14
  5587.9  202.00  5599.7  202.20  5614.1  203.47  5634.9  203.65  5720.9  207.09
#Mann=6,-1,0
  4648.3    0.04       0  4798.4    0.12       0  5108.6    0.05       0
  5112.6    0.12       0  5466.0    0.05       0  5587.9    0.03       0
Bank Sta=5108.6,5112.6
Exp/Cntr=0.3,0.1

Type RM Length L Ch R = 1,698,423,423,423
BEGIN DESCRIPTION:
Mapping XS 93917d80
END DESCRIPTION:
XS GIS Cut Line= 3
      2517156.66     13544084.43      2516917.08     13543553.17
      2516109.89     13543225.09
#Sta/Elev= 30
  4363.3  204.13  4627.1  197.83  4713.7  196.77  4739.1  195.91  4789.0  195.39
  4846.3  193.89  4979.3  192.54  5000.3  189.12  5000.5  188.62  5004.0  188.62
  5004.3  189.12  5007.7  189.26  5013.1  191.16  5023.9  192.93  5099.4  192.27
  5168.3  193.99  5288.1  195.74  5369.3  197.30  5401.1  199.14  5420.5  199.06
  5489.6  200.27  5508.2  199.96  5513.6  200.65  5525.5  200.83  5596.6  202.97
  5615.3  202.93  5630.4  203.84  5653.3  204.42  5735.4  207.40  5817.4  209.56
#Mann=11,-1,0
  4363.3    0.04       0  4739.1    0.12       0  4979.3     0.1       0
  5000.3    0.05       0  5004.3     0.1       0  5288.1    0.12       0
  5420.5    0.05       0  5525.5    0.12       0  5630.4    0.03       0
  5653.3    0.12       0  5735.4    0.05       0
Bank Sta=5000.3,5004.3
Exp/Cntr=0.3,0.1

Type RM Length L Ch R = 1,275,0,0,0
BEGIN DESCRIPTION:
TRIB 2 TO FIVEMILE CREEK 1.0
END DESCRIPTION:
XS GIS Cut Line= 3
      2517376.03     13543838.53      2517076.04     13543238.54
      2516626.98     13542889.27
#Sta/Elev= 30
  4283.5  198.49  4649.9  192.89  4716.6  192.71  4831.7  192.13  4868.8  191.24
  4935.9  190.78  4943.5  191.43  4949.1  190.74  4958.1  191.08  4971.4  189.05
  4979.6  189.13  4998.4  186.29  4998.6  185.79  5002.1  185.79  5002.4  186.29
  5006.7  190.14  5021.2  190.14  5035.7  191.31  5149.9  193.08  5193.1  194.58
  5199.5  194.11  5271.9  196.21  5278.2  195.89  5333.6  197.08  5406.7  199.27
  5427.5  199.19  5470.9  200.71  5506.2  200.85  5513.0  201.53  5523.2  201.53
#Mann=7,-1,0
  4283.5    0.04       0  4649.9    0.05       0  4716.6     0.1       0
  4998.4    0.05       0  5002.4     0.1       0  5149.9    0.12       0
  5333.6    0.05       0
Bank Sta=4998.4,5002.4
Exp/Cntr=0.3,0.1

Chan Stop Cuts=-1