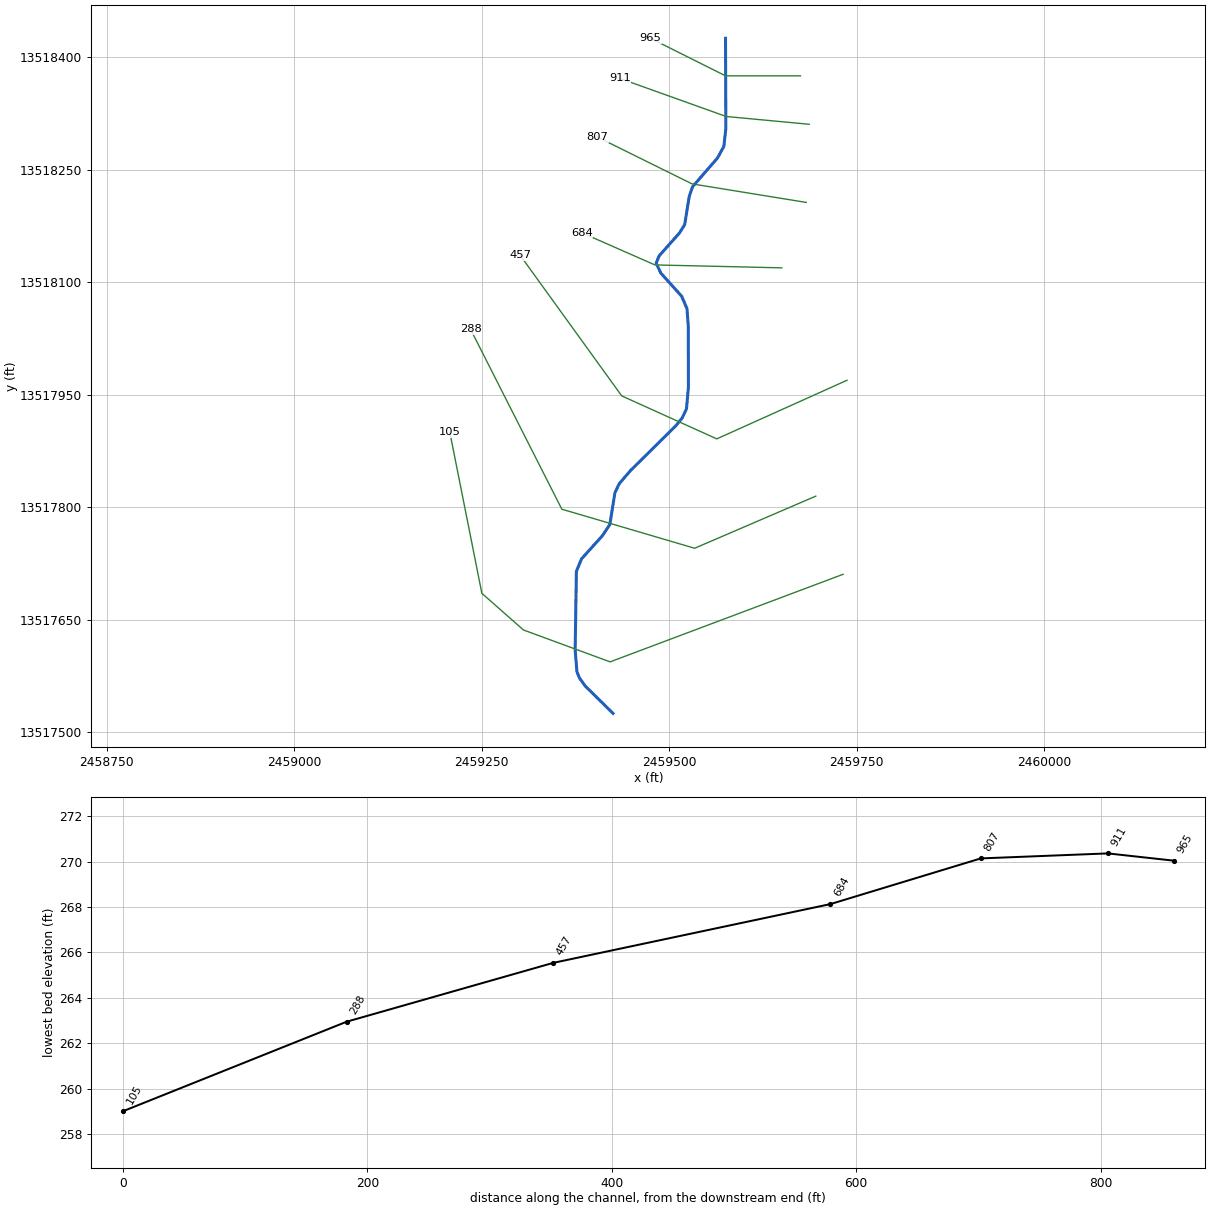
--- TRIB 2 TO HOOSIER CREEK.prj (project) ---

Proj Title=TRIB 2 TO HOOSIER CREEK Base Level Engineering
Current Plan=p01
Default Exp/Contr=0.3,0.1
English Units
Geom File=g01
Flow File=f01
Plan File=p01
Y Axis Title=Elevation
X Axis Title(PF)=Main Channel Distance
X Axis Title(XS)=Station
BEGIN DESCRIPTION:
TRIB 2 TO HOOSIER CREEK
END DESCRIPTION:
DSS Export Rating Curves= 0
DSS Export Rating Curve Sorted= 0
DSS Export Volume Flow Curves= 0
DXF OffsetX= 0
DXF OffsetY= 0
DXF ScaleX= 1
DXF ScaleY= 10

--- TRIB 2 TO HOOSIER CREEK.p01 (plan) ---

Plan Title=Multiple Run
Short Identifier=Multiple
Geom File=g01
Flow File=f01
Subcritical Flow
K Sum by GR= 0
Std Step Tol= 0.01
Critical Tol= 0.01
Num of Std Step Trials= 20
Max Error Tol= 0.3
Flow Tol Ratio= 0.001
Split Flow NTrial= 30
Split Flow Tol= 0.02
Split Flow Ratio= 0.02
Log Output Level= 0
Friction Slope Method= 1
Unsteady Friction Slope Method= 2
Unsteady Bridges Friction Slope Method= 1
Parabolic Critical Depth
Global Vel Dist=  1 , 1 , 1
Global Log Level= 0
CheckData=True
Encroach Param= -1, 0, 0, 0
BEGIN DESCRIPTION:
Multiple Run
END DESCRIPTION:

--- TRIB 2 TO HOOSIER CREEK.f01 (steady flow) ---

Flow Title=Multiple
Number of Profiles=7
Profile Names=10-year,25-year,50-year,1pct_min,100-year,1pct_plu,500-year
River Rch & RM= TRIB 2 TO HOOSIE,Reach-1,965
     259     397     516     326     651    1299    1021
Boundary for River Rch & Prof#=TRIB 2 TO HOOSIE,Reach-1,1
Up Type=0
Dn Type=3
Dn Slope=0.005
Boundary for River Rch & Prof#=TRIB 2 TO HOOSIE,Reach-1,2
Up Type=0
Dn Type=3
Dn Slope=0.005
Boundary for River Rch & Prof#=TRIB 2 TO HOOSIE,Reach-1,3
Up Type=0
Dn Type=3
Dn Slope=0.005
Boundary for River Rch & Prof#=TRIB 2 TO HOOSIE,Reach-1,4
Up Type=0
Dn Type=3
Dn Slope=0.005
Boundary for River Rch & Prof#=TRIB 2 TO HOOSIE,Reach-1,5
Up Type=0
Dn Type=3
Dn Slope=0.005
Boundary for River Rch & Prof#=TRIB 2 TO HOOSIE,Reach-1,6
Up Type=0
Dn Type=3
Dn Slope=0.005
Boundary for River Rch & Prof#=TRIB 2 TO HOOSIE,Reach-1,7
Up Type=0
Dn Type=3
Dn Slope=0.005

--- TRIB 2 TO HOOSIER CREEK.g01 (geometry) ---

Geom Title=Existing Conditions
Program Version=4.10

River Reach=TRIB 2 TO HOOSIE,Reach-1
Reach XY= 30
        2459575.       13518425.      2459575.44     13518304.82
       2459572.8     13518280.91      2459564.21     13518265.33
      2459531.09     13518227.17      2459526.62     13518214.29
      2459520.58     13518176.64       2459513.5     13518165.33
      2459486.42     13518134.93      2459482.53     13518125.01
      2459488.94      13518111.8      2459516.55     13518081.18
      2459523.63     13518064.56      2459525.41     13518040.19
      2459525.53     13517959.81      2459522.94     13517930.86
      2459517.18     13517918.82      2459508.54     13517908.25
      2459448.06     13517848.45      2459433.16     13517831.05
       2459427.5     13517818.96      2459420.78     13517776.75
      2459410.95     13517761.96      2459383.09     13517731.07
      2459376.18      13517714.5      2459374.55     13517609.85
      2459376.88     13517580.79      2459380.13     13517572.42
      2459387.91      13517561.5        2459425.       13517525.

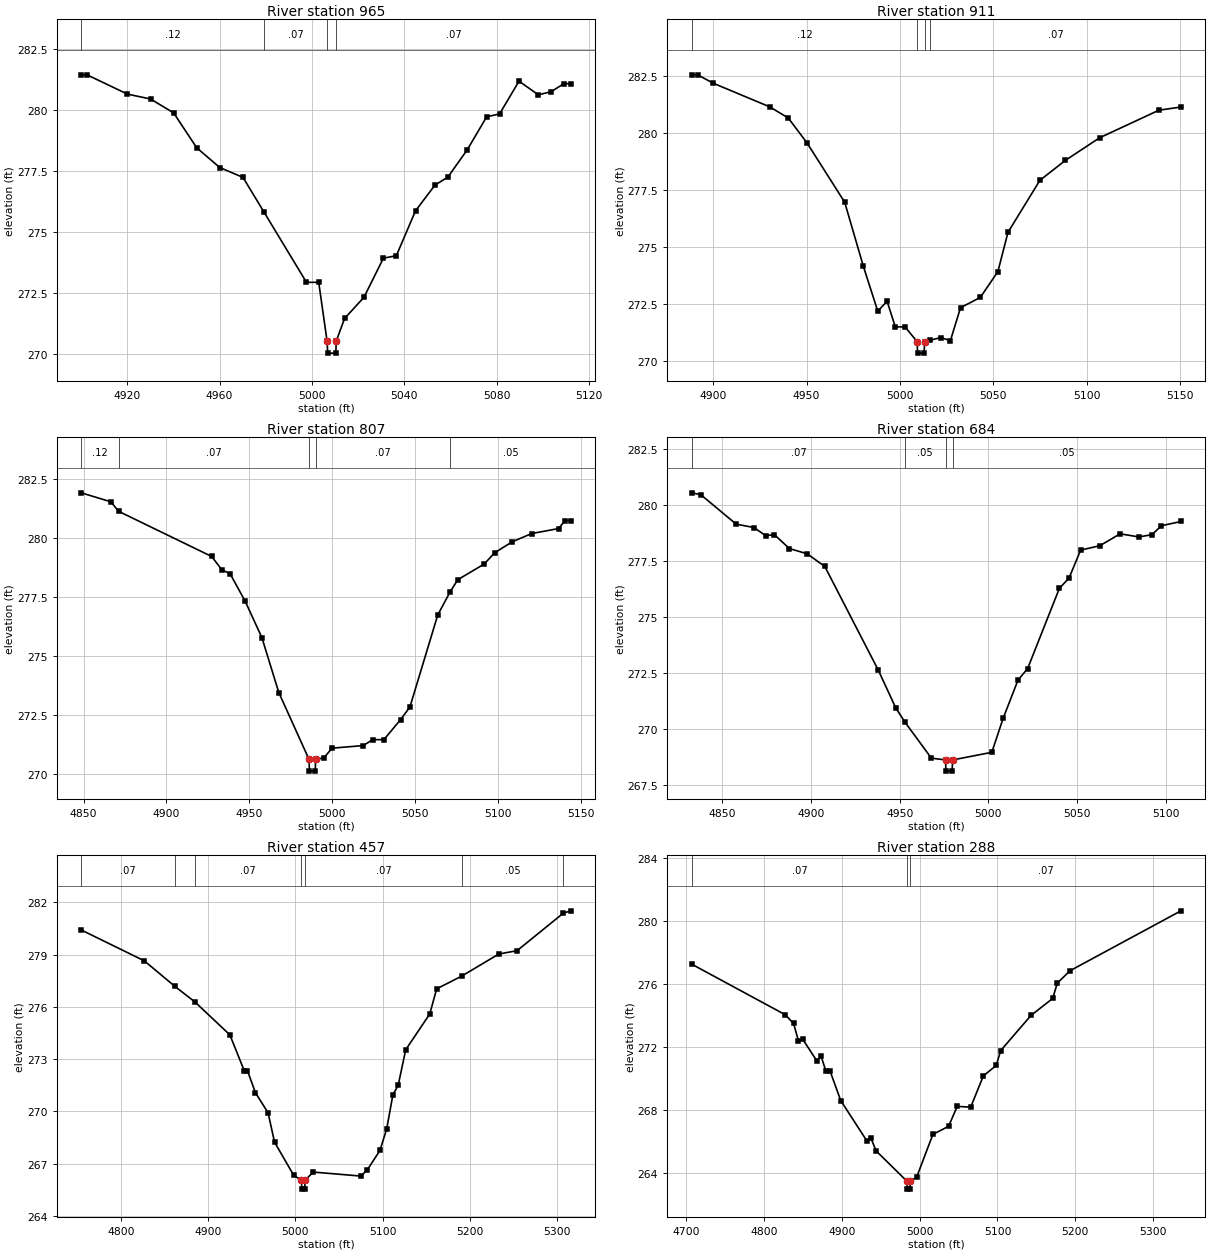
Type RM Length L Ch R = 1 ,965     ,54,54,54
BEGIN DESCRIPTION:
TRIB 2 TO HOOSIER CREEK 2.0
END DESCRIPTION:
XS GIS Cut Line= 3
      2459675.03       13518375.        2459575.       13518375.
      2459475.03     13518424.99
#Sta/Elev= 30
  4900.1  281.44  4902.6  281.44  4920.1  280.65  4930.1  280.45  4940.1  279.88
  4950.1  278.45  4960.1  277.64  4970.1  277.24  4979.2  275.82  4997.6  272.94
  5002.9  272.94  5006.5  270.54  5006.8  270.04  5010.3  270.04  5010.5  270.54
  5014.1  271.46  5022.5  272.33  5030.9  273.93  5036.5  274.03  5044.8  275.87
  5053.2  276.92  5058.8  277.25  5067.2  278.37  5075.6  279.72  5081.2  279.84
  5089.6  281.18    5098  280.62  5103.5  280.75  5109.1  281.08  5111.9  281.08
#Mann= 4 ,-1 , 0
  4900.1     .12       0  4979.2     .07       0  5006.5     .05       0
  5010.5     .07       0
Bank Sta=5006.5,5010.5
XS Rating Curve= 0 ,0
Exp/Cntr=0.3,0.1

Type RM Length L Ch R = 1 ,911     ,104,104,104
BEGIN DESCRIPTION:
Mapping XS 2c682aab
END DESCRIPTION:
XS GIS Cut Line= 3
      2459686.51     13518310.41      2459575.88     13518320.82
      2459433.91     13518371.62
#Sta/Elev= 28
  4888.5  282.55  4891.7  282.55  4900.1  282.18  4930.2  281.15  4940.2  280.66
  4950.3  279.56  4970.4  276.97  4980.4  274.16  4988.1   272.2  4993.1  272.63
  4997.5  271.51  5002.7  271.51  5009.2  270.86  5009.4  270.36  5012.9  270.36
  5013.2  270.86    5016  270.92  5021.7  271.04    5027  270.91  5032.4  272.35
    5043   272.8  5052.4  273.93  5057.8  275.65  5074.9  277.93  5088.5   278.8
  5106.8  279.79  5138.6     281  5150.4  281.14
#Mann= 4 ,-1 , 0
  4888.5     .12       0  5009.2     .05       0  5013.2     .12       0
    5016     .07       0
Bank Sta=5009.2,5013.2
XS Rating Curve= 0 ,0
Exp/Cntr=0.3,0.1

Type RM Length L Ch R = 1 ,807     ,123,123,123
BEGIN DESCRIPTION:
Mapping XS c135a5c9
END DESCRIPTION:
XS GIS Cut Line= 3
      2459682.63     13518206.24       2459530.3     13518230.98
      2459404.04     13518293.46
#Sta/Elev= 30
  4848.6   281.9  4866.5  281.52  4871.1  281.12  4927.3  279.21  4933.4  278.65
  4938.4  278.48  4947.5  277.32  4957.6  275.78  4967.8  273.46    4986  270.64
  4986.3  270.14  4989.8  270.14    4990  270.64    4995   270.7  4999.9  271.11
  5018.8  271.22  5024.4  271.47  5031.2  271.47  5041.3  272.32  5046.9  272.85
  5063.7  276.74  5071.2  277.72  5075.8  278.23  5091.7  278.89  5098.1  279.37
  5108.6  279.83  5120.4  280.18  5136.6  280.39  5140.5  280.73  5143.8  280.73
#Mann= 5 ,-1 , 0
  4848.6     .12       0  4871.1     .07       0    4986     .05       0
    4990     .07       0  5071.2     .05       0
Bank Sta=4986,4990
XS Rating Curve= 0 ,0
Exp/Cntr=0.3,0.1

Type RM Length L Ch R = 1 ,684     ,227,227,227
BEGIN DESCRIPTION:
Mapping XS 528e530a
END DESCRIPTION:
XS GIS Cut Line= 3
      2459650.13       13518119.      2459480.83     13518122.91
      2459383.21     13518165.86
#Sta/Elev= 30
  4832.7  280.56  4837.8  280.48  4857.8  279.16  4867.8  279.01  4874.4  278.65
  4879.4  278.69  4887.8  278.07  4897.8  277.84  4907.8  277.27  4937.9  272.65
  4947.9  270.94    4953  270.32  4967.9  268.71  4975.9  268.63  4976.1  268.13
  4979.6  268.13  4979.9  268.63    5002  268.97  5008.4  270.49  5016.8   272.2
  5022.2  272.71  5040.1  276.29  5045.6  276.76  5052.1     278    5063   278.2
  5074.4  278.73  5084.9  278.59  5092.3  278.69  5097.7  279.09  5108.7  279.28
#Mann= 4 ,-1 , 0
  4832.7     .07       0    4953     .05       0  4975.9     .05       0
  4979.9     .05       0
Bank Sta=4975.9,4979.9
XS Rating Curve= 0 ,0
Exp/Cntr=0.3,0.1

Type RM Length L Ch R = 1 ,457     ,169,169,169
BEGIN DESCRIPTION:
Mapping XS 82b60c81
END DESCRIPTION:
XS GIS Cut Line= 4
      2459736.97     13517969.11      2459563.37     13517890.98
      2459436.63     13517948.28      2459301.24     13518135.74
#Sta/Elev= 30
  4754.6  280.42  4826.8  278.65  4861.7  277.19  4884.8  276.29  4924.9   274.4
  4941.3  272.35    4945  272.35  4954.2  271.08  4968.7  269.92  4976.1  268.24
    4998  266.34    5007  266.04  5007.3  265.54  5010.8  265.54    5011  266.04
  5020.4  266.52  5074.9  266.29  5082.2  266.63  5096.9  267.76  5104.7  269.01
  5111.7  270.95  5117.8   271.5  5126.4  273.54    5154   275.6  5161.9  277.04
  5190.9  277.78  5233.1  279.04    5254  279.23  5306.9  281.38  5315.3  281.52
#Mann= 7 ,-1 , 0
  4754.6     .07       0  4861.7     .05       0  4884.8     .07       0
    5007     .05       0    5011     .07       0  5190.9     .05       0
  5306.9     .07       0
Bank Sta=5007,5011
XS Rating Curve= 0 ,0
Exp/Cntr=0.3,0.1

Type RM Length L Ch R = 1 ,288     ,183,183,183
BEGIN DESCRIPTION:
Mapping XS c2f7bcb9
END DESCRIPTION:
XS GIS Cut Line= 4
      2459695.32      13517814.6      2459533.85     13517745.15
      2459356.77     13517797.23      2459235.24     13518036.82
#Sta/Elev= 30
  4706.9  277.25    4827  274.04  4837.9  273.48  4844.2  272.36  4849.6  272.48
  4867.7  271.11  4873.2  271.41  4879.3  270.47  4884.7  270.47  4898.5  268.58
  4931.8  266.04    4937  266.23    4944  265.38  4983.7  263.45    4984  262.95
  4987.5  262.95  4987.7  263.45  4996.1  263.71    5017  266.43  5037.1  266.94
  5048.3  268.21  5065.6  268.16  5081.9  270.15  5098.4  270.81  5104.2  271.76
  5143.1  273.99    5171  275.07  5176.9  276.04  5193.2  276.83  5335.9  280.64
#Mann= 3 ,-1 , 0
  4706.9     .07       0  4983.7     .05       0  4987.7     .07       0
Bank Sta=4983.7,4987.7
XS Rating Curve= 0 ,0
Exp/Cntr=0.3,0.1

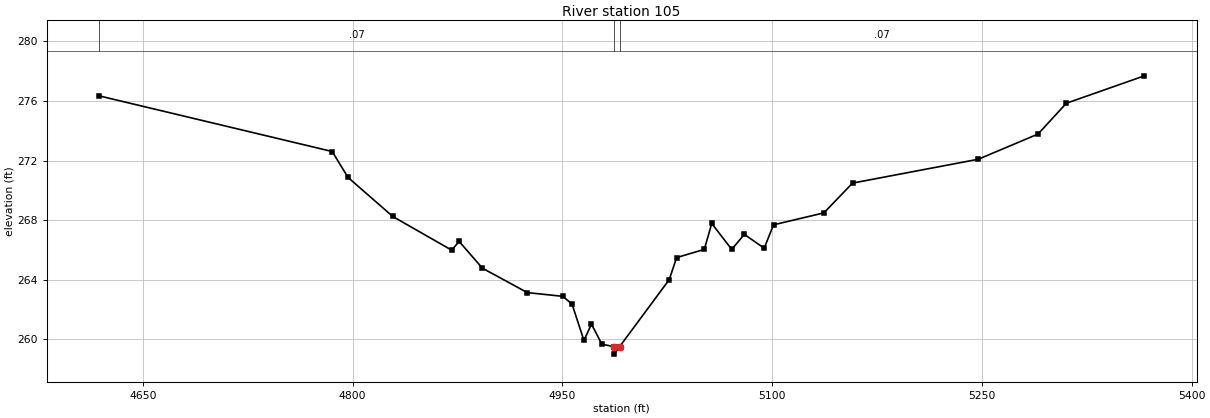
Type RM Length L Ch R = 1 ,105     ,0,0,0
BEGIN DESCRIPTION:
TRIB 2 TO HOOSIER CREEK 1.0
END DESCRIPTION:
XS GIS Cut Line= 5
      2459731.77     13517710.43      2459421.14     13517593.67
      2459305.57     13517636.21      2459250.15     13517685.08
      2459207.46     13517899.68
#Sta/Elev= 30
  4618.5  276.35  4785.4  272.61  4796.7  270.87  4828.7  268.25  4870.8  265.99
  4876.2  266.57  4892.8  264.78  4924.9  263.14  4950.3  262.89  4956.9  262.37
  4965.4  259.93  4970.8  261.02  4978.2  259.68  4986.9  259.51  4987.1  259.01
  4990.9  259.51  5026.4  264.01  5031.7  265.49  5051.5  266.04  5056.8  267.78
  5071.1  266.04  5080.1  267.05  5094.3  266.12    5101  267.69    5137  268.49
  5157.5  270.49  5247.4  272.09  5290.1  273.78  5310.4  275.85  5366.2  277.69
#Mann= 3 ,-1 , 0
  4618.5     .07       0  4986.9     .05       0  4990.9     .07       0
Bank Sta=4986.9,4990.9
XS Rating Curve= 0 ,0
Exp/Cntr=0.3,0.1

Chan Stop Cuts=-1
Use User Specified Reach Order=0
Composite Channel Slope=5