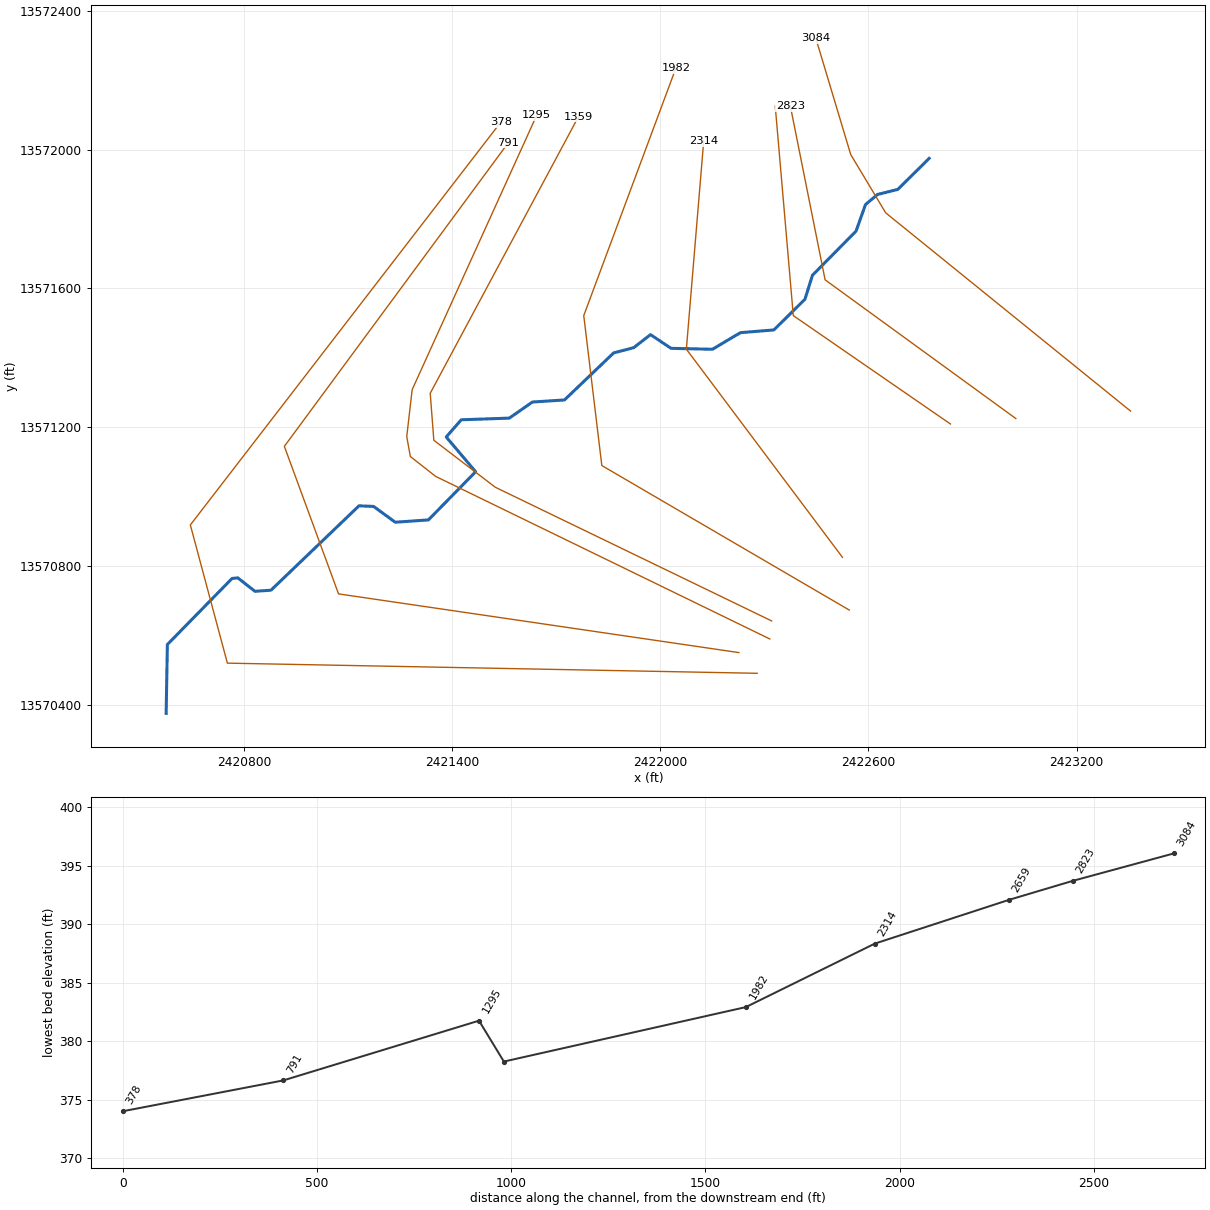
--- TRIB 2 TO LITTLE SALT CREEK.prj (project) ---

Proj Title=TRIB 2 TO LITTLE SALT CREEK Base Level Engineering
Current Plan=p01
Default Exp/Contr=0.3,0.1
English Units
Geom File=g01
Flow File=f01
Plan File=p01
Y Axis Title=Elevation
X Axis Title(PF)=Main Channel Distance
X Axis Title(XS)=Station
BEGIN DESCRIPTION:
TRIB 2 TO LITTLE SALT CREEK
END DESCRIPTION:
DSS Export Rating Curves= 0
DSS Export Rating Curve Sorted= 0
DSS Export Volume Flow Curves= 0
DXF OffsetX= 0
DXF OffsetY= 0
DXF ScaleX= 1
DXF ScaleY= 10

--- TRIB 2 TO LITTLE SALT CREEK.p01 (plan) ---

Plan Title=Multiple Run
Short Identifier=Multiple
Geom File=g01
Flow File=f01
Subcritical Flow
K Sum by GR= 0
Std Step Tol= 0.01
Critical Tol= 0.01
Num of Std Step Trials= 20
Max Error Tol= 0.3
Flow Tol Ratio= 0.001
Split Flow NTrial= 30
Split Flow Tol= 0.02
Split Flow Ratio= 0.02
Log Output Level= 0
Friction Slope Method= 1
Unsteady Friction Slope Method= 2
Unsteady Bridges Friction Slope Method= 1
Parabolic Critical Depth
Global Vel Dist=  1 , 1 , 1
Global Log Level= 0
CheckData=True
Encroach Param= -1, 0, 0, 0
BEGIN DESCRIPTION:
Multiple Run
END DESCRIPTION:

--- TRIB 2 TO LITTLE SALT CREEK.f01 (steady flow) ---

Flow Title=Multiple
Number of Profiles=7
Profile Names=10-year,25-year,50-year,1pct_min,100-year,1pct_plu,500-year
River Rch & RM= TRIB 2 TO LITTLE,Reach-1,3084
     440     700     932     602    1202    2399    1979
Boundary for River Rch & Prof#=TRIB 2 TO LITTLE,Reach-1,1
Up Type=0
Dn Type=3
Dn Slope=0.005
Boundary for River Rch & Prof#=TRIB 2 TO LITTLE,Reach-1,2
Up Type=0
Dn Type=3
Dn Slope=0.005
Boundary for River Rch & Prof#=TRIB 2 TO LITTLE,Reach-1,3
Up Type=0
Dn Type=3
Dn Slope=0.005
Boundary for River Rch & Prof#=TRIB 2 TO LITTLE,Reach-1,4
Up Type=0
Dn Type=3
Dn Slope=0.005
Boundary for River Rch & Prof#=TRIB 2 TO LITTLE,Reach-1,5
Up Type=0
Dn Type=3
Dn Slope=0.005
Boundary for River Rch & Prof#=TRIB 2 TO LITTLE,Reach-1,6
Up Type=0
Dn Type=3
Dn Slope=0.005
Boundary for River Rch & Prof#=TRIB 2 TO LITTLE,Reach-1,7
Up Type=0
Dn Type=3
Dn Slope=0.005

--- TRIB 2 TO LITTLE SALT CREEK.g01 (geometry) ---

Geom Title=Existing Conditions
Program Version=4.10

River Reach=TRIB 2 TO LITTLE,Reach-1
Reach XY= 30
        2422775.       13571975.      2422684.69     13571885.72
      2422626.43     13571871.13       2422591.5     13571842.05
      2422564.21     13571765.34      2422438.63     13571638.21
      2422416.85     13571568.93      2422327.44     13571480.52
      2422230.98     13571472.64      2422150.07     13571424.77
      2422030.86     13571427.45      2421971.68     13571466.96
      2421923.35     13571429.45      2421865.32     13571414.25
       2421723.5     13571278.61      2421630.98     13571272.64
      2421564.49     13571226.23      2421425.98     13571221.46
      2421382.53     13571171.87      2421467.39     13571071.67
      2421331.17     13570932.76      2421235.55     13570926.12
      2421173.25     13570971.66      2421131.03     13570973.38
      2420877.29     13570730.12      2420831.05     13570726.99
      2420781.55     13570765.67      2420764.95     13570763.89
      2420578.53     13570573.54        2420575.       13570375.

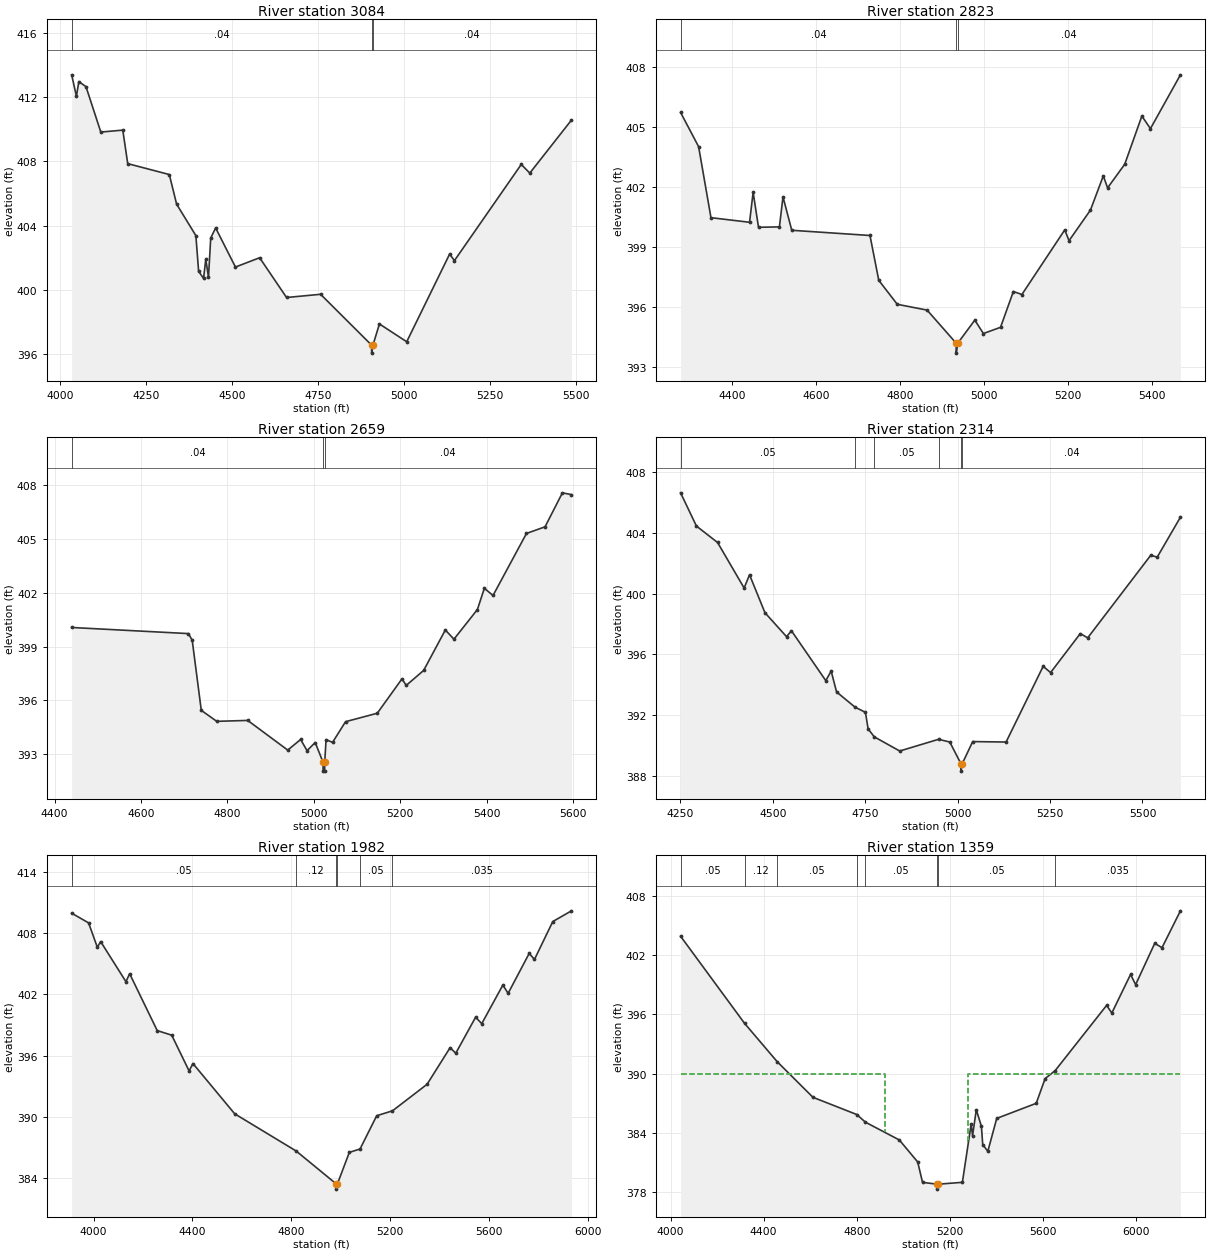
Type RM Length L Ch R = 1 ,3084    ,261,261,261
BEGIN DESCRIPTION:
LGII4622
END DESCRIPTION:
XS GIS Cut Line= 4
      2423355.79     13571246.54      2422649.72     13571818.12
      2422548.85     13571986.23      2422448.36      13572321.2
#Sta/Elev= 30
  4033.7   413.4  4047.6  412.06  4054.6  412.98  4075.4  412.66  4118.5  409.83
  4182.5  409.95  4196.8  407.86  4317.8  407.18  4339.1  405.33  4395.1  403.37
  4403.1  401.14  4417.5   400.7  4423.9   401.9  4431.8  400.78  4438.3  403.22
  4452.6  403.85  4510.2  401.41  4580.6  401.99  4658.9  399.51    4758  399.71
  4906.3  396.54  4906.5  396.04  4910.3  396.54  4929.1  397.86  5008.5  396.75
  5133.4  402.22  5147.3  401.81  5341.7  407.81  5366.6  407.27  5487.9  410.58
#Mann= 3 ,-1 , 0
  4033.7     .04       0  4906.3     .04       0  4910.3     .04       0
Bank Sta=4906.3,4910.3
XS Rating Curve= 0 ,0
Exp/Cntr=0.3,0.1

Type RM Length L Ch R = 1 ,2823    ,164,164,164
BEGIN DESCRIPTION:
TRIB 2 TO LITTLE SALT CREEK 3.0
END DESCRIPTION:
XS GIS Cut Line= 3
        2423025.       13571225.        2422475.       13571625.
        2422375.     13572125.02
#Sta/Elev= 30
  4277.1  405.72    4320  404.01  4349.4  400.46  4441.3  400.23  4449.8  401.73
  4462.6  399.98  4512.4     400  4520.9   401.5  4541.8  399.83    4728  399.57
  4748.9  397.33    4793  396.13    4864  395.84  4933.1  394.19  4933.4  393.69
  4937.1  394.19  4977.6  395.34    4998  394.67  5038.8  394.98  5069.4  396.77
  5089.7  396.62  5191.7  399.85  5201.9  399.31  5252.9  400.84  5283.5  402.55
  5293.7  401.95  5334.5  403.13  5375.3  405.54  5395.7  404.91  5467.1   407.6
#Mann= 3 ,-1 , 0
  4277.1     .04       0  4933.1     .04       0  4937.1     .04       0
Bank Sta=4933.1,4937.1
XS Rating Curve= 0 ,0
Exp/Cntr=0.3,0.1

Type RM Length L Ch R = 1 ,2659    ,345,345,345
BEGIN DESCRIPTION:
Mapping XS 69f56262
END DESCRIPTION:
XS GIS Cut Line= 3
      2422836.42     13571209.32      2422383.31     13571521.81
      2422331.23     13572125.95
#Sta/Elev= 30
  4439.6  400.06  4709.8  399.72  4718.6  399.35  4739.6  395.45  4775.4  394.84
  4847.1  394.89  4939.7  393.24  4969.5  393.83  4984.4  393.21  5003.3  393.66
  5021.3  392.57  5021.6  392.07  5025.1  392.07  5025.3  392.57  5028.4  393.82
  5043.4  393.67  5073.5  394.82  5146.9  395.29    5204   397.2    5214  396.84
  5254.2  397.67  5304.4  399.92  5324.4  399.41  5378.7  401.06  5394.7  402.24
  5414.8  401.84  5492.2  405.29  5535.2  405.66  5575.4  407.55  5596.4  407.45
#Mann= 3 ,-1 , 0
  4439.6     .04       0  5021.3     .04       0  5025.3     .04       0
Bank Sta=5021.3,5025.3
XS Rating Curve= 0 ,0
Exp/Cntr=0.3,0.1

Type RM Length L Ch R = 1 ,2314    ,332,332,332
BEGIN DESCRIPTION:
TRIB 2 TO LITTLE SALT CREEK 2.0
END DESCRIPTION:
XS GIS Cut Line= 3
      2422525.03     13570824.97        2422075.       13571425.
        2422125.     13572024.98
#Sta/Elev= 30
  4250.5  406.61  4293.3  404.43  4350.5  403.35  4422.4  400.36    4437  401.23
  4478.7  398.74    4537  397.17  4550.5  397.55  4643.3  394.28  4657.8  394.91
  4672.4  393.54  4722.4  392.54  4750.5   392.2  4757.8  391.11  4774.5  390.59
  4843.3  389.66  4948.4  390.43  4978.7  390.25  5008.6  388.84  5008.8  388.34
  5012.6  388.84  5040.7  390.28    5131  390.25  5231.3  395.22  5251.4  394.81
  5331.7  397.37  5351.8  397.09  5522.3  402.51  5539.9  402.39  5602.6  405.01
#Mann= 6 ,-1 , 0
  4250.5     .05       0  4722.4     .04       0  4774.5     .05       0
  4948.4     .04       0  5008.6     .04       0  5012.6     .04       0
Bank Sta=5008.6,5012.6
XS Rating Curve= 0 ,0
Exp/Cntr=0.3,0.1

Type RM Length L Ch R = 1 ,1982    ,623,623,623
BEGIN DESCRIPTION:
Mapping XS 9bb2b365
END DESCRIPTION:
XS GIS Cut Line= 4
      2422544.75     13570672.86      2421831.23     13571089.52
      2421779.14     13571521.81      2422044.78     13572235.38
#Sta/Elev= 30
  3911.5  409.95    3980     409  4015.4  406.61  4028.8  407.17  4131.2  403.24
  4146.2  404.02  4257.8  398.45  4316.5     398  4386.8   394.5  4402.5  395.22
  4571.3   390.3  4820.4  386.65    4983  383.42  4983.3  382.92    4987  383.42
  5035.4  386.52  5078.7  386.85  5146.2  390.11  5210.1  390.59  5350.1  393.19
  5443.4  396.78  5466.2  396.23  5546.5  399.76  5571.4  399.13  5656.8  402.91
  5678.1   402.1  5763.5  406.01  5784.8  405.42  5858.9  409.13  5934.6  410.18
#Mann= 6 ,-1 , 0
  3911.5     .05       0  4820.4     .12       0    4983     .05       0
    4987     .12       0  5078.7     .05       0  5210.1    .035       0
Bank Sta=4983,4987
XS Rating Curve= 0 ,0
Exp/Cntr=0.3,0.1

Type RM Length L Ch R = 1 ,1359    ,64,64,64
BEGIN DESCRIPTION:
Mapping XS 30a04f53
END DESCRIPTION:
XS GIS Cut Line= 5
      2422320.79     13570641.61      2421523.93     13571027.02
      2421346.85     13571162.44      2421336.43     13571297.85
      2421763.51     13572094.71
#Sta/Elev= 30
  4043.1  403.94    4318   395.1  4458.1  391.21    4612  387.59  4800.5  385.84
  4837.1  385.07  4983.1  383.26    5062  381.03  5082.8  378.96  5145.2  378.77
  5145.5  378.27  5149.2  378.77  5254.1  378.96    5292   384.9  5297.7  383.68
  5313.9  386.33  5335.9  384.64  5341.5  382.79  5363.5  382.11  5401.7  385.45
  5571.4  386.98  5609.6  389.49  5653.1  390.31  5873.8  396.92  5896.4  396.15
  5976.8  400.06  5998.7  399.03  6080.7  403.22    6112  402.78  6191.1  406.52
#Mann= 8 ,-1 , 0
  4043.1     .05       0    4318     .12       0  4458.1     .05       0
  4800.5     .12       0  4837.1     .05       0  5145.2     .05       0
  5149.2     .05       0  5653.1    .035       0
#XS Ineff= 2 , 0
       0    4920     390    5280       0     390
Permanent Ineff=
       F       F
Bank Sta=5145.2,5149.2
XS Rating Curve= 0 ,0
Exp/Cntr=0.3,0.1

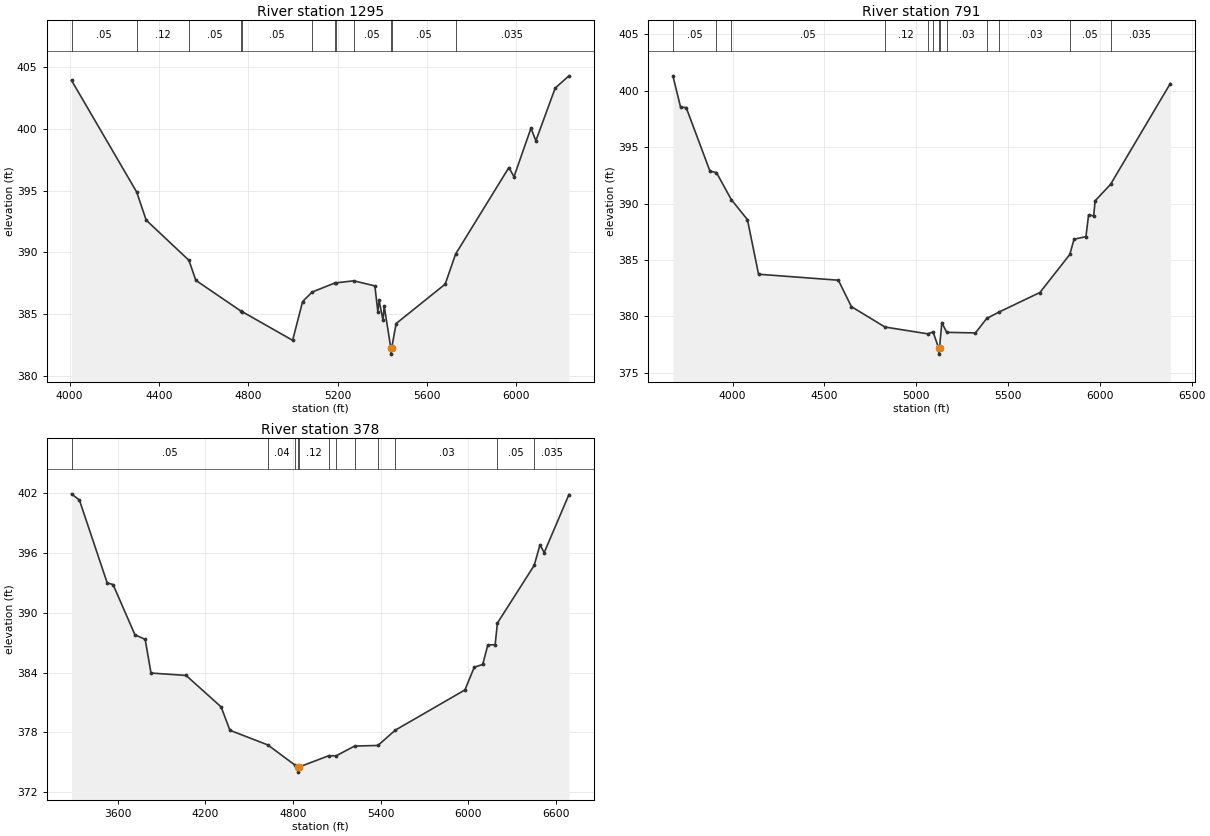
Type RM Length L Ch R = 1 ,1295    ,504,504,504
BEGIN DESCRIPTION:
Mapping XS 94faa880
END DESCRIPTION:
XS GIS Cut Line= 6
      2422315.61     13570589.51      2421352.06     13571058.27
      2421279.14     13571115.56      2421268.73     13571172.85
      2421284.35     13571308.27      2421643.72     13572099.92
#Sta/Elev= 30
  4008.3  403.94  4300.3  394.89  4342.6  392.62  4534.3  389.36    4565  387.74
  4766.3  385.26  4772.7   385.2  4998.7  382.88  5043.4  386.02    5086  386.79
  5188.6  387.53  5191.2  387.53  5272.4   387.7  5367.1  387.29  5380.4   385.2
  5385.9  386.11  5403.5  384.51  5408.9  385.65  5438.4  382.26  5438.6  381.76
  5442.4  382.26  5462.4  384.24    5682  387.43  5728.8  389.87  5967.5  396.88
  5990.3  396.13  6066.4  400.07  6088.3  399.05  6174.9  403.32  6236.5  404.31
#Mann= 12 ,-1 , 0
  4008.3     .05       0  4300.3     .12       0  4534.3     .05       0
  4766.3     .12       0  4772.7     .05       0    5086     .12       0
  5188.6     .05       0  5191.2     .12       0  5272.4     .05       0
  5438.4     .05       0  5442.4     .05       0  5728.8    .035       0
Bank Sta=5438.4,5442.4
XS Rating Curve= 0 ,0
Exp/Cntr=0.3,0.1

Type RM Length L Ch R = 1 ,791     ,413,413,413
BEGIN DESCRIPTION:
Mapping XS 9b805e72
END DESCRIPTION:
XS GIS Cut Line= 4
      2422226.58     13570550.22      2421072.09     13570719.49
      2420915.84     13571144.84      2421561.94     13572020.76
#Sta/Elev= 30
  3675.3  401.32  3717.3  398.54  3747.7  398.51  3877.3  392.87  3912.5  392.75
  3993.2  390.36  4081.2  388.58  4141.8  383.74  4576.4  383.21  4647.2  380.87
  4830.3  379.06  5062.5  378.46  5092.1  378.62    5123  377.16  5123.2  376.66
    5127  377.16  5139.6  379.45  5166.4  378.59  5322.8  378.54  5383.8  379.82
  5452.4   380.4  5673.7  382.12  5836.5  385.49  5859.5  386.84  5924.3  387.07
  5938.9  389.01  5966.5   388.9  5974.4  390.25  6058.2   391.7  6383.7  400.64
#Mann= 13 ,-1 , 0
  3675.3     .05       0  3912.5     .12       0  3993.2     .05       0
  4830.3     .12       0  5062.5     .03       0  5092.1     .12       0
    5123     .05       0    5127     .12       0  5166.4     .03       0
  5383.8     .12       0  5452.4     .03       0  5836.5     .05       0
  6058.2    .035       0
Bank Sta=5123,5127
XS Rating Curve= 0 ,0
Exp/Cntr=0.3,0.1

Type RM Length L Ch R = 1 ,378     ,0,0,0
BEGIN DESCRIPTION:
Mapping XS b22b6caf
END DESCRIPTION:
XS GIS Cut Line= 4
      2422279.13     13570490.56      2420751.56     13570519.84
      2420644.79     13570918.27      2421539.56     13572079.11
#Sta/Elev= 30
  3282.8  401.89  3336.9  401.26    3527  392.97    3567  392.81    3717  387.78
    3787  387.32    3827  383.95  4067.1  383.71  4307.1  380.56  4367.1  378.22
  4627.3  376.75    4816   374.7  4834.7  374.53    4835  374.03  4838.7  374.53
  5045.2  375.68  5092.8  375.65    5221  376.64  5380.6   376.7  5499.5  378.23
  5976.6  382.26  6040.2  384.53  6098.2  384.81  6133.5  386.77  6183.3  386.78
  6198.9  388.95  6450.8  394.73  6490.4  396.78  6519.4  396.01  6688.8  401.82
#Mann= 12 ,-1 , 0
  3282.8     .05       0  4627.3     .04       0    4816     .12       0
  4834.7     .05       0  4838.7     .12       0  5045.2     .03       0
  5092.8     .12       0    5221     .03       0  5380.6     .12       0
  5499.5     .03       0  6198.9     .05       0  6450.8    .035       0
Bank Sta=4834.7,4838.7
XS Rating Curve= 0 ,0
Exp/Cntr=0.3,0.1

Chan Stop Cuts=-1
Use User Specified Reach Order=0
Composite Channel Slope=5