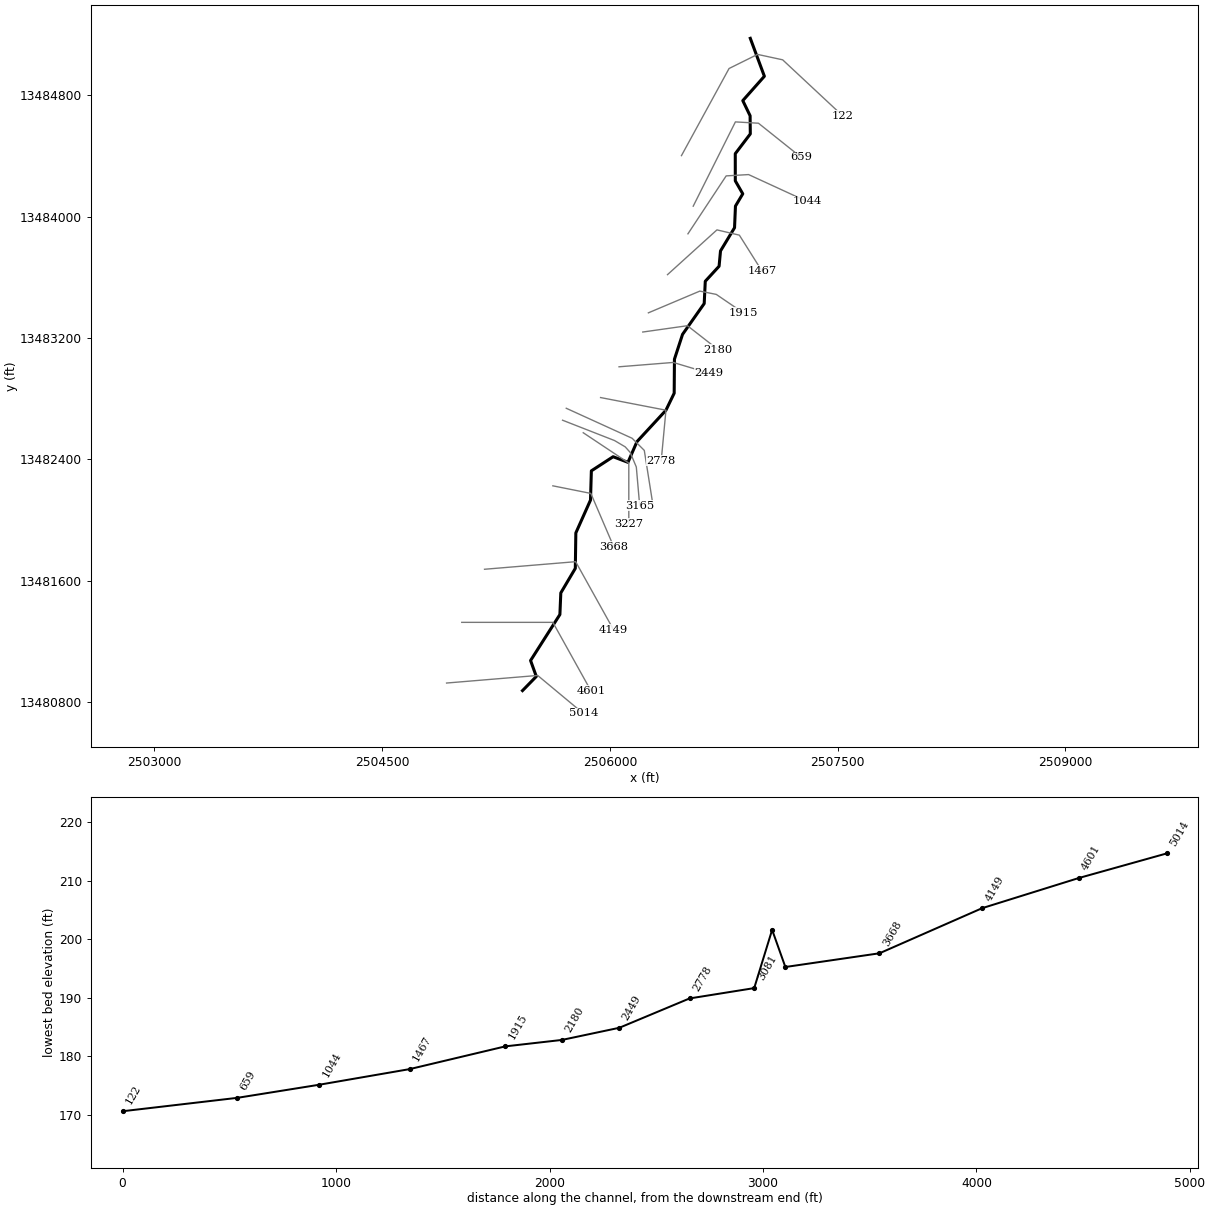
--- TRIB 2 TO MILBY CREEK.prj (project) ---

Proj Title=TRIB 2 TO MILBY CREEK Base Level Engineering
Current Plan=p01
Default Exp/Contr=0.3,0.1
English Units
Geom File=g01
Flow File=f01
Plan File=p01
Y Axis Title=Elevation
X Axis Title(PF)=Main Channel Distance
X Axis Title(XS)=Station
BEGIN DESCRIPTION:
TRIB 2 TO MILBY CREEK
END DESCRIPTION:
DSS Export Rating Curves= 0
DSS Export Rating Curve Sorted= 0
DSS Export Volume Flow Curves= 0
DXF OffsetX= 0
DXF OffsetY= 0
DXF ScaleX= 1
DXF ScaleY= 10

--- TRIB 2 TO MILBY CREEK.p01 (plan) ---

Plan Title=Multiple Run
Program Version=4.10
Short Identifier=Multiple
Geom File=g01
Flow File=f01
Subcritical Flow
K Sum by GR= 0
Std Step Tol= 0.01
Critical Tol= 0.01
Num of Std Step Trials= 20
Max Error Tol= 0.3
Flow Tol Ratio= 0.001
Split Flow NTrial= 30
Split Flow Tol= 0.02
Split Flow Ratio= 0.02
Log Output Level= 0
Friction Slope Method= 1
Unsteady Friction Slope Method= 2
Unsteady Bridges Friction Slope Method= 1
Parabolic Critical Depth
Global Vel Dist= 1 , 1 , 1
Global Log Level= 0
CheckData=True
Encroach Param=-1 ,0,0, 0
BEGIN DESCRIPTION:
Multiple Run
END DESCRIPTION:
Computation Interval=1HOUR
Output Interval=1HOUR
Run HTab= 0
Run UNet= 0
Run PostProcess= 0
Run WQNet= 0
UNET Theta= 1
UNET Theta Warmup= 1
UNET ZTol= 0.02
UNET ZSATol= 0.05
UNET MxIter= 20
UNET MaxInSteps= 0
UNET DtIC= 0
UNET DtMin= 0
UNET MaxCRTS= 20
UNET WFStab= 2
UNET SFStab= 1
UNET WFX= 1
UNET SFX= 1
UNET DSS MLevel= 4
UNET DZMax Abort= 100
UNET Convert EG Bridges= 0
UNET Use Existing IB Tables=-1
UNET Froude Reduction=False
UNET Froude Limit= 1
UNET Froude Power= 10
UNET Time Slicing=0,0, 5
UNET Junction Losses=0
Instantaneous Interval=1HOUR
Write IC File= 0
Write IC File at Sim End=0
Echo Input=False
Echo Parameters=False
Echo Output=False
Write Detailed= 0
WQ AD Non Conservative
WQ ULTIMATE=-1
WQ Max Comp Step=1HOUR
WQ Output Interval=15MIN
WQ Output Selected Increments= 0
WQ Output face flow=0
WQ Output face velocity=0
WQ Output face area=0
WQ Output face dispersion=0
WQ Output cell volume=0
WQ Output cell surface area=0
WQ Output cell continuity=0
WQ Output cumulative cell continuity=0
WQ Output face conc=0
WQ Output face dconc_dx=0
WQ Output face courant=0
WQ Output face peclet=0
WQ Output face adv mass=0
WQ Output face disp mass=0
WQ Output cell mass=0
WQ Output cell source sink temp=0
WQ Output cell source sink nsm=0
WQ Output MaxMinRange=-1
WQ Daily Max Min Mean=-1
WQ Daily Range=0
WQ Daily Time=0
WQ Create Restart=0
WQ Fixed Restart=0
WQ System Summary=0
WQ Use Fixed Temperature=0
Sorting and Armoring Iterations= 10
XS Update Threshold= 0.02
Hydraulics Update Threshold= 0.02
Energy Slope Method= 1
Volume Change Method= 0
XS Weighting Method= 0
Number of US Weighted Cross Sections= 1
Number of DS Weighted Cross Sections= 1
Upstream XS Weight=0.25
Main XS Weight=0.5
Downstream XS Weight=0.25
Number of DS XS's Weighted with US Boundary= 1
Upstream Boundary Weight= 1
Weight of XSs Associated with US Boundary= 0
Number of US XS's Weighted with DS Boundary= 1
Downstream Boundary Weight= 0.5
Weight of XSs Associated with DS Boundary= 0.5
Sediment Output Level= 4
Mass or Volume Output= 0
Output Increment Type= 1
Profile and TS Output Increment= 10
XS Output Flag= 0
XS Output Increment= 10
Disregard all LS=0
Disregard all Conn=0
Disregard all Breaches=0
Disregard all Pumps=0

--- TRIB 2 TO MILBY CREEK.f01 (steady flow) ---

Flow Title=Multiple
Program Version=4.10
Number of Profiles= 7
Profile Names=10-year,25-year,50-year,1pct_min,100-year,1pct_plu,500-year
River Rch & RM=TRIB 2 TO MILBY,Reach-1         ,5014
     190     280     355     219     437     871     651
River Rch & RM=TRIB 2 TO MILBY,Reach-1         ,2449
     719    1164    1569    1023    2042    4074    3421
Boundary for River Rch & Prof#=TRIB 2 TO MILBY,Reach-1         , 1
Up Type= 0
Dn Type= 3
Dn Slope=0.0061
Boundary for River Rch & Prof#=TRIB 2 TO MILBY,Reach-1         , 2
Up Type= 0
Dn Type= 3
Dn Slope=0.0061
Boundary for River Rch & Prof#=TRIB 2 TO MILBY,Reach-1         , 3
Up Type= 0
Dn Type= 3
Dn Slope=0.0061
Boundary for River Rch & Prof#=TRIB 2 TO MILBY,Reach-1         , 4
Up Type= 0
Dn Type= 3
Dn Slope=0.0061
Boundary for River Rch & Prof#=TRIB 2 TO MILBY,Reach-1         , 5
Up Type= 0
Dn Type= 3
Dn Slope=0.0061
Boundary for River Rch & Prof#=TRIB 2 TO MILBY,Reach-1         , 6
Up Type= 0
Dn Type= 3
Dn Slope=0.0061
Boundary for River Rch & Prof#=TRIB 2 TO MILBY,Reach-1         , 7
Up Type= 0
Dn Type= 3
Dn Slope=0.0061
DSS Import GetInterval= 0
DSS Import GetPeak= 0
DSS Import FillOption= 0

--- TRIB 2 TO MILBY CREEK.g01 (geometry) ---

Geom Title=Existing Conditions
Program Version=4.10

River Reach=TRIB 2 TO MILBY ,Reach-1
Reach XY= 30
        2505425.       13480875.      2505515.99     13480968.27
      2505478.17     13481073.35      2505671.24     13481376.56
      2505677.25     13481519.07      2505772.76     13481680.93
      2505776.22      13481914.5      2505872.74     13482130.94
      2505878.45     13482323.75      2506021.72     13482416.92
      2506119.41      13482379.8      2506178.84     13482516.38
      2506369.17      13482722.7       2506423.8      13482835.5
      2506425.52     13483059.78      2506478.83     13483223.42
      2506621.45     13483426.47      2506628.56     13483573.53
      2506719.46     13483672.58      2506728.83     13483773.41
      2506821.24     13483926.56       2506827.3     13484069.07
       2506875.4       13484150.      2506826.24      13484235.5
      2506826.05     13484414.56      2506925.06     13484544.99
      2506923.77      13484664.5       2506875.6     13484764.38
      2507017.69      13484924.9        2506925.       13485175.

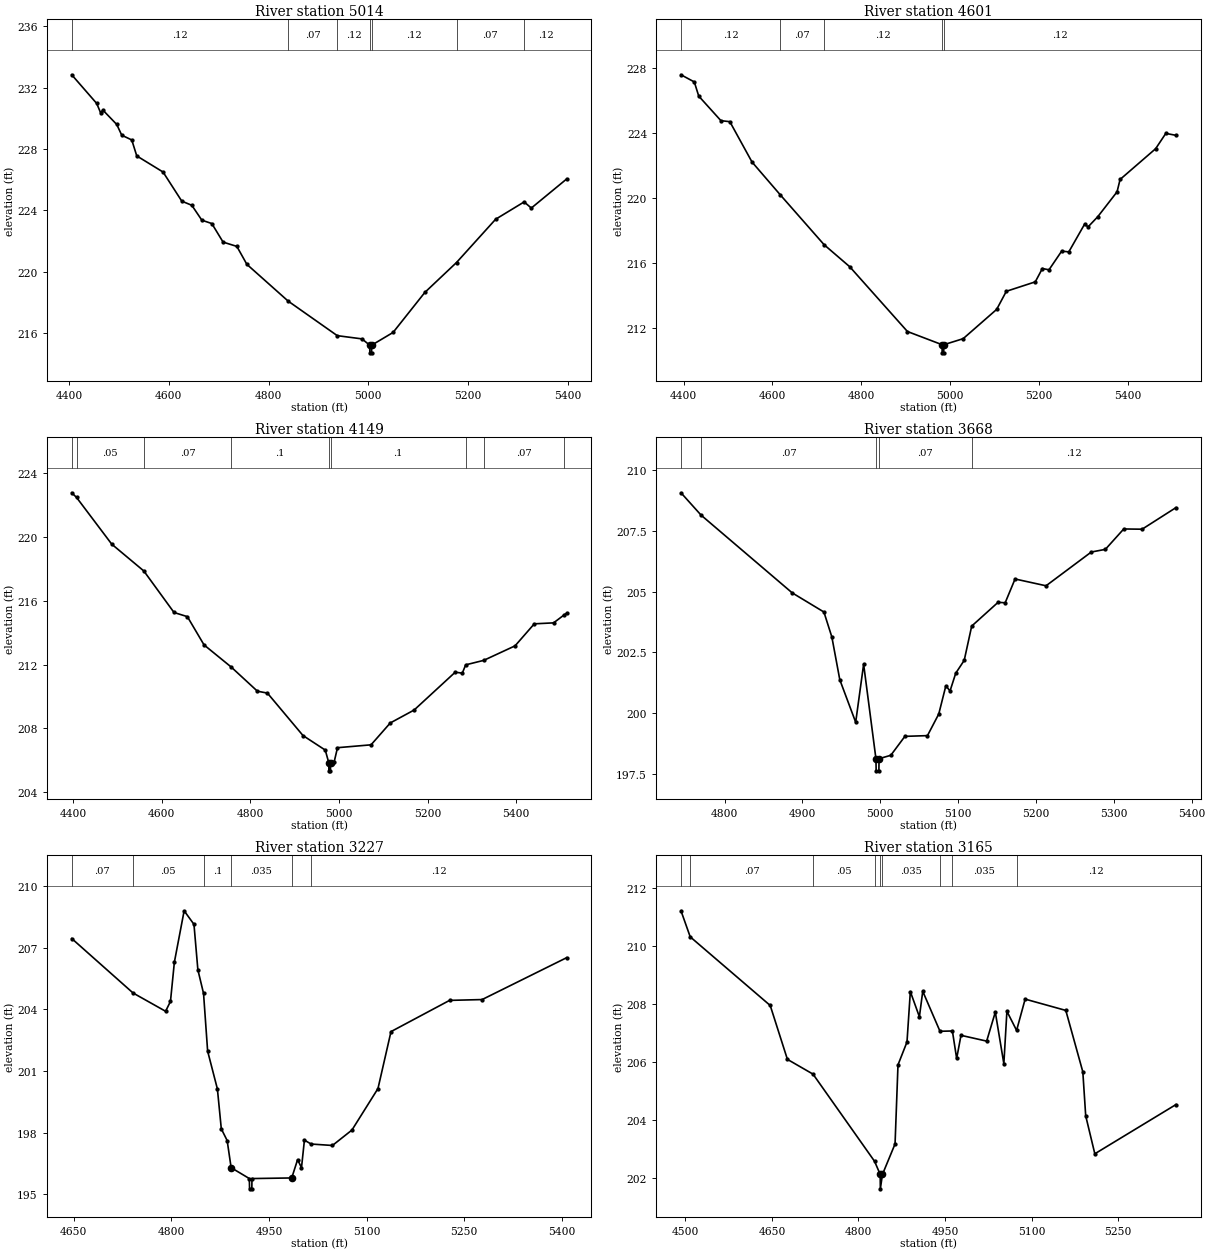
Type RM Length L Ch R = 1 ,5014    ,413,413,413
BEGIN DESCRIPTION:
TRIB 2 TO MILBY CREEK 11.0
END DESCRIPTION:
XS GIS Cut Line= 3
      2504925.03       13480925.        2505525.       13480975.
      2505825.03     13480724.98
#Sta/Elev= 30
  4405.3  232.84  4455.4  230.97    4463  230.38    4468  230.53  4495.6   229.6
  4505.6   228.9  4525.7  228.59  4535.7  227.55  4588.4   226.5    4626   224.6
  4646.1  224.33  4666.2  223.36  4686.2  223.14  4708.8  221.93  4736.4  221.65
  4756.5  220.48  4839.4  218.08  4937.8  215.83  4987.3  215.62  5002.8  215.21
  5003.1  214.71  5006.6  214.71  5006.8  215.21  5049.7  216.04  5113.4  218.65
  5176.9   220.6  5255.3  223.42  5312.5  224.55  5326.9  224.15  5397.9  226.05
#Mann= 7 ,-1 , 0
  4405.3     .12       0  4839.4     .07       0  4937.8     .12       0
  5002.8     .05       0  5006.8     .12       0  5176.9     .07       0
  5312.5     .12       0
Bank Sta=5002.8,5006.8
XS Rating Curve= 0 ,0
Exp/Cntr=0.3,0.1

Type RM Length L Ch R = 1 ,4601    ,452,452,452
BEGIN DESCRIPTION:
TRIB 2 TO MILBY CREEK 10.0
END DESCRIPTION:
XS GIS Cut Line= 3
      2505025.01       13481325.        2505625.       13481325.
      2505875.01     13480874.97
#Sta/Elev= 30
  4393.9  227.57  4423.9  227.13  4433.9  226.26  4483.9  224.75  4503.9  224.69
  4553.9  222.21    4618  220.18  4716.3  217.13  4773.9  215.78  4903.9   211.8
  4981.9  210.99  4982.1  210.49  4985.6  210.49  4985.9  210.99  5029.4  211.36
  5104.9  213.16  5126.6  214.27  5191.8  214.85  5207.8  215.67  5222.7  215.59
  5251.3  216.74  5267.3  216.69  5302.8  218.39  5310.8  218.23  5332.5  218.85
    5376  220.38  5382.8  221.14  5462.9  223.03  5485.8  223.97  5508.7  223.85
#Mann= 5 ,-1 , 0
  4393.9     .12       0    4618     .07       0  4716.3     .12       0
  4981.9     .05       0  4985.9     .12       0
Bank Sta=4981.9,4985.9
XS Rating Curve= 0 ,0
Exp/Cntr=0.3,0.1

Type RM Length L Ch R = 1 ,4149    ,481,481,481
BEGIN DESCRIPTION:
TRIB 2 TO MILBY CREEK 9.0
END DESCRIPTION:
XS GIS Cut Line= 3
      2505175.02       13481675.        2505775.       13481725.
      2506024.98     13481275.04
#Sta/Elev= 30
  4397.1  222.76  4407.9  222.47  4487.4  219.54  4559.8  217.86  4627.9  215.26
    4658     215  4695.6  213.23  4756.6  211.85    4816  210.33  4838.6  210.21
  4918.9  207.55  4969.1  206.64  4977.1  205.84  4977.3  205.34  4980.8  205.34
  4981.1  205.84  4989.1  205.89  4996.7  206.79  5072.4  206.97  5115.8  208.34
  5169.6  209.15  5262.3  211.52  5278.3  211.46  5285.9  211.98  5326.5  212.26
  5397.3  213.17  5440.7  214.55  5484.2  214.61  5508.1  215.11  5513.9  215.22
#Mann= 9 ,-1 , 0
  4397.1     .12       0  4407.9     .05       0  4559.8     .07       0
  4756.6      .1       0  4977.1     .05       0  4981.1      .1       0
  5285.9     .12       0  5326.5     .07       0  5508.1     .12       0
Bank Sta=4977.1,4981.1
XS Rating Curve= 0 ,0
Exp/Cntr=0.3,0.1

Type RM Length L Ch R = 1 ,3668    ,441,441,441
BEGIN DESCRIPTION:
TRIB 2 TO MILBY CREEK 8.0
END DESCRIPTION:
XS GIS Cut Line= 3
      2505624.97     13482225.01        2505875.       13482175.
      2506025.01     13481824.97
#Sta/Elev= 30
    4744  209.07  4769.8  208.15  4886.8  204.95  4927.6  204.16  4937.8  203.13
    4948  201.37  4968.4  199.62  4978.6  202.01  4994.4  198.12  4994.7  197.62
  4998.2  197.62  4998.4  198.12  5013.5  198.26  5031.6  199.04  5060.6  199.07
  5075.1  199.96  5084.2  201.12  5089.6  200.91  5096.9  201.64  5107.8  202.17
  5117.4  203.58  5151.3  204.56  5160.4  204.54  5173.1  205.52  5212.9  205.24
    5271  206.63  5289.1  206.74  5312.7  207.58  5336.3  207.57  5379.8  208.46
#Mann= 5 ,-1 , 0
    4744     .05       0  4769.8     .07       0  4994.4     .05       0
  4998.4     .07       0  5117.4     .12       0
Bank Sta=4994.4,4998.4
XS Rating Curve= 0 ,0
Exp/Cntr=0.3,0.1

Type RM Length L Ch R = 1 ,3227    ,62,62,62
BEGIN DESCRIPTION:
TRIB 2 TO MILBY CREEK 7.0
END DESCRIPTION:
XS GIS Cut Line= 3
      2505825.02     13482574.99        2506125.       13482375.
        2506125.     13481975.03
#Sta/Elev= 30
  4647.1  207.45  4741.3   204.8  4791.3  203.91  4798.8  204.39  4804.8   206.3
  4819.8   208.8  4834.9  208.14  4840.9  205.93  4849.6  204.78  4855.9  201.97
  4870.9  200.13  4876.9  198.19  4885.9  197.62    4892   196.3    4920  195.77
  4920.3  195.27  4923.8  195.27    4924  195.77  4985.1   195.8  4994.1  196.69
  5000.1   196.3  5004.6  197.64  5014.9  197.45  5047.6  197.38  5077.6  198.13
  5117.6  200.15  5137.6  202.92  5227.6  204.44  5277.6  204.48  5407.6  206.52
#Mann= 6 ,-1 , 0
  4647.1     .07       0  4741.3     .05       0  4849.6      .1       0
    4892    .035       0  4985.1    .035       0  5014.9     .12       0
Bank Sta=4892,4985.1
XS Rating Curve= 0 ,0
Exp/Cntr=0.3,0.1

Type RM Length L Ch R = 1 ,3165    ,84,84,84
BEGIN DESCRIPTION:
Mapping XS 46d566b1
END DESCRIPTION:
XS GIS Cut Line= 6
      2505688.81     13482657.54      2506031.24     13482523.43
      2506101.55     13482481.76      2506134.11      13482445.3
      2506174.47     13482348.95       2506196.6     13482095.08
#Sta/Elev= 30
  4492.3  211.23  4508.3  210.33    4647  207.96  4676.8   206.1  4721.2  205.59
  4827.9  202.58  4837.6  202.13  4837.9  201.63  4841.6  202.13  4863.4  203.18
  4868.5  205.91  4884.1   206.7  4889.9  208.44  4905.6  207.57  4911.4  208.45
  4941.3  207.07  4962.8  207.08  4970.2  206.13  4977.7  206.93  5022.2  206.73
  5037.2  207.73    5052  205.95  5057.3  207.76  5074.1   207.1  5088.9  208.18
  5159.4  207.79  5188.9  205.67  5193.9  204.15  5209.7  202.84  5350.4  204.54
#Mann= 9 ,-1 , 0
  4492.3     .05       0  4508.3     .07       0  4721.2     .05       0
  4827.9    .035       0  4837.6    .035       0  4841.6    .035       0
  4941.3      .1       0  4962.8    .035       0  5074.1     .12       0
Bank Sta=4837.6,4841.6
XS Rating Curve= 0 ,0
Exp/Cntr=0.3,0.1

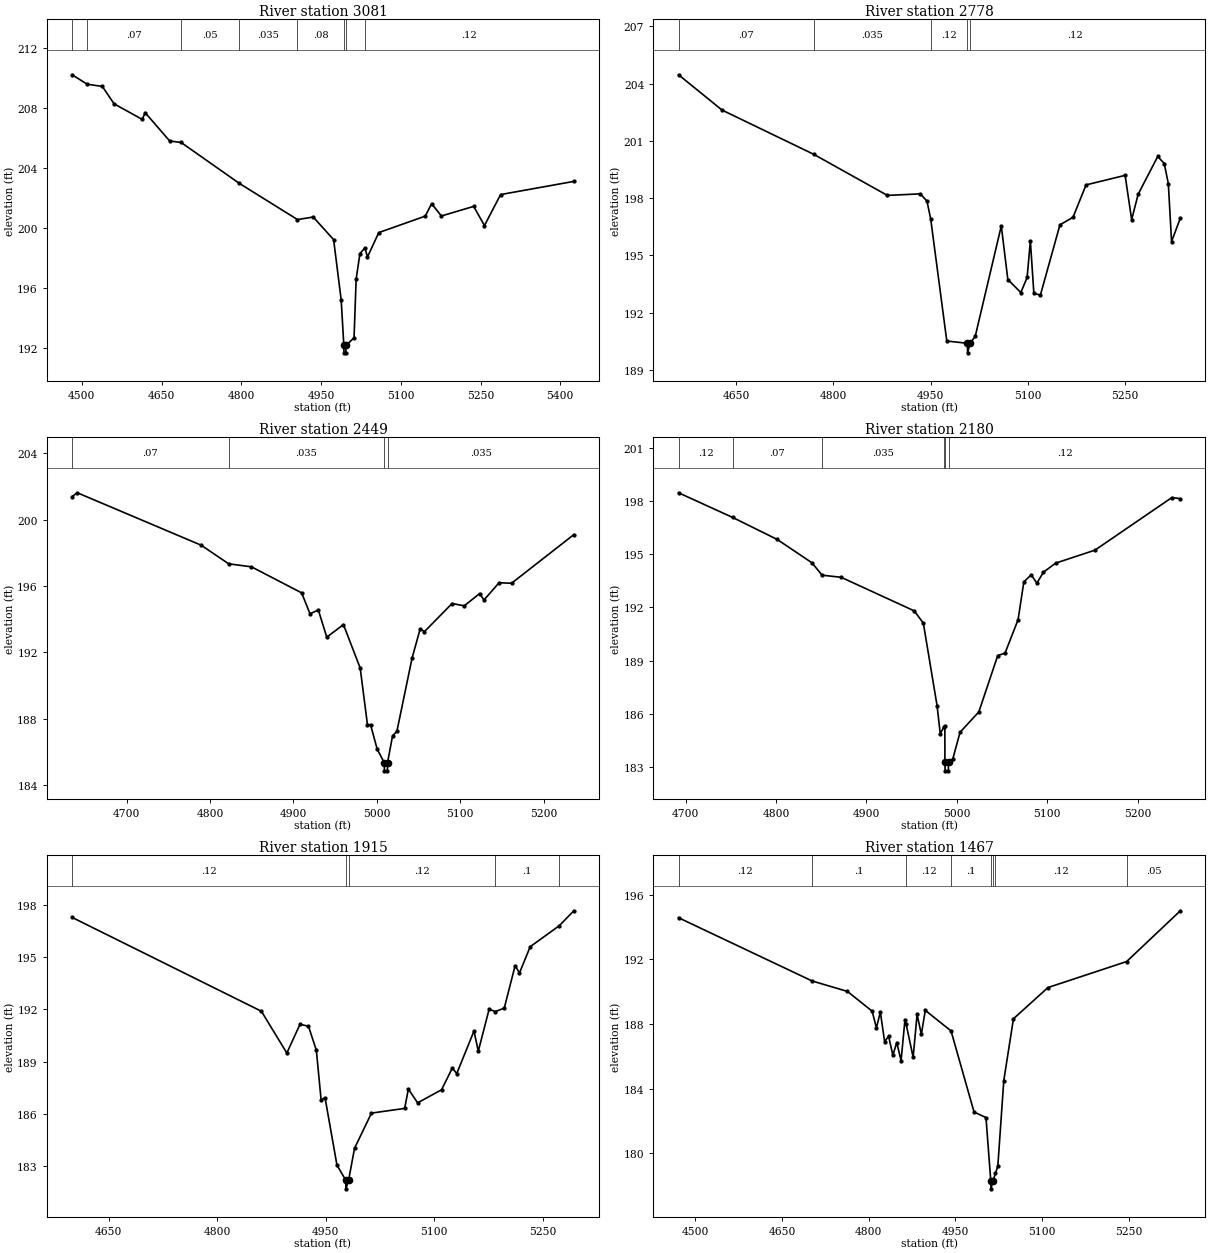
Type RM Length L Ch R = 1 ,3081    ,303,303,303
BEGIN DESCRIPTION:
Mapping XS 2c7db37f
END DESCRIPTION:
XS GIS Cut Line= 4
      2505713.13     13482736.28      2506147.13     13482538.37
      2506226.99     13482458.51      2506282.37      13482108.9
#Sta/Elev= 30
  4481.6  210.23  4510.1   209.6  4538.6  209.45  4560.6  208.29  4613.6  207.25
  4619.1   207.7  4665.2  205.81  4686.7  205.71  4796.1  202.98  4905.6  200.56
  4935.2  200.73  4973.6  199.22  4987.8   195.2  4992.8  192.16  4993.1  191.66
  4996.6  191.66  4996.8  192.16    5012  192.66    5016   196.6  5023.1  198.29
  5032.4  198.67  5037.3  198.06  5058.5  199.69    5146  200.79  5157.9  201.62
  5176.3   200.8  5237.1  201.44  5257.3  200.16  5287.7  202.23  5425.5  203.11
#Mann= 8 ,-1 , 0
  4481.6     .05       0  4510.1     .07       0  4686.7     .05       0
  4796.1    .035       0  4905.6     .08       0  4992.8    .075       0
  4996.8     .08       0  5032.4     .12       0
Bank Sta=4992.8,4996.8
XS Rating Curve= 0 ,0
Exp/Cntr=0.3,0.1

Type RM Length L Ch R = 1 ,2778    ,329,329,329
BEGIN DESCRIPTION:
Mapping XS 9962ca34
END DESCRIPTION:
XS GIS Cut Line= 3
      2505939.11     13482806.96      2506369.64     13482723.63
      2506338.39     13482390.32
#Sta/Elev= 30
  4561.5  204.46  4628.6  202.61    4770  200.29  4883.3  198.14  4934.2  198.22
  4944.4  197.84  4950.2  196.88  4974.9  190.51  5006.7  190.39  5006.9  189.89
  5010.7  190.39  5018.7  190.75  5058.9  196.54    5069  193.73    5089  193.05
  5098.7  193.84  5103.7  195.76  5109.1     193  5119.2  192.92  5149.3   196.6
  5169.4  196.99  5189.5  198.69  5249.7  199.19  5259.8  196.87  5269.8   198.2
    5300  200.18    5310  199.81  5316.3  198.76  5321.3  195.72  5334.8  196.95
#Mann= 5 ,-1 , 0
  4561.5     .07       0    4770    .035       0  4950.2     .12       0
  5006.7     .05       0  5010.7     .12       0
Bank Sta=5006.7,5010.7
XS Rating Curve= 0 ,0
Exp/Cntr=0.3,0.1

Type RM Length L Ch R = 1 ,2449    ,269,269,269
BEGIN DESCRIPTION:
Mapping XS 167a037f
END DESCRIPTION:
XS GIS Cut Line= 3
      2506060.62     13483009.74      2506417.38     13483038.39
      2506650.89     13482968.34
#Sta/Elev= 30
  4634.6  201.39  4640.9  201.62  4789.5  198.46  4822.4  197.34  4849.7  197.16
  4909.9  195.59  4919.9  194.33  4929.9  194.56    4940  192.92    4960  193.68
  4980.1  191.06  4988.8  187.65  4992.5  187.65  5000.5  186.17  5008.9  185.37
  5009.2  184.87  5012.7  184.87  5012.9  185.37  5018.9  186.98  5024.1  187.25
  5042.2  191.64    5052  193.42  5057.2  193.26  5090.3  194.95  5104.9  194.81
  5123.3  195.55  5128.5  195.16  5146.6   196.2  5161.6  196.17  5236.3   199.1
#Mann= 4 ,-1 , 0
  4634.6     .07       0  4822.4    .035       0  5008.9    .035       0
  5012.9    .035       0
Bank Sta=5008.9,5012.9
XS Rating Curve= 0 ,0
Exp/Cntr=0.3,0.1

Type RM Length L Ch R = 1 ,2180    ,265,265,265
BEGIN DESCRIPTION:
Mapping XS af945ae4
END DESCRIPTION:
XS GIS Cut Line= 3
      2506216.85     13483238.91      2506511.13     13483280.58
      2506714.27     13483121.71
#Sta/Elev= 30
  4692.2  198.45  4752.1  197.06  4801.4  195.82  4839.7  194.51    4851  193.81
  4872.1  193.69  4952.9   191.8    4963  191.11  4978.2  186.46  4981.7  184.89
    4986  185.27  4986.8  185.34  4986.9  183.29  4987.1  182.79  4990.6  182.79
  4990.9  183.29  4995.5  183.44  5003.6  184.96  5024.4  186.11  5045.3  189.28
  5053.4  189.42  5067.8   191.3  5074.2  193.43  5082.3  193.83  5088.6  193.36
  5095.9  193.98  5109.5  194.49  5152.9  195.22  5237.9  198.18  5247.3  198.12
#Mann= 6 ,-1 , 0
  4692.2     .12       0  4752.1     .07       0    4851    .035       0
    4986     .12       0  4986.9     .05       0  4990.9     .12       0
Bank Sta=4986.9,4990.9
XS Rating Curve= 0 ,0
Exp/Cntr=0.3,0.1

Type RM Length L Ch R = 1 ,1915    ,448,448,448
BEGIN DESCRIPTION:
Mapping XS ba472d1f
END DESCRIPTION:
XS GIS Cut Line= 4
      2506253.98     13483365.43      2506592.51     13483508.66
      2506701.02     13483486.96      2506878.95     13483365.44
#Sta/Elev= 30
  4599.3  197.28    4861  191.89  4896.2  189.49  4914.4  191.14  4926.1  191.03
    4937  189.65  4943.6  186.79    4949  186.93  4965.5  183.05  4977.6  182.19
  4977.9  181.69  4981.6  182.19  4989.8  184.02  5013.2  186.04  5059.1  186.31
  5064.2  187.42    5077  186.63  5110.1  187.38    5125  188.63  5131.1  188.31
  5154.9  190.75  5160.9   189.6  5175.9  192.01  5184.3  191.87  5196.8  192.07
  5211.8  194.51  5217.8  194.09  5232.7   195.6  5272.8   196.8    5293  197.66
#Mann= 5 ,-1 , 0
  4599.3     .12       0  4977.6     .05       0  4981.6     .12       0
  5184.3      .1       0  5272.8     .05       0
Bank Sta=4977.6,4981.6
XS Rating Curve= 0 ,0
Exp/Cntr=0.3,0.1

Type RM Length L Ch R = 1 ,1467    ,423,423,423
BEGIN DESCRIPTION:
Mapping XS 8cac2869
END DESCRIPTION:
XS GIS Cut Line= 4
      2506379.86     13483617.18      2506705.36      13483912.3
      2506852.93     13483877.58      2507000.27     13483643.57
#Sta/Elev= 30
  4471.2  194.57    4702  190.66  4763.3  190.01  4805.9  188.79  4813.3  187.76
  4820.1  188.74  4827.5   186.9  4834.3  187.25  4841.7  186.07  4848.5  186.85
  4855.9  185.73  4862.7  188.27  4864.8  187.97  4876.8  185.94  4883.6  188.59
    4891  187.36  4897.8  188.84  4942.3  187.57  4982.1  182.55  5002.7  182.21
    5011   178.3  5011.3   177.8    5015   178.3  5019.1  178.76  5023.2  179.21
  5033.5   184.5  5050.2  188.32  5109.8  190.25  5245.9  191.86  5338.7     195
#Mann= 8 ,-1 , 0
  4471.2     .12       0    4702      .1       0  4864.8     .12       0
  4942.3      .1       0    5011     .05       0    5015      .1       0
  5019.1     .12       0  5245.9     .05       0
Bank Sta=5011,5015
XS Rating Curve= 0 ,0
Exp/Cntr=0.3,0.1

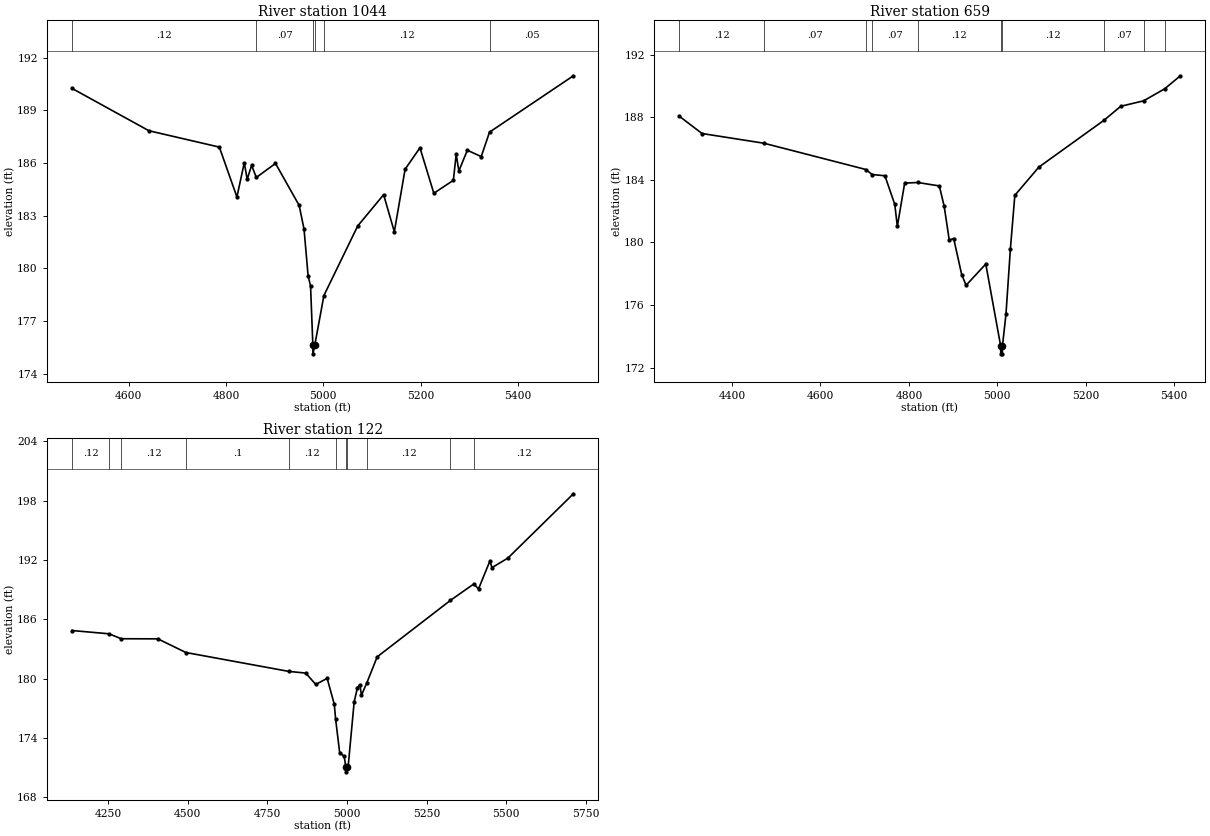
Type RM Length L Ch R = 1 ,1044    ,385,385,385
BEGIN DESCRIPTION:
Mapping XS 74720faa
END DESCRIPTION:
XS GIS Cut Line= 4
      2506514.39     13483886.27      2506766.13     13484268.21
       2506913.7     13484276.89      2507298.84     13484099.46
#Sta/Elev= 30
    4484  190.24  4641.9  187.83  4786.4   186.9  4822.5  184.06  4837.6  186.01
  4843.6  185.07  4852.7  185.86  4862.3  185.17  4901.7  185.97  4950.3  183.58
  4960.3  182.23  4968.7  179.56  4973.7  178.99  4978.4  175.63  4978.6  175.13
  4982.4  175.63  5001.1  178.45  5070.5  182.41  5123.7  184.19  5145.7  182.08
  5167.8  185.64  5198.3  186.86  5226.8  184.27  5266.9  185.01  5272.7  186.49
  5278.2  185.54  5295.6  186.72  5324.1  186.36  5341.1  187.75  5513.3  190.96
#Mann= 6 ,-1 , 0
    4484     .12       0  4862.3     .07       0  4978.4     .05       0
  4982.4     .07       0  5001.1     .12       0  5341.1     .05       0
Bank Sta=4978.4,4982.4
XS Rating Curve= 0 ,0
Exp/Cntr=0.3,0.1

Type RM Length L Ch R = 1 ,659     ,537,537,537
BEGIN DESCRIPTION:
Mapping XS d214c826
END DESCRIPTION:
XS GIS Cut Line= 4
      2506549.13     13484068.59      2506826.89     13484624.11
       2506978.8     13484615.43      2507260.26     13484390.26
#Sta/Elev= 30
  4280.2  188.08  4332.3  186.96  4472.2  186.34  4702.8  184.66  4716.9  184.34
  4745.8  184.26  4768.1  182.43  4773.9  181.03  4790.5  183.79  4820.1  183.83
  4868.9  183.61  4879.9   182.3  4891.3  180.15  4901.3  180.25  4919.4  177.95
  4929.4  177.26  4973.9  178.62  5007.6  173.38  5007.8  172.88  5011.3  172.88
  5011.6  173.38  5019.6  175.43  5029.6   179.6  5039.6  183.01  5093.8  184.81
  5241.4  187.81  5279.1   188.7  5330.9  189.05  5378.6  189.82  5413.9  190.65
#Mann= 10 ,-1 , 0
  4280.2     .12       0  4472.2     .07       0  4702.8     .12       0
  4716.9     .07       0  4820.1     .12       0  5007.6     .05       0
  5011.6     .12       0  5241.4     .07       0  5330.9     .12       0
  5378.6     .07       0
Bank Sta=5007.6,5011.6
XS Rating Curve= 0 ,0
Exp/Cntr=0.3,0.1

Type RM Length L Ch R = 1 ,122     ,0,0,0
BEGIN DESCRIPTION:
TRIB 2 TO MILBY CREEK 1.0
END DESCRIPTION:
XS GIS Cut Line= 5
      2506471.75     13484401.77      2506785.14     13484976.13
      2506972.78     13485069.08        2507138.     13485033.42
      2507534.35     13484663.18
#Sta/Elev= 30
  4136.3  184.87  4252.5  184.54  4290.8  184.04  4405.9  184.03  4493.9  182.65
  4817.2  180.74  4870.5  180.57    4902  179.42  4937.8  180.04  4960.2  177.42
  4964.5  175.89  4977.1  172.53  4991.3  172.16  4996.4  171.09  4996.7  170.59
  5000.4  171.09  5003.7  171.09  5022.7  177.67    5033   179.1  5040.6  179.37
  5045.7  178.34  5062.3  179.57    5095  182.21  5325.2  187.92  5398.7  189.58
  5413.3  189.07  5448.9  191.88  5455.8  191.23  5505.6  192.19  5711.4  198.69
#Mann= 11 ,-1 , 0
  4136.3     .12       0  4252.5     .07       0  4290.8     .12       0
  4493.9      .1       0  4817.2     .12       0  4964.5     .05       0
  4996.4     .05       0  5000.4     .05       0  5062.3     .12       0
  5325.2     .07       0  5398.7     .12       0
Bank Sta=4996.4,5000.4
XS Rating Curve= 0 ,0
Exp/Cntr=0.3,0.1

Chan Stop Cuts=-1
Use User Specified Reach Order=0
Composite Channel Slope=5