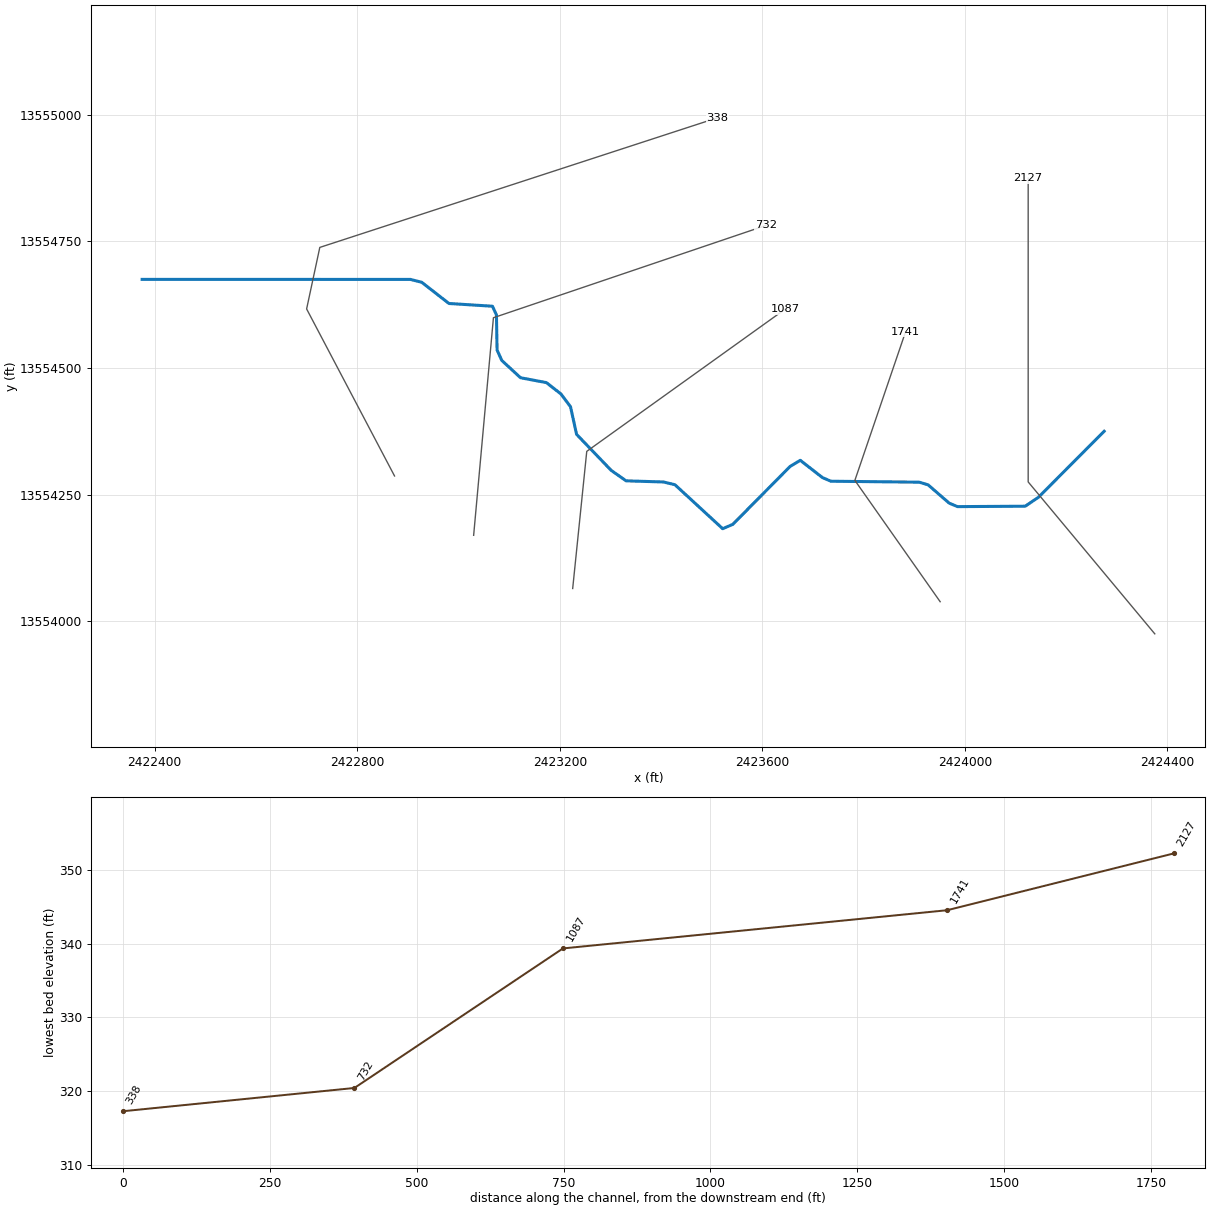
--- TRIB 2 TO SALT CREEK.prj (project) ---

Proj Title=TRIB 2 TO SALT CREEK Base Level Engineering
Current Plan=p01
Default Exp/Contr=0.3,0.1
English Units
Geom File=g01
Flow File=f01
Plan File=p01
BEGIN DESCRIPTION:
TRIB 2 TO SALT CREEK
END DESCRIPTION:

--- TRIB 2 TO SALT CREEK.p01 (plan) ---

Plan Title=Multiple Run
Short Identifier=Multiple
Geom File=g01
Flow File=f01
Subcritical Flow
K Sum by GR= 0
Std Step Tol= 0.01
Critical Tol= 0.01
Num of Std Step Trials= 20
Max Error Tol= 0.3
Flow Tol Ratio= 0.001
Split Flow NTrial= 30
Split Flow Tol= 0.02
Split Flow Ratio= 0.02
Log Output Level= 0
Friction Slope Method= 1
Unsteady Friction Slope Method= 2
Unsteady Bridges Friction Slope Method= 1
Parabolic Critical Depth
Global Vel Dist=  1 , 1 , 1
Global Log Level= 0
CheckData=True
Encroach Param= -1, 0, 0, 0
BEGIN DESCRIPTION:
Multiple Run
END DESCRIPTION:

--- TRIB 2 TO SALT CREEK.f01 (steady flow) ---

Flow Title=Multiple
Number of Profiles=7
Profile Names=10-year,25-year,50-year,1pct_min,100-year,1pct_plu,500-year
River Rch & RM= TRIB 2 TO SALT C,Reach-1,2127
     237     362     470     297     593    1183     930
Boundary for River Rch & Prof#=TRIB 2 TO SALT C,Reach-1,1
Up Type=0
Dn Type=3
Dn Slope=0.005
Boundary for River Rch & Prof#=TRIB 2 TO SALT C,Reach-1,2
Up Type=0
Dn Type=3
Dn Slope=0.005
Boundary for River Rch & Prof#=TRIB 2 TO SALT C,Reach-1,3
Up Type=0
Dn Type=3
Dn Slope=0.005
Boundary for River Rch & Prof#=TRIB 2 TO SALT C,Reach-1,4
Up Type=0
Dn Type=3
Dn Slope=0.005
Boundary for River Rch & Prof#=TRIB 2 TO SALT C,Reach-1,5
Up Type=0
Dn Type=3
Dn Slope=0.005
Boundary for River Rch & Prof#=TRIB 2 TO SALT C,Reach-1,6
Up Type=0
Dn Type=3
Dn Slope=0.005
Boundary for River Rch & Prof#=TRIB 2 TO SALT C,Reach-1,7
Up Type=0
Dn Type=3
Dn Slope=0.005

--- TRIB 2 TO SALT CREEK.g01 (geometry) ---

Geom Title=Existing Conditions

River Reach=TRIB 2 TO SALT C,Reach-1
Reach XY= 30
      2424275.00     13554375.00      2424145.17     13554244.59
      2424119.15     13554227.04      2423985.51     13554226.21
      2423968.95     13554233.14      2423927.33     13554269.25
      2423909.78     13554274.48      2423735.43     13554276.39
      2423718.81     13554283.47      2423674.90     13554317.68
      2423654.97     13554305.71      2423541.67     13554191.20
      2423521.67     13554182.60      2423427.43     13554269.45
      2423404.94     13554274.86      2423330.88     13554277.15
      2423301.43     13554297.86      2423233.16     13554368.95
      2423221.11     13554423.57      2423202.13     13554448.83
      2423173.54     13554471.10      2423122.45     13554480.75
      2423085.41     13554514.94      2423076.15     13554535.45
      2423074.87     13554604.95      2423066.99     13554621.97
      2422981.07     13554627.40      2422927.34     13554669.26
      2422904.97     13554674.93      2422375.00     13554675.00

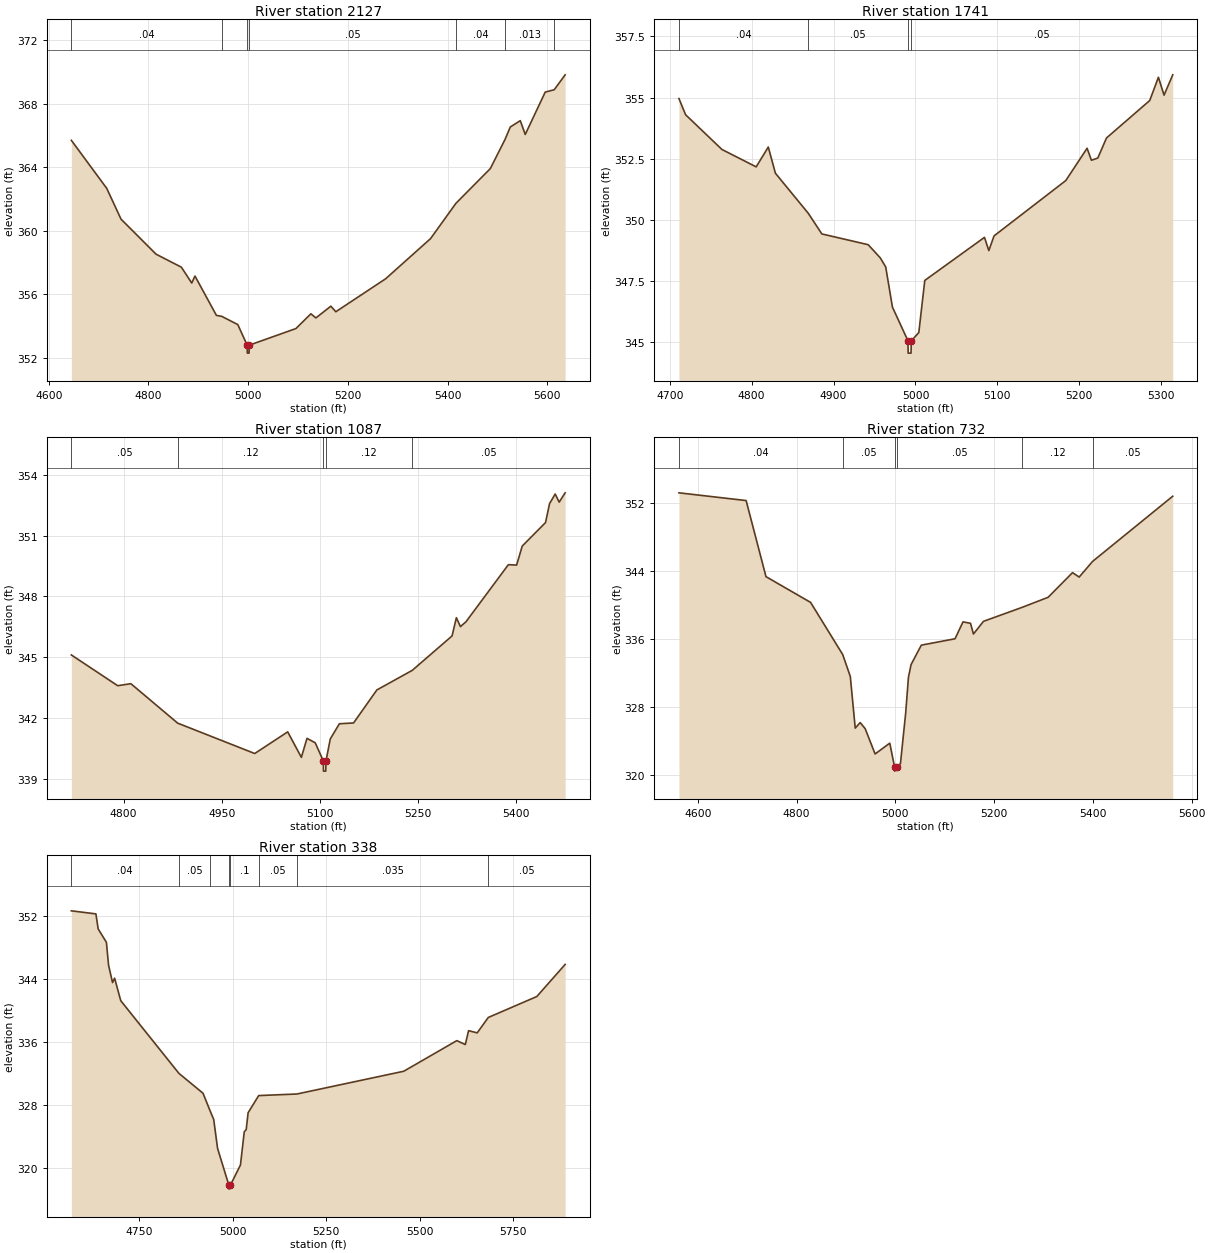
Type RM Length L Ch R = 1,2127,386,386,386
BEGIN DESCRIPTION:
TRIB 2 TO SALT CREEK 4.0
END DESCRIPTION:
XS GIS Cut Line= 3
      2424375.02     13553974.98      2424125.00     13554275.00
      2424125.00     13554874.96
#Sta/Elev= 30
  4645.4  365.70  4716.4  362.67  4745.0  360.73  4815.3  358.52  4866.1  357.70
  4886.9  356.70  4893.4  357.14  4936.4  354.66  4947.0  354.60  4979.3  354.08
  4998.1  352.78  4998.4  352.28  5001.9  352.28  5002.1  352.78  5095.9  353.83
  5125.9  354.76  5135.9  354.50  5165.9  355.24  5175.9  354.89  5275.9  356.97
  5365.9  359.50  5416.9  361.73  5485.9  363.92  5515.4  365.76  5525.9  366.54
  5545.9  366.94  5555.9  366.07  5595.9  368.74  5614.0  368.89  5635.9  369.83
#Mann=7,-1,0
  4645.4    0.04       0  4947.0    0.05       0  4998.1    0.05       0
  5002.1    0.05       0  5416.9    0.04       0  5515.4   0.013       0
  5614.0    0.04       0
Bank Sta=4998.1,5002.1
Exp/Cntr=0.3,0.1

Type RM Length L Ch R = 1,1741,654,654,654
BEGIN DESCRIPTION:
Mapping XS c852ce9a
END DESCRIPTION:
XS GIS Cut Line= 3
      2423951.17     13554038.44      2423782.74     13554278.05
      2423882.88     13554571.55
#Sta/Elev= 30
  4711.2  354.96  4719.3  354.30  4763.7  352.88  4805.5  352.17  4820.3  352.98
  4829.0  351.91  4869.2  350.27  4885.7  349.43  4942.3  348.99  4957.1  348.45
  4963.7  348.08  4971.9  346.44  4990.9  345.06  4991.1  344.56  4994.6  344.56
  4994.9  345.06  5004.1  345.40  5011.4  347.53  5084.3  349.29  5089.6  348.75
  5096.0  349.35  5183.6  351.61  5209.6  352.93  5214.9  352.44  5222.7  352.53
  5233.3  353.35  5286.1  354.88  5296.7  355.83  5303.6  355.10  5314.2  355.93
#Mann=4,-1,0
  4711.2    0.04       0  4869.2    0.05       0  4990.9    0.05       0
  4994.9    0.05       0
Bank Sta=4990.9,4994.9
Exp/Cntr=0.3,0.1

Type RM Length L Ch R = 1,1087,355,355,355
BEGIN DESCRIPTION:
Mapping XS 3bc8a3f0
END DESCRIPTION:
XS GIS Cut Line= 3
      2423225.45     13554064.49      2423253.23     13554335.35
      2423645.57     13554616.58
#Sta/Elev= 30
  4720.0  345.11  4790.9  343.59  4811.0  343.69  4882.6  341.74  5000.4  340.24
  5050.8  341.31  5071.7  340.05  5080.3  340.99  5092.9  340.77  5105.3  339.87
  5105.5  339.37  5109.0  339.37  5109.3  339.87  5115.9  340.96  5129.8  341.71
  5151.5  341.75  5187.1  343.38  5241.3  344.35  5302.1  346.05  5308.7  346.95
  5314.9  346.51  5323.4  346.75  5388.2  349.57  5400.8  349.55  5409.4  350.49
  5445.0  351.65  5451.2  352.59  5459.8  353.06  5465.9  352.66  5475.0  353.12
#Mann=5,-1,0
  4720.0    0.05       0  4882.6    0.12       0  5105.3    0.05       0
  5109.3    0.12       0  5241.3    0.05       0
Bank Sta=5105.3,5109.3
Exp/Cntr=0.3,0.1

Type RM Length L Ch R = 1,732,394,394,394
BEGIN DESCRIPTION:
Mapping XS 46178825
END DESCRIPTION:
XS GIS Cut Line= 3
      2423029.86     13554169.56      2423068.92     13554599.25
      2423607.13     13554781.54
#Sta/Elev= 30
  4562.0  353.15  4698.0  352.24  4738.2  343.29  4828.5  340.26  4893.5  334.13
  4908.9  331.55  4918.9  325.47  4928.9  326.12  4939.0  325.41  4959.1  322.43
  4988.8  323.70  4998.5  320.91  4998.7  320.41  5002.5  320.91  5010.4  321.28
  5021.0  327.23  5026.6  331.44  5031.9  332.94  5052.7  335.23  5120.9  335.98
  5137.1  337.97  5152.3  337.80  5158.2  336.54  5178.5  338.03  5257.4  339.69
  5309.4  340.86  5358.8  343.76  5372.3  343.24  5399.4  345.08  5561.7  352.75
#Mann=6,-1,0
  4562.0    0.04       0  4893.5    0.05       0  4998.5    0.05       0
  5002.5    0.05       0  5257.4    0.12       0  5399.4    0.05       0
Bank Sta=4998.5,5002.5
Exp/Cntr=0.3,0.1

Type RM Length L Ch R = 1,338,0,0,0
BEGIN DESCRIPTION:
Mapping XS 885e71d3
END DESCRIPTION:
XS GIS Cut Line= 4
      2422873.61     13554286.74      2422700.00     13554616.61
      2422726.04     13554738.14      2423510.85     13554993.96
#Sta/Elev= 30
  4567.5  352.71  4633.3  352.32  4639.3  350.41  4661.4  348.70  4667.2  345.77
  4677.8  343.57  4683.4  344.13  4699.8  341.26  4855.6  332.00  4920.1  329.47
  4938.4  327.31  4948.8  326.12  4959.1  322.44  4989.4  317.75  4989.7  317.25
  4993.4  317.75  5020.4  320.33  5030.6  324.56  5035.8  324.84  5040.9  326.98
  5069.3  329.17  5171.7  329.37  5457.8  332.27  5599.9  336.17  5622.6  335.67
  5631.4  337.44  5654.5  337.16  5684.1  339.12  5814.1  341.79  5890.0  345.88
#Mann=8,-1,0
  4567.5    0.04       0  4855.6    0.05       0  4938.4     0.1       0
  4989.4    0.05       0  4993.4     0.1       0  5069.3    0.05       0
  5171.7   0.035       0  5684.1    0.05       0
Bank Sta=4989.4,4993.4
Exp/Cntr=0.3,0.1

Chan Stop Cuts=-1