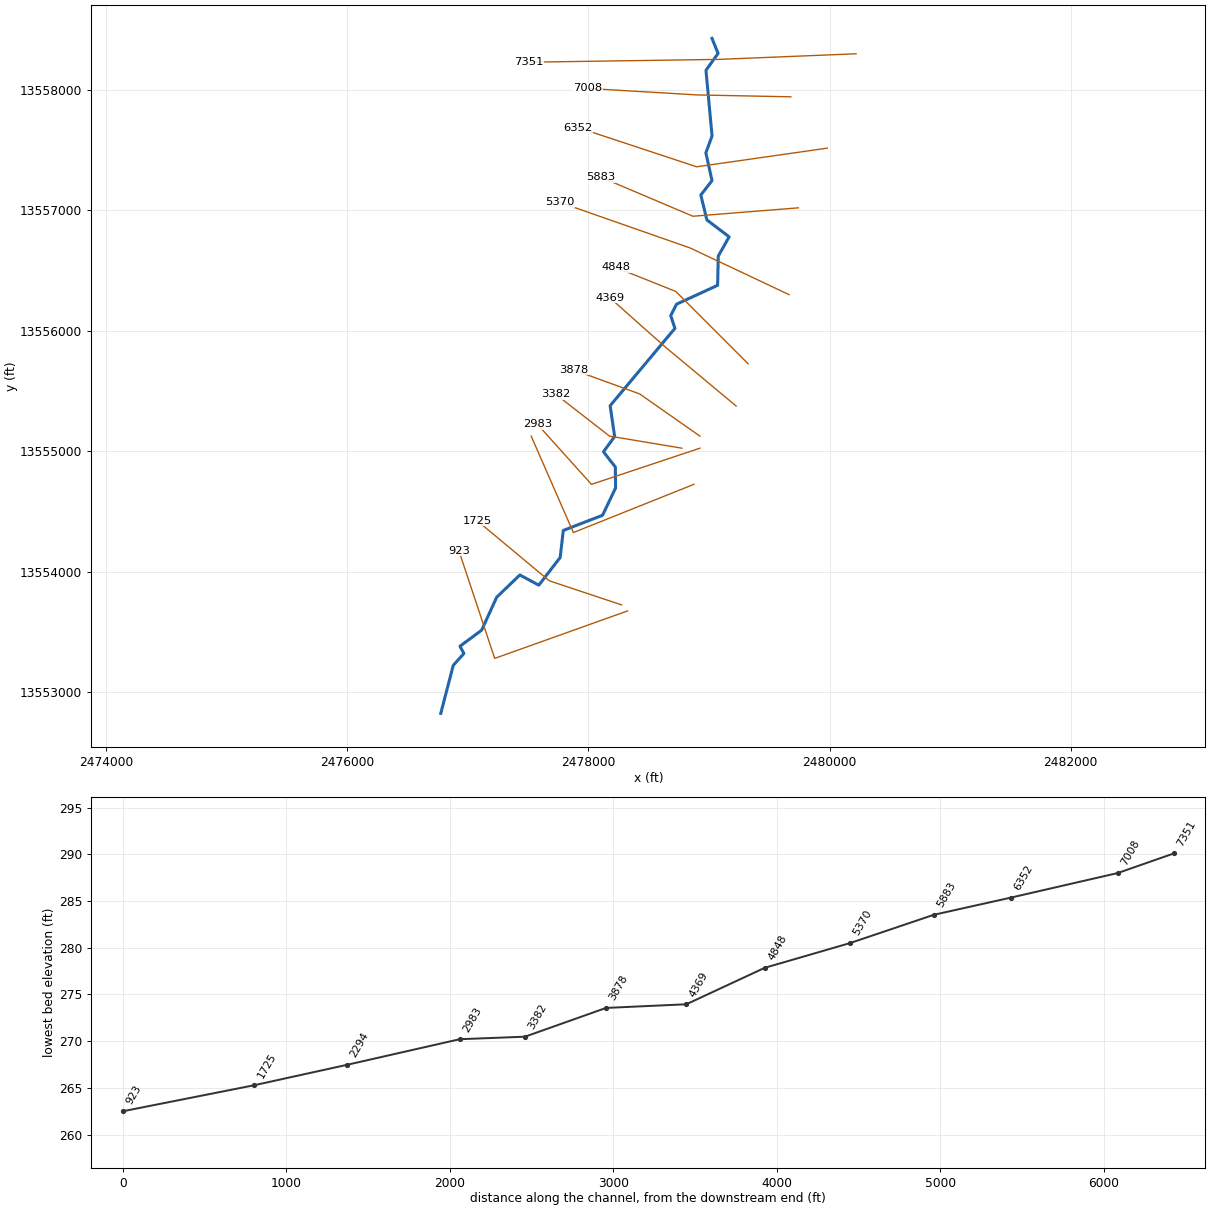
--- TRIB 2 TO SHILOH CREEK.prj (project) ---

Proj Title=TRIB 2 TO SHILOH CREEK Base Level Engineering
Current Plan=p01
Default Exp/Contr=0.3,0.1
English Units
Geom File=g01
Flow File=f01
Plan File=p01
BEGIN DESCRIPTION:
TRIB 2 TO SHILOH CREEK
END DESCRIPTION:

--- TRIB 2 TO SHILOH CREEK.p01 (plan) ---

Plan Title=Multiple Run
Short Identifier=Multiple
Geom File=g01
Flow File=f01
Subcritical Flow
K Sum by GR= 0
Std Step Tol= 0.01
Critical Tol= 0.01
Num of Std Step Trials= 20
Max Error Tol= 0.3
Flow Tol Ratio= 0.001
Split Flow NTrial= 30
Split Flow Tol= 0.02
Split Flow Ratio= 0.02
Log Output Level= 0
Friction Slope Method= 1
Unsteady Friction Slope Method= 2
Unsteady Bridges Friction Slope Method= 1
Parabolic Critical Depth
Global Vel Dist=  1 , 1 , 1
Global Log Level= 0
CheckData=True
Encroach Param= -1, 0, 0, 0
BEGIN DESCRIPTION:
Multiple Run
END DESCRIPTION:

--- TRIB 2 TO SHILOH CREEK.f01 (steady flow) ---

Flow Title=Multiple
Number of Profiles=7
Profile Names=10-year,25-year,50-year,1pct_min,100-year,1pct_plu,500-year
River Rch & RM= TRIB 2 TO SHILOH,Reach-1,7351
     436     690     915     590    1176    2347    1922
River Rch & RM= TRIB 2 TO SHILOH,Reach-1,6352
     540     863    1152     745    1487    2968    2456
River Rch & RM= TRIB 2 TO SHILOH,Reach-1,2294
     707    1146    1544    1008    2011    4012    3377
Boundary for River Rch & Prof#=TRIB 2 TO SHILOH,Reach-1,1
Up Type=0
Dn Type=3
Dn Slope=0.005
Boundary for River Rch & Prof#=TRIB 2 TO SHILOH,Reach-1,2
Up Type=0
Dn Type=3
Dn Slope=0.005
Boundary for River Rch & Prof#=TRIB 2 TO SHILOH,Reach-1,3
Up Type=0
Dn Type=3
Dn Slope=0.005
Boundary for River Rch & Prof#=TRIB 2 TO SHILOH,Reach-1,4
Up Type=0
Dn Type=3
Dn Slope=0.005
Boundary for River Rch & Prof#=TRIB 2 TO SHILOH,Reach-1,5
Up Type=0
Dn Type=3
Dn Slope=0.005
Boundary for River Rch & Prof#=TRIB 2 TO SHILOH,Reach-1,6
Up Type=0
Dn Type=3
Dn Slope=0.005
Boundary for River Rch & Prof#=TRIB 2 TO SHILOH,Reach-1,7
Up Type=0
Dn Type=3
Dn Slope=0.005

--- TRIB 2 TO SHILOH CREEK.g01 (geometry) ---

Geom Title=Existing Conditions

River Reach=TRIB 2 TO SHILOH,Reach-1
Reach XY= 30
      2479025.00     13558425.00      2479075.51     13558299.94
      2478974.96     13558159.66      2479025.50     13557614.83
      2478974.18     13557475.00      2479025.05     13557244.99
      2478932.33     13557125.10      2478982.70     13556918.53
      2479167.24     13556778.42      2479077.24     13556619.07
      2479071.57     13556376.22      2478730.56     13556219.38
      2478682.55     13556125.03      2478717.50     13556018.95
      2478180.11     13555377.29      2478217.17     13555121.60
      2478124.54     13554995.16      2478222.93     13554869.14
      2478225.04     13554694.99      2478117.14     13554468.20
      2477791.46     13554342.61      2477765.42     13554118.45
      2477588.34     13553888.41      2477431.05     13553973.42
      2477238.62     13553788.21      2477114.24     13553515.30
      2476934.19     13553381.95      2476966.98     13553321.68
      2476878.57     13553223.53      2476775.00     13552825.00

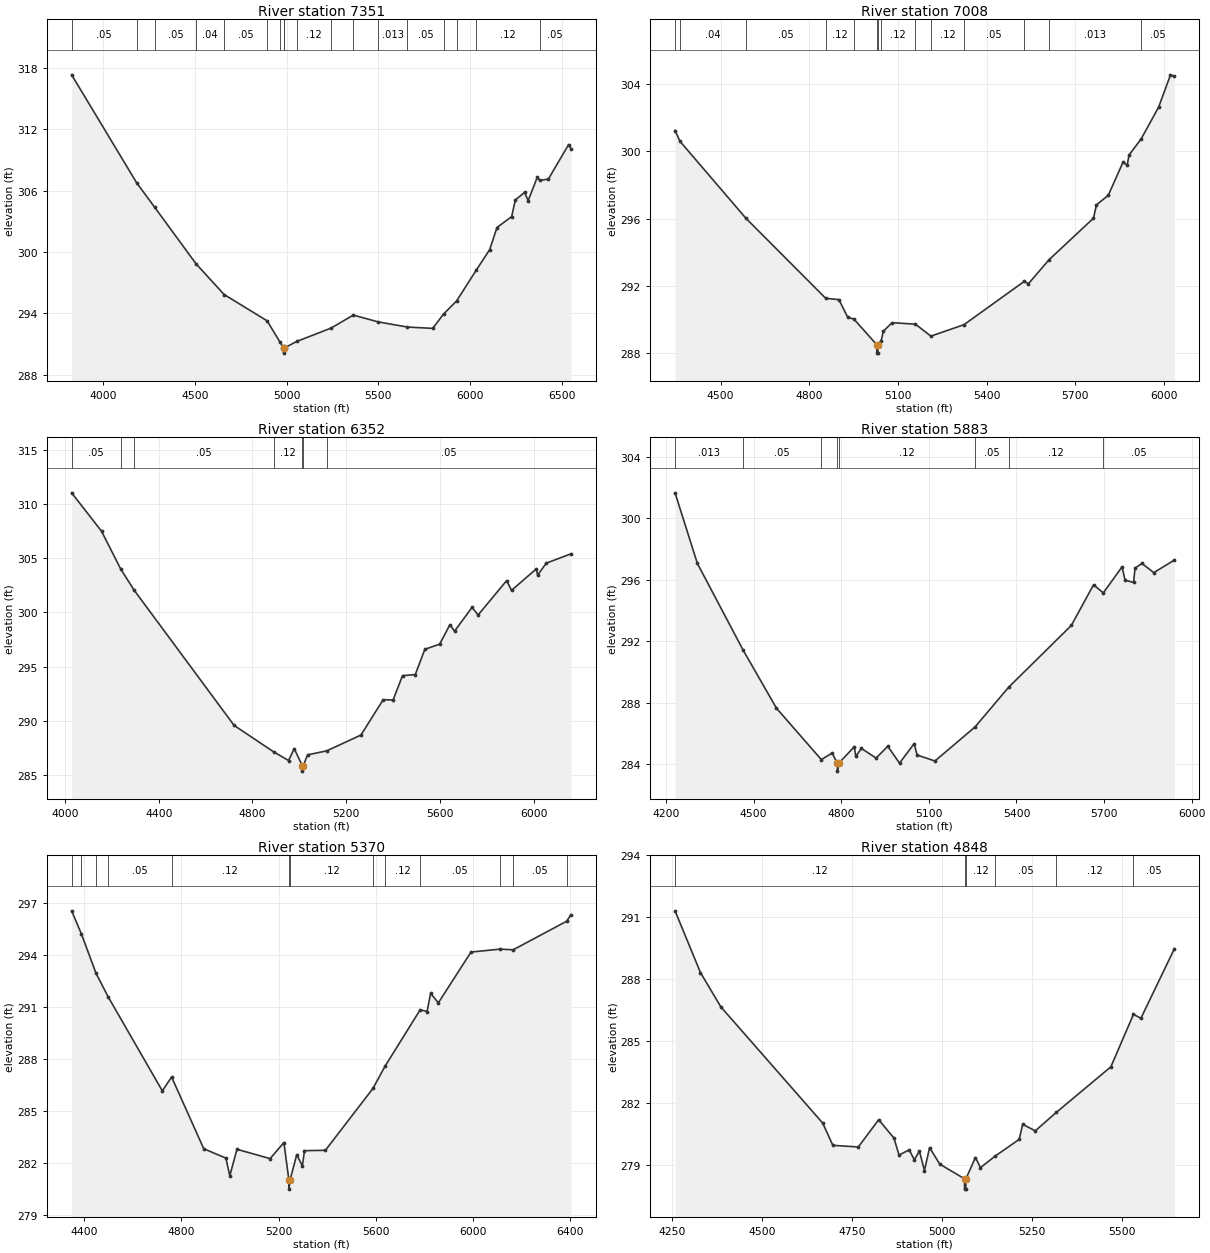
Type RM Length L Ch R = 1,7351,343,343,343
BEGIN DESCRIPTION:
TRIB 2 TO SHILOH CREEK 12.0
END DESCRIPTION:
XS GIS Cut Line= 3
      2480220.10     13558296.79      2479081.88     13558250.33
      2477502.32     13558227.10
#Sta/Elev= 30
  3829.4  317.31  4183.3  306.76  4281.6  304.36  4507.0  298.83  4659.7  295.83
  4893.9  293.26  4963.2  291.20  4983.5  290.60  4983.7  290.10  4987.5  290.60
  5054.8  291.24  5242.4  292.55  5363.1  293.82  5499.5  293.15  5658.0  292.65
  5795.5  292.52  5854.6  293.92  5925.7  295.20  6031.9  298.19  6105.6  300.21
  6145.6  302.38  6225.6  303.45  6245.6  305.08  6295.6  305.81  6315.6  305.02
  6365.6  307.32  6377.6  306.98  6425.6  307.12  6535.6  310.49  6548.3  310.08
#Mann=18,-1,0
  3829.4    0.05       0  4183.3    0.04       0  4281.6    0.05       0
  4507.0    0.04       0  4659.7    0.05       0  4893.9    0.12       0
  4963.2    0.05       0  4983.5    0.05       0  4987.5    0.05       0
  5054.8    0.12       0  5242.4    0.05       0  5363.1    0.12       0
  5499.5   0.013       0  5658.0    0.05       0  5854.6    0.12       0
  5925.7    0.05       0  6031.9    0.12       0  6377.6    0.05       0
Bank Sta=4983.5,4987.5
Exp/Cntr=0.3,0.1

Type RM Length L Ch R = 1,7008,656,656,656
BEGIN DESCRIPTION:
Mapping XS 7b15212b
END DESCRIPTION:
XS GIS Cut Line= 3
      2479679.33     13557939.87      2478905.30     13557955.35
      2477991.99     13558009.53
#Sta/Elev= 30
  4345.6  301.23  4362.3  300.59  4585.1  296.02  4855.1  291.26  4900.0  291.18
  4930.0  290.12  4950.3  290.03  5028.1  288.50  5028.3  288.00  5031.8  288.00
  5032.1  288.50  5042.9  288.73  5050.1  289.30  5080.1  289.81  5158.9  289.72
  5211.1  289.01  5323.1  289.69  5527.5  292.27  5540.9  292.12  5610.8  293.55
  5761.2  296.02  5771.2  296.81  5811.3  297.38  5861.4  299.36  5875.1  299.16
  5881.4  299.77  5922.3  300.73  5981.6  302.62  6021.7  304.54  6034.7  304.45
#Mann=14,-1,0
  4345.6    0.05       0  4362.3    0.04       0  4585.1    0.05       0
  4855.1    0.12       0  4950.3    0.05       0  5028.1    0.05       0
  5032.1    0.05       0  5042.9    0.12       0  5158.9    0.05       0
  5211.1    0.12       0  5323.1    0.05       0  5527.5    0.12       0
  5610.8   0.013       0  5922.3    0.05       0
Bank Sta=5028.1,5032.1
Exp/Cntr=0.3,0.1

Type RM Length L Ch R = 1,6352,469,469,469
BEGIN DESCRIPTION:
Mapping XS b8cf7ac6
END DESCRIPTION:
XS GIS Cut Line= 3
      2479981.17     13557514.16      2478897.56     13557359.35
      2477914.54     13557684.45
#Sta/Elev= 30
  4028.6  311.04  4156.1  307.50  4238.0  304.01  4295.1  302.06  4721.7  289.58
  4891.0  287.13  4954.1  286.34  4978.3  287.43  5012.7  285.86  5012.9  285.36
  5016.7  285.86  5034.9  286.86  5116.7  287.23  5262.8  288.69  5357.6  291.95
  5399.8  291.92  5440.2  294.17  5494.6  294.27  5535.4  296.60  5598.8  297.08
  5642.0  298.86  5662.3  298.28  5736.8  300.47  5762.7  299.77  5884.3  302.94
  5905.3  302.04  6010.7  304.02  6016.5  303.45  6053.5  304.55  6158.6  305.41
#Mann=7,-1,0
  4028.6    0.05       0  4238.0    0.04       0  4295.1    0.05       0
  4891.0    0.12       0  5012.7    0.05       0  5016.7    0.12       0
  5116.7    0.05       0
Bank Sta=5012.7,5016.7
Exp/Cntr=0.3,0.1

Type RM Length L Ch R = 1,5883,513,513,513
BEGIN DESCRIPTION:
Mapping XS fe88bf0e
END DESCRIPTION:
XS GIS Cut Line= 3
      2479741.23     13557018.78      2478866.60     13556949.12
      2478100.31     13557274.21
#Sta/Elev= 30
  4230.9  301.66  4307.4  297.06  4463.3  291.44  4578.2  287.63  4731.9  284.28
  4768.8  284.71  4786.9  284.03  4787.1  283.53  4790.9  284.03  4844.7  285.12
  4849.7  284.49  4869.1  285.01  4919.3  284.38  4959.4  285.15  4999.6  284.05
  5049.7  285.32  5059.7  284.58  5120.9  284.19  5258.4  286.41  5373.0  288.99
  5588.0  293.02  5664.0  295.67  5697.4  295.14  5761.8  296.84  5771.8  295.97
  5800.9  295.82  5806.3  296.76  5829.9  297.06  5870.4  296.46  5940.7  297.28
#Mann=8,-1,0
  4230.9   0.013       0  4463.3    0.05       0  4731.9    0.12       0
  4786.9    0.05       0  4790.9    0.12       0  5258.4    0.05       0
  5373.0    0.12       0  5697.4    0.05       0
Bank Sta=4786.9,4790.9
Exp/Cntr=0.3,0.1

Type RM Length L Ch R = 1,5370,522,522,522
BEGIN DESCRIPTION:
Mapping XS 59412912
END DESCRIPTION:
XS GIS Cut Line= 3
      2479663.82     13556298.95      2478843.38     13556685.95
      2477759.86     13557065.18
#Sta/Elev= 30
  4348.5  296.56  4388.9  295.22  4449.1  292.95  4499.1  291.59  4721.8  286.17
  4760.0  286.97  4892.3  282.83  4983.4  282.29  4999.5  281.27  5029.0  282.80
  5165.4  282.26  5222.2  283.19  5243.0  281.00  5243.2  280.50  5247.0  281.00
  5275.1  282.49  5298.2  281.84  5306.9  282.72  5393.0  282.74  5588.7  286.31
  5638.0  287.58  5783.1  290.85  5811.5  290.75  5826.0  291.80  5857.8  291.25
  5992.3  294.18  6111.8  294.35  6165.7  294.31  6386.2  295.96  6403.6  296.34
#Mann=13,-1,0
  4348.5   0.013       0  4388.9    0.12       0  4449.1   0.013       0
  4499.1    0.05       0  4760.0    0.12       0  5243.0    0.05       0
  5247.0    0.12       0  5588.7    0.05       0  5638.0    0.12       0
  5783.1    0.05       0  6111.8    0.04       0  6165.7    0.05       0
  6386.2    0.12       0
Bank Sta=5243,5247
Exp/Cntr=0.3,0.1

Type RM Length L Ch R = 1,4848,479,479,479
BEGIN DESCRIPTION:
TRIB 2 TO SHILOH CREEK 8.0
END DESCRIPTION:
XS GIS Cut Line= 3
      2479324.99     13555725.01      2478725.00     13556325.00
      2478225.03     13556524.99
#Sta/Elev= 30
  4257.7  291.32  4328.4  288.33  4385.0  286.67  4667.8  281.05  4696.1  279.97
  4766.8  279.89  4823.4  281.21  4865.8  280.32  4879.9  279.50  4908.2  279.75
  4922.4  279.27  4936.5  279.69  4950.6  278.75  4964.8  279.86  4993.1  279.06
  5061.8  278.35  5062.0  277.85  5065.5  277.85  5065.8  278.35  5092.1  279.38
  5106.2  278.89  5147.1  279.45  5213.9  280.26  5223.3  280.99  5258.3  280.67
  5316.6  281.56  5468.4  283.77  5531.2  286.31  5551.8  286.12  5644.7  289.48
#Mann=6,-1,0
  4257.7    0.12       0  5061.8    0.05       0  5065.8    0.12       0
  5147.1    0.05       0  5316.6    0.12       0  5531.2    0.05       0
Bank Sta=5061.8,5065.8
Exp/Cntr=0.3,0.1

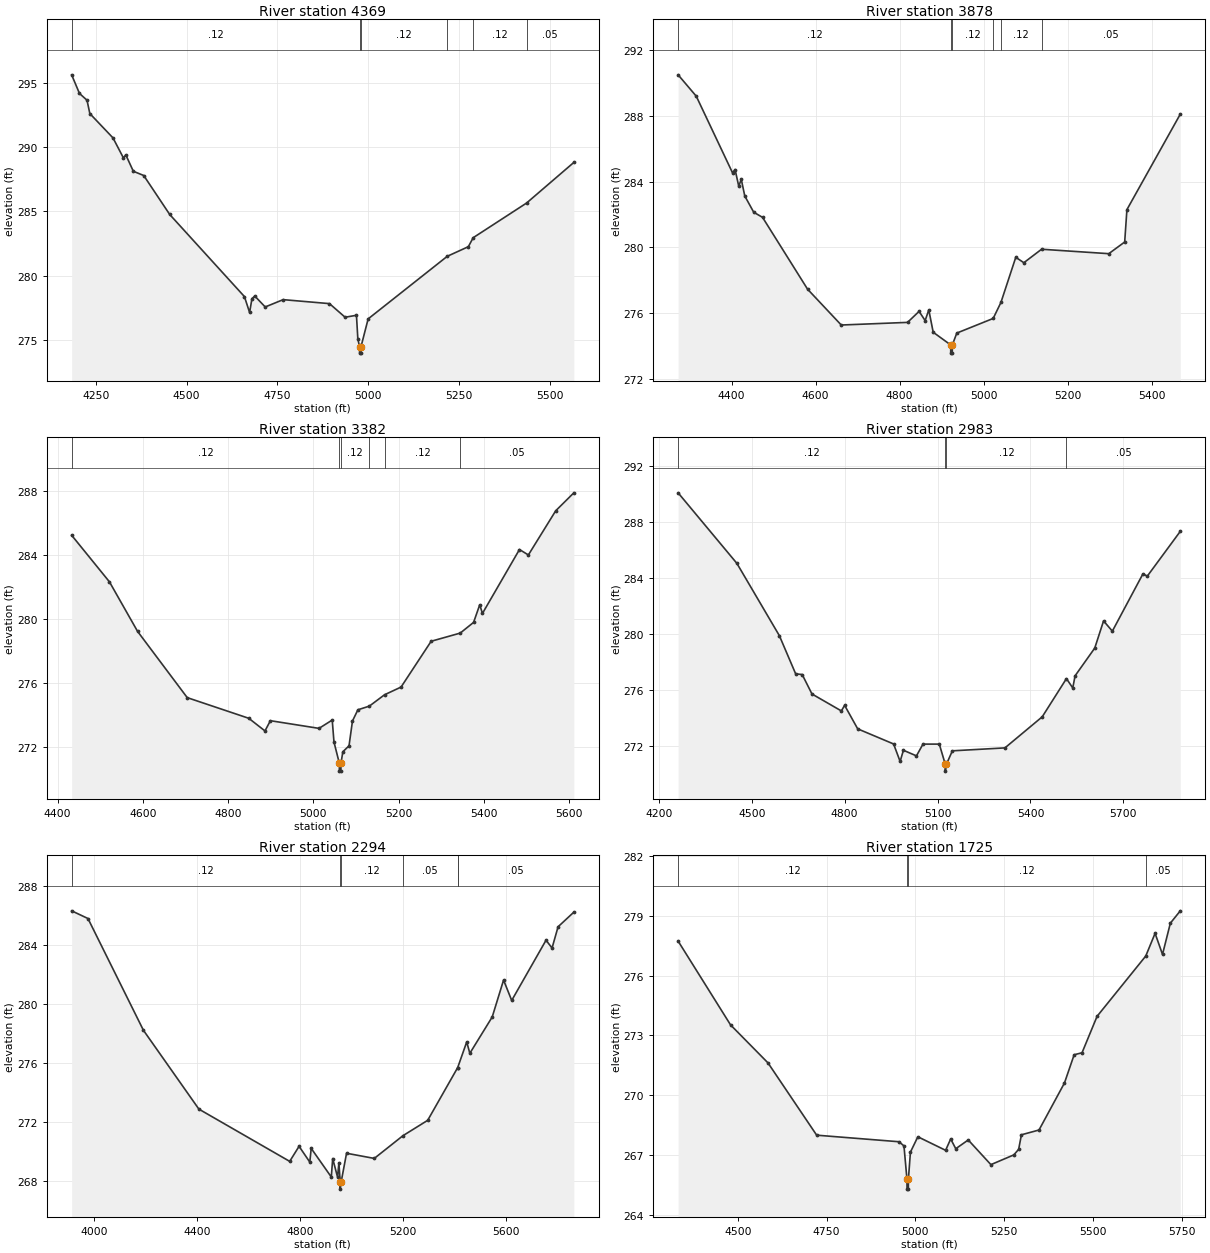
Type RM Length L Ch R = 1,4369,491,491,491
BEGIN DESCRIPTION:
TRIB 2 TO SHILOH CREEK 7.0
END DESCRIPTION:
XS GIS Cut Line= 3
      2479225.03     13555374.98      2478625.00     13555875.00
      2478175.03     13556274.98
#Sta/Elev= 30
  4183.2  295.65  4204.7  294.20  4225.5  293.67  4233.3  292.63  4297.1  290.73
  4325.8  289.17  4332.3  289.41  4353.1  288.13  4381.7  287.80  4453.3  284.76
  4659.0  278.36  4673.3  277.12  4679.8  278.20  4687.6  278.40  4716.3  277.55
  4765.7  278.12  4893.3  277.81  4936.3  276.75  4967.6  276.90  4971.4  275.07
  4976.1  274.45  4976.3  273.95  4979.8  273.95  4980.1  274.45  4999.8  276.62
  5217.7  281.50  5275.8  282.25  5289.1  282.95  5436.0  285.65  5566.3  288.82
#Mann=6,-1,0
  4183.2    0.12       0  4976.1    0.05       0  4980.1    0.12       0
  5217.7    0.05       0  5289.1    0.12       0  5436.0    0.05       0
Bank Sta=4976.1,4980.1
Exp/Cntr=0.3,0.1

Type RM Length L Ch R = 1,3878,496,496,496
BEGIN DESCRIPTION:
TRIB 2 TO SHILOH CREEK 6.0
END DESCRIPTION:
XS GIS Cut Line= 3
      2478925.00     13555125.00      2478425.00     13555475.00
      2477874.97     13555675.01
#Sta/Elev= 30
  4272.6  290.49  4315.8  289.19  4402.1  284.53  4408.2  284.73  4416.9  283.72
  4423.0  284.13  4431.3  283.12  4452.6  282.13  4473.6  281.82  4580.8  277.45
  4661.0  275.27  4818.8  275.43  4846.3  276.10  4860.7  275.54  4869.4  276.19
  4879.9  274.83  4921.5  274.06  4921.7  273.56  4925.2  273.56  4925.5  274.06
  4936.1  274.78  5022.7  275.67  5041.1  276.64  5076.5  279.39  5095.7  279.06
  5137.9  279.88  5297.9  279.61  5335.8  280.32  5341.1  282.29  5468.2  288.10
#Mann=6,-1,0
  4272.6    0.12       0  4921.5    0.05       0  4925.5    0.12       0
  5022.7    0.05       0  5041.1    0.12       0  5137.9    0.05       0
Bank Sta=4921.5,4925.5
Exp/Cntr=0.3,0.1

Type RM Length L Ch R = 1,3382,399,399,399
BEGIN DESCRIPTION:
TRIB 2 TO SHILOH CREEK 5.0
END DESCRIPTION:
XS GIS Cut Line= 3
      2478774.97     13555025.00      2478175.00     13555125.00
      2477725.03     13555474.98
#Sta/Elev= 30
  4433.1  285.21  4521.8  282.30  4587.7  279.21  4704.3  275.07  4848.7  273.78
  4886.7  272.99  4899.4  273.63  5013.5  273.15  5044.5  273.67  5048.6  272.30
  5061.1  270.98  5061.3  270.48  5064.8  270.48  5065.1  270.98  5069.4  271.69
  5083.9  272.06  5092.0  273.61  5104.7  274.31  5131.6  274.54  5167.3  275.25
  5206.0  275.73  5276.6  278.59  5344.8  279.10  5376.2  279.77  5390.6  280.87
  5397.0  280.33  5483.8  284.32  5504.7  283.98  5568.9  286.74  5611.4  287.86
#Mann=6,-1,0
  4433.1    0.12       0  5061.1    0.05       0  5065.1    0.12       0
  5131.6    0.05       0  5167.3    0.12       0  5344.8    0.05       0
Bank Sta=5061.1,5065.1
Exp/Cntr=0.3,0.1

Type RM Length L Ch R = 1,2983,689,689,689
BEGIN DESCRIPTION:
TRIB 2 TO SHILOH CREEK 4.0
END DESCRIPTION:
XS GIS Cut Line= 3
      2478925.04     13555025.01      2478025.00     13554725.00
      2477575.01     13555224.99
#Sta/Elev= 30
  4262.3  290.09  4452.1  285.05  4589.1  279.89  4641.8  277.16  4662.9  277.11
  4694.5  275.72  4789.4  274.51  4799.9  274.91  4842.1  273.23  4958.0  272.15
  4979.1  270.90  4989.7  271.70  5031.8  271.30  5052.9  272.14  5105.6  272.14
  5124.7  270.71  5125.0  270.21  5128.7  270.71  5147.8  271.66  5317.5  271.87
  5437.9  274.09  5516.1  276.82  5536.5  276.15  5544.0  277.02  5607.5  279.00
  5635.9  280.94  5664.3  280.21  5763.0  284.30  5777.2  284.14  5883.7  287.34
#Mann=4,-1,0
  4262.3    0.12       0  5124.7    0.05       0  5128.7    0.12       0
  5516.1    0.05       0
Bank Sta=5124.7,5128.7
Exp/Cntr=0.3,0.1

Type RM Length L Ch R = 1,2294,569,569,569
BEGIN DESCRIPTION:
TRIB 2 TO SHILOH CREEK 3.0
END DESCRIPTION:
XS GIS Cut Line= 3
      2478875.02     13554725.01      2477875.00     13554325.00
      2477524.99     13555125.03
#Sta/Elev= 30
  3913.9  286.32  3977.2  285.80  4192.6  278.23  4408.0  272.89  4760.7  269.35
  4797.1  270.37  4838.8  269.30  4844.2  270.23  4922.3  268.29  4927.7  269.54
  4946.5  268.29  4951.9  269.26  4956.6  267.97  4956.9  267.47  4960.7  267.97
  4981.5  269.90  5089.2  269.55  5200.6  271.09  5296.6  272.13  5412.7  275.69
  5413.1  275.70  5448.2  277.44  5460.3  276.67  5547.2  279.13  5591.3  281.63
  5622.9  280.25  5756.2  284.33  5779.6  283.80  5803.0  285.24  5864.2  286.23
#Mann=6,-1,0
  3913.9    0.12       0  4956.6    0.05       0  4960.7    0.12       0
  5200.6    0.05       0  5412.7    0.12       0  5413.1    0.05       0
Bank Sta=4956.6,4960.7
Exp/Cntr=0.3,0.1

Type RM Length L Ch R = 1,1725,802,802,802
BEGIN DESCRIPTION:
TRIB 2 TO SHILOH CREEK 2.0
END DESCRIPTION:
XS GIS Cut Line= 3
      2478274.99     13553725.00      2477675.00     13553925.00
      2477074.98     13554425.02
#Sta/Elev= 30
  4332.2  277.74  4479.8  273.53  4585.2  271.62  4722.2  267.99  4954.1  267.66
  4967.9  267.45  4976.3  265.78  4976.6  265.28  4980.1  265.28  4980.4  265.78
  4986.1  267.14  5007.0  267.91  5085.1  267.23  5099.4  267.80  5113.7  267.31
  5148.8  267.75  5212.6  266.51  5277.1  267.00  5290.7  267.28  5298.5  268.01
  5348.0  268.25  5419.6  270.61  5446.9  272.03  5469.1  272.13  5511.4  273.96
  5648.5  276.99  5674.7  278.13  5695.6  277.07  5717.7  278.64  5745.7  279.26
#Mann=4,-1,0
  4332.2    0.12       0  4976.3    0.05       0  4980.4    0.12       0
  5648.5    0.05       0
Bank Sta=4976.3,4980.4
Exp/Cntr=0.3,0.1

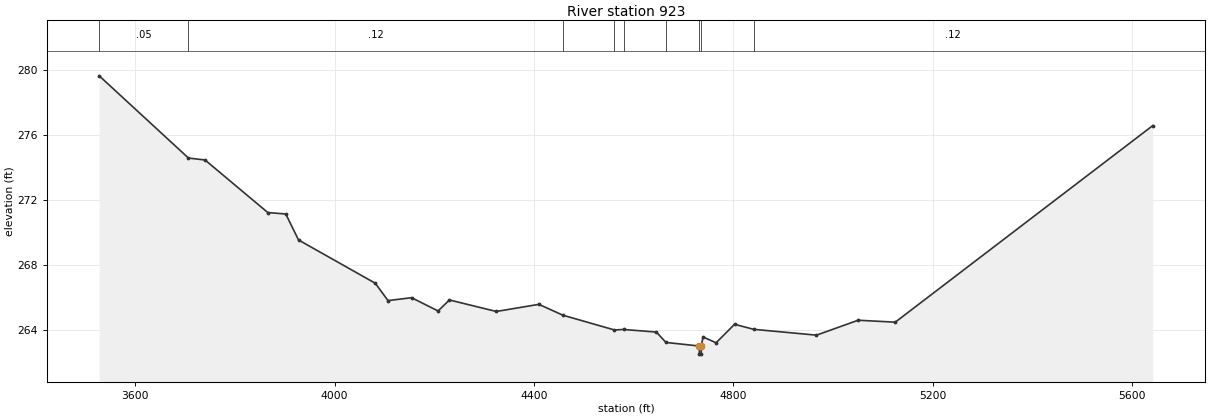
Type RM Length L Ch R = 1,923,0,0,0
BEGIN DESCRIPTION:
TRIB 2 TO SHILOH CREEK 1.0
END DESCRIPTION:
XS GIS Cut Line= 3
      2478324.96     13553674.99      2477222.29     13553281.12
      2476925.01     13554174.98
#Sta/Elev= 30
  3528.0  279.66  3707.0  274.59  3740.3  274.47  3866.1  271.23  3902.2  271.14
  3927.7  269.54  4081.7  266.87  4107.2  265.80  4154.5  265.98  4207.6  265.16
  4230.3  265.84  4324.4  265.13  4409.8  265.57  4457.9  264.90  4561.3  263.99
  4579.5  264.02  4645.5  263.86  4664.6  263.22  4731.5  263.00  4731.8  262.50
  4735.4  262.50  4735.6  263.00  4738.9  263.56  4765.2  263.20  4802.2  264.34
  4840.4  264.03  4966.5  263.67  5050.1  264.59  5124.5  264.47  5640.9  276.59
#Mann=9,-1,0
  3528.0    0.05       0  3707.0    0.12       0  4457.9    0.05       0
  4561.3     0.1       0  4579.5    0.05       0  4664.6     0.1       0
  4731.5    0.05       0  4735.6     0.1       0  4840.4    0.12       0
Bank Sta=4731.5,4735.6
Exp/Cntr=0.3,0.1

Chan Stop Cuts=-1