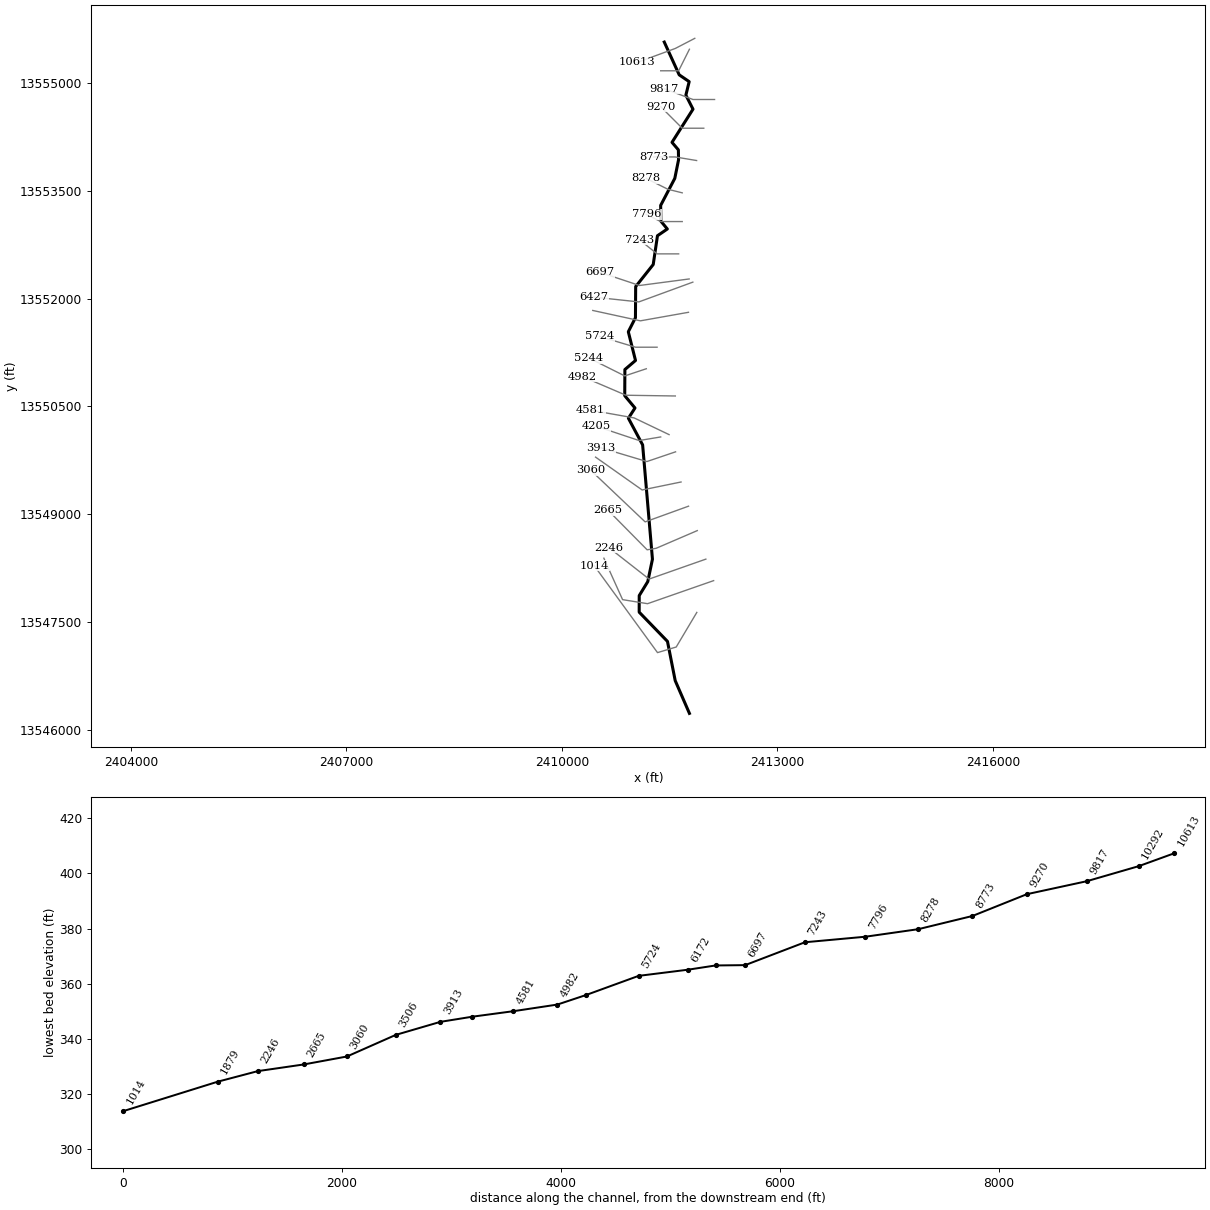
--- TRIB 2 TO THOMAS CREEK.prj (project) ---

Proj Title=TRIB 2 TO THOMAS CREEK Base Level Engineering
Current Plan=p01
Default Exp/Contr=0.3,0.1
English Units
Geom File=g01
Flow File=f01
Plan File=p01
BEGIN DESCRIPTION:
TRIB 2 TO THOMAS CREEK
END DESCRIPTION:

--- TRIB 2 TO THOMAS CREEK.p01 (plan) ---

Plan Title=Multiple Run
Short Identifier=Multiple
Geom File=g01
Flow File=f01
Subcritical Flow
K Sum by GR= 0
Std Step Tol= 0.01
Critical Tol= 0.01
Num of Std Step Trials= 20
Max Error Tol= 0.3
Flow Tol Ratio= 0.001
Split Flow NTrial= 30
Split Flow Tol= 0.02
Split Flow Ratio= 0.02
Log Output Level= 0
Friction Slope Method= 1
Unsteady Friction Slope Method= 2
Unsteady Bridges Friction Slope Method= 1
Parabolic Critical Depth
Global Vel Dist=  1 , 1 , 1
Global Log Level= 0
CheckData=True
Encroach Param= -1, 0, 0, 0
BEGIN DESCRIPTION:
Multiple Run
END DESCRIPTION:

--- TRIB 2 TO THOMAS CREEK.f01 (steady flow) ---

Flow Title=Multiple
Number of Profiles=7
Profile Names=10-year,25-year,50-year,1pct_min,100-year,1pct_plu,500-year
River Rch & RM= TRIB 2 TO THOMAS,Reach-1,10613
     435     694     925     599    1195    2384    1973
River Rch & RM= TRIB 2 TO THOMAS,Reach-1,5724
     665    1086    1469     963    1921    3833    3251
Boundary for River Rch & Prof#=TRIB 2 TO THOMAS,Reach-1,1
Up Type=0
Dn Type=3
Dn Slope=0.005
Boundary for River Rch & Prof#=TRIB 2 TO THOMAS,Reach-1,2
Up Type=0
Dn Type=3
Dn Slope=0.005
Boundary for River Rch & Prof#=TRIB 2 TO THOMAS,Reach-1,3
Up Type=0
Dn Type=3
Dn Slope=0.005
Boundary for River Rch & Prof#=TRIB 2 TO THOMAS,Reach-1,4
Up Type=0
Dn Type=3
Dn Slope=0.005
Boundary for River Rch & Prof#=TRIB 2 TO THOMAS,Reach-1,5
Up Type=0
Dn Type=3
Dn Slope=0.005
Boundary for River Rch & Prof#=TRIB 2 TO THOMAS,Reach-1,6
Up Type=0
Dn Type=3
Dn Slope=0.005
Boundary for River Rch & Prof#=TRIB 2 TO THOMAS,Reach-1,7
Up Type=0
Dn Type=3
Dn Slope=0.005

--- TRIB 2 TO THOMAS CREEK.g01 (geometry) ---

Geom Title=Existing Conditions

River Reach=TRIB 2 TO THOMAS,Reach-1
Reach XY= 30
      2411425.00     13555575.00      2411632.75     13555118.55
      2411771.63     13555023.72      2411725.61     13554835.62
      2411824.76     13554640.22      2411532.61     13554178.33
      2411621.45     13554073.53      2411623.79     13553935.51
      2411571.45     13553676.47      2411374.79     13553300.09
      2411377.08     13553080.85      2411467.50     13552971.42
      2411330.36     13552877.70      2411271.24     13552476.56
      2411026.97     13552169.11      2411023.80     13551735.50
      2410924.52     13551540.16      2411024.62     13551140.15
      2410876.85     13551013.86      2410874.70     13550649.88
      2411017.40     13550478.34      2410925.70     13550335.70
      2411123.80     13549964.50      2411260.43     13548372.21
      2411195.40     13548060.05      2411076.44     13547865.36
      2411075.80     13547634.79      2411469.54     13547227.45
      2411577.25     13546680.93      2411775.00     13546225.00

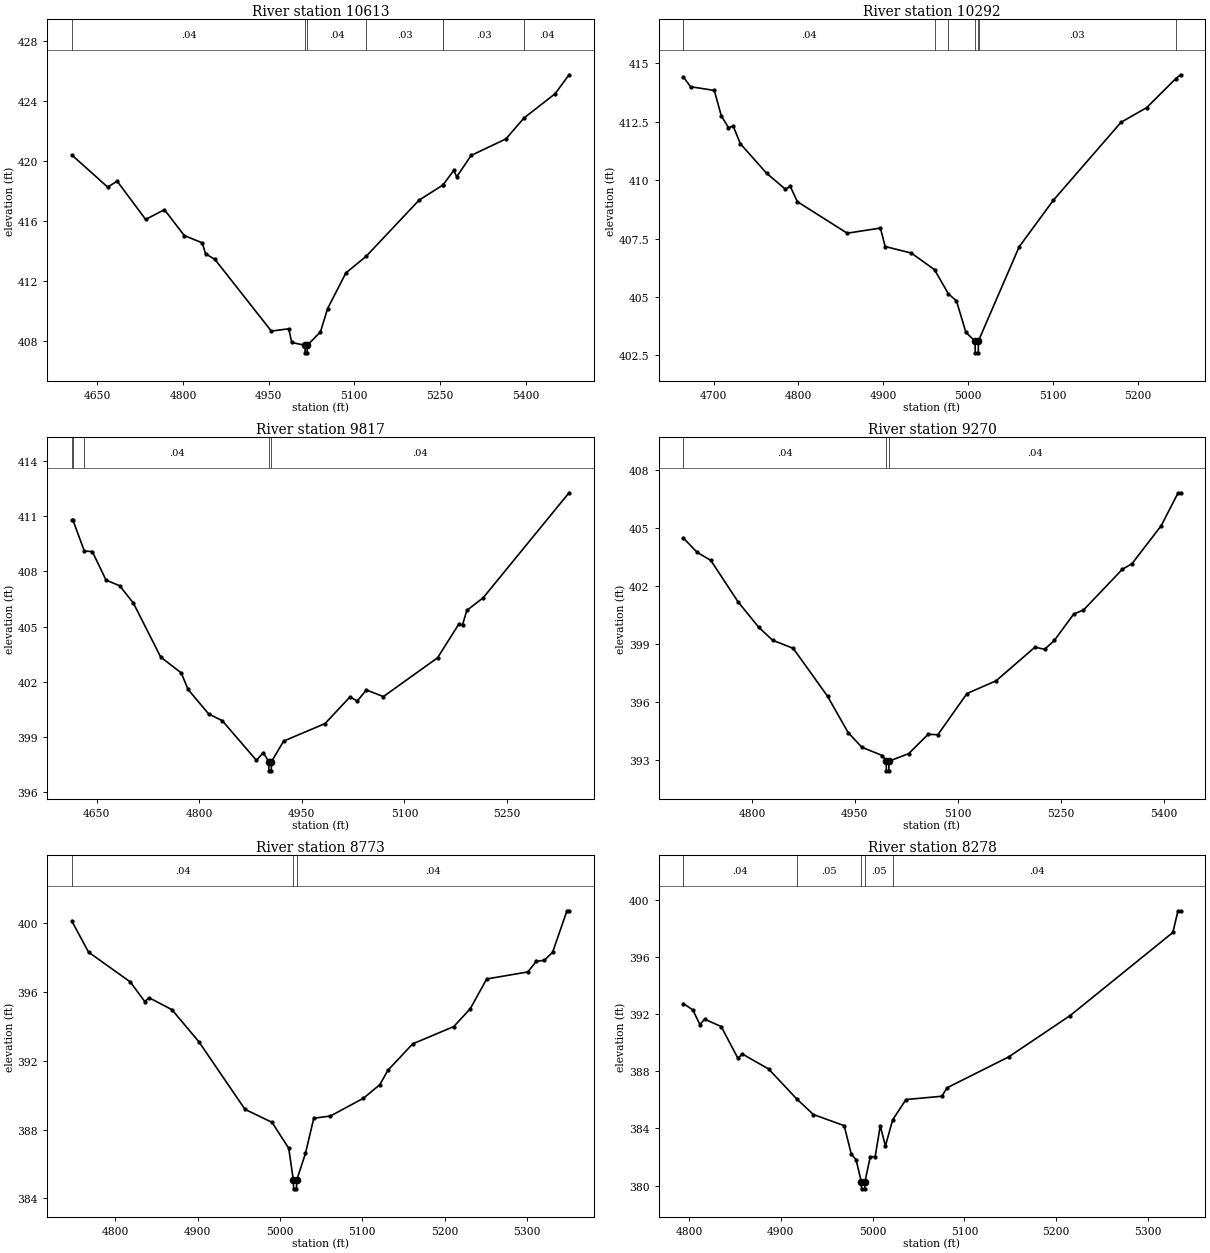
Type RM Length L Ch R = 1,10613,321,321,321
BEGIN DESCRIPTION:
TRIB 2 TO THOMAS CREEK 19.0
END DESCRIPTION:
XS GIS Cut Line= 3
      2411849.63     13555626.93      2411578.34     13555485.86
      2411048.35     13555291.17
#Sta/Elev= 30
  4605.6  420.40  4668.4  418.26  4684.9  418.66  4734.8  416.11  4767.7  416.76
  4802.4  415.04  4834.0  414.55  4839.6  413.83  4856.1  413.45  4954.8  408.68
  4985.3  408.83  4990.6  407.92  5013.8  407.73  5014.0  407.23  5017.5  407.23
  5017.8  407.73  5040.9  408.63  5053.4  410.18  5085.4  412.55  5120.7  413.65
  5213.1  417.38  5255.5  418.41  5255.7  418.42  5274.1  419.37  5279.4  418.95
  5304.6  420.37  5365.5  421.47  5397.1  422.86  5451.7  424.48  5476.0  425.74
#Mann=7,-1,0
  4605.6    0.04       0  5013.8    0.04       0  5017.8    0.04       0
  5120.7    0.03       0  5255.5    0.04       0  5255.7    0.03       0
  5397.1    0.04       0
Bank Sta=5013.8,5017.8
Exp/Cntr=0.3,0.1

Type RM Length L Ch R = 1,10292,475,475,475
BEGIN DESCRIPTION:
TRIB 2 TO THOMAS CREEK 18.0
END DESCRIPTION:
XS GIS Cut Line= 3
      2411775.01     13555475.03      2411625.00     13555175.00
      2411375.04     13555175.00
#Sta/Elev= 30
  4664.5  414.42  4672.9  414.00  4700.9  413.84  4709.2  412.75  4717.6  412.25
  4723.2  412.31  4731.6  411.56  4762.4  410.30  4784.7  409.61  4790.3  409.74
  4798.7  409.08  4857.4  407.73  4896.5  407.95  4902.1  407.16  4932.9  406.88
  4960.2  406.17  4976.6  405.13  4986.0  404.84  4997.1  403.49  5007.9  403.11
  5008.2  402.61  5011.7  402.61  5011.9  403.11  5012.4  403.16  5059.9  407.15
  5099.9  409.13  5179.9  412.48  5209.9  413.10  5244.4  414.35  5249.9  414.51
#Mann=7,-1,0
  4664.5    0.04       0  4960.2    0.03       0  4976.6    0.04       0
  5007.9    0.04       0  5011.9    0.04       0  5012.4    0.03       0
  5244.4    0.04       0
Bank Sta=5007.9,5011.9
Exp/Cntr=0.3,0.1

Type RM Length L Ch R = 1,9817,547,547,547
BEGIN DESCRIPTION:
TRIB 2 TO THOMAS CREEK 17.0
END DESCRIPTION:
XS GIS Cut Line= 3
      2412124.97     13554775.00      2411825.00     13554775.00
      2411424.97     13554925.01
#Sta/Elev= 30
  4613.6  410.79  4615.2  410.79  4631.9  409.11  4643.6  409.08  4663.6  407.53
  4683.6  407.22  4703.6  406.28  4743.6  403.34  4773.6  402.48  4783.6  401.58
  4813.6  400.25  4833.6  399.88  4883.6  397.72  4893.6  398.14  4901.6  397.65
  4901.8  397.15  4905.3  397.15  4905.6  397.65  4923.4  398.77  4983.9  399.72
  5020.4  401.17  5031.1  400.95  5044.4  401.55  5069.3  401.19  5148.5  403.30
  5179.7  405.14  5185.0  405.09  5191.3  405.88  5215.3  406.57  5340.8  412.28
#Mann=5,-1,0
  4613.6    0.04       0  4615.2    0.05       0  4631.9    0.04       0
  4901.6    0.04       0  4905.6    0.04       0
Bank Sta=4901.6,4905.6
Exp/Cntr=0.3,0.1

Type RM Length L Ch R = 1,9270,497,497,497
BEGIN DESCRIPTION:
TRIB 2 TO THOMAS CREEK 16.0
END DESCRIPTION:
XS GIS Cut Line= 3
      2411974.96     13554375.00      2411675.00     13554375.00
      2411375.02     13554674.98
#Sta/Elev= 30
  4700.2  404.50  4720.2  403.76  4740.2  403.34  4780.2  401.18  4810.2  399.87
  4830.2  399.21  4860.2  398.79  4910.2  396.31  4940.2  394.43  4960.2  393.67
  4990.2  393.24  4995.7  392.95  4995.9  392.45  4999.4  392.45  4999.7  392.95
  5028.4  393.34  5056.7  394.34  5070.9  394.32  5113.3  396.45  5155.7  397.11
  5212.3  398.85  5226.4  398.74  5240.6  399.20  5268.9  400.57  5283.0  400.77
  5339.6  402.88  5353.7  403.17  5396.1  405.13  5420.9  406.84  5424.4  406.84
#Mann=3,-1,0
  4700.2    0.04       0  4995.7    0.04       0  4999.7    0.04       0
Bank Sta=4995.7,4999.7
Exp/Cntr=0.3,0.1

Type RM Length L Ch R = 1,8773,495,495,495
BEGIN DESCRIPTION:
TRIB 2 TO THOMAS CREEK 15.0
END DESCRIPTION:
XS GIS Cut Line= 3
      2411875.02     13553925.00      2411575.00     13553975.00
      2411274.96     13553975.00
#Sta/Elev= 30
  4747.0  400.14  4767.3  398.33  4818.0  396.60  4835.7  395.45  4840.8  395.68
  4868.7  394.98  4901.6  393.10  4957.4  389.18  4990.3  388.42  5010.6  386.91
  5016.2  385.05  5016.5  384.55  5020.0  384.55  5020.2  385.05  5030.9  386.61
  5041.0  388.66  5061.2  388.79  5101.2  389.82  5121.2  390.61  5131.2  391.46
  5161.2  392.99  5211.2  394.00  5231.2  395.04  5251.2  396.77  5301.2  397.18
  5311.2  397.79  5321.2  397.86  5331.2  398.32  5348.7  400.74  5351.2  400.74
#Mann=3,-1,0
  4747.0    0.04       0  5016.2    0.04       0  5020.2    0.04       0
Bank Sta=5016.2,5020.2
Exp/Cntr=0.3,0.1

Type RM Length L Ch R = 1,8278,482,482,482
BEGIN DESCRIPTION:
TRIB 2 TO THOMAS CREEK 14.0
END DESCRIPTION:
XS GIS Cut Line= 3
      2411674.99     13553475.00      2411475.00     13553525.00
      2411174.96     13553675.02
#Sta/Elev= 30
  4793.8  392.74  4804.1  392.29  4811.8  391.27  4817.0  391.64  4835.0  391.13
  4853.1  388.92  4858.2  389.20  4886.6  388.16  4917.8  386.03  4935.5  384.97
  4969.0  384.19  4976.8  382.18  4981.9  381.82  4987.6  380.27  4987.9  379.77
  4991.4  379.77  4991.6  380.27  4997.4  382.02  5002.7  382.02  5008.3  384.18
  5013.9  382.77  5021.8  384.60  5036.3  386.02  5075.4  386.25  5081.0  386.84
  5148.1  389.00  5215.2  391.90  5327.0  397.71  5332.6  399.23  5335.4  399.23
#Mann=5,-1,0
  4793.8    0.04       0  4917.8    0.05       0  4987.6    0.05       0
  4991.6    0.05       0  5021.8    0.04       0
Bank Sta=4987.6,4991.6
Exp/Cntr=0.3,0.1

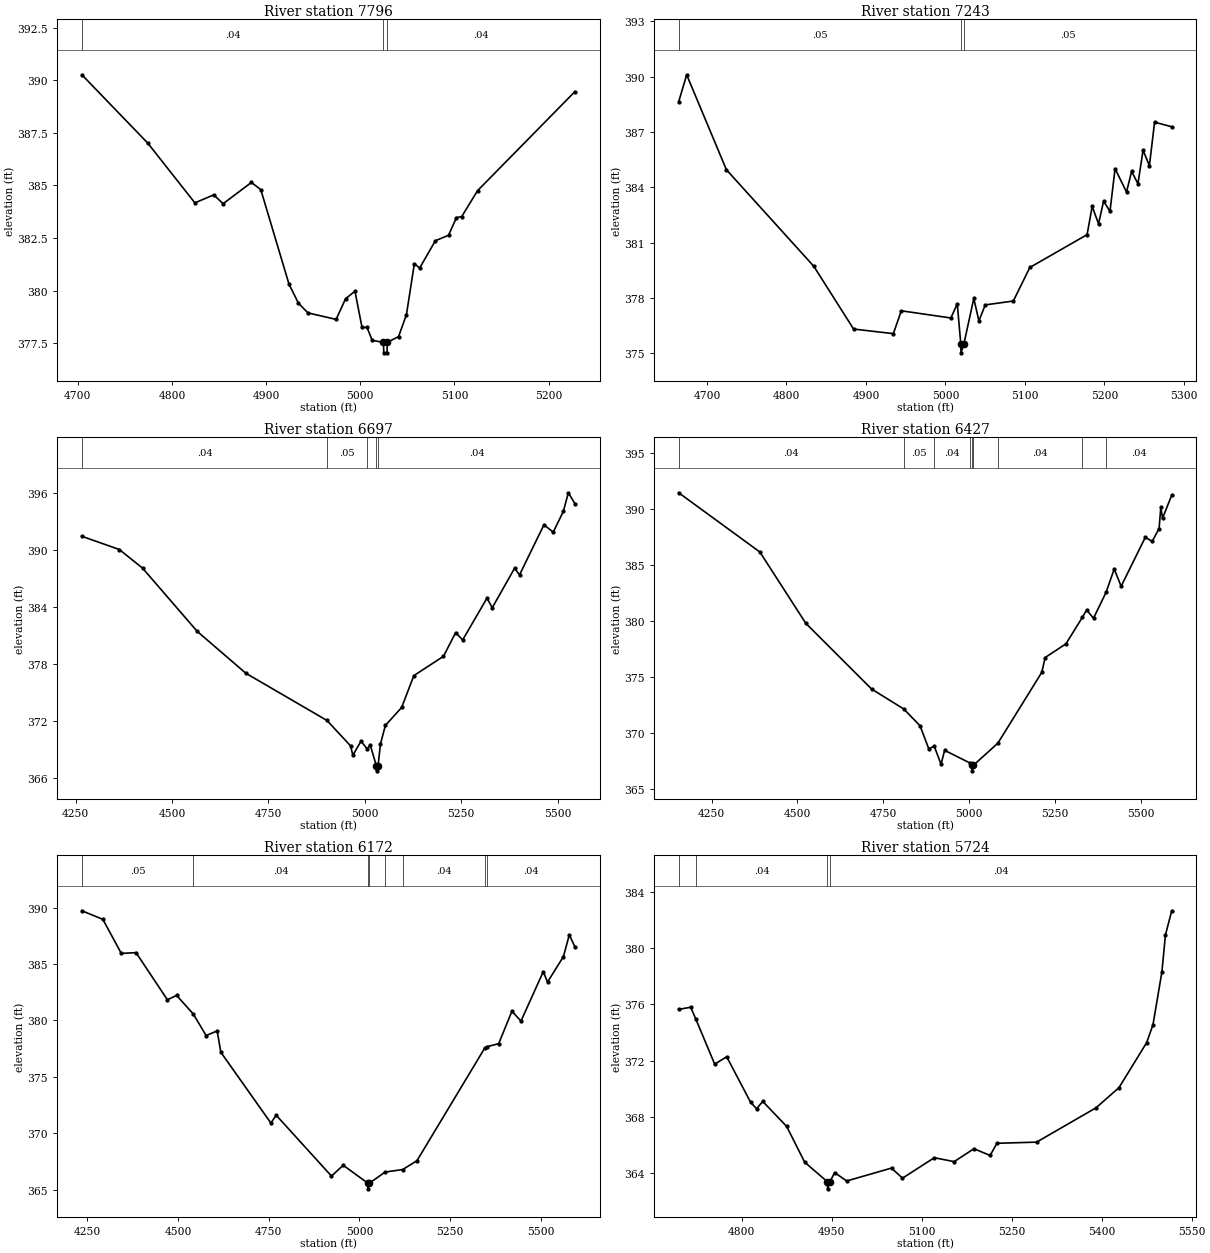
Type RM Length L Ch R = 1,7796,553,553,553
BEGIN DESCRIPTION:
TRIB 2 TO THOMAS CREEK 13.0
END DESCRIPTION:
XS GIS Cut Line= 3
      2411674.98     13553075.00      2411375.00     13553075.00
      2411174.99     13553175.01
#Sta/Elev= 30
  4704.3  390.26  4774.3  387.01  4824.3  384.17  4844.3  384.55  4854.3  384.13
  4884.3  385.14  4894.3  384.80  4924.3  380.30  4934.3  379.40  4944.3  378.94
  4974.3  378.63  4984.3  379.61  4994.3  379.97  5001.8  378.25  5007.1  378.25
  5012.7  377.63  5024.6  377.54  5024.9  377.04  5028.4  377.04  5028.6  377.54
  5040.6  377.81  5049.0  378.86  5057.4  381.28  5063.0  381.07  5079.7  382.37
  5093.7  382.63  5102.1  383.47  5107.7  383.52  5124.5  384.75  5227.9  389.46
#Mann=3,-1,0
  4704.3    0.04       0  5024.6    0.04       0  5028.6    0.04       0
Bank Sta=5024.6,5028.6
Exp/Cntr=0.3,0.1

Type RM Length L Ch R = 1,7243,546,546,546
BEGIN DESCRIPTION:
TRIB 2 TO THOMAS CREEK 12.0
END DESCRIPTION:
XS GIS Cut Line= 3
      2411625.01     13552625.00      2411325.00     13552625.00
      2411074.97     13552825.02
#Sta/Elev= 30
  4664.5  388.65  4674.5  390.11  4724.5  384.96  4834.5  379.72  4884.5  376.32
  4934.5  376.07  4944.5  377.31  5006.9  376.92  5014.9  377.69  5019.3  375.53
  5019.6  375.03  5023.3  375.53  5035.7  377.98  5042.1  376.76  5050.1  377.63
  5085.4  377.84  5106.2  379.66  5178.2  381.44  5184.6  382.97  5192.6  382.03
  5199.0  383.26  5207.0  382.70  5213.4  385.02  5227.8  383.75  5234.2  384.87
  5242.2  384.20  5248.6  386.02  5256.6  385.18  5263.1  387.54  5284.7  387.29
#Mann=3,-1,0
  4664.5    0.05       0  5019.3    0.05       0  5023.3    0.05       0
Bank Sta=5019.3,5023.3
Exp/Cntr=0.3,0.1

Type RM Length L Ch R = 1,6697,270,270,270
BEGIN DESCRIPTION:
Mapping XS 81906cfd
END DESCRIPTION:
XS GIS Cut Line= 3
      2411771.29     13552275.56      2411080.65     13552184.56
      2410528.81     13552368.50
#Sta/Elev= 30
  4266.5  391.42  4363.6  390.03  4424.1  388.06  4565.4  381.42  4691.6  377.01
  4902.0  372.04  4963.1  369.37  4969.1  368.38  4990.1  369.86  5006.1  369.06
  5014.2  369.44  5030.3  367.24  5030.6  366.74  5034.3  367.24  5040.6  369.56
  5053.4  371.52  5095.6  373.41  5127.2  376.76  5204.0  378.79  5235.6  381.29
  5253.7  380.51  5316.9  384.92  5330.4  383.90  5388.4  388.06  5401.2  387.36
  5464.5  392.63  5488.6  391.86  5514.9  394.05  5527.7  396.00  5544.8  394.86
#Mann=5,-1,0
  4266.5    0.04       0  4902.0    0.05       0  5006.1    0.04       0
  5030.3    0.05       0  5034.3    0.04       0
Bank Sta=5030.3,5034.3
Exp/Cntr=0.3,0.1

Type RM Length L Ch R = 1,6427,255,255,255
BEGIN DESCRIPTION:
Mapping XS 3dd9ffa2
END DESCRIPTION:
XS GIS Cut Line= 3
      2411822.58     13552231.21      2411071.31     13551955.90
      2410438.33     13552023.39
#Sta/Elev= 30
  4154.1  391.45  4390.6  386.16  4524.3  379.80  4716.0  373.93  4810.5  372.13
  4857.4  370.64  4882.6  368.60  4898.8  368.81  4918.5  367.21  4929.0  368.45
  5002.7  367.32  5008.9  367.12  5009.1  366.62  5012.9  367.12  5084.1  369.09
  5212.0  375.41  5222.0  376.74  5282.4  377.96  5330.2  380.32  5342.7  380.98
  5362.8  380.25  5399.3  382.55  5423.2  384.64  5443.3  383.10  5513.7  387.47
  5533.8  387.11  5553.9  388.26  5558.9  390.14  5564.0  389.18  5590.8  391.24
#Mann=9,-1,0
  4154.1    0.04       0  4810.5    0.05       0  4898.8    0.04       0
  5002.7    0.05       0  5008.9    0.04       0  5012.9    0.05       0
  5084.1    0.04       0  5330.2    0.05       0  5399.3    0.04       0
Bank Sta=5008.9,5012.9
Exp/Cntr=0.3,0.1

Type RM Length L Ch R = 1,6172,448,448,448
BEGIN DESCRIPTION:
Mapping XS 7b7452dd
END DESCRIPTION:
XS GIS Cut Line= 3
      2411761.92     13551811.24      2411092.31     13551692.25
      2410429.82     13551836.87
#Sta/Elev= 30
  4235.5  389.72  4293.3  388.96  4344.1  385.94  4384.7  386.01  4471.1  381.83
  4496.4  382.22  4542.6  380.56  4577.7  378.66  4608.2  379.07  4618.3  377.18
  4756.2  370.90  4770.7  371.60  4923.1  366.20  4955.4  367.16  5023.4  365.57
  5023.7  365.07  5027.4  365.57  5071.0  366.56  5119.1  366.78  5158.5  367.56
  5345.7  377.57  5350.2  377.66  5383.7  377.94  5420.2  380.82  5445.1  379.94
  5506.5  384.32  5518.2  383.40  5562.1  385.66  5578.2  387.58  5593.7  386.53
#Mann=8,-1,0
  4235.5    0.05       0  4542.6    0.04       0  5023.4    0.04       0
  5027.4    0.04       0  5071.0    0.05       0  5119.1    0.04       0
  5345.7    0.05       0  5350.2    0.04       0
Bank Sta=5023.4,5027.4
Exp/Cntr=0.3,0.1

Type RM Length L Ch R = 1,5724,480,480,480
BEGIN DESCRIPTION:
TRIB 2 TO THOMAS CREEK 9.0
END DESCRIPTION:
XS GIS Cut Line= 3
      2411324.97     13551325.00      2411025.00     13551325.00
      2410524.98     13551475.00
#Sta/Elev= 30
  4694.8  375.65  4714.8  375.80  4723.6  374.93  4754.8  371.74  4774.8  372.27
  4814.8  369.01  4824.8  368.56  4834.8  369.09  4874.8  367.30  4904.8  364.75
  4942.8  363.35  4943.0  362.85  4946.8  363.35  4954.8  364.01  4974.8  363.41
  5049.6  364.33  5067.9  363.61  5120.9  365.07  5154.0  364.79  5187.0  365.71
  5214.0  365.23  5225.3  366.10  5291.4  366.18  5390.6  368.63  5428.9  370.07
  5475.0  373.28  5485.5  374.55  5500.3  378.30  5506.3  380.96  5516.8  382.68
#Mann=4,-1,0
  4694.8    0.05       0  4723.6    0.04       0  4942.8    0.04       0
  4946.8    0.04       0
Bank Sta=4942.8,4946.8
Exp/Cntr=0.3,0.1

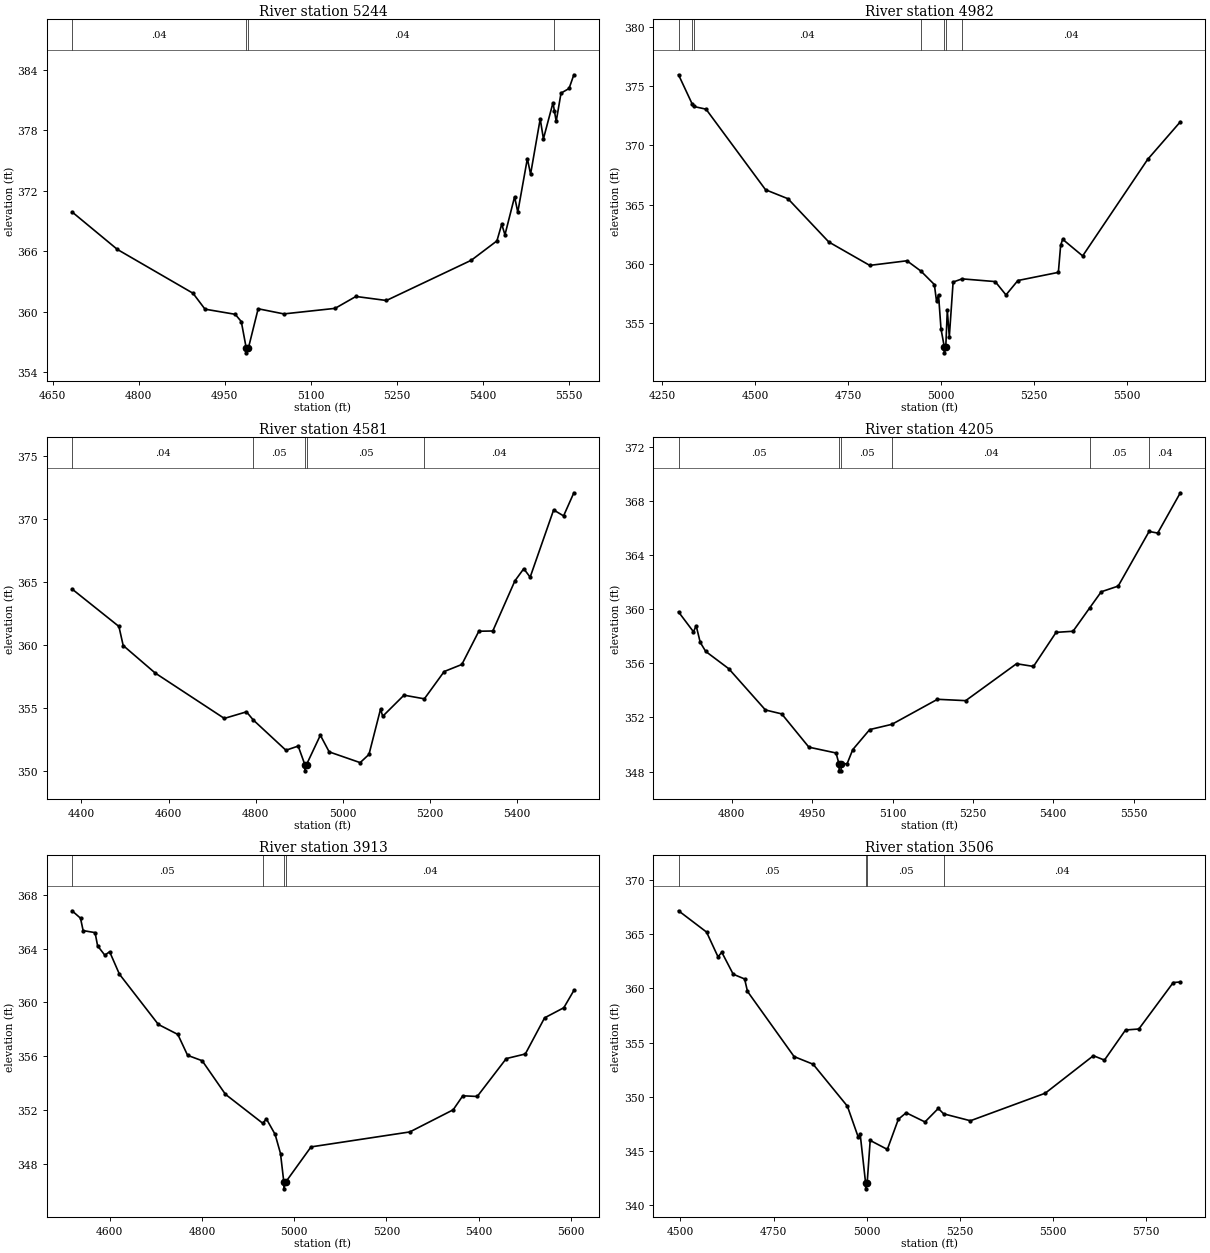
Type RM Length L Ch R = 1,5244,262,262,262
BEGIN DESCRIPTION:
TRIB 2 TO THOMAS CREEK 8.0
END DESCRIPTION:
XS GIS Cut Line= 3
      2411175.03     13551025.01      2410875.00     13550925.00
      2410374.98     13551175.01
#Sta/Elev= 30
  4683.6  369.88  4762.7  366.16  4894.5  361.82  4915.5  360.24  4968.2  359.73
  4978.8  359.01  4987.3  356.41  4987.6  355.91  4991.3  356.41  5008.2  360.28
  5053.0  359.77  5142.4  360.32  5178.7  361.50  5231.9  361.10  5380.0  365.09
  5424.7  367.01  5433.1  368.67  5438.7  367.61  5455.5  371.38  5461.1  369.86
  5477.8  375.17  5483.4  373.62  5500.2  379.11  5505.8  377.13  5522.5  380.71
  5525.1  379.85  5528.1  378.86  5536.5  381.66  5550.5  382.12  5558.9  383.48
#Mann=4,-1,0
  4683.6    0.04       0  4987.3    0.04       0  4991.3    0.04       0
  5525.1    0.05       0
Bank Sta=4987.3,4991.3
Exp/Cntr=0.3,0.1

Type RM Length L Ch R = 1,4982,401,401,401
BEGIN DESCRIPTION:
Mapping XS 8303d88f
END DESCRIPTION:
XS GIS Cut Line= 3
      2411578.85     13550645.61      2410891.33     13550656.03
      2410283.69     13550916.45
#Sta/Elev= 30
  4294.1  375.98  4331.2  373.48  4334.5  373.30  4368.0  373.07  4528.0  366.25
  4588.3  365.49  4698.0  361.83  4808.0  359.85  4908.0  360.24  4945.5  359.37
  4981.7  358.23  4987.5  356.82  4992.9  357.37  4999.5  354.49  5008.4  352.95
  5008.6  352.45  5012.4  352.95  5016.5  356.06  5021.9  353.81  5032.1  358.44
  5056.2  358.71  5145.2  358.48  5174.2  357.35  5206.2  358.57  5315.0  359.26
  5321.1  361.54  5326.5  362.06  5380.3  360.65  5555.0  368.82  5642.8  372.00
#Mann=7,-1,0
  4294.1    0.03       0  4331.2    0.05       0  4334.5    0.04       0
  4945.5    0.05       0  5008.4    0.05       0  5012.4    0.05       0
  5056.2    0.04       0
Bank Sta=5008.4,5012.4
Exp/Cntr=0.3,0.1

Type RM Length L Ch R = 1,4581,376,376,376
BEGIN DESCRIPTION:
Mapping XS f7ef6058
END DESCRIPTION:
XS GIS Cut Line= 3
      2411492.02     13550107.42      2411005.92     13550340.06
      2410401.73     13550447.70
#Sta/Elev= 30
  4378.5  364.44  4486.1  361.48  4495.9  359.97  4569.5  357.79  4728.2  354.20
  4779.1  354.72  4794.9  354.07  4869.7  351.68  4897.9  352.01  4913.1  350.55
  4913.3  350.05  4917.1  350.55  4948.8  352.87  4969.1  351.55  5040.2  350.70
  5060.5  351.35  5087.0  354.93  5092.1  354.37  5140.9  356.04  5187.7  355.75
  5233.2  357.91  5273.8  358.47  5312.8  361.10  5344.9  361.12  5395.7  365.09
  5416.0  366.05  5430.7  365.38  5484.6  370.70  5507.5  370.23  5531.1  372.06
#Mann=5,-1,0
  4378.5    0.04       0  4794.9    0.05       0  4913.1    0.05       0
  4917.1    0.05       0  5187.7    0.04       0
Bank Sta=4913.1,4917.1
Exp/Cntr=0.3,0.1

Type RM Length L Ch R = 1,4205,292,292,292
BEGIN DESCRIPTION:
TRIB 2 TO THOMAS CREEK 6.0
END DESCRIPTION:
XS GIS Cut Line= 3
      2411374.99     13550075.00      2411075.00     13550025.00
      2410474.98     13550225.01
#Sta/Elev= 30
  4700.6  359.80  4728.5  358.33  4733.5  358.78  4741.1  357.55  4751.3  356.88
  4794.4  355.60  4862.8  352.55  4893.2  352.26  4943.9  349.80  4994.6  349.37
  5000.2  348.55  5000.4  348.05  5003.9  348.05  5004.2  348.55  5015.3  348.58
  5025.8  349.62  5057.4  351.10  5098.9  351.49  5183.9  353.34  5236.6  353.24
  5331.5  355.97  5363.1  355.77  5405.3  358.29  5436.9  358.37  5467.7  360.08
  5489.6  361.29  5521.2  361.71  5578.9  365.75  5595.0  365.63  5637.2  368.61
#Mann=6,-1,0
  4700.6    0.05       0  5000.2    0.05       0  5004.2    0.05       0
  5098.9    0.04       0  5467.7    0.05       0  5578.9    0.04       0
Bank Sta=5000.2,5004.2
Exp/Cntr=0.3,0.1

Type RM Length L Ch R = 1,3913,407,407,407
BEGIN DESCRIPTION:
Mapping XS 17202c5e
END DESCRIPTION:
XS GIS Cut Line= 3
      2411582.28     13549867.83      2411183.00     13549732.42
      2410544.15     13549923.38
#Sta/Elev= 30
  4518.1  366.80  4536.4  366.25  4542.1  365.33  4568.0  365.18  4573.5  364.20
  4589.1  363.51  4599.6  363.76  4620.8  362.10  4705.3  358.37  4747.5  357.63
  4768.7  356.08  4800.3  355.68  4850.8  353.19  4931.4  351.05  4939.7  351.36
  4958.5  350.22  4970.2  348.80  4977.4  346.68  4977.6  346.18  4981.4  346.68
  5036.4  349.29  5250.7  350.40  5344.7  352.04  5365.6  353.08  5396.9  353.03
  5459.9  355.84  5501.2  356.18  5543.0  358.86  5584.7  359.61  5606.5  360.89
#Mann=4,-1,0
  4518.1    0.05       0  4931.4    0.04       0  4977.4    0.04       0
  4981.4    0.04       0
Bank Sta=4977.4,4981.4
Exp/Cntr=0.3,0.1

Type RM Length L Ch R = 1,3506,446,446,446
BEGIN DESCRIPTION:
Mapping XS c3eeb96d
END DESCRIPTION:
XS GIS Cut Line= 3
      2411658.71     13549447.70      2411117.03     13549336.58
      2410468.90     13549794.09
#Sta/Elev= 30
  4495.2  367.19  4570.4  365.22  4601.1  362.93  4611.3  363.35  4641.9  361.32
  4672.5  360.88  4680.2  359.73  4805.2  353.70  4856.3  352.99  4948.2  349.11
  4977.5  346.23  4982.6  346.51  4997.2  341.96  4997.4  341.46  5001.2  341.96
  5009.4  345.94  5055.4  345.11  5085.0  347.90  5105.9  348.50  5156.4  347.65
  5192.1  348.90  5206.5  348.40  5278.3  347.76  5479.1  350.31  5608.3  353.78
  5637.9  353.37  5694.5  356.16  5730.2  356.25  5822.5  360.55  5841.5  360.60
#Mann=4,-1,0
  4495.2    0.05       0  4997.2    0.05       0  5001.2    0.05       0
  5206.5    0.04       0
Bank Sta=4997.2,5001.2
Exp/Cntr=0.3,0.1

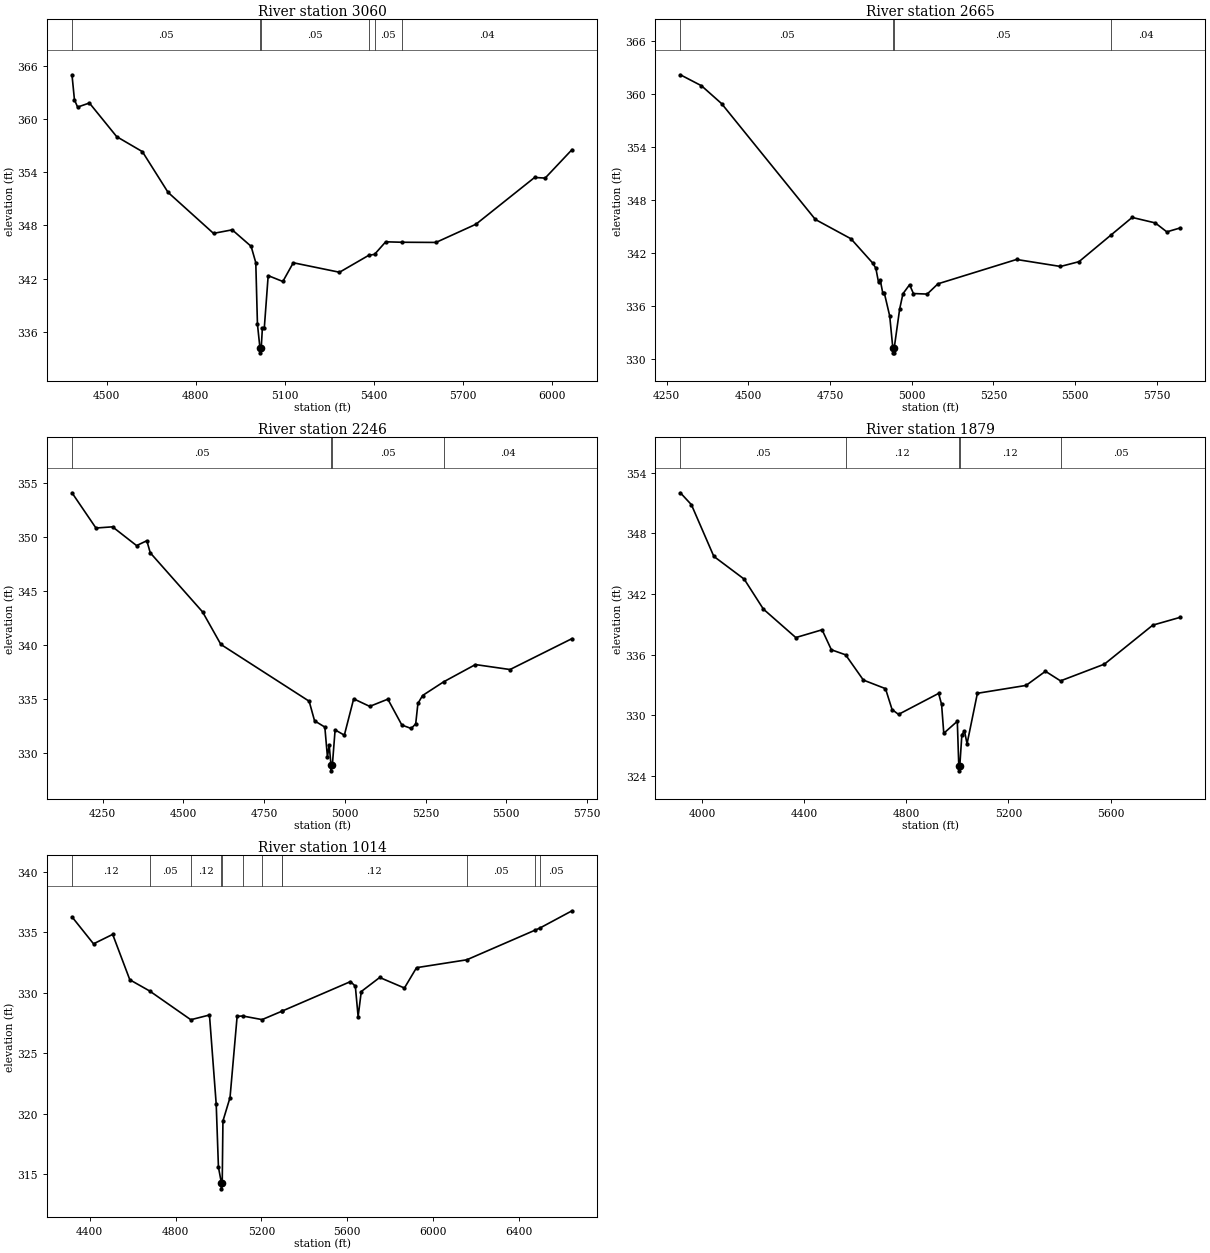
Type RM Length L Ch R = 1,3060,395,395,395
BEGIN DESCRIPTION:
Mapping XS dcb2d61b
END DESCRIPTION:
XS GIS Cut Line= 3
      2411762.82     13549110.88      2411158.69     13548892.14
      2410402.21     13549610.46
#Sta/Elev= 30
  4382.7  364.96  4391.0  362.14  4401.7  361.32  4441.4  361.78  4533.4  357.99
  4620.0  356.30  4706.6  351.71  4859.8  347.09  4922.8  347.49  4986.6  345.63
  5002.3  343.79  5007.9  336.86  5016.5  334.13  5016.8  333.63  5020.5  334.13
  5024.5  336.38  5030.9  336.38  5044.1  342.33  5093.5  341.67  5128.7  343.78
  5284.5  342.71  5383.7  344.63  5402.5  344.72  5440.2  346.14  5496.0  346.09
  5609.7  346.07  5744.4  348.12  5942.2  353.39  5977.8  353.32  6068.4  356.53
#Mann=6,-1,0
  4382.7    0.05       0  5016.5    0.05       0  5020.5    0.05       0
  5383.7    0.04       0  5402.5    0.05       0  5496.0    0.04       0
Bank Sta=5016.5,5020.5
Exp/Cntr=0.3,0.1

Type RM Length L Ch R = 1,2665,419,419,419
BEGIN DESCRIPTION:
Mapping XS 4637e4cc
END DESCRIPTION:
XS GIS Cut Line= 4
      2411884.34     13548770.59      2411311.47     13548524.08
      2411186.47     13548503.25      2410638.96     13549057.70
#Sta/Elev= 30
  4292.3  362.16  4356.9  360.92  4418.5  358.90  4705.3  345.81  4814.1  343.63
  4880.3  340.90  4890.3  340.30  4898.4  338.72  4903.8  338.95  4911.3  337.53
  4916.0  337.53  4932.7  334.90  4942.3  331.24  4942.6  330.74  4946.1  330.74
  4946.3  331.24  4963.1  335.69  4973.2  337.42  4993.5  338.44  5005.2  337.44
  5047.3  337.38  5080.3  338.54  5320.7  341.29  5455.1  340.50  5511.6  341.04
  5608.8  344.03  5674.3  346.04  5745.0  345.42  5780.3  344.41  5821.9  344.86
#Mann=4,-1,0
  4292.3    0.05       0  4942.3    0.05       0  4946.3    0.05       0
  5608.8    0.04       0
Bank Sta=4942.3,4946.3
Exp/Cntr=0.3,0.1

Type RM Length L Ch R = 1,2246,367,367,367
BEGIN DESCRIPTION:
Mapping XS 6a49994c
END DESCRIPTION:
XS GIS Cut Line= 3
      2412003.70     13548373.35      2411213.73     13548095.55
      2410653.81     13548533.94
#Sta/Elev= 30
  4154.9  354.13  4229.1  350.86  4280.5  350.97  4354.9  349.23  4386.7  349.68
  4397.3  348.56  4559.2  343.08  4615.9  340.06  4889.3  334.79  4906.1  332.97
  4937.9  332.39  4946.0  329.61  4951.3  330.73  4957.1  328.83  4957.4  328.33
  4961.1  328.83  4969.7  332.13  4998.3  331.64  5027.2  335.01  5076.9  334.31
  5133.0  334.98  5176.4  332.58  5205.3  332.26  5219.3  332.69  5226.1  334.58
  5240.6  335.32  5305.9  336.59  5404.2  338.19  5511.4  337.73  5703.4  340.60
#Mann=4,-1,0
  4154.9    0.05       0  4957.1    0.05       0  4961.1    0.05       0
  5305.9    0.04       0
Bank Sta=4957.1,4961.1
Exp/Cntr=0.3,0.1

Type RM Length L Ch R = 1,1879,865,865,865
BEGIN DESCRIPTION:
Mapping XS aaa0db5f
END DESCRIPTION:
XS GIS Cut Line= 4
      2412112.13     13548073.84      2411192.03     13547752.67
      2410844.81     13547809.10      2410584.39     13548386.35
#Sta/Elev= 30
  3914.3  352.03  3957.6  350.85  4045.5  345.73  4164.4  343.48  4239.6  340.51
  4366.7  337.69  4469.7  338.46  4506.1  336.48  4561.9  335.98  4631.5  333.48
  4718.2  332.63  4744.0  330.56  4769.2  330.08  4926.4  332.16  4938.0  331.07
  4946.6  328.21  4999.6  329.40  5005.4  324.99  5005.7  324.49  5009.4  324.99
  5017.5  328.07  5027.7  328.43  5037.8  327.17  5078.3  332.17  5269.0  332.95
  5345.0  334.35  5404.1  333.40  5576.2  335.06  5765.6  338.92  5873.9  339.70
#Mann=5,-1,0
  3914.3    0.05       0  4561.9    0.12       0  5005.4    0.05       0
  5009.4    0.12       0  5404.1    0.05       0
Bank Sta=5005.4,5009.4
Exp/Cntr=0.3,0.1

Type RM Length L Ch R = 1,1014,0,0,0
BEGIN DESCRIPTION:
Mapping XS 00fd2fd9
END DESCRIPTION:
XS GIS Cut Line= 4
      2411877.82     13547631.19      2411591.33     13547149.37
      2411330.92     13547071.25      2410450.72     13548280.98
#Sta/Elev= 30
  4317.9  336.26  4418.2  334.03  4507.4  334.81  4587.2  331.06  4679.0  330.14
  4871.2  327.76  4958.1  328.15  4989.5  320.78  4999.9  315.58  5013.5  314.29
  5013.8  313.79  5017.5  314.29  5020.8  319.39  5053.8  321.33  5086.9  328.04
  5112.4  328.07  5203.1  327.77  5294.8  328.46  5295.9  328.47  5614.8  330.91
  5637.3  330.53  5650.3  328.02  5665.0  330.09  5750.8  331.25  5865.9  330.38
  5922.3  332.06  6156.2  332.71  6473.1  335.15  6495.2  335.32  6646.4  336.76
#Mann=12,-1,0
  4317.9    0.12       0  4679.0    0.05       0  4871.2    0.12       0
  5013.5    0.05       0  5017.5    0.12       0  5112.4    0.05       0
  5203.1    0.12       0  5294.8    0.05       0  5295.9    0.12       0
  6156.2    0.05       0  6473.1    0.12       0  6495.2    0.05       0
Bank Sta=5013.5,5017.5
Exp/Cntr=0.3,0.1

Chan Stop Cuts=-1