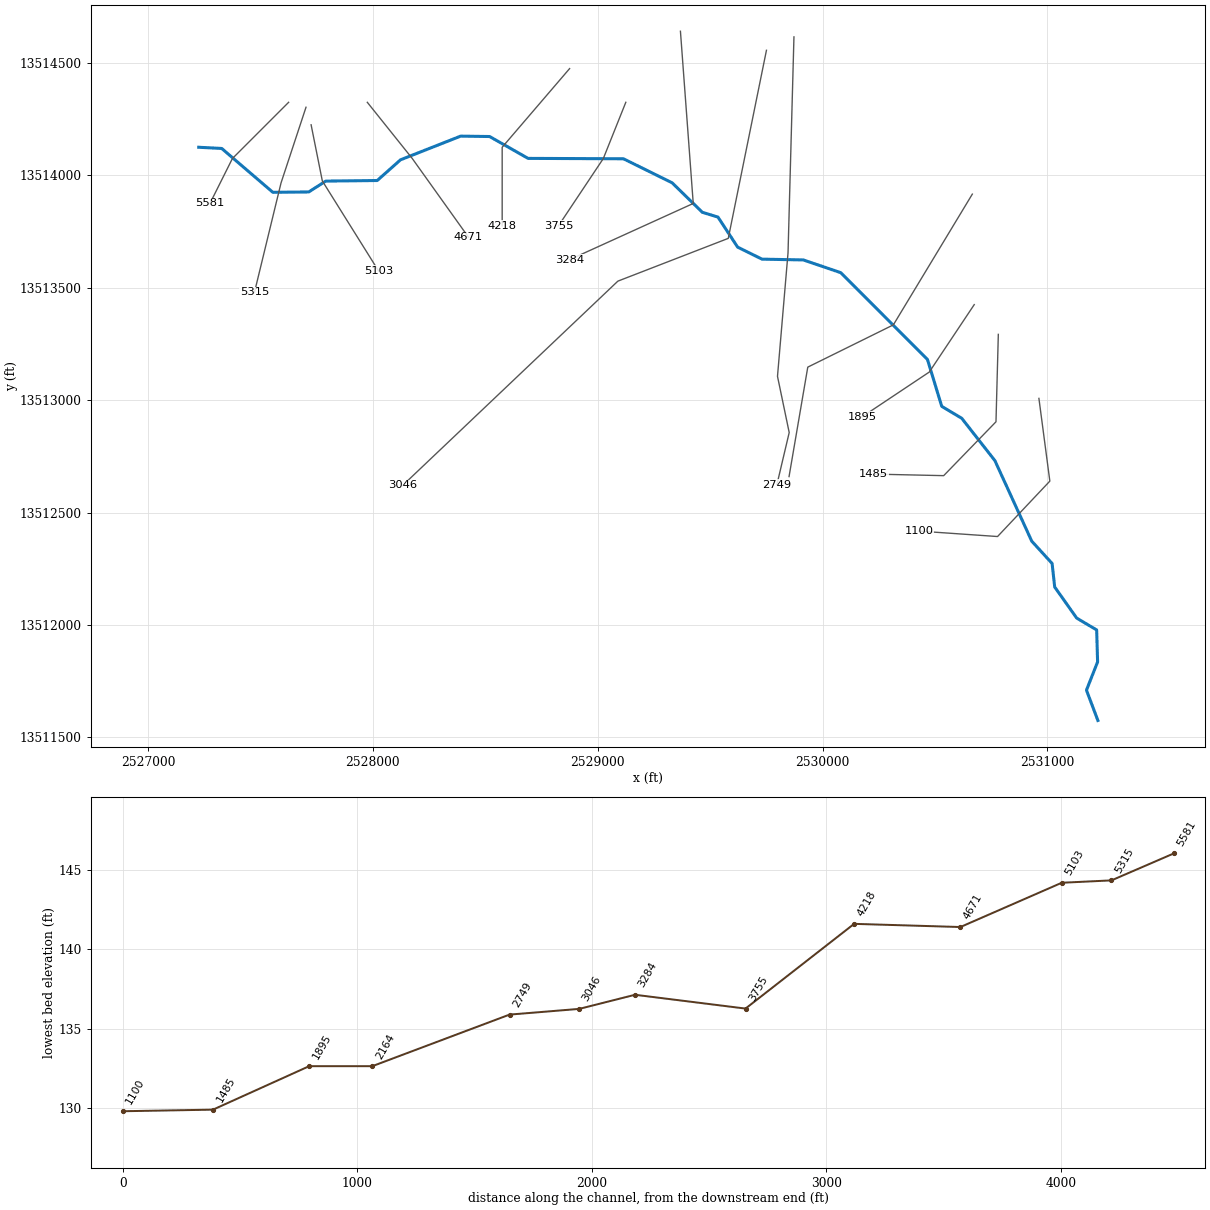
--- TRIB 2 TO TWELVEMILE CREEK.prj (project) ---

Proj Title=TRIB 2 TO TWELVEMILE CREEK Base Level Engineering
Current Plan=p01
Default Exp/Contr=0.3,0.1
English Units
Geom File=g01
Flow File=f01
Plan File=p01
Y Axis Title=Elevation
X Axis Title(PF)=Main Channel Distance
X Axis Title(XS)=Station
BEGIN DESCRIPTION:
TRIB 2 TO TWELVEMILE CREEK
END DESCRIPTION:
DSS Export Rating Curves= 0
DSS Export Rating Curve Sorted= 0
DSS Export Volume Flow Curves= 0
DXF OffsetX= 0
DXF OffsetY= 0
DXF ScaleX= 1
DXF ScaleY= 10

--- TRIB 2 TO TWELVEMILE CREEK.p01 (plan) ---

Plan Title=Multiple Run
Short Identifier=Multiple
Geom File=g01
Flow File=f01
Subcritical Flow
K Sum by GR= 0
Std Step Tol= 0.01
Critical Tol= 0.01
Num of Std Step Trials= 20
Max Error Tol= 0.3
Flow Tol Ratio= 0.001
Split Flow NTrial= 30
Split Flow Tol= 0.02
Split Flow Ratio= 0.02
Log Output Level= 0
Friction Slope Method= 1
Unsteady Friction Slope Method= 2
Unsteady Bridges Friction Slope Method= 1
Parabolic Critical Depth
Global Vel Dist=  1 , 1 , 1
Global Log Level= 0
CheckData=True
Encroach Param= -1, 0, 0, 0
BEGIN DESCRIPTION:
Multiple Run
END DESCRIPTION:

--- TRIB 2 TO TWELVEMILE CREEK.f01 (steady flow) ---

Flow Title=Multiple
Number of Profiles=7
Profile Names=10-year,25-year,50-year,1pct_min,100-year,1pct_plu,500-year
River Rch & RM= TRIB 2 TO TWELVE,Reach-1,5581
    1048    1720    2337    1534    3061    6107    5195
River Rch & RM= TRIB 2 TO TWELVE,Reach-1,3046
    1068    1752    2379    1561    3115    6215    5282
Boundary for River Rch & Prof#=TRIB 2 TO TWELVE,Reach-1,1
Up Type=0
Dn Type=3
Dn Slope=0.005
Boundary for River Rch & Prof#=TRIB 2 TO TWELVE,Reach-1,2
Up Type=0
Dn Type=3
Dn Slope=0.005
Boundary for River Rch & Prof#=TRIB 2 TO TWELVE,Reach-1,3
Up Type=0
Dn Type=3
Dn Slope=0.005
Boundary for River Rch & Prof#=TRIB 2 TO TWELVE,Reach-1,4
Up Type=0
Dn Type=3
Dn Slope=0.005
Boundary for River Rch & Prof#=TRIB 2 TO TWELVE,Reach-1,5
Up Type=0
Dn Type=3
Dn Slope=0.005
Boundary for River Rch & Prof#=TRIB 2 TO TWELVE,Reach-1,6
Up Type=0
Dn Type=3
Dn Slope=0.005
Boundary for River Rch & Prof#=TRIB 2 TO TWELVE,Reach-1,7
Up Type=0
Dn Type=3
Dn Slope=0.005

--- TRIB 2 TO TWELVEMILE CREEK.g01 (geometry) ---

Geom Title=Existing Conditions
Program Version=4.10

River Reach=TRIB 2 TO TWELVE,Reach-1
Reach XY= 30
        2527225.       13514125.       2527327.5     13514119.65
      2527554.82     13513924.56      2527714.49     13513926.22
      2527790.22     13513974.48      2528019.14     13513977.06
      2528122.71     13514069.15      2528390.22      13514174.5
      2528519.07     13514172.77      2528690.21     13514075.51
       2529114.5      13514073.8      2529331.06     13513966.86
      2529465.34     13513835.79      2529534.99     13513814.35
      2529622.45     13513680.73      2529730.93     13513627.24
       2529914.5     13513623.78      2530081.17     13513567.14
      2530466.86     13513181.06      2530530.46     13512972.34
      2530619.35     13512919.36      2530766.86     13512731.06
      2530930.85     13512372.71      2531021.37      13512273.5
      2531032.88     13512168.83      2531130.65     13512030.64
      2531219.61     13511977.68      2531223.79     13511835.51
      2531174.27     13511709.94        2531225.       13511575.

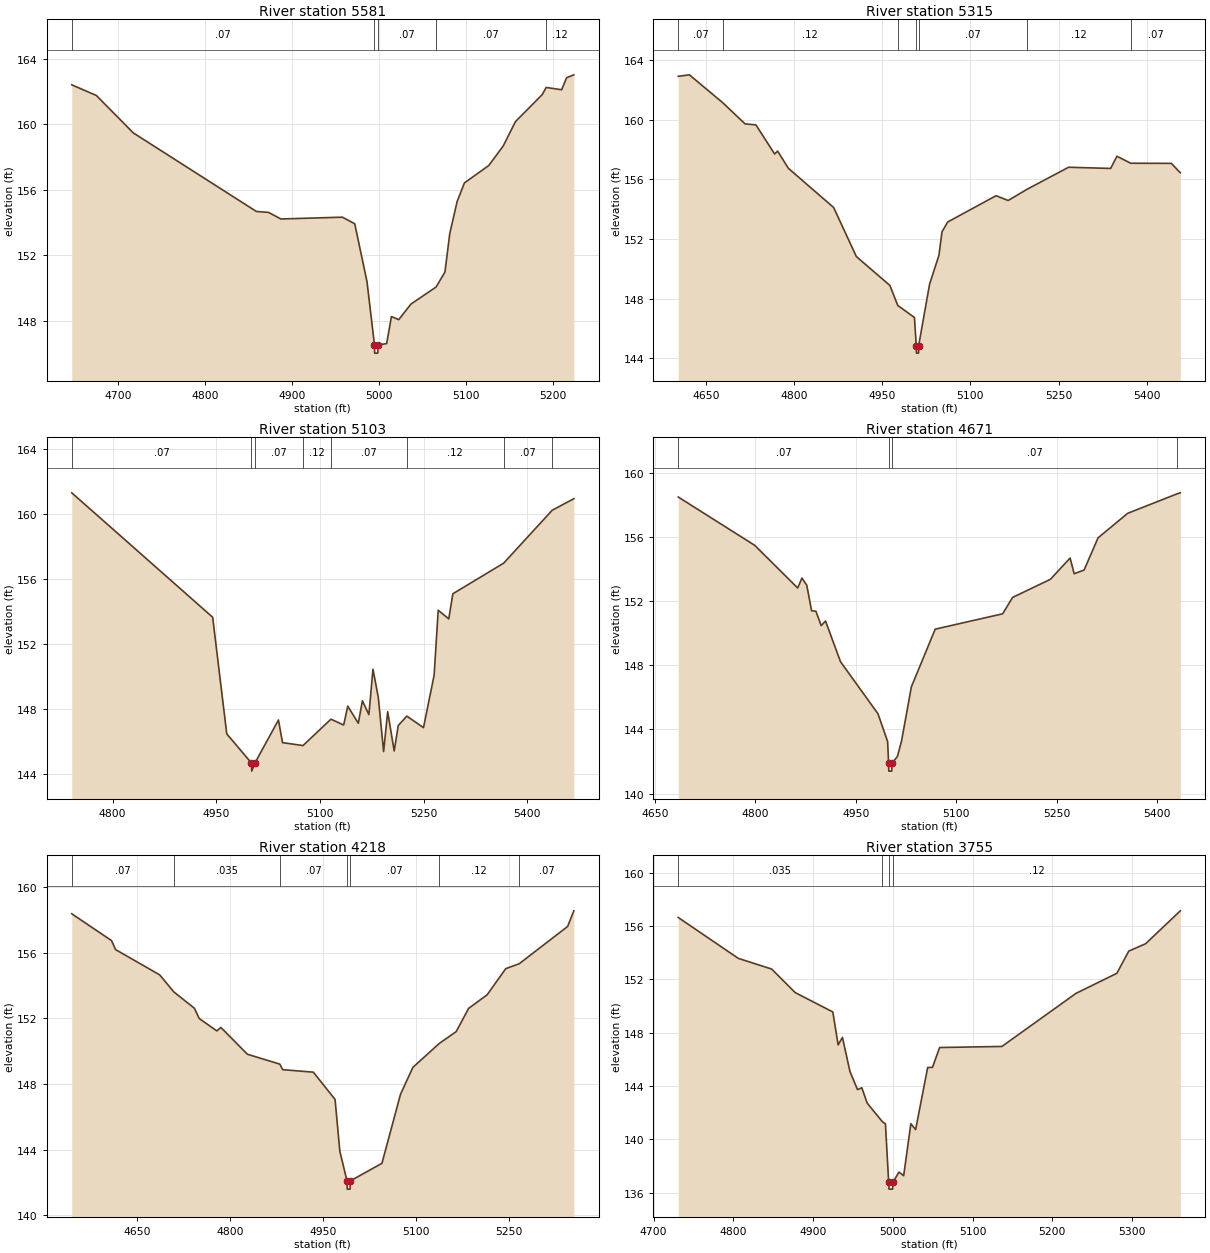
Type RM Length L Ch R = 1 ,5581    ,266,266,266
BEGIN DESCRIPTION:
TRIB 2 TO TWELVEMILE CREEK 10.0
END DESCRIPTION:
XS GIS Cut Line= 3
      2527625.01     13514325.01        2527375.       13514075.
      2527274.99     13513874.98
#Sta/Elev= 30
  4646.7   162.4    4675  161.75  4717.4  159.47  4858.9  154.68    4873  154.62
  4887.1  154.22  4957.8  154.33    4972  153.93  4986.1   150.4  4994.7  146.54
  4994.9  146.04  4998.5  146.04  4998.8  146.54  5008.7  146.62  5014.2  148.27
  5022.6  148.08  5036.6  149.03  5065.5  150.07  5075.7  150.98  5081.3  153.34
  5089.7  155.28  5098.1  156.42  5126.1  157.48  5142.8  158.68  5156.8  160.16
  5187.5   161.8  5192.1  162.24  5209.9   162.1  5215.5  162.83  5223.9  163.01
#Mann= 5 ,-1 , 0
  4646.7     .07       0  4994.7     .05       0  4998.8     .07       0
  5065.5     .07       0  5192.1     .12       0
Bank Sta=4994.7,4998.8
XS Rating Curve= 0 ,0
Exp/Cntr=0.3,0.1

Type RM Length L Ch R = 1 ,5315    ,212,212,212
BEGIN DESCRIPTION:
Mapping XS 8bc3f2ff
END DESCRIPTION:
XS GIS Cut Line= 3
      2527702.31     13514303.05      2527591.19     13513966.21
      2527473.14     13513480.14
#Sta/Elev= 30
  4602.5  162.91  4621.5  163.01  4678.3  161.14  4716.3  159.72  4734.8  159.65
  4766.6   157.7  4771.8  157.89    4790  156.74  4867.1  154.11  4905.8  150.82
  4962.9  148.88  4976.3  147.54  5004.7  146.73  5007.8  144.84  5008.1  144.34
  5011.7  144.34  5011.9  144.84  5030.5  148.97  5046.4   150.9  5051.6  152.48
  5061.4  153.14  5143.7   154.9  5164.3  154.58  5196.4  155.33  5267.2  156.81
  5338.8  156.73  5349.5  157.55  5372.9  157.08  5442.1  157.07  5457.4  156.44
#Mann= 7 ,-1 , 0
  4602.5     .07       0  4678.3     .12       0  4976.3     .07       0
  5007.8     .05       0  5011.9     .07       0  5196.4     .12       0
  5372.9     .07       0
Bank Sta=5007.8,5011.9
XS Rating Curve= 0 ,0
Exp/Cntr=0.3,0.1

Type RM Length L Ch R = 1 ,5103    ,432,432,432
BEGIN DESCRIPTION:
TRIB 2 TO TWELVEMILE CREEK 9.0
END DESCRIPTION:
XS GIS Cut Line= 3
      2527725.01     13514224.96        2527775.       13513975.
        2528025.     13513575.01
#Sta/Elev= 30
  4740.9  161.28  4944.8  153.64  4965.2  146.48  5000.9  144.69  5001.3  144.19
    5006  144.69    5040  147.33  5045.9  145.94  5075.5  145.76    5116  147.38
  5134.4  147.02  5140.3  148.18  5155.6  147.13  5161.5  148.51  5170.9  147.66
  5176.8  150.45  5184.5  148.72  5192.2  145.39  5198.1  147.84  5207.5  145.43
  5213.4  146.99  5225.8  147.57  5249.9  146.86  5265.3  150.08  5271.2  154.07
  5286.5  153.54  5292.4  155.08  5365.9  156.96  5436.2  160.21  5467.5  160.92
#Mann= 8 ,-1 , 0
  4740.9     .07       0  5000.9     .05       0    5006     .07       0
  5075.5     .12       0    5116     .07       0  5225.8     .12       0
  5365.9     .07       0  5436.2    .035       0
Bank Sta=5000.9,5006
XS Rating Curve= 0 ,0
Exp/Cntr=0.3,0.1

Type RM Length L Ch R = 1 ,4671    ,453,453,453
BEGIN DESCRIPTION:
TRIB 2 TO TWELVEMILE CREEK 8.0
END DESCRIPTION:
XS GIS Cut Line= 3
      2527975.01     13514324.99        2528175.       13514075.
      2528425.02     13513724.97
#Sta/Elev= 30
  4684.7  158.51  4799.1  155.49  4863.2  152.83  4869.6  153.45  4876.8     153
    4884  151.41  4890.4  151.38  4898.4  150.48  4904.8  150.77  4927.2  148.23
  4983.2  144.98  4997.6  143.25  4999.1   141.9  4999.4   141.4  5003.8   141.4
  5004.2   141.9  5012.2  142.31  5018.4  143.28  5033.1  146.66  5068.7  150.26
  5169.5  151.22  5184.3  152.24  5240.8  153.37  5270.3   154.7  5276.4  153.72
  5291.2  153.95  5312.1  155.96  5356.3  157.49  5430.4  158.71    5435  158.77
#Mann= 4 ,-1 , 0
  4684.7     .07       0  4999.1     .05       0  5004.2     .07       0
  5430.4     .12       0
Bank Sta=4999.1,5004.2
XS Rating Curve= 0 ,0
Exp/Cntr=0.3,0.1

Type RM Length L Ch R = 1 ,4218    ,463,463,463
BEGIN DESCRIPTION:
TRIB 2 TO TWELVEMILE CREEK 7.0
END DESCRIPTION:
XS GIS Cut Line= 3
        2528875.       13514475.        2528575.       13514125.
        2528575.     13513774.97
#Sta/Elev= 30
  4543.9  158.36  4608.1  156.73  4614.7  156.18    4686  154.64  4708.6  153.61
    4742  152.61  4749.7  151.99  4778.2  151.23  4784.8  151.44  4827.6  149.81
  4879.9  149.21  4884.7  148.87  4934.1  148.72  4969.2  147.06  4976.9  143.91
  4988.5   142.1  4988.9   141.6  4993.4   141.6  4993.8   142.1  5044.9  143.17
  5074.9  147.37  5094.9  149.01  5137.3  150.46  5164.9  151.19  5184.9   152.6
  5214.9  153.43  5244.9  155.02  5266.7  155.32  5344.9  157.59  5354.9  158.54
#Mann= 7 ,-1 , 0
  4543.9     .07       0  4708.6    .035       0  4879.9     .07       0
  4988.5     .05       0  4993.8     .07       0  5137.3     .12       0
  5266.7     .07       0
Bank Sta=4988.5,4993.8
XS Rating Curve= 0 ,0
Exp/Cntr=0.3,0.1

Type RM Length L Ch R = 1 ,3755    ,471,471,471
BEGIN DESCRIPTION:
TRIB 2 TO TWELVEMILE CREEK 6.0
END DESCRIPTION:
XS GIS Cut Line= 3
      2529125.01     13514325.03        2529025.       13514075.
      2528825.03     13513775.04
#Sta/Elev= 30
  4730.8  156.65  4806.2  153.58    4848  152.78  4877.6  151.01  4924.7  149.56
  4931.4  147.09  4936.8  147.65  4946.2  145.09  4955.7  143.73  4961.1  143.87
  4967.8  142.72  4986.9  141.32  4990.7  141.17  4994.8  136.76  4995.2  136.26
  4999.7  136.26  5000.1  136.76  5007.6  137.54  5013.6  137.27  5022.6  141.17
  5028.6  140.73  5043.7  145.39  5049.7   145.4  5058.7  146.89  5136.8  146.97
  5229.9  150.96    5281  152.46    5296  154.13  5317.1  154.68  5360.6  157.15
#Mann= 4 ,-1 , 0
  4730.8    .035       0  4986.9     .12       0  4994.8     .05       0
  5000.1     .12       0
Bank Sta=4994.8,5000.1
XS Rating Curve= 0 ,0
Exp/Cntr=0.3,0.1

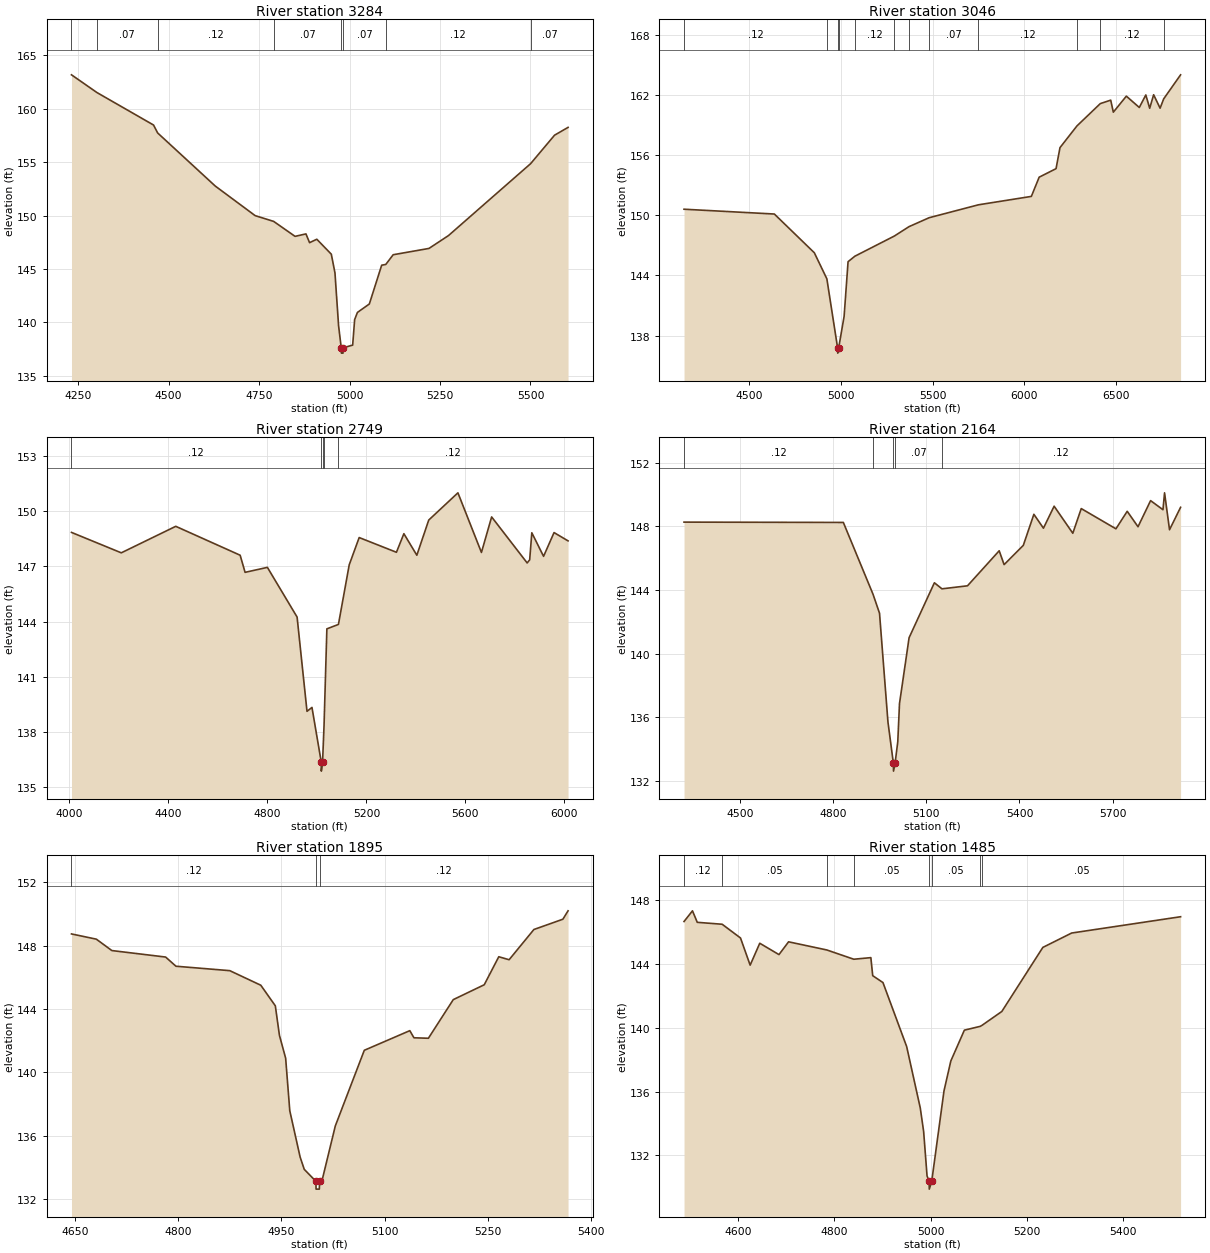
Type RM Length L Ch R = 1 ,3284    ,238,238,238
BEGIN DESCRIPTION:
TRIB 2 TO TWELVEMILE CREEK 5.0
END DESCRIPTION:
XS GIS Cut Line= 3
      2529367.99     13514641.16        2529425.       13513875.
      2528875.03     13513625.01
#Sta/Elev= 30
  4231.5  163.18  4301.9  161.52  4458.3  158.48  4469.6  157.74  4628.8  152.77
  4739.1     150  4790.3  149.46  4849.4  148.06  4879.5  148.29  4889.5  147.47
  4909.5  147.79  4949.6  146.39  4959.7  144.64  4969.7  139.69    4977  137.63
  4977.5  137.13    4982  137.13  4982.4  137.63  5008.6  137.88  5014.1  140.27
  5021.8  140.94  5054.7  141.73  5088.8  145.36  5100.1  145.43  5120.6  146.34
  5219.5  146.93  5273.3  148.13  5500.3  154.86  5566.6  157.53  5603.9  158.26
#Mann= 8 ,-1 , 0
  4231.5     .12       0  4301.9     .07       0  4469.6     .12       0
  4790.3     .07       0    4977     .05       0  4982.4     .07       0
  5100.1     .12       0  5500.3     .07       0
Bank Sta=4977,4982.4
XS Rating Curve= 0 ,0
Exp/Cntr=0.3,0.1

Type RM Length L Ch R = 1 ,3046    ,297,297,297
BEGIN DESCRIPTION:
Mapping XS 064a598b
END DESCRIPTION:
XS GIS Cut Line= 4
      2529750.66     13514556.44      2529580.77     13513719.68
       2529089.7     13513529.46      2528132.19     13512620.49
#Sta/Elev= 30
  4148.3  150.61  4639.6  150.13  4857.1  146.26  4925.2  143.66  4983.8  136.74
  4984.3  136.24  4989.2  136.74    5019  139.91  5040.5  145.37  5077.7  145.92
  5292.1  147.93  5372.1  148.87  5481.3  149.76  5749.4  151.05  6037.4  151.89
  6079.9  153.81  6171.7  154.66  6193.1  156.76  6285.5  158.93  6412.6  161.16
    6469   161.5  6483.2   160.3    6554   161.9  6624.5  160.77  6659.9  162.02
    6681  160.69  6702.4  162.04  6737.6   160.7  6757.1  161.63    6849  164.03
#Mann= 12 ,-1 , 0
  4148.3     .12       0  4925.2     .07       0  4983.8     .05       0
  4989.2     .07       0  5077.7     .12       0  5292.1     .07       0
  5372.1     .12       0  5481.3     .07       0  5749.4     .12       0
  6285.5     .07       0  6412.6     .12       0  6757.1     .07       0
Bank Sta=4983.8,4989.2
XS Rating Curve= 0 ,0
Exp/Cntr=0.3,0.1

Type RM Length L Ch R = 1 ,2749    ,585,585,585
BEGIN DESCRIPTION:
Mapping XS 1596b617
END DESCRIPTION:
XS GIS Cut Line= 5
      2529872.99     13514616.08      2529846.64     13513655.39
      2529799.76     13513105.92      2529851.85     13512855.92
      2529797.17     13512624.17
#Sta/Elev= 30
  4008.6  148.85  4209.8  147.74  4429.8  149.18  4689.9  147.61  4709.9  146.68
    4800  146.95    4920  144.25    4960  139.13  4980.1  139.34  5017.5  136.38
  5017.9  135.88  5022.9  136.38  5028.8  138.34  5040.3  143.61    5087  143.85
  5130.6  147.09  5170.8  148.57  5321.3  147.77  5351.4  148.78  5403.7  147.61
  5451.8  149.52  5569.7     151  5664.7  147.76  5705.9  149.69  5849.4  147.19
  5859.6  147.36  5868.2  148.83  5915.7  147.55    5958  148.84  6014.6  148.39
#Mann= 5 ,-1 , 0
  4008.6     .12       0  5017.5     .05       0  5022.9     .12       0
  5028.8     .07       0    5087     .12       0
Bank Sta=5017.5,5022.9
XS Rating Curve= 0 ,0
Exp/Cntr=0.3,0.1

Type RM Length L Ch R = 1 ,2164    ,269,269,269
BEGIN DESCRIPTION:
TRIB 2 TO TWELVEMILE CREEK 3.0
END DESCRIPTION:
XS GIS Cut Line= 4
      2530666.54     13513916.57      2530315.17     13513334.86
      2529934.49     13513146.89      2529851.16     13512659.92
#Sta/Elev= 30
  4320.4  148.27  4833.2  148.25  4928.7  143.74  4949.6  142.55  4976.8  135.71
  4994.2  133.13  4994.7  132.63  4999.7  133.13  5008.4  134.48  5013.9  136.87
  5044.8  141.01  5126.2  144.46  5150.6  144.08  5232.8  144.27  5334.8  146.47
  5350.6   145.6  5412.4  146.81  5446.4  148.76  5477.2  147.89  5511.6  149.27
  5571.7  147.57  5598.9  149.12  5710.5  147.85  5746.8  148.95  5781.6  147.98
  5822.1  149.62  5861.9  149.05    5867  150.11    5883  147.79  5918.6   149.2
#Mann= 5 ,-1 , 0
  4320.4     .12       0  4928.7     .07       0  4994.2     .05       0
  4999.7     .07       0  5150.6     .12       0
Bank Sta=4994.2,4999.7
XS Rating Curve= 0 ,0
Exp/Cntr=0.3,0.1

Type RM Length L Ch R = 1 ,1895    ,410,410,410
BEGIN DESCRIPTION:
TRIB 2 TO TWELVEMILE CREEK 2.0
END DESCRIPTION:
XS GIS Cut Line= 3
        2530675.       13513425.        2530475.       13513125.
      2530175.01     13512925.01
#Sta/Elev= 30
  4645.2  148.75  4681.3  148.42  4703.8   147.7  4781.9  147.29  4796.9  146.71
  4875.1  146.43  4920.1  145.51  4941.2  144.21  4947.2  142.34  4956.2   140.9
  4962.2  137.58  4977.2  134.66  4983.2  133.88    5000  133.13  5000.4  132.63
  5005.1  132.63  5005.5  133.13  5008.8  133.13  5028.3  136.62  5070.4   141.4
  5136.5  142.64  5142.5  142.19  5163.5  142.16  5199.6   144.6  5244.6  145.54
  5265.7  147.31  5280.7  147.12  5316.7  149.03  5358.8  149.68  5366.3  150.21
#Mann= 3 ,-1 , 0
  4645.2     .12       0    5000     .05       0  5005.5     .12       0
Bank Sta=5000,5005.5
XS Rating Curve= 0 ,0
Exp/Cntr=0.3,0.1

Type RM Length L Ch R = 1 ,1485    ,385,385,385
BEGIN DESCRIPTION:
Mapping XS da39e355
END DESCRIPTION:
XS GIS Cut Line= 4
      2530782.16     13513292.61      2530771.74     13512903.71
       2530539.1     13512664.13      2530228.26     13512671.04
#Sta/Elev= 30
  4486.8  146.64  4504.4  147.31  4514.4  146.59  4566.2  146.47  4604.4  145.61
  4624.5  143.91  4644.5  145.28  4684.5  144.57  4704.5  145.37  4784.1  144.86
  4840.3  144.28  4875.8  144.38  4879.7  143.25    4901  142.82  4950.4  138.81
  4978.7  134.97  4985.7   133.5  4992.8  130.72    4997  130.39  4997.5  129.89
  5002.6  130.39  5028.1  136.04  5042.3  137.91  5070.5  139.84  5103.6  140.08
  5107.6  140.15  5148.5  141.01  5233.9  145.02  5293.9  145.92  5520.7  146.94
#Mann= 8 ,-1 , 0
  4486.8     .12       0  4566.2     .05       0  4784.1     .12       0
  4840.3     .05       0    4997     .05       0  5002.6     .05       0
  5103.6     .12       0  5107.6     .05       0
Bank Sta=4997,5002.6
XS Rating Curve= 0 ,0
Exp/Cntr=0.3,0.1

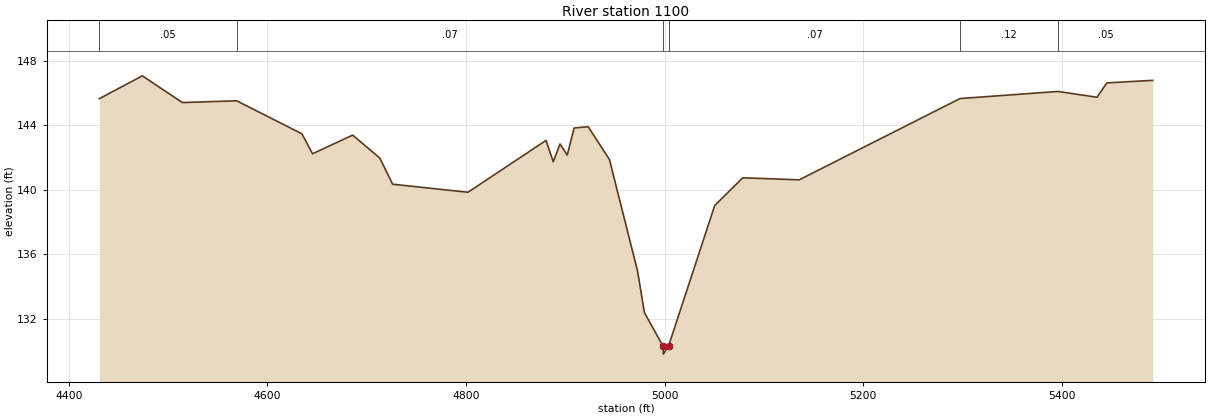
Type RM Length L Ch R = 1 ,1100    ,0,0,0
BEGIN DESCRIPTION:
Mapping XS 1bc9cdaf
END DESCRIPTION:
XS GIS Cut Line= 4
      2530962.71      13513007.9      2531011.32     13512639.82
      2530778.69     13512393.29      2530428.96     13512417.53
#Sta/Elev= 30
  4430.7  145.65    4474  147.07  4514.3  145.41    4569  145.52  4634.7  143.47
  4645.4  142.23  4685.8  143.39  4713.2  141.96  4726.1  140.34  4801.9  139.84
  4880.5  143.06  4887.8  141.73  4894.6  142.84  4901.9  142.15  4908.8  143.83
    4923  143.91  4944.4  141.87  4972.7  134.95  4979.6  132.37  4998.3  130.29
  4998.7  129.79  5003.9  130.29  5050.4  139.02  5078.7  140.74  5135.4  140.61
  5297.5  145.66  5396.2   146.1  5435.3  145.74  5445.3  146.63  5491.5  146.79
#Mann= 6 ,-1 , 0
  4430.7     .05       0    4569     .07       0  4998.3     .05       0
  5003.9     .07       0  5297.5     .12       0  5396.2     .05       0
Bank Sta=4998.3,5003.9
XS Rating Curve= 0 ,0
Exp/Cntr=0.3,0.1

Chan Stop Cuts=-1
Use User Specified Reach Order=0
Composite Channel Slope=5