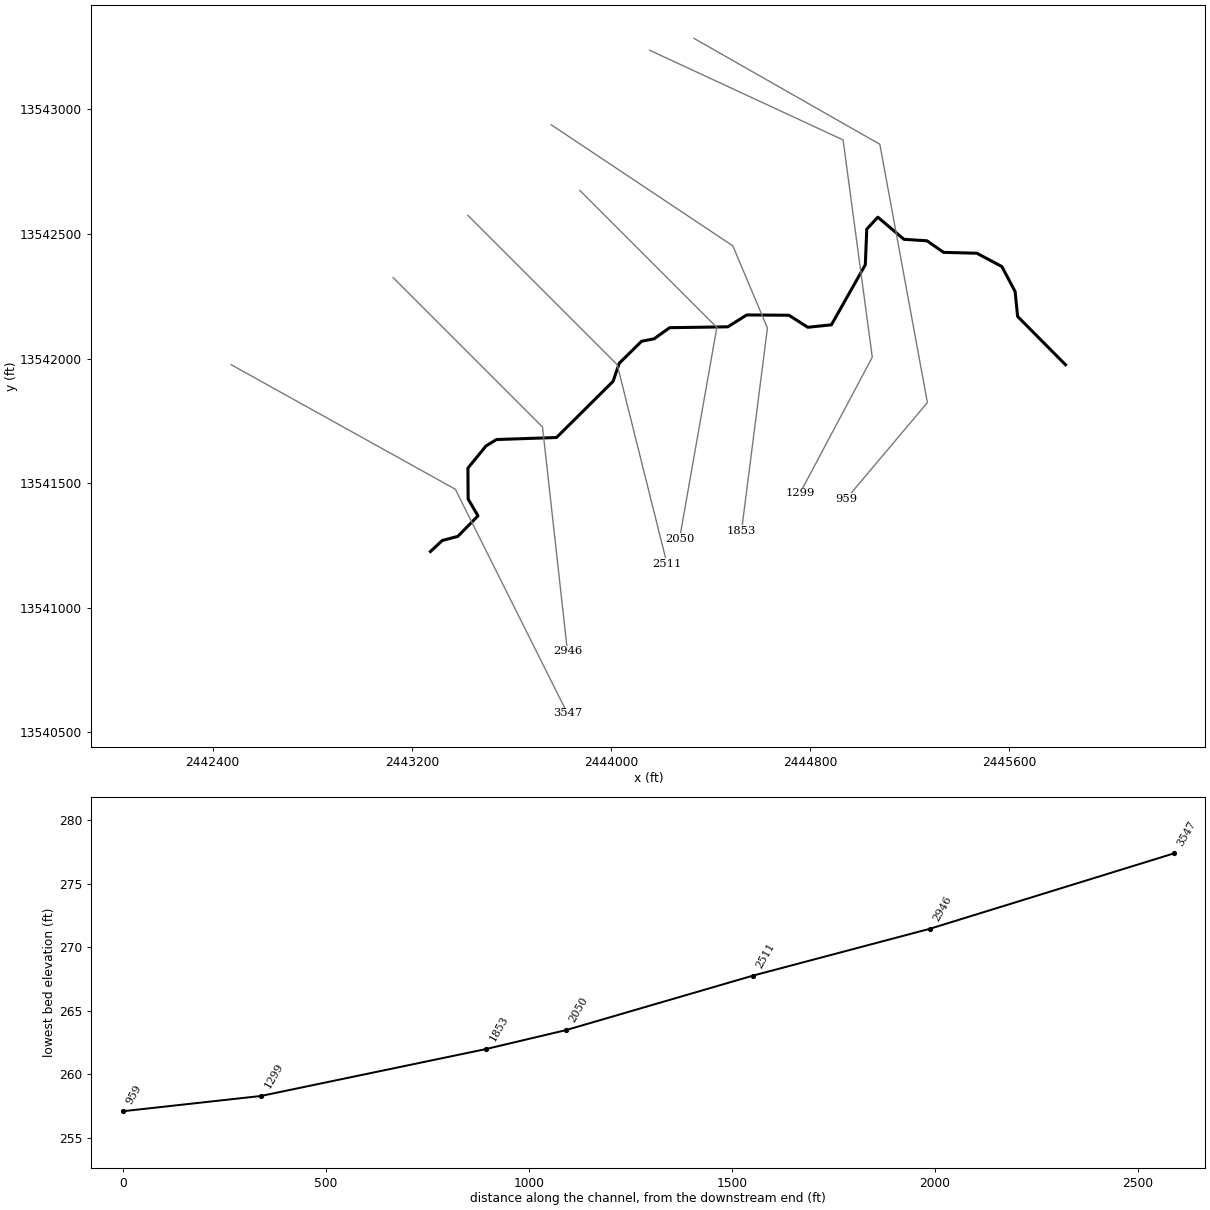
--- TRIB 2 TO YORKTOWN CREEK.prj (project) ---

Proj Title=TRIB 2 TO YORKTOWN CREEK Base Level Engineering
Current Plan=p01
Default Exp/Contr=0.3,0.1
English Units
Geom File=g01
Flow File=f01
Plan File=p01
BEGIN DESCRIPTION:
TRIB 2 TO YORKTOWN CREEK
END DESCRIPTION:

--- TRIB 2 TO YORKTOWN CREEK.p01 (plan) ---

Plan Title=Multiple Run
Short Identifier=Multiple
Geom File=g01
Flow File=f01
Subcritical Flow
K Sum by GR= 0
Std Step Tol= 0.01
Critical Tol= 0.01
Num of Std Step Trials= 20
Max Error Tol= 0.3
Flow Tol Ratio= 0.001
Split Flow NTrial= 30
Split Flow Tol= 0.02
Split Flow Ratio= 0.02
Log Output Level= 0
Friction Slope Method= 1
Unsteady Friction Slope Method= 2
Unsteady Bridges Friction Slope Method= 1
Parabolic Critical Depth
Global Vel Dist=  1 , 1 , 1
Global Log Level= 0
CheckData=True
Encroach Param= -1, 0, 0, 0
BEGIN DESCRIPTION:
Multiple Run
END DESCRIPTION:

--- TRIB 2 TO YORKTOWN CREEK.f01 (steady flow) ---

Flow Title=Multiple
Number of Profiles=7
Profile Names=10-year,25-year,50-year,1pct_min,100-year,1pct_plu,500-year
River Rch & RM= TRIB 2 TO YORKTO,Reach-1,3547
     715    1163    1571    1027    2050    4089    3452
Boundary for River Rch & Prof#=TRIB 2 TO YORKTO,Reach-1,1
Up Type=0
Dn Type=3
Dn Slope=0.005
Boundary for River Rch & Prof#=TRIB 2 TO YORKTO,Reach-1,2
Up Type=0
Dn Type=3
Dn Slope=0.005
Boundary for River Rch & Prof#=TRIB 2 TO YORKTO,Reach-1,3
Up Type=0
Dn Type=3
Dn Slope=0.005
Boundary for River Rch & Prof#=TRIB 2 TO YORKTO,Reach-1,4
Up Type=0
Dn Type=3
Dn Slope=0.005
Boundary for River Rch & Prof#=TRIB 2 TO YORKTO,Reach-1,5
Up Type=0
Dn Type=3
Dn Slope=0.005
Boundary for River Rch & Prof#=TRIB 2 TO YORKTO,Reach-1,6
Up Type=0
Dn Type=3
Dn Slope=0.005
Boundary for River Rch & Prof#=TRIB 2 TO YORKTO,Reach-1,7
Up Type=0
Dn Type=3
Dn Slope=0.005

--- TRIB 2 TO YORKTOWN CREEK.g01 (geometry) ---

Geom Title=Existing Conditions

River Reach=TRIB 2 TO YORKTO,Reach-1
Reach XY= 30
      2443275.00     13541225.00      2443322.65     13541269.29
      2443384.76     13541285.70      2443465.88     13541368.24
      2443426.38     13541435.44      2443425.36     13541559.84
      2443498.06     13541648.86      2443540.15     13541674.62
      2443781.19     13541682.81      2444008.35     13541908.33
      2444033.15     13541981.07      2444122.69     13542069.18
      2444173.25     13542079.22      2444235.50     13542123.80
      2444469.06     13542127.26      2444545.03     13542174.93
      2444714.50     13542173.78      2444790.28     13542125.37
      2444885.11     13542135.30      2445021.24     13542376.56
      2445027.07     13542519.56      2445071.38     13542567.52
      2445176.50     13542478.64      2445269.02     13542472.64
      2445335.51     13542426.23      2445469.09     13542422.76
      2445569.42     13542369.42      2445622.68     13542269.06
      2445632.86     13542168.83      2445825.00     13541975.00

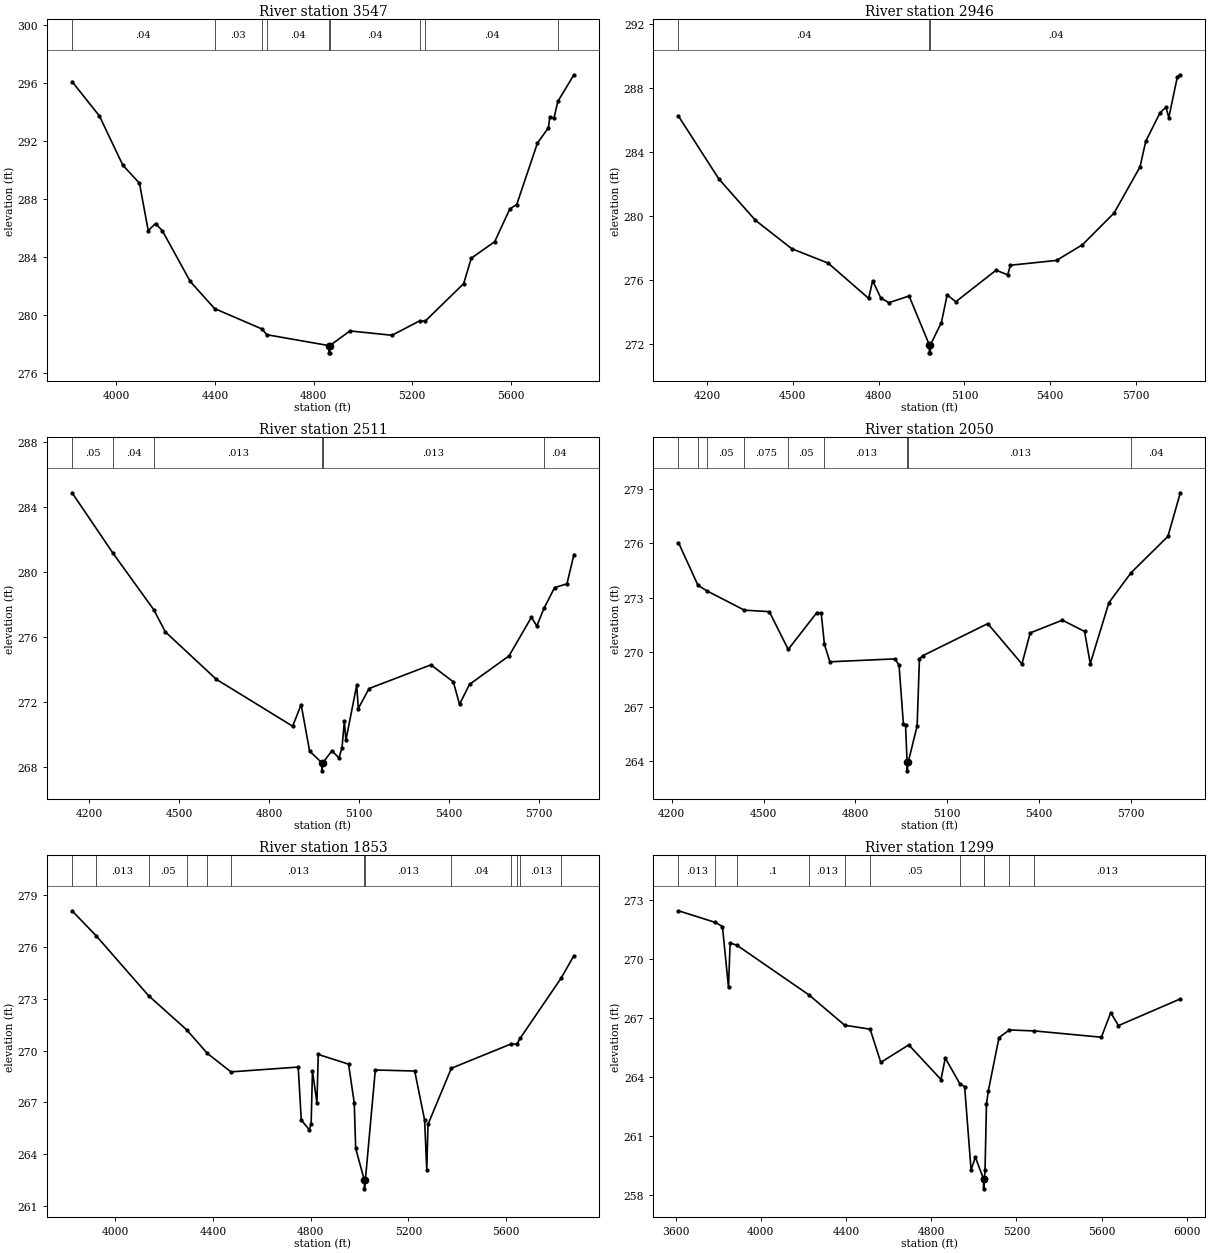
Type RM Length L Ch R = 1,3547,601,601,601
BEGIN DESCRIPTION:
TRIB 2 TO YORKTOWN CREEK 5.0
END DESCRIPTION:
XS GIS Cut Line= 3
      2442474.98     13541975.01      2443375.00     13541475.00
      2443824.99     13540575.02
#Sta/Elev= 30
  3820.6  296.07  3931.6  293.70  4026.5  290.31  4094.0  289.07  4129.5  285.80
  4159.2  286.29  4186.7  285.80  4299.9  282.30  4398.6  280.43  4591.6  279.02
  4610.4  278.63  4862.2  277.88  4862.4  277.38  4865.9  277.38  4866.2  277.88
  4948.0  278.89  5118.5  278.59  5230.2  279.58  5253.4  279.57  5409.2  282.15
  5440.0  283.90  5535.0  285.04  5596.5  287.30  5624.4  287.60  5708.3  291.83
  5753.0  292.89  5758.6  293.61  5775.4  293.55  5791.1  294.70  5856.4  296.54
#Mann=9,-1,0
  3820.6    0.04       0  4398.6    0.03       0  4591.6    0.12       0
  4610.4    0.04       0  4862.2    0.04       0  4866.2    0.04       0
  5230.2    0.03       0  5253.4    0.04       0  5791.1   0.013       0
Bank Sta=4862.2,4866.2
Exp/Cntr=0.3,0.1

Type RM Length L Ch R = 1,2946,435,435,435
BEGIN DESCRIPTION:
TRIB 2 TO YORKTOWN CREEK 4.0
END DESCRIPTION:
XS GIS Cut Line= 3
      2443125.00     13542325.00      2443725.00     13541725.00
      2443825.00     13540824.96
#Sta/Elev= 30
  4100.7  286.23  4242.1  282.30  4369.4  279.73  4496.7  277.95  4624.0  277.05
  4765.4  274.85  4779.5  275.95  4807.8  274.88  4836.1  274.58  4906.8  275.00
  4977.4  271.95  4977.7  271.45  4981.2  271.45  4981.4  271.95  5019.7  273.34
  5039.8  275.07  5070.0  274.64  5210.8  276.61  5251.1  276.32  5261.1  276.92
  5422.1  277.22  5512.7  278.20  5623.3  280.18  5713.9  283.06  5734.0  284.66
  5784.3  286.45  5804.5  286.78  5814.5  286.14  5844.7  288.70  5854.8  288.81
#Mann=3,-1,0
  4100.7    0.04       0  4977.4    0.04       0  4981.4    0.04       0
Bank Sta=4977.4,4981.4
Exp/Cntr=0.3,0.1

Type RM Length L Ch R = 1,2511,461,461,461
BEGIN DESCRIPTION:
TRIB 2 TO YORKTOWN CREEK 3.0
END DESCRIPTION:
XS GIS Cut Line= 3
      2443425.01     13542574.99      2444025.00     13541975.00
      2444224.99     13541175.03
#Sta/Elev= 30
  4143.0  284.90  4279.7  281.17  4415.2  277.70  4454.1  276.33  4623.8  273.41
  4878.4  270.52  4906.7  271.85  4934.9  268.99  4975.4  268.27  4975.6  267.77
  4979.4  268.27  5009.5  269.01  5032.7  268.56  5043.0  269.19  5050.8  270.86
  5055.9  269.65  5092.0  273.05  5097.2  271.61  5133.2  272.84  5339.4  274.30
  5414.1  273.25  5434.7  271.87  5468.2  273.10  5599.7  274.85  5674.4  277.23
  5692.4  276.69  5716.2  277.78  5751.7  279.06  5792.9  279.29  5816.1  281.09
#Mann=6,-1,0
  4143.0    0.05       0  4279.7    0.04       0  4415.2   0.013       0
  4975.4    0.03       0  4979.4   0.013       0  5716.2    0.04       0
Bank Sta=4975.4,4979.4
Exp/Cntr=0.3,0.1

Type RM Length L Ch R = 1,2050,197,197,197
BEGIN DESCRIPTION:
TRIB 2 TO YORKTOWN CREEK 2.0
END DESCRIPTION:
XS GIS Cut Line= 3
      2443875.02     13542674.98      2444425.00     13542125.00
      2444275.00     13541275.03
#Sta/Elev= 30
  4221.8  276.04  4285.5  273.69  4315.1  273.38  4437.5  272.32  4518.8  272.24
  4580.6  270.16  4674.3  272.19  4688.5  272.15  4699.0  270.44  4716.8  269.48
  4928.9  269.64  4943.0  269.30  4957.2  266.06  4964.2  266.00  4969.3  263.98
  4969.6  263.48  4973.3  263.98  5002.1  265.95  5009.7  269.65  5019.9  269.81
  5233.1  271.58  5344.8  269.36  5371.9  271.07  5476.9  271.77  5549.6  271.15
  5568.2  269.38  5629.2  272.73  5701.5  274.38  5822.1  276.38  5862.7  278.78
#Mann=9,-1,0
  4221.8    0.05       0  4285.5   0.013       0  4315.1    0.05       0
  4437.5   0.075       0  4580.6    0.05       0  4699.0   0.013       0
  4969.3    0.03       0  4973.3   0.013       0  5701.5    0.04       0
Bank Sta=4969.3,4973.3
Exp/Cntr=0.3,0.1

Type RM Length L Ch R = 1,1853,554,554,554
BEGIN DESCRIPTION:
Mapping XS 0a22926d
END DESCRIPTION:
XS GIS Cut Line= 4
      2443760.05     13542938.47      2444489.26     13542452.33
      2444628.15     13542122.47      2444524.21     13541308.29
#Sta/Elev= 30
  3822.9  278.11  3921.0  276.67  4136.0  273.19  4291.5  271.22  4377.0  269.84
  4473.7  268.77  4749.0  269.05  4761.5  265.98  4794.1  265.42  4801.9  265.75
  4807.3  268.82  4825.6  266.98  4831.0  269.78  4955.1  269.22  4978.5  266.96
  4984.3  264.33  5019.9  262.49  5020.2  261.99  5023.9  262.49  5064.7  268.88
  5226.0  268.82  5266.4  265.99  5275.4  263.11  5280.5  265.73  5376.0  268.98
  5618.9  270.38  5644.0  270.38  5658.0  270.72  5825.8  274.21  5878.0  275.51
#Mann=13,-1,0
  3822.9    0.05       0  3921.0   0.013       0  4136.0    0.05       0
  4291.5   0.075       0  4377.0    0.05       0  4473.7   0.013       0
  5019.9    0.03       0  5023.9   0.013       0  5376.0    0.04       0
  5618.9   0.013       0  5644.0    0.04       0  5658.0   0.013       0
  5825.8    0.04       0
Bank Sta=5019.9,5023.9
Exp/Cntr=0.3,0.1

Type RM Length L Ch R = 1,1299,340,340,340
BEGIN DESCRIPTION:
Mapping XS b4917fdb
END DESCRIPTION:
XS GIS Cut Line= 4
      2444155.06     13543237.92      2444931.97     13542877.68
      2445049.15     13542005.29      2444758.34     13541458.39
#Sta/Elev= 30
  3613.7  272.44  3786.1  271.85  3820.1  271.64  3848.6  268.54  3856.1  270.80
  3887.8  270.69  4226.4  268.16  4394.1  266.62  4513.4  266.42  4563.6  264.73
  4694.7  265.62  4846.1  263.86  4866.3  264.95  4934.8  263.64  4957.1  263.50
  4987.3  259.26  5007.5  259.91  5045.9  258.80  5046.1  258.30  5049.9  258.80
  5052.9  259.25  5059.6  262.60  5068.1  263.27  5118.5  265.99  5167.1  266.38
  5285.1  266.33  5599.1  266.01  5643.1  267.26  5679.1  266.60  5969.7  267.96
#Mann=11,-1,0
  3613.7   0.013       0  3786.1    0.05       0  3887.8     0.1       0
  4226.4   0.013       0  4394.1     0.1       0  4513.4    0.05       0
  4934.8   0.013       0  5045.9    0.03       0  5049.9   0.013       0
  5167.1    0.05       0  5285.1   0.013       0
Bank Sta=5045.9,5049.9
Exp/Cntr=0.3,0.1

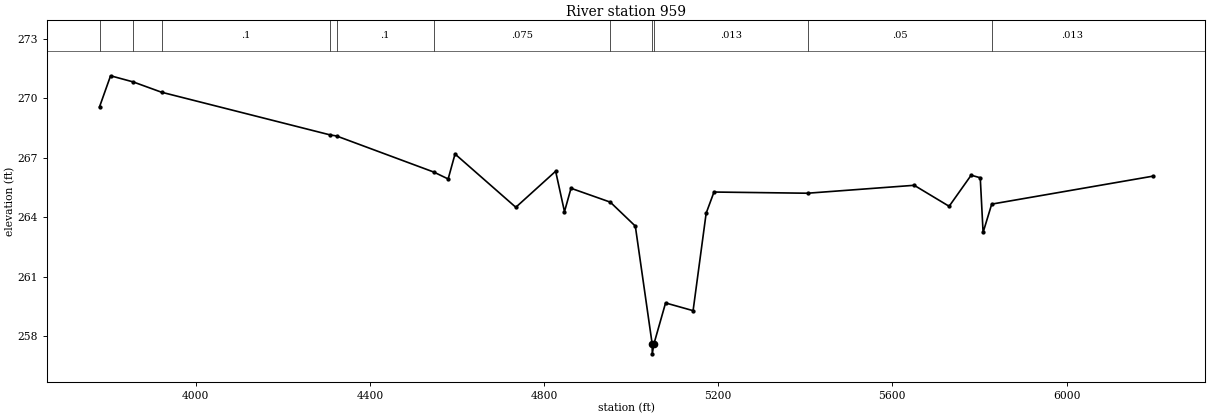
Type RM Length L Ch R = 1,959,0,0,0
BEGIN DESCRIPTION:
Mapping XS 36ca8092
END DESCRIPTION:
XS GIS Cut Line= 4
      2444332.97     13543285.69      2445079.54     13542860.32
      2445270.51     13541822.99      2444944.96     13541436.67
#Sta/Elev= 30
  3778.9  269.57  3804.3  271.14  3856.2  270.83  3921.3  270.31  4307.6  268.16
  4323.4  268.10  4546.5  266.28  4579.7  265.93  4595.5  267.19  4735.1  264.50
  4826.6  266.32  4846.9  264.28  4861.9  265.46  4952.1  264.76  5009.6  263.55
  5048.3  257.60  5048.5  257.10  5052.3  257.60  5079.1  259.67  5142.3  259.28
  5172.3  264.20  5190.3  265.27  5405.2  265.21  5650.2  265.61  5730.4  264.55
  5781.0  266.12  5801.9  265.99  5808.4  263.23  5828.2  264.66  6198.1  266.07
#Mann=11,-1,0
  3778.9   0.013       0  3856.2    0.05       0  3921.3     0.1       0
  4307.6   0.013       0  4323.4     0.1       0  4546.5   0.075       0
  4952.1   0.013       0  5048.3    0.03       0  5052.3   0.013       0
  5405.2    0.05       0  5828.2   0.013       0
Bank Sta=5048.3,5052.3
Exp/Cntr=0.3,0.1

Chan Stop Cuts=-1