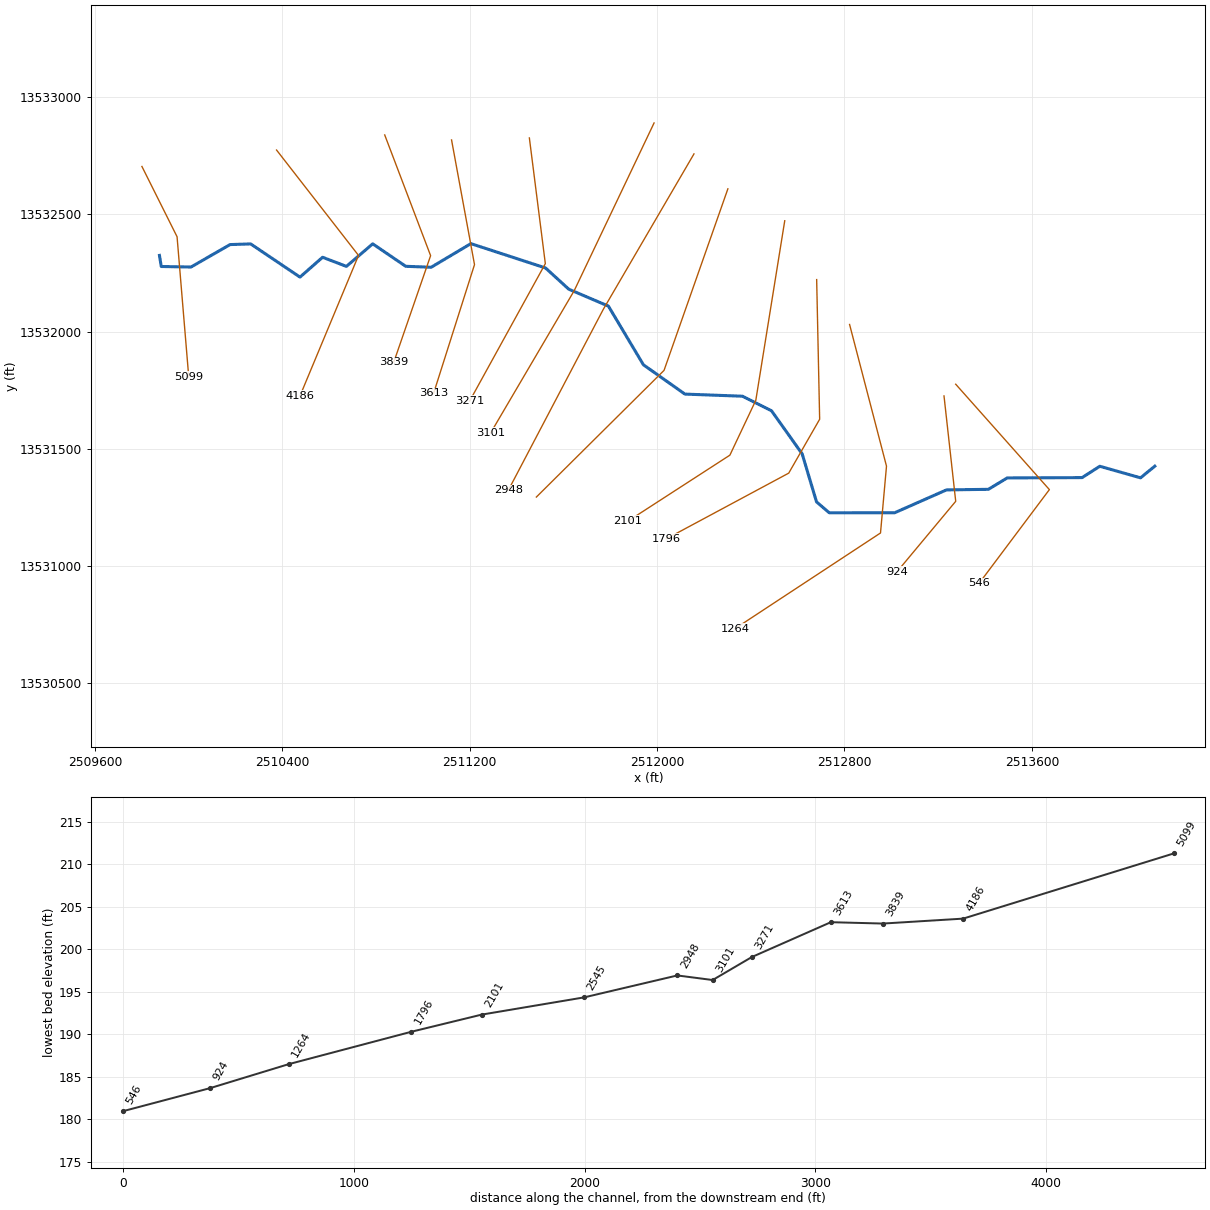
--- TRIB 3 TO BOGGY BRANCH.prj (project) ---

Proj Title=TRIB 3 TO BOGGY BRANCH Base Level Engineering
Current Plan=p01
Default Exp/Contr=0.3,0.1
English Units
Geom File=g01
Flow File=f01
Plan File=p01
BEGIN DESCRIPTION:
TRIB 3 TO BOGGY BRANCH
END DESCRIPTION:

--- TRIB 3 TO BOGGY BRANCH.p01 (plan) ---

Plan Title=Multiple Run
Short Identifier=Multiple
Geom File=g01
Flow File=f01
Subcritical Flow
K Sum by GR= 0
Std Step Tol= 0.01
Critical Tol= 0.01
Num of Std Step Trials= 20
Max Error Tol= 0.3
Flow Tol Ratio= 0.001
Split Flow NTrial= 30
Split Flow Tol= 0.02
Split Flow Ratio= 0.02
Log Output Level= 0
Friction Slope Method= 1
Unsteady Friction Slope Method= 2
Unsteady Bridges Friction Slope Method= 1
Parabolic Critical Depth
Global Vel Dist=  1 , 1 , 1
Global Log Level= 0
CheckData=True
Encroach Param= -1, 0, 0, 0
BEGIN DESCRIPTION:
Multiple Run
END DESCRIPTION:

--- TRIB 3 TO BOGGY BRANCH.f01 (steady flow) ---

Flow Title=Multiple
Number of Profiles=7
Profile Names=10-year,25-year,50-year,1pct_min,100-year,1pct_plu,500-year
River Rch & RM= TRIB 3 TO BOGGY ,Reach-1,5099
     422     659     867     553    1103    2201    1764
River Rch & RM= TRIB 3 TO BOGGY ,Reach-1,2948
     511     805    1064     682    1360    2714    2195
Boundary for River Rch & Prof#=TRIB 3 TO BOGGY ,Reach-1,1
Up Type=0
Dn Type=3
Dn Slope=0.005
Boundary for River Rch & Prof#=TRIB 3 TO BOGGY ,Reach-1,2
Up Type=0
Dn Type=3
Dn Slope=0.005
Boundary for River Rch & Prof#=TRIB 3 TO BOGGY ,Reach-1,3
Up Type=0
Dn Type=3
Dn Slope=0.005
Boundary for River Rch & Prof#=TRIB 3 TO BOGGY ,Reach-1,4
Up Type=0
Dn Type=3
Dn Slope=0.005
Boundary for River Rch & Prof#=TRIB 3 TO BOGGY ,Reach-1,5
Up Type=0
Dn Type=3
Dn Slope=0.005
Boundary for River Rch & Prof#=TRIB 3 TO BOGGY ,Reach-1,6
Up Type=0
Dn Type=3
Dn Slope=0.005
Boundary for River Rch & Prof#=TRIB 3 TO BOGGY ,Reach-1,7
Up Type=0
Dn Type=3
Dn Slope=0.005

--- TRIB 3 TO BOGGY BRANCH.g01 (geometry) ---

Geom Title=Existing Conditions

River Reach=TRIB 3 TO BOGGY ,Reach-1
Reach XY= 30
      2509875.00     13532325.00      2509882.71     13532277.69
      2510009.78     13532275.48      2510176.59     13532371.33
      2510264.52     13532374.06      2510475.09     13532232.31
      2510571.59     13532317.15      2510673.35     13532278.17
      2510785.64     13532374.44      2510926.47     13532278.54
      2511035.19     13532274.45      2511204.79     13532375.36
      2511523.50     13532271.38      2511622.71     13532180.85
      2511792.05     13532108.51      2511941.50     13531857.95
      2512118.81     13531732.83      2512364.50     13531723.80
      2512488.57     13531661.53      2512619.46     13531477.42
      2512680.71     13531272.41      2512735.28     13531225.98
      2513014.50     13531226.22      2513235.50     13531323.78
      2513414.49     13531326.22      2513495.03     13531374.93
      2513814.50     13531376.22      2513890.27     13531424.62
      2514064.34     13531375.33      2514125.00     13531425.00

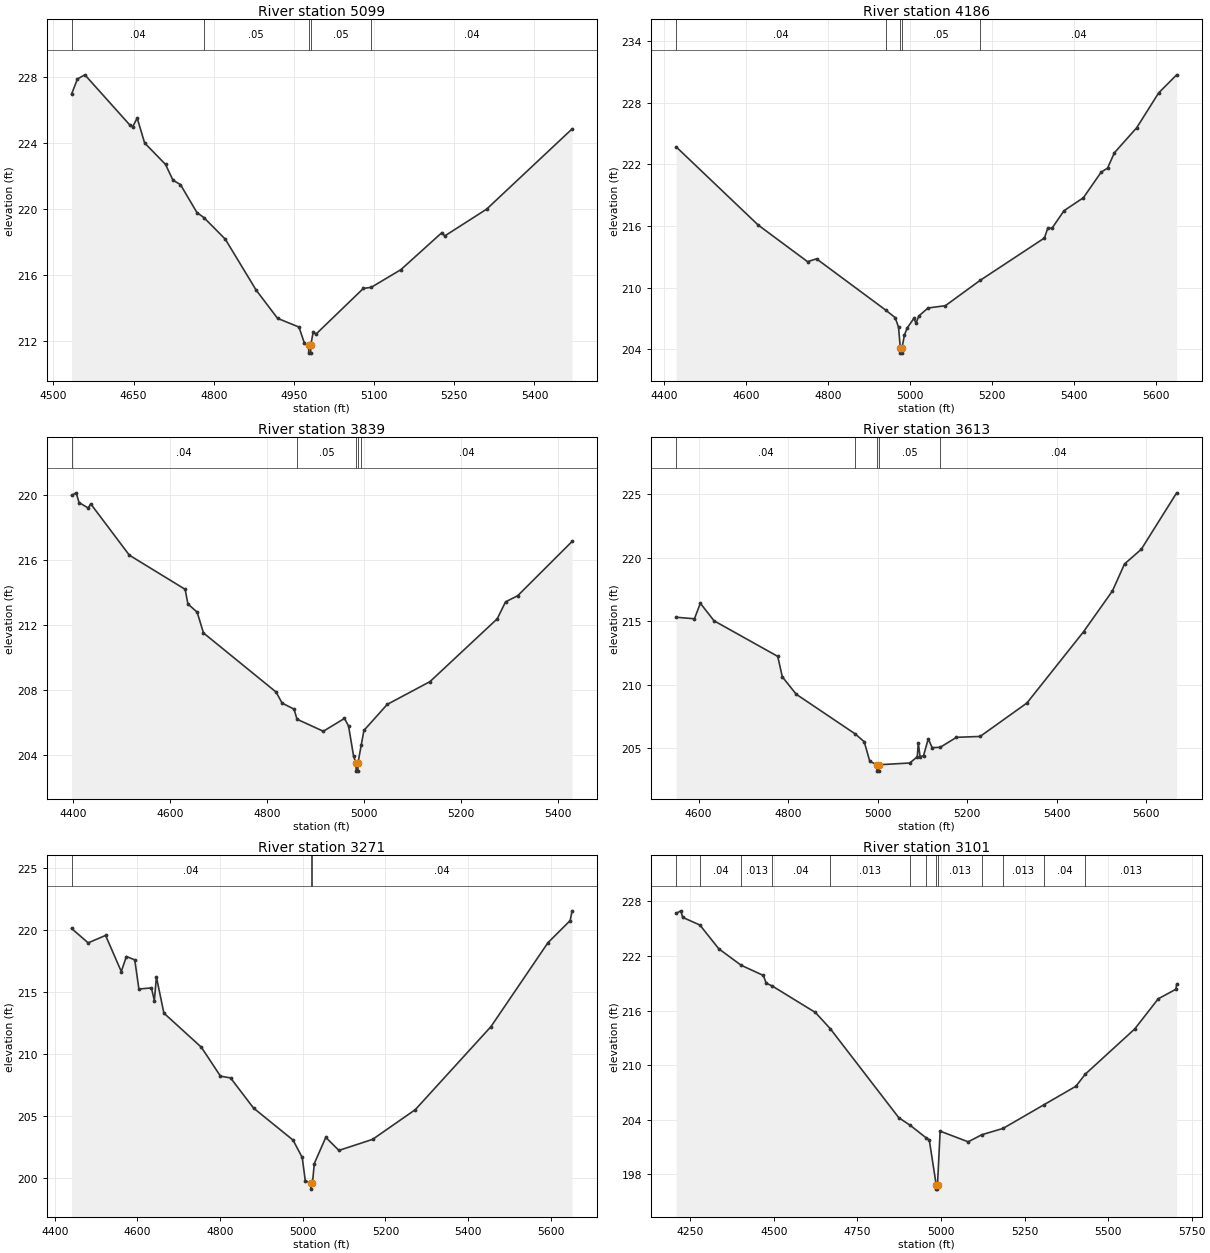
Type RM Length L Ch R = 1,5099,913,913,913
BEGIN DESCRIPTION:
TRIB 3 TO BOGGY BRANCH 10.0
END DESCRIPTION:
XS GIS Cut Line= 3
      2509800.16     13532704.80      2509950.16     13532404.82
      2510000.08     13531805.79
#Sta/Elev= 30
  4533.9  226.99  4544.9  227.91  4558.8  228.16  4642.6  225.13  4648.2  225.01
  4656.7  225.54  4670.6  224.03  4709.7  222.73  4723.7  221.77  4737.6  221.51
  4768.5  219.81  4781.4  219.51  4821.5  218.20  4879.1  215.12  4919.3  213.40
  4959.4  212.87  4969.5  211.90  4977.5  211.79  4977.7  211.29  4981.2  211.29
  4981.5  211.79  4986.2  212.59  4991.2  212.44  5079.8  215.21  5094.7  215.28
  5150.1  216.35  5227.0  218.60  5232.0  218.39  5310.6  220.02  5470.4  224.88
#Mann=5,-1,0
  4533.9    0.04       0  4781.4    0.05       0  4977.5    0.05       0
  4981.5    0.05       0  5094.7    0.04       0
Bank Sta=4977.5,4981.5
Exp/Cntr=0.3,0.1

Type RM Length L Ch R = 1,4186,347,347,347
BEGIN DESCRIPTION:
TRIB 3 TO BOGGY BRANCH 9.0
END DESCRIPTION:
XS GIS Cut Line= 3
      2510374.99     13532775.02      2510725.00     13532325.00
      2510475.00     13531725.01
#Sta/Elev= 30
  4429.9  223.71  4629.9  216.09  4750.3  212.52  4772.0  212.80  4940.8  207.80
  4963.8  207.07  4972.0  206.13  4976.3  204.11  4976.5  203.61  4980.0  203.61
  4980.3  204.11  4986.4  205.38  4992.8  206.04  5009.2  206.99  5014.6  206.55
  5021.7  207.24  5043.9  208.01  5086.1  208.23  5170.5  210.69  5327.7  214.83
  5335.8  215.80  5346.1  215.78  5375.4  217.49  5422.5  218.75  5465.8  221.24
  5481.5  221.64  5498.3  223.14  5552.5  225.57  5606.1  228.97  5650.0  230.73
#Mann=5,-1,0
  4429.9    0.04       0  4940.8    0.05       0  4976.3    0.05       0
  4980.3    0.05       0  5170.5    0.04       0
Bank Sta=4976.3,4980.3
Exp/Cntr=0.3,0.1

Type RM Length L Ch R = 1,3839,226,226,226
BEGIN DESCRIPTION:
Mapping XS adf4541b
END DESCRIPTION:
XS GIS Cut Line= 3
      2510836.86     13532839.45      2511032.82     13532324.00
      2510875.51     13531869.08
#Sta/Elev= 30
  4396.2  219.97  4405.7  220.13  4411.7  219.53  4430.4  219.20  4435.8  219.45
  4515.4  216.30  4630.6  214.20  4636.3  213.30  4655.3  212.80  4668.4  211.52
  4818.2  207.89  4830.7  207.21  4855.3  206.84  4861.4  206.22  4915.7  205.48
  4959.4  206.27  4967.8  205.80  4978.3  203.93  4983.2  203.53  4983.5  203.03
  4987.0  203.03  4987.2  203.53  4993.9  204.62  4999.5  205.53  5047.6  207.13
  5135.8  208.53  5274.6  212.39  5291.7  213.43  5316.9  213.81  5429.0  217.14
#Mann=5,-1,0
  4396.2    0.04       0  4861.4    0.05       0  4983.2    0.04       0
  4987.2    0.05       0  4993.9    0.04       0
Bank Sta=4983.2,4987.2
Exp/Cntr=0.3,0.1

Type RM Length L Ch R = 1,3613,342,342,342
BEGIN DESCRIPTION:
Mapping XS f8f3da32
END DESCRIPTION:
XS GIS Cut Line= 3
      2511122.26     13532818.15      2511220.24     13532285.67
      2511045.60     13531736.18
#Sta/Elev= 30
  4549.8  215.30  4590.6  215.18  4603.8  216.40  4634.4  215.02  4776.7  212.22
  4786.9  210.61  4818.0  209.24  4949.7  206.12  4969.9  205.50  4982.3  203.96
  4998.4  203.69  4998.6  203.19  5002.1  203.19  5002.4  203.69  5071.6  203.83
  5088.4  204.32  5090.6  205.42  5094.6  204.32  5102.4  204.41  5112.9  205.73
  5121.6  205.04  5139.4  205.06  5175.9  205.85  5228.8  205.92  5333.3  208.55
  5459.8  214.16  5524.3  217.37  5551.3  219.49  5588.8  220.65  5667.8  225.09
#Mann=5,-1,0
  4549.8    0.04       0  4949.7    0.05       0  4998.4    0.05       0
  5002.4    0.05       0  5139.4    0.04       0
Bank Sta=4998.4,5002.4
Exp/Cntr=0.3,0.1

Type RM Length L Ch R = 1,3271,170,170,170
BEGIN DESCRIPTION:
Mapping XS a21939fc
END DESCRIPTION:
XS GIS Cut Line= 3
      2511454.51     13532826.64      2511522.67     13532289.93
      2511199.47     13531703.07
#Sta/Elev= 30
  4440.7  220.09  4480.9  218.93  4523.0  219.53  4561.0  216.62  4573.4  217.83
  4593.6  217.56  4603.6  215.21  4633.9  215.30  4641.0  214.28  4646.0  216.18
  4664.1  213.27  4754.8  210.52  4801.0  208.19  4825.4  208.05  4881.0  205.62
  4976.6  203.04  4998.8  201.64  5006.2  199.76  5019.6  199.59  5019.9  199.09
  5023.6  199.59  5028.0  201.15  5055.8  203.26  5087.6  202.21  5169.1  203.10
  5272.3  205.49  5455.4  212.18  5593.3  218.94  5647.2  220.73  5651.7  221.51
#Mann=3,-1,0
  4440.7    0.04       0  5019.6    0.04       0  5023.6    0.04       0
Bank Sta=5019.6,5023.6
Exp/Cntr=0.3,0.1

Type RM Length L Ch R = 1,3101,153,153,153
BEGIN DESCRIPTION:
Mapping XS 51c61dd9
END DESCRIPTION:
XS GIS Cut Line= 3
      2511986.98     13532890.56      2511646.20     13532174.92
      2511289.19     13531567.16
#Sta/Elev= 30
  4207.7  226.68  4221.7  226.96  4227.2  226.24  4278.7  225.40  4335.2  222.79
  4402.1  220.98  4468.6  219.86  4477.0  219.01  4494.7  218.71  4624.3  215.79
  4668.5  214.02  4874.0  204.22  4907.7  203.40  4955.4  202.02  4964.9  201.81
  4985.6  196.88  4985.8  196.38  4989.3  196.38  4989.6  196.88  4997.5  202.75
  5081.4  201.58  5122.3  202.36  5185.7  203.05  5307.5  205.64  5403.9  207.69
  5431.4  209.00  5579.7  213.98  5649.9  217.29  5702.8  218.34  5705.2  218.90
#Mann=13,-1,0
  4207.7   0.013       0  4278.7    0.04       0  4402.1   0.013       0
  4494.7    0.04       0  4668.5   0.013       0  4907.7    0.04       0
  4955.4   0.013       0  4985.6    0.03       0  4989.6   0.013       0
  5122.3    0.04       0  5185.7   0.013       0  5307.5    0.04       0
  5431.4   0.013       0
Bank Sta=4985.6,4989.6
Exp/Cntr=0.3,0.1

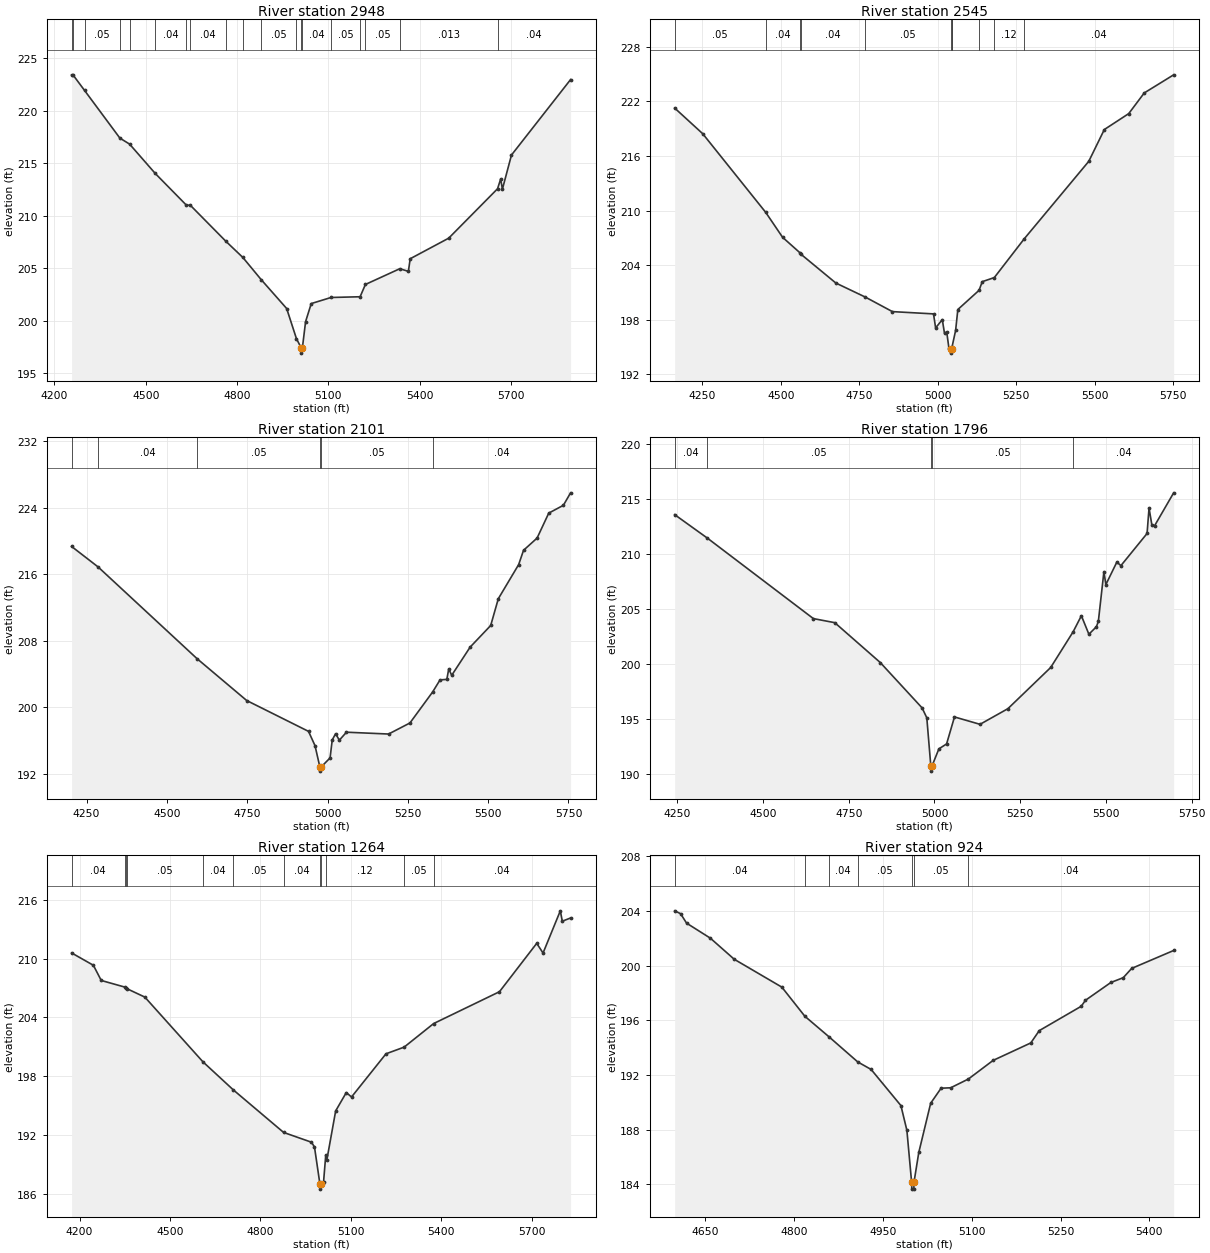
Type RM Length L Ch R = 1,2948,403,403,403
BEGIN DESCRIPTION:
Mapping XS cfbb6c77
END DESCRIPTION:
XS GIS Cut Line= 3
      2512157.34     13532758.46      2511769.72     13532093.98
      2511365.06     13531323.00
#Sta/Elev= 30
  4256.3  223.43  4260.7  223.43  4298.9  221.94  4415.0  217.40  4446.9  216.83
  4531.0  214.04  4633.0  211.03  4647.0  210.99  4763.1  207.58  4819.2  206.03
  4879.1  203.93  4963.1  201.17  4995.1  198.31  5010.8  197.42  5011.1  196.92
  5014.8  197.42  5025.3  199.92  5043.9  201.64  5108.9  202.22  5204.5  202.29
  5221.9  203.46  5334.9  204.96  5363.2  204.71  5369.1  205.91  5495.7  207.87
  5656.3  212.58  5666.5  213.51  5672.2  212.54  5702.0  215.79  5896.3  222.98
#Mann=19,-1,0
  4256.3   0.013       0  4260.7    0.04       0  4298.9    0.05       0
  4415.0    0.04       0  4446.9    0.05       0  4531.0    0.04       0
  4633.0    0.05       0  4647.0    0.04       0  4763.1    0.05       0
  4819.2    0.04       0  4879.1    0.05       0  4995.1    0.04       0
  5010.8    0.04       0  5014.8    0.04       0  5108.9    0.05       0
  5204.5    0.04       0  5221.9    0.05       0  5334.9   0.013       0
  5656.3    0.04       0
Bank Sta=5010.8,5014.8
Exp/Cntr=0.3,0.1

Type RM Length L Ch R = 1,2545,444,444,444
BEGIN DESCRIPTION:
Mapping XS d0add5cc
END DESCRIPTION:
XS GIS Cut Line= 3
      2512302.17     13532609.38      2512029.56     13531834.15
      2511484.35     13531293.20
#Sta/Elev= 30
  4161.9  221.26  4251.3  218.44  4452.0  209.80  4505.8  207.06  4560.8  205.37
  4564.4  205.20  4675.4  202.04  4769.1  200.50  4855.6  198.90  4986.6  198.65
  4993.3  197.11  5014.6  198.02  5021.6  196.51  5028.7  196.66  5035.8  194.85
  5040.9  194.84  5041.1  194.34  5044.9  194.84  5045.5  195.00  5057.0  196.83
  5064.1  199.13  5131.7  201.24  5141.9  202.19  5180.3  202.64  5275.7  206.90
  5481.3  215.41  5530.8  218.90  5608.6  220.65  5658.0  222.92  5751.7  224.91
#Mann=11,-1,0
  4161.9    0.05       0  4452.0    0.04       0  4560.8   0.013       0
  4564.4    0.04       0  4769.1    0.05       0  5040.9    0.05       0
  5044.9    0.05       0  5045.5    0.12       0  5131.7    0.05       0
  5180.3    0.12       0  5275.7    0.04       0
Bank Sta=5040.9,5044.9
Exp/Cntr=0.3,0.1

Type RM Length L Ch R = 1,2101,305,305,305
BEGIN DESCRIPTION:
Mapping XS ed2a9901
END DESCRIPTION:
XS GIS Cut Line= 4
      2512544.97     13532473.10      2512421.44     13531706.36
      2512310.69     13531472.09      2511876.18     13531190.93
#Sta/Elev= 30
  4203.4  219.32  4285.8  216.86  4593.9  205.83  4748.4  200.80  4940.9  197.09
  4961.1  195.37  4976.2  192.81  4976.4  192.31  4980.2  192.81  5008.0  193.90
  5014.7  196.06  5025.2  196.81  5036.8  196.03  5059.0  196.99  5190.1  196.77
  5256.6  198.10  5327.3  201.83  5350.3  203.28  5371.4  203.34  5377.4  204.60
  5386.6  203.83  5444.0  207.22  5508.0  209.82  5531.7  213.04  5595.0  217.14
  5610.2  218.86  5652.4  220.33  5688.7  223.33  5734.2  224.27  5756.7  225.77
#Mann=6,-1,0
  4203.4    0.05       0  4285.8    0.04       0  4593.9    0.05       0
  4976.2    0.05       0  4980.2    0.05       0  5327.3    0.04       0
Bank Sta=4976.2,4980.2
Exp/Cntr=0.3,0.1

Type RM Length L Ch R = 1,1796,532,532,532
BEGIN DESCRIPTION:
Mapping XS 1cd25ee8
END DESCRIPTION:
XS GIS Cut Line= 4
      2512681.28     13532221.76      2512694.05     13531625.43
      2512562.01     13531395.41      2512039.03     13531114.79
#Sta/Elev= 30
  4242.3  213.58  4338.0  211.44  4646.8  204.14  4709.2  203.77  4841.9  200.15
  4963.9  196.03  4977.6  195.13  4989.2  190.79  4989.5  190.29  4993.2  190.79
  5012.8  192.31  5035.3  192.76  5058.3  195.21  5132.8  194.54  5214.1  195.96
  5338.9  199.70  5404.5  202.95  5428.4  204.40  5450.3  202.72  5472.2  203.40
  5477.9  203.89  5494.1  208.40  5499.8  207.23  5531.8  209.27  5543.7  208.95
  5620.0  211.87  5625.7  214.18  5634.0  212.64  5641.9  212.57  5697.5  215.56
#Mann=5,-1,0
  4242.3    0.04       0  4338.0    0.05       0  4989.2    0.05       0
  4993.2    0.05       0  5404.5    0.04       0
Bank Sta=4989.2,4993.2
Exp/Cntr=0.3,0.1

Type RM Length L Ch R = 1,1264,340,340,340
BEGIN DESCRIPTION:
Mapping XS c0614c39
END DESCRIPTION:
XS GIS Cut Line= 4
      2512821.84     13532030.10      2512979.45     13531425.23
      2512953.89     13531139.84      2512331.99     13530730.92
#Sta/Elev= 30
  4173.6  210.59  4245.8  209.33  4271.9  207.78  4349.2  207.11  4354.8  206.99
  4357.1  206.94  4416.6  206.08  4609.4  199.47  4710.0  196.61  4877.1  192.26
  4969.6  191.26  4979.6  190.77  4997.7  186.97  4998.0  186.47  5001.7  186.97
  5009.7  187.20  5017.0  189.95  5020.7  189.47  5049.9  194.46  5085.1  196.33
  5102.5  195.88  5216.9  200.29  5277.1  200.97  5375.1  203.38  5593.5  206.63
  5717.1  211.57  5738.1  210.58  5795.4  214.89  5802.0  213.83  5829.5  214.16
#Mann=12,-1,0
  4173.6    0.04       0  4349.2    0.05       0  4354.8    0.04       0
  4357.1    0.05       0  4609.4    0.04       0  4710.0    0.05       0
  4877.1    0.04       0  4997.7    0.04       0  5001.7    0.04       0
  5017.0    0.12       0  5277.1    0.05       0  5375.1    0.04       0
Bank Sta=4997.7,5001.7
Exp/Cntr=0.3,0.1

Type RM Length L Ch R = 1,924,378,378,378
BEGIN DESCRIPTION:
TRIB 3 TO BOGGY BRANCH 2.0
END DESCRIPTION:
XS GIS Cut Line= 3
      2513225.01     13531724.95      2513275.00     13531275.00
      2513025.02     13530975.03
#Sta/Elev= 30
  4598.0  204.00  4608.0  203.79  4618.1  203.10  4658.3  202.00  4698.6  200.46
  4779.1  198.42  4818.0  196.29  4858.2  194.81  4907.4  192.95  4930.0  192.40
  4980.3  189.76  4990.4  187.95  4998.4  184.15  4998.7  183.65  5002.2  183.65
  5002.4  184.15  5010.5  186.33  5030.6  189.93  5048.2  191.03  5064.4  191.06
  5094.3  191.70  5136.0  193.06  5199.8  194.34  5214.1  195.24  5285.0  197.02
  5292.2  197.46  5335.1  198.76  5356.0  199.11  5370.3  199.79  5441.2  201.10
#Mann=7,-1,0
  4598.0    0.04       0  4818.0    0.05       0  4858.2    0.04       0
  4907.4    0.05       0  4998.4    0.05       0  5002.4    0.05       0
  5094.3    0.04       0
Bank Sta=4998.4,5002.4
Exp/Cntr=0.3,0.1

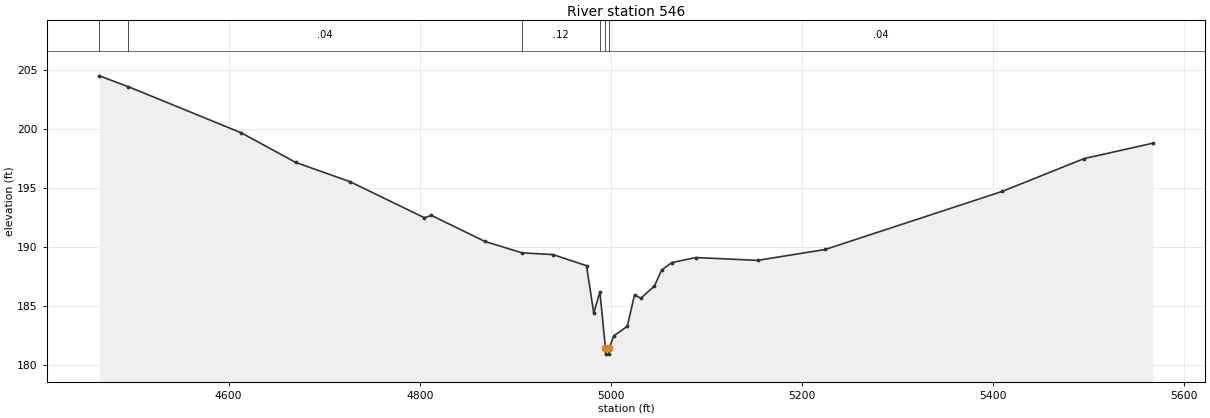
Type RM Length L Ch R = 1,546,0,0,0
BEGIN DESCRIPTION:
TRIB 3 TO BOGGY BRANCH 1.0
END DESCRIPTION:
XS GIS Cut Line= 3
      2513274.97     13531775.04      2513675.00     13531325.00
      2513375.02     13530925.02
#Sta/Elev= 30
  4464.8  204.47  4495.2  203.55  4613.3  199.65  4670.1  197.15  4727.0  195.52
  4804.8  192.47  4812.3  192.66  4868.3  190.46  4906.9  189.50  4939.4  189.35
  4974.5  188.41  4982.1  184.39  4988.5  186.20  4994.3  181.43  4994.5  180.93
  4998.0  180.93  4998.3  181.43  5003.0  182.47  5017.2  183.29  5024.7  185.94
  5031.4  185.66  5045.6  186.70  5053.1  188.04  5063.6  188.67  5088.8  189.10
  5153.4  188.86  5224.2  189.78  5409.6  194.70  5495.1  197.47  5566.9  198.77
#Mann=6,-1,0
  4464.8    0.05       0  4495.2    0.04       0  4906.9    0.12       0
  4988.5    0.04       0  4994.3    0.04       0  4998.3    0.04       0
Bank Sta=4994.3,4998.3
Exp/Cntr=0.3,0.1

Chan Stop Cuts=-1