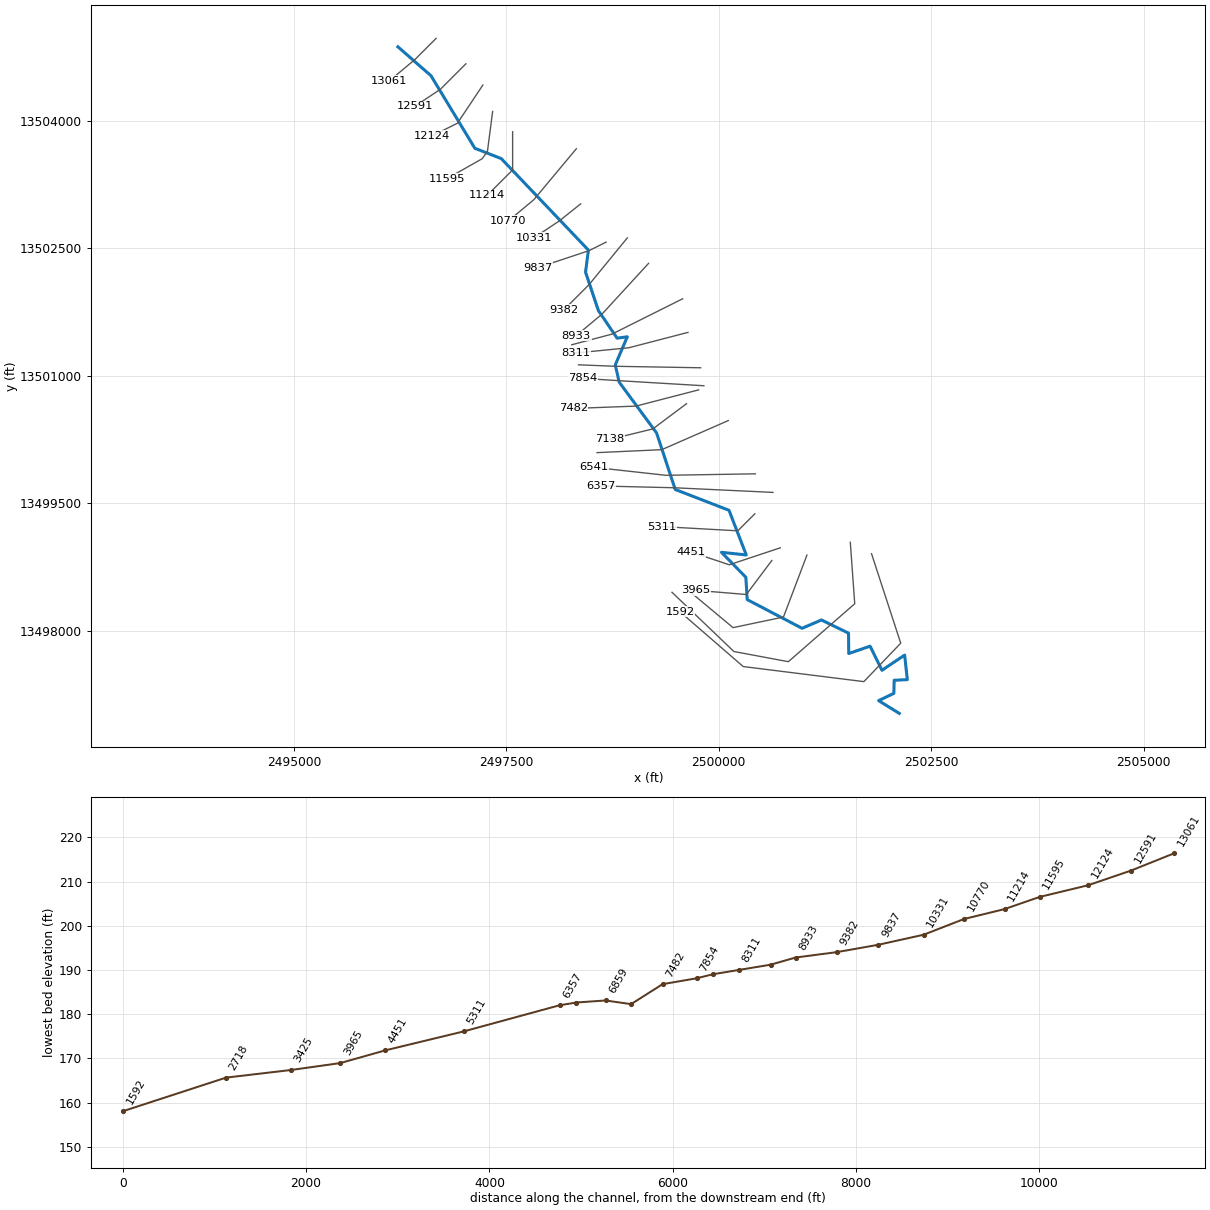
--- TRIB 3 TO EIGHTEENMILE CREEK.prj (project) ---

Proj Title=TRIB 3 TO EIGHTEENMILE CREEK Base Level Engineering
Current Plan=p01
Default Exp/Contr=0.3,0.1
English Units
Geom File=g01
Flow File=f01
Plan File=p01
Y Axis Title=Elevation
X Axis Title(PF)=Main Channel Distance
X Axis Title(XS)=Station
BEGIN DESCRIPTION:
TRIB 3 TO EIGHTEENMILE CREEK
END DESCRIPTION:
DSS Export Rating Curves= 0
DSS Export Rating Curve Sorted= 0
DSS Export Volume Flow Curves= 0
DXF OffsetX= 0
DXF OffsetY= 0
DXF ScaleX= 1
DXF ScaleY= 10

--- TRIB 3 TO EIGHTEENMILE CREEK.p01 (plan) ---

Plan Title=Multiple Run
Short Identifier=Multiple
Geom File=g01
Flow File=f01
Subcritical Flow
K Sum by GR= 0
Std Step Tol= 0.01
Critical Tol= 0.01
Num of Std Step Trials= 20
Max Error Tol= 0.3
Flow Tol Ratio= 0.001
Split Flow NTrial= 30
Split Flow Tol= 0.02
Split Flow Ratio= 0.02
Log Output Level= 0
Friction Slope Method= 1
Unsteady Friction Slope Method= 2
Unsteady Bridges Friction Slope Method= 1
Parabolic Critical Depth
Global Vel Dist=  1 , 1 , 1
Global Log Level= 0
CheckData=True
Encroach Param= -1, 0, 0, 0
BEGIN DESCRIPTION:
Multiple Run
END DESCRIPTION:

--- TRIB 3 TO EIGHTEENMILE CREEK.f01 (steady flow) ---

Flow Title=Multiple
Number of Profiles=7
Profile Names=10-year,25-year,50-year,1pct_min,100-year,1pct_plu,500-year
River Rch & RM= TRIB 3 TO EIGHTE,Reach-1,13061
     315     485     631     399     797    1589    1251
River Rch & RM= TRIB 3 TO EIGHTE,Reach-1,12591
     608     974    1302     843    1682    3356    2774
River Rch & RM= TRIB 3 TO EIGHTE,Reach-1,7482
     768    1244    1676    1092    2178    4346    3642
Boundary for River Rch & Prof#=TRIB 3 TO EIGHTE,Reach-1,1
Up Type=0
Dn Type=3
Dn Slope=0.005
Boundary for River Rch & Prof#=TRIB 3 TO EIGHTE,Reach-1,2
Up Type=0
Dn Type=3
Dn Slope=0.005
Boundary for River Rch & Prof#=TRIB 3 TO EIGHTE,Reach-1,3
Up Type=0
Dn Type=3
Dn Slope=0.005
Boundary for River Rch & Prof#=TRIB 3 TO EIGHTE,Reach-1,4
Up Type=0
Dn Type=3
Dn Slope=0.005
Boundary for River Rch & Prof#=TRIB 3 TO EIGHTE,Reach-1,5
Up Type=0
Dn Type=3
Dn Slope=0.005
Boundary for River Rch & Prof#=TRIB 3 TO EIGHTE,Reach-1,6
Up Type=0
Dn Type=3
Dn Slope=0.005
Boundary for River Rch & Prof#=TRIB 3 TO EIGHTE,Reach-1,7
Up Type=0
Dn Type=3
Dn Slope=0.005

--- TRIB 3 TO EIGHTEENMILE CREEK.g01 (geometry) ---

Geom Title=Existing Conditions
Program Version=4.10

River Reach=TRIB 3 TO EIGHTE,Reach-1
Reach XY= 30
        2496225.       13504875.      2496614.22     13504534.68
      2497130.47     13503680.26      2497441.68     13503558.36
      2498466.88     13502481.05      2498433.06     13502221.71
      2498584.31     13501768.34      2498804.59     13501444.14
      2498924.34     13501459.72      2498782.79     13501128.42
      2498828.76     13500926.56      2499269.17      13500327.3
      2499488.62     13499661.76       2500121.5     13499416.54
      2500324.46      13498890.5      2500032.76       13498922.
      2500319.66     13498627.74      2500335.47     13498365.17
       2500980.9     13498026.97      2501209.64     13498125.11
      2501528.02     13497969.53      2501530.41     13497730.11
      2501782.06     13497816.03      2501921.65     13497532.58
       2502188.8     13497711.66      2502219.55     13497421.99
      2502064.89     13497414.93      2502061.63     13497261.21
      2501881.97     13497175.23        2502125.       13497025.

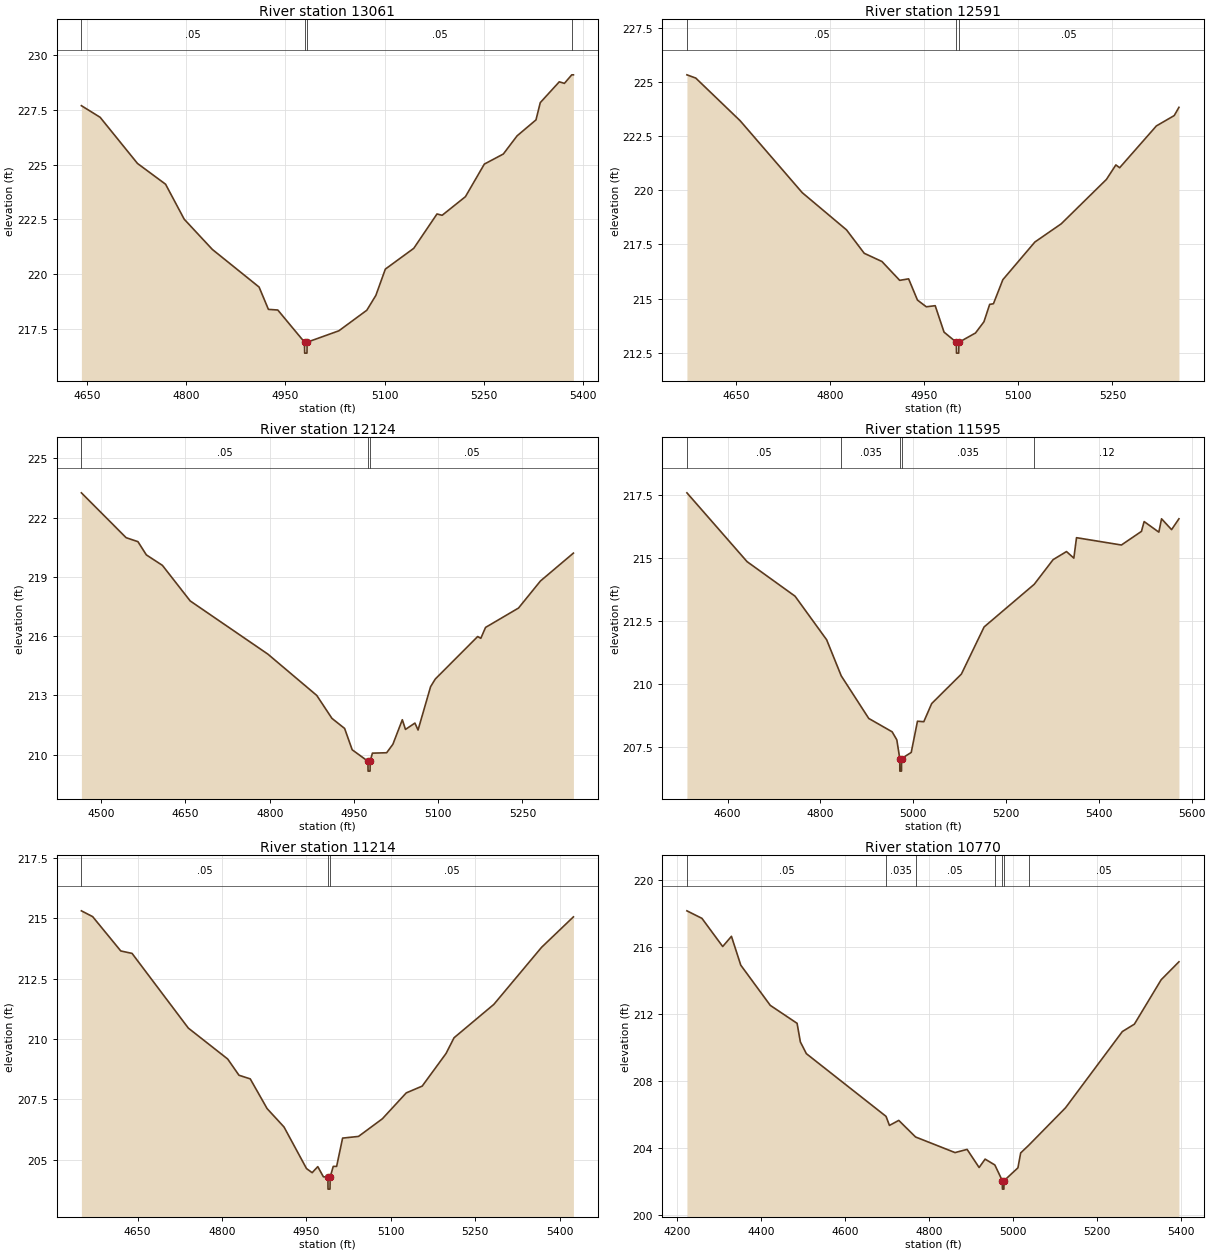
Type RM Length L Ch R = 1 ,13061   ,470,470,470
BEGIN DESCRIPTION:
TRIB 3 TO EIGHTEENMILE CREEK 21.0
END DESCRIPTION:
XS GIS Cut Line= 3
      2496674.99     13504974.99        2496425.       13504725.
      2496125.04     13504475.03
#Sta/Elev= 30
  4641.4  227.69  4669.7  227.16  4726.2  225.05  4768.7   224.1  4796.9   222.5
  4839.4  221.12  4910.1   219.4  4924.2  218.38  4938.4  218.35  4978.8  216.88
    4979  216.38  4982.5  216.38  4982.8  216.88  5030.7   217.4    5073  218.34
  5086.7  219.02    5101  220.22    5144  221.17  5179.1  222.74  5186.9  222.68
  5222.1  223.53  5250.7  225.02  5279.4  225.48  5300.2  226.31  5328.8  227.04
  5335.3  227.83    5364  228.78  5371.8  228.71  5382.9   229.1  5385.4   229.1
#Mann= 4 ,-1 , 0
  4641.4     .05       0  4978.8     .05       0  4982.8     .05       0
  5382.9     .12       0
Bank Sta=4978.8,4982.8
XS Rating Curve= 0 ,0
Exp/Cntr=0.3,0.1

Type RM Length L Ch R = 1 ,12591   ,467,467,467
BEGIN DESCRIPTION:
TRIB 3 TO EIGHTEENMILE CREEK 20.0
END DESCRIPTION:
XS GIS Cut Line= 3
        2497025.       13504675.        2496725.       13504375.
      2496425.02     13504175.01
#Sta/Elev= 30
  4571.3  225.33  4585.4  225.18  4656.2  223.21  4755.2  219.89  4825.9  218.17
  4854.1  217.09  4882.4  216.71  4910.7  215.84  4924.9  215.91    4939  214.93
  4953.1  214.62  4967.3  214.67  4981.4  213.45  5001.1  212.98  5001.3  212.48
  5004.8  212.48  5005.1  212.98  5031.6  213.41  5045.1  213.93  5054.2  214.73
  5060.2  214.76  5075.2  215.87  5126.3  217.61  5168.3  218.45  5240.4   220.5
  5255.5  221.17  5261.5  221.04  5320.1  222.97  5348.6  223.45  5356.1  223.83
#Mann= 3 ,-1 , 0
  4571.3     .05       0  5001.1     .05       0  5005.1     .05       0
Bank Sta=5001.1,5005.1
XS Rating Curve= 0 ,0
Exp/Cntr=0.3,0.1

Type RM Length L Ch R = 1 ,12124   ,529,529,529
BEGIN DESCRIPTION:
TRIB 3 TO EIGHTEENMILE CREEK 19.0
END DESCRIPTION:
XS GIS Cut Line= 3
      2497225.02     13504425.03        2496925.       13503975.
      2496624.98     13503824.99
#Sta/Elev= 30
  4464.6  223.25  4544.3  220.98  4565.3  220.78  4580.3  220.11  4608.9  219.58
  4658.4  217.78  4796.7  215.09  4883.8     213  4910.8  211.84  4933.4  211.33
  4946.9  210.25  4974.9  209.67  4975.2  209.17  4978.7  209.17  4978.9  209.67
  4982.9  210.08  5008.3   210.1  5019.4  210.53  5036.2  211.77  5041.8  211.28
  5058.6   211.6  5064.2  211.25  5086.5  213.44  5094.9  213.83  5170.4  215.98
    5176  215.89  5184.4  216.44  5243.1  217.42  5282.2  218.79  5340.9   220.2
#Mann= 3 ,-1 , 0
  4464.6     .05       0  4974.9     .05       0  4978.9     .05       0
Bank Sta=4974.9,4978.9
XS Rating Curve= 0 ,0
Exp/Cntr=0.3,0.1

Type RM Length L Ch R = 1 ,11595   ,381,381,381
BEGIN DESCRIPTION:
Mapping XS bf9196a0
END DESCRIPTION:
XS GIS Cut Line= 4
      2497339.62     13504113.55      2497278.85     13503644.77
      2497218.09     13503557.96      2496799.21     13503320.45
#Sta/Elev= 30
  4512.5  217.57  4642.1  214.84  4745.5  213.47  4813.6  211.74    4845  210.31
  4904.3  208.62  4954.7  208.09  4964.8  207.77  4971.1  207.03  4971.3  206.53
  4974.8  206.53  4975.1  207.03  4995.8  207.27  5009.3  208.51  5022.9  208.49
  5039.9  209.21  5103.9  210.38  5152.9  212.25  5260.8  213.94  5301.6  214.92
  5330.4  215.24  5346.2  214.98    5352  215.79  5448.7   215.5  5491.9  216.04
  5497.7  216.43  5529.4  216.01  5535.2  216.54  5556.8  216.11  5572.7  216.54
#Mann= 5 ,-1 , 0
  4512.5     .05       0    4845    .035       0  4971.1    .035       0
  4975.1    .035       0  5260.8     .12       0
Bank Sta=4971.1,4975.1
XS Rating Curve= 0 ,0
Exp/Cntr=0.3,0.1

Type RM Length L Ch R = 1 ,11214   ,444,444,444
BEGIN DESCRIPTION:
TRIB 3 TO EIGHTEENMILE CREEK 17.0
END DESCRIPTION:
XS GIS Cut Line= 3
        2497575.     13503874.95        2497575.       13503425.
      2497275.01     13503125.01
#Sta/Elev= 30
  4550.1   215.3  4570.1  215.06  4620.1  213.64  4640.1  213.54  4740.1  210.45
  4810.1  209.17  4830.1   208.5  4850.1  208.35  4880.1  207.12  4910.1  206.36
  4950.1  204.64  4960.1  204.47  4970.1  204.72  4980.1   204.3  4988.1  204.29
  4988.3  203.79  4991.8  203.79  4992.1  204.29  4997.6  204.73  5003.6  204.73
  5014.2   205.9  5042.5  205.97  5084.9   206.7  5127.3  207.77  5155.6  208.05
    5198   209.4  5212.2  210.05  5282.9  211.43  5367.7  213.79  5424.3  215.05
#Mann= 3 ,-1 , 0
  4550.1     .05       0  4988.1     .05       0  4992.1     .05       0
Bank Sta=4988.1,4992.1
XS Rating Curve= 0 ,0
Exp/Cntr=0.3,0.1

Type RM Length L Ch R = 1 ,10770   ,439,439,439
BEGIN DESCRIPTION:
TRIB 3 TO EIGHTEENMILE CREEK 16.0
END DESCRIPTION:
XS GIS Cut Line= 3
      2498324.97     13503674.97        2497825.       13503075.
        2497525.       13502825.
#Sta/Elev= 30
  4223.2  218.14    4259  217.69  4308.4  216.01  4329.2  216.62  4351.4   214.9
  4421.7   212.5  4485.5  211.43  4493.3  210.32  4507.6  209.62  4697.3  205.88
  4705.4  205.34  4727.6  205.64  4767.6  204.65  4861.6  203.72  4890.3  203.91
  4918.9  202.83  4933.2  203.33  4956.4  202.98  4974.2  202.04  4974.4  201.54
  4977.9  201.54  4978.2  202.04  5011.3  202.81  5017.9   203.7  5036.8  204.15
  5124.6  206.39    5260  210.94  5288.6  211.38  5352.4  214.03  5394.7   215.1
#Mann= 7 ,-1 , 0
  4223.2     .05       0  4697.3    .035       0  4767.6     .05       0
  4956.4    .035       0  4974.2    .035       0  4978.2    .035       0
  5036.8     .05       0
Bank Sta=4974.2,4978.2
XS Rating Curve= 0 ,0
Exp/Cntr=0.3,0.1

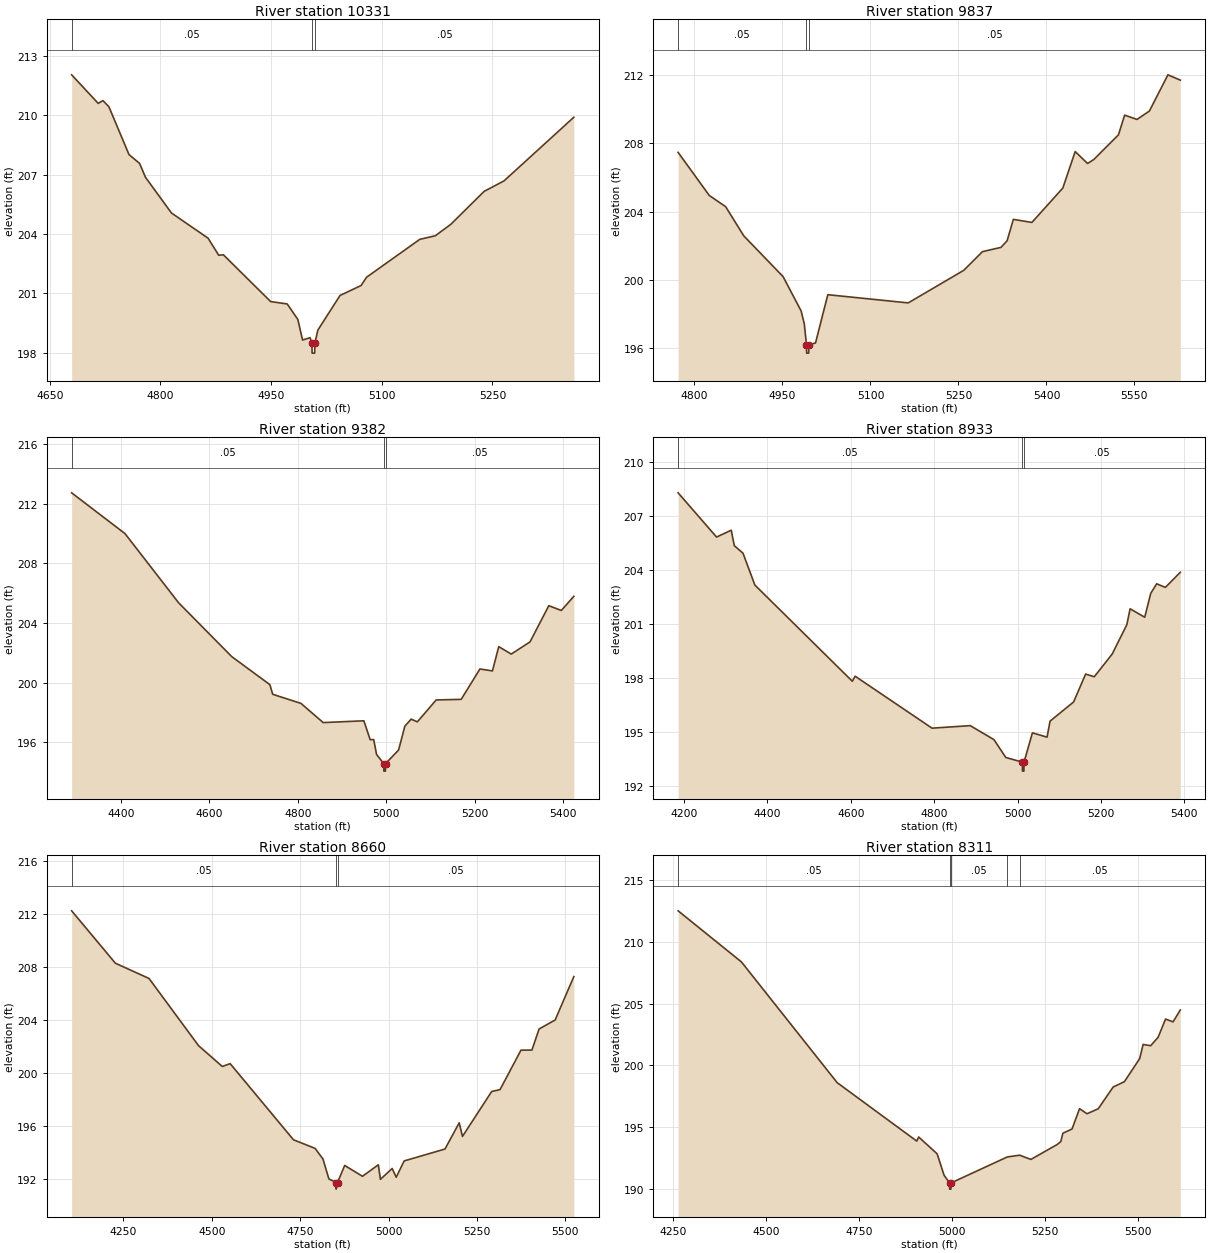
Type RM Length L Ch R = 1 ,10331   ,494,494,494
BEGIN DESCRIPTION:
TRIB 3 TO EIGHTEENMILE CREEK 15.0
END DESCRIPTION:
XS GIS Cut Line= 3
      2498375.02     13503025.02        2498125.       13502825.
      2497825.03     13502625.02
#Sta/Elev= 30
  4679.6  212.03  4715.6  210.59    4722  210.73  4730.1  210.42  4757.3  208.01
  4771.7  207.56  4779.7  206.86  4814.9  205.06  4864.5  203.79  4878.9  202.93
  4885.3  202.95  4949.4  200.59  4971.8  200.47  4986.2  199.69  4992.6  198.65
  5002.8  198.77  5005.3  198.49  5005.5  197.99    5009  197.99  5009.3  198.49
  5013.3  199.15  5043.4   200.9  5071.9   201.4  5079.4  201.82  5151.5  203.73
  5172.5  203.91  5193.6  204.49  5238.7  206.15  5265.7  206.68  5360.3  209.89
#Mann= 3 ,-1 , 0
  4679.6     .05       0  5005.3     .05       0  5009.3     .05       0
Bank Sta=5005.3,5009.3
XS Rating Curve= 0 ,0
Exp/Cntr=0.3,0.1

Type RM Length L Ch R = 1 ,9837    ,455,455,455
BEGIN DESCRIPTION:
TRIB 3 TO EIGHTEENMILE CREEK 14.0
END DESCRIPTION:
XS GIS Cut Line= 3
      2498675.02     13502575.01        2498475.       13502475.
      2497874.98     13502274.99
#Sta/Elev= 30
  4772.1  207.47  4825.2  204.95  4853.2  204.29  4883.9  202.59    4951   200.2
  4981.8  198.19  4987.3  197.41  4990.9  196.22  4991.2  195.72  4994.7  195.72
  4994.9  196.22  5006.3  196.31  5027.3  199.14  5164.4  198.66  5259.2  200.57
  5290.9  201.66  5322.5  201.91    5333   202.3  5343.6  203.55  5375.2  203.37
  5427.9  205.38    5449  207.52  5470.1  206.82  5480.6  207.05  5522.8   208.5
  5533.3  209.65  5554.4   209.4  5575.5  209.89  5607.1  212.01  5628.2   211.7
#Mann= 3 ,-1 , 0
  4772.1     .05       0  4990.9     .05       0  4994.9     .05       0
Bank Sta=4990.9,4994.9
XS Rating Curve= 0 ,0
Exp/Cntr=0.3,0.1

Type RM Length L Ch R = 1 ,9382    ,449,449,449
BEGIN DESCRIPTION:
TRIB 3 TO EIGHTEENMILE CREEK 13.0
END DESCRIPTION:
XS GIS Cut Line= 3
      2498924.99     13502624.99        2498475.       13502075.
      2498174.99     13501774.99
#Sta/Elev= 30
  4288.9  212.74  4409.5     210  4530.8  205.35  4650.7  201.74  4736.8  199.86
  4743.3  199.21  4807.1   198.6  4857.4  197.31  4949.3  197.43  4963.6  196.16
  4971.5  196.17    4978  195.17  4994.3  194.55  4994.5  194.05    4998  194.05
  4998.3  194.55  5027.8  195.47  5041.9  197.07  5056.1  197.54  5070.2  197.36
  5112.7  198.83  5169.2  198.87  5211.6  200.91  5239.9  200.78  5254.1  202.41
  5282.4  201.91  5324.8  202.73  5367.2  205.16  5395.5  204.84  5423.8  205.79
#Mann= 3 ,-1 , 0
  4288.9     .05       0  4994.3     .05       0  4998.3     .05       0
Bank Sta=4994.3,4998.3
XS Rating Curve= 0 ,0
Exp/Cntr=0.3,0.1

Type RM Length L Ch R = 1 ,8933    ,273,273,273
BEGIN DESCRIPTION:
TRIB 3 TO EIGHTEENMILE CREEK 12.0
END DESCRIPTION:
XS GIS Cut Line= 3
      2499175.03     13502325.04        2498625.       13501725.
        2498325.       13501475.
#Sta/Elev= 30
  4185.9  208.31  4278.1  205.85  4313.3  206.23  4320.7  205.37  4341.6  204.95
    4370  203.18  4603.7  197.83  4610.5  198.11  4794.9  195.22  4886.7  195.36
  4943.5  194.58  4971.8  193.59  5011.6  193.33  5011.8  192.83  5015.3  192.83
  5015.6  193.33  5035.7  194.96  5070.8  194.72    5078  195.61  5134.6  196.68
  5163.3  198.23  5184.1  198.08    5227  199.34  5262.2  200.98    5270  201.86
  5305.1  201.39  5319.5  202.72  5333.8  203.25  5354.6  203.05  5390.4  203.89
#Mann= 3 ,-1 , 0
  4185.9     .05       0  5011.6     .05       0  5015.6     .05       0
Bank Sta=5011.6,5015.6
XS Rating Curve= 0 ,0
Exp/Cntr=0.3,0.1

Type RM Length L Ch R = 1 ,8660    ,349,349,349
BEGIN DESCRIPTION:
Mapping XS 470469c8
END DESCRIPTION:
XS GIS Cut Line= 3
      2499576.04     13501907.69      2498742.69     13501491.02
      2498270.46     13501366.02
#Sta/Elev= 30
  4103.7  212.24  4227.5  208.28  4322.5  207.13  4462.6  202.05  4529.7  200.48
  4552.1  200.69    4731  194.94  4792.1  194.29  4814.4  193.49  4831.2  191.98
  4851.6  191.71  4851.8  191.21  4855.6  191.71  4875.9     193  4926.2  192.18
    4971  193.05  4976.9  191.95  5010.1  192.77  5021.6  192.11    5044  193.34
  5159.5  194.24  5199.7  196.22  5208.9  195.19  5291.6  198.59  5315.2  198.73
  5374.4  201.71  5405.4  201.72  5425.6  203.31    5471  203.99  5523.9  207.27
#Mann= 3 ,-1 , 0
  4103.7     .05       0  4851.6     .05       0  4855.6     .05       0
Bank Sta=4851.6,4855.6
XS Rating Curve= 0 ,0
Exp/Cntr=0.3,0.1

Type RM Length L Ch R = 1 ,8311    ,275,275,275
BEGIN DESCRIPTION:
Mapping XS 6b995364
END DESCRIPTION:
XS GIS Cut Line= 3
      2499638.52     13501511.85      2498944.08      13501331.3
      2498315.61      13501268.8
#Sta/Elev= 30
  4263.7  212.49  4433.9  208.36    4691  198.61  4904.8  193.89    4910  194.22
  4959.6  192.86  4978.2  191.13  4992.9  190.51  4993.1  190.01  4996.6  190.01
  4996.9  190.51  5148.1  192.61  5181.2  192.75  5211.4  192.41  5281.8  193.61
  5291.8  193.85  5297.2  194.52    5322  194.87  5342.1  196.51  5362.2   196.1
  5392.3   196.5  5432.5  198.26  5462.7  198.69  5503.8  200.56  5512.9   201.7
    5533  201.59  5553.1  202.27  5573.2  203.75  5593.3  203.52  5612.8  204.48
#Mann= 5 ,-1 , 0
  4263.7     .05       0  4992.9     .05       0  4996.9     .05       0
  5148.1     .12       0  5181.2     .05       0
Bank Sta=4992.9,4996.9
XS Rating Curve= 0 ,0
Exp/Cntr=0.3,0.1

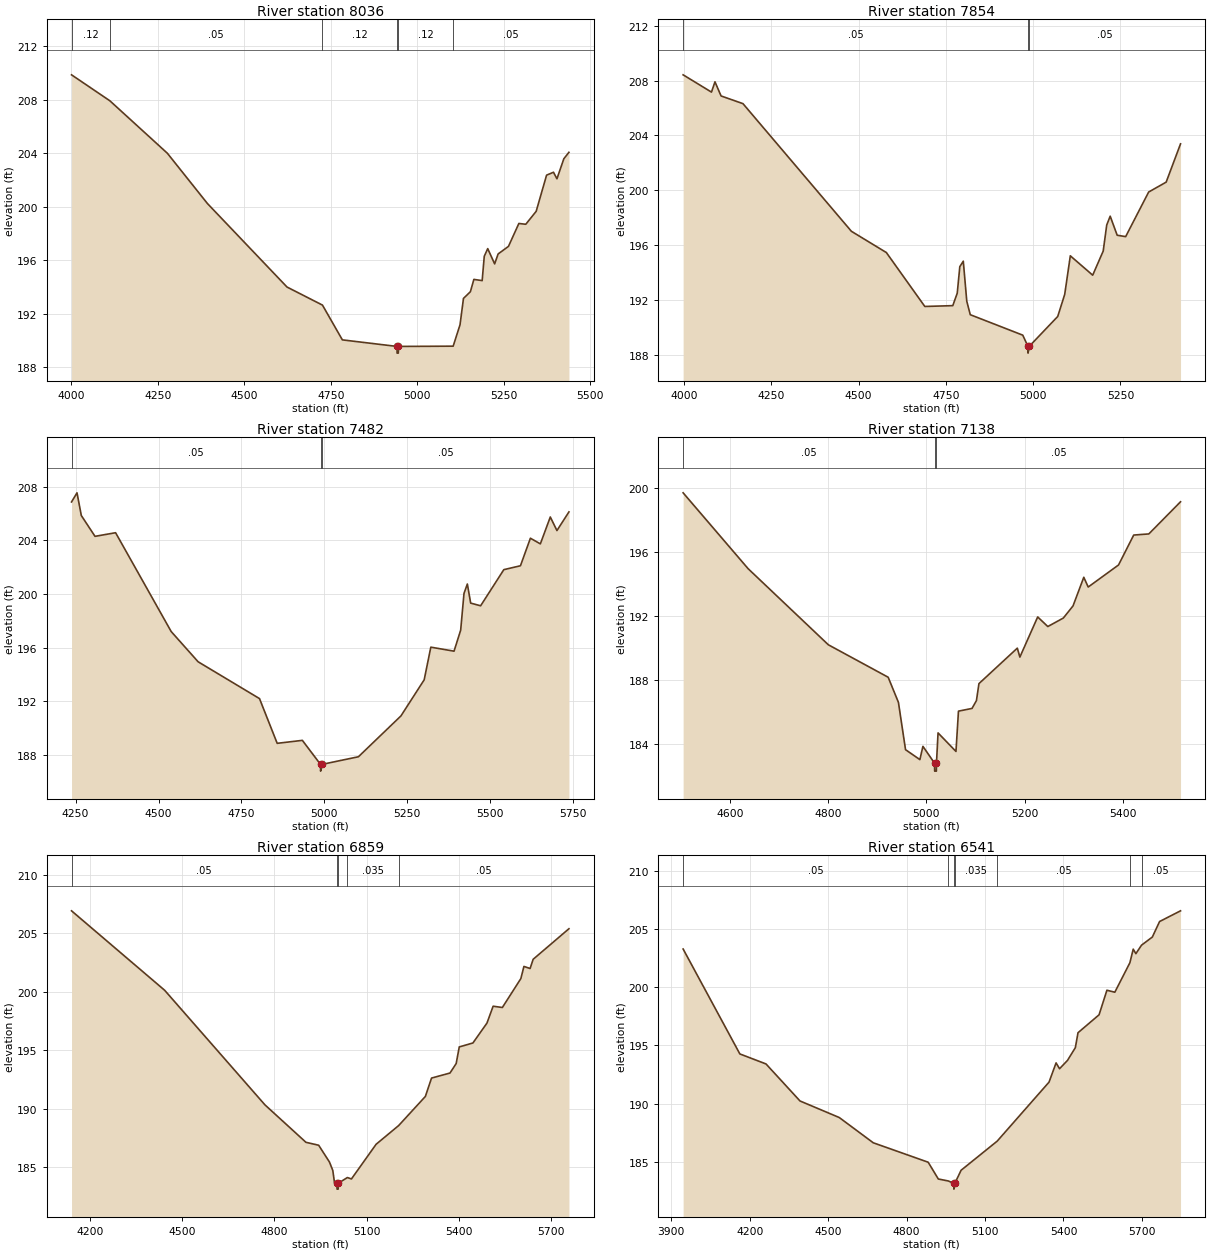
Type RM Length L Ch R = 1 ,8036    ,182,182,182
BEGIN DESCRIPTION:
Mapping XS e8778c22
END DESCRIPTION:
XS GIS Cut Line= 3
      2499787.85     13501095.19      2498791.31     13501112.55
      2498350.34     13501129.91
#Sta/Elev= 30
  4000.2  209.87    4111  207.93  4277.2  204.01  4393.1  200.25  4623.1  194.01
  4725.6  192.66  4783.2  190.06  4941.2  189.57  4941.4  189.07  4944.9  189.07
  4945.2  189.57  5103.5  189.59  5123.3  191.19  5133.3  193.16  5153.3  193.66
  5163.3  194.58  5187.3  194.49  5193.4  196.31  5203.4  196.88  5223.4  195.74
  5233.4  196.48  5263.4  197.05  5293.4  198.76  5313.4   198.7  5343.5  199.67
  5373.5  202.37  5393.5  202.59  5403.5   202.1  5423.5   203.6  5438.2  204.08
#Mann= 6 ,-1 , 0
  4000.2     .12       0    4111     .05       0  4725.6     .12       0
  4941.2     .05       0  4945.2     .12       0  5103.5     .05       0
Bank Sta=4941.2,4945.2
XS Rating Curve= 0 ,0
Exp/Cntr=0.3,0.1

Type RM Length L Ch R = 1 ,7854    ,372,372,372
BEGIN DESCRIPTION:
Mapping XS f20ab1c0
END DESCRIPTION:
XS GIS Cut Line= 3
      2499826.07     13500883.38      2498836.44     13500942.41
      2498403.92     13500970.09
#Sta/Elev= 30
  3997.4  208.42  4078.6  207.16  4088.6  207.91  4106.1  206.88  4168.8  206.32
  4479.3  197.02  4579.5  195.47  4689.7  191.54  4769.8   191.6  4782.6  192.51
  4789.9  194.44  4799.9  194.84  4809.9  191.92  4819.9  190.94  4970.2  189.45
    4985  188.64  4985.3  188.14    4989  188.64  5070.4  190.81  5090.4  192.42
  5106.5  195.23  5170.6  193.82  5200.7  195.58  5210.7  197.47  5220.7  198.12
  5240.7  196.73    5265  196.63  5330.9  199.88    5381   200.6  5422.2  203.39
#Mann= 3 ,-1 , 0
  3997.4     .05       0    4985     .05       0    4989     .05       0
Bank Sta=4985,4989
XS Rating Curve= 0 ,0
Exp/Cntr=0.3,0.1

Type RM Length L Ch R = 1 ,7482    ,344,344,344
BEGIN DESCRIPTION:
Mapping XS 77801aed
END DESCRIPTION:
XS GIS Cut Line= 3
      2499763.58     13500834.78      2499027.42      13500643.8
      2498288.87     13500616.06
#Sta/Elev= 30
  4237.7  206.85  4254.2  207.53  4267.2  205.84  4308.5  204.29  4370.5  204.56
  4538.2   197.2  4619.4  194.95  4804.4  192.21  4857.7  188.88  4933.6   189.1
  4988.4  187.31  4988.6  186.81  4992.4  187.31  5102.6  187.88  5230.8  190.92
  5300.9  193.61  5320.9  196.04  5390.9  195.74  5410.9  197.31  5420.9  200.04
    5431  200.74    5441  199.32    5471  199.12    5541  201.81  5591.1   202.1
  5621.1  204.15  5651.1  203.73  5681.1  205.73  5701.1  204.72  5737.3  206.11
#Mann= 3 ,-1 , 0
  4237.7     .05       0  4988.4     .05       0  4992.4     .05       0
Bank Sta=4988.4,4992.4
XS Rating Curve= 0 ,0
Exp/Cntr=0.3,0.1

Type RM Length L Ch R = 1 ,7138    ,279,279,279
BEGIN DESCRIPTION:
TRIB 3 TO EIGHTEENMILE CREEK 9.0
END DESCRIPTION:
XS GIS Cut Line= 3
      2499621.66     13500672.52        2499225.       13500375.
      2498722.29     13500252.35
#Sta/Elev= 30
  4504.4  199.69  4636.7  194.95  4800.2  190.19  4922.1  188.16    4943  186.59
  4957.5  183.63  4986.7  183.01  4992.9  183.84  5016.5  182.79  5016.8  182.29
  5020.3  182.29  5020.5  182.79  5023.7  184.68  5060.2  183.52  5065.3  186.04
  5092.9  186.21  5101.9   186.7    5107  187.76  5185.2  189.98  5190.4  189.42
  5226.7  191.93  5247.3  191.33  5278.9  191.86  5298.7  192.62  5320.6  194.41
  5329.6   193.8  5391.4  195.18  5422.3  197.05  5453.1  197.12  5517.7  199.13
#Mann= 3 ,-1 , 0
  4504.4     .05       0  5016.5     .05       0  5020.5     .05       0
Bank Sta=5016.5,5020.5
XS Rating Curve= 0 ,0
Exp/Cntr=0.3,0.1

Type RM Length L Ch R = 1 ,6859    ,318,318,318
BEGIN DESCRIPTION:
Mapping XS 95a61aea
END DESCRIPTION:
XS GIS Cut Line= 3
       2500112.9     13500473.33      2499329.46     13500130.44
      2498568.84     13500095.77
#Sta/Elev= 30
  4140.4   206.9  4443.1  200.11    4769  190.32  4902.3  187.12  4943.6  186.87
  4978.6  185.44  4989.5  184.72  4995.3  183.62  5003.2  183.62  5003.4  183.12
  5006.9  183.12  5007.2  183.62  5036.9  184.11  5050.1  183.99  5130.2  186.95
  5203.5  188.55  5290.4  191.04  5310.4  192.61  5370.4  193.04  5390.5  193.85
  5400.5  195.27    5445  195.61  5490.6  197.31  5510.6  198.75  5540.6  198.64
  5600.7  201.11  5610.7  202.15  5630.7  201.97  5640.7  202.76    5757  205.37
#Mann= 5 ,-1 , 0
  4140.4     .05       0  5003.2     .05       0  5007.2     .05       0
  5036.9    .035       0  5203.5     .05       0
Bank Sta=5003.2,5007.2
XS Rating Curve= 0 ,0
Exp/Cntr=0.3,0.1

Type RM Length L Ch R = 1 ,6541    ,184,184,184
BEGIN DESCRIPTION:
Mapping XS bbb71a23
END DESCRIPTION:
XS GIS Cut Line= 3
      2500431.86     13499846.15      2499379.38     13499828.79
      2498535.24      13499922.1
#Sta/Elev= 30
  3945.7  203.28  4162.6  194.27  4262.6  193.41  4392.6  190.23  4542.6  188.81
  4672.7  186.64  4882.7  184.97  4921.4  183.53  4959.7  183.36  4980.7  183.16
  4980.9  182.66  4984.7  183.16  5008.5  184.28  5146.5  186.78  5344.8  191.85
  5371.7   193.5    5385     193  5415.2  193.71  5445.4  194.81  5455.5  196.09
    5536  197.63  5566.1  199.74  5596.3  199.57  5653.9   202.1  5666.7  203.27
  5676.8  202.88  5698.4  203.61  5739.8  204.31  5767.4  205.64  5847.6  206.56
#Mann= 7 ,-1 , 0
  3945.7     .05       0  4959.7    .035       0  4980.7    .035       0
  4984.7    .035       0  5146.5     .05       0  5653.9    .035       0
  5698.4     .05       0
Bank Sta=4980.7,4984.7
XS Rating Curve= 0 ,0
Exp/Cntr=0.3,0.1

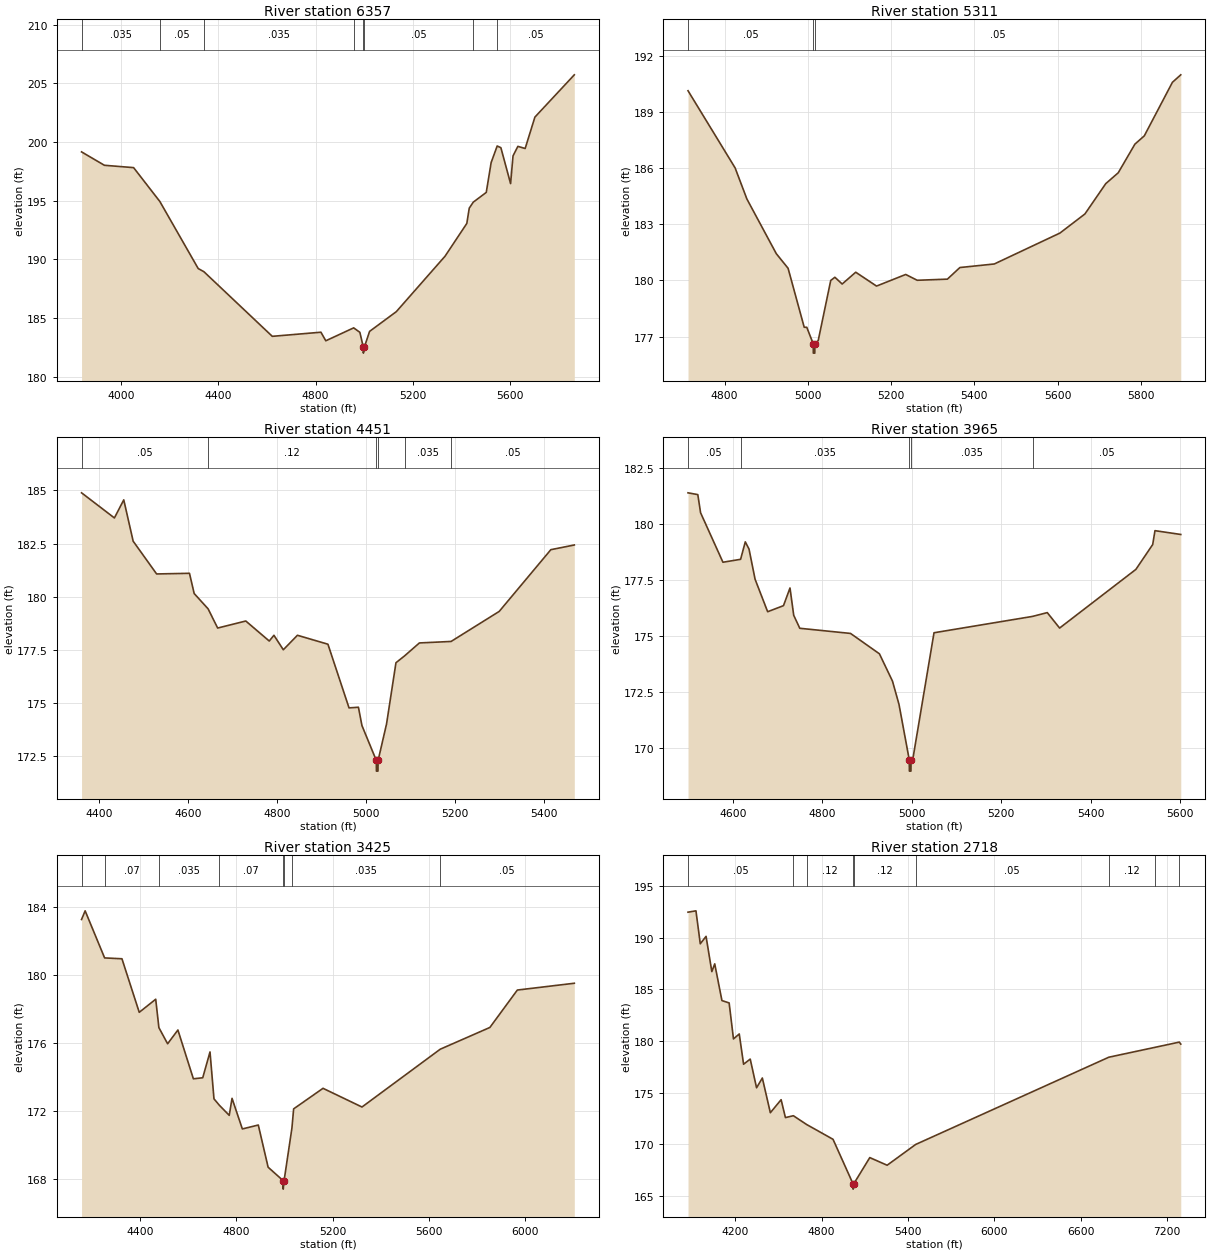
Type RM Length L Ch R = 1 ,6357    ,1046,1046,1046
BEGIN DESCRIPTION:
Mapping XS 23360406
END DESCRIPTION:
XS GIS Cut Line= 3
      2500638.92      13499627.4      2499477.47     13499682.09
      2498612.85     13499702.92
#Sta/Elev= 30
  3837.1  199.16  3931.1  198.02  4051.3  197.82  4159.2  194.94  4317.1  189.23
  4340.6  188.96  4621.9  183.46  4822.1  183.81  4842.1  183.08  4956.8  184.18
  4982.3   183.8  4996.6  182.53  4996.8  182.03  5000.6  182.53  5022.3  183.88
  5132.3  185.56  5332.8  190.28  5422.4  193.07  5432.4  194.37  5448.9  194.88
  5502.4  195.71  5522.5  198.25  5547.3  199.66  5562.5  199.52  5602.5  196.46
  5612.5  198.82  5632.5  199.63  5662.5  199.45  5702.5  202.12  5864.7  205.72
#Mann= 8 ,-1 , 0
  3837.1    .035       0  4159.2     .05       0  4340.6    .035       0
  4956.8     .05       0  4996.6     .05       0  5000.6     .05       0
  5448.9    .035       0  5547.3     .05       0
Bank Sta=4996.6,5000.6
XS Rating Curve= 0 ,0
Exp/Cntr=0.3,0.1

Type RM Length L Ch R = 1 ,5311    ,860,860,860
BEGIN DESCRIPTION:
TRIB 3 TO EIGHTEENMILE CREEK 6.0
END DESCRIPTION:
XS GIS Cut Line= 3
      2500425.02     13499375.02        2500225.       13499175.
      2499324.96       13499225.
#Sta/Elev= 30
  4711.9  190.13  4825.1  186.01  4853.4  184.35  4924.1  181.43  4952.4  180.65
  4991.2   177.5  4997.3   177.5  5012.8  176.62  5013.1  176.12  5016.6  176.12
  5016.8  176.62  5024.8  176.79  5054.9     180  5064.9  180.17  5082.4  179.81
    5115  180.44    5165   179.7  5235.1  180.32  5262.7  180.01  5335.3  180.07
  5365.3  180.69    5448  180.88  5605.7  182.53  5665.8  183.55  5715.9  185.17
  5745.9  185.75    5786  187.28  5808.5  187.72  5876.1  190.58  5896.2  190.98
#Mann= 3 ,-1 , 0
  4711.9     .05       0  5012.8     .05       0  5016.8     .05       0
Bank Sta=5012.8,5016.8
XS Rating Curve= 0 ,0
Exp/Cntr=0.3,0.1

Type RM Length L Ch R = 1 ,4451    ,486,486,486
BEGIN DESCRIPTION:
TRIB 3 TO EIGHTEENMILE CREEK 5.0
END DESCRIPTION:
XS GIS Cut Line= 3
      2500724.97     13498974.99        2500125.       13498775.
      2499674.97     13498925.01
#Sta/Elev= 30
  4361.2  184.88    4435   183.7    4456  184.55  4477.1  182.61  4529.8  181.07
  4603.6   181.1  4614.2  180.15  4645.5  179.43  4666.9  178.53  4730.1  178.86
  4782.8  177.92  4793.3  178.19  4814.4  177.51  4846.1  178.19  4914.6  177.77
    4962  174.78  4983.1  174.81    4991  173.95  5023.3  172.31  5023.5  171.81
    5027  171.81  5027.3  172.31  5046.3  174.03  5067.4   176.9  5086.6  177.22
  5120.1  177.83  5191.2   177.9  5299.3  179.31  5415.3  182.21    5468  182.43
#Mann= 6 ,-1 , 0
  4361.2     .05       0  4645.5     .12       0  5023.3     .05       0
  5027.3     .12       0  5086.6    .035       0  5191.2     .05       0
Bank Sta=5023.3,5027.3
XS Rating Curve= 0 ,0
Exp/Cntr=0.3,0.1

Type RM Length L Ch R = 1 ,3965    ,540,540,540
BEGIN DESCRIPTION:
TRIB 3 TO EIGHTEENMILE CREEK 4.0
END DESCRIPTION:
XS GIS Cut Line= 3
      2500624.99     13498824.98        2500325.       13498425.
      2499724.96       13498475.
#Sta/Elev= 30
  4499.6  181.39  4521.5  181.31  4527.7   180.5  4577.7  178.29  4617.2  178.42
  4627.7   179.2    4636  178.88  4649.6  177.53  4677.7  176.08  4713.1  176.35
  4727.7  177.14    4736  175.92  4749.6  175.34  4863.1  175.11  4927.7   174.2
  4956.9  172.98  4971.5  171.94  4994.5  169.46  4994.7  168.96  4998.2  168.96
  4998.5  169.46  5002.1  169.46  5049.8  175.14  5270.1  175.87  5303.1  176.04
  5330.7  175.35  5501.3  177.97  5538.9  179.08    5544   179.7  5601.7  179.53
#Mann= 5 ,-1 , 0
  4499.6     .05       0  4617.2    .035       0  4994.5    .035       0
  4998.5    .035       0  5270.1     .05       0
Bank Sta=4994.5,4998.5
XS Rating Curve= 0 ,0
Exp/Cntr=0.3,0.1

Type RM Length L Ch R = 1 ,3425    ,707,707,707
BEGIN DESCRIPTION:
Mapping XS 357369dd
END DESCRIPTION:
XS GIS Cut Line= 4
      2501038.52     13498888.94      2500762.47     13498159.76
      2500168.72     13498034.76      2499663.54     13498456.61
#Sta/Elev= 30
  4158.4  183.25  4173.3  183.76  4254.1  180.99    4326  180.94  4397.8  177.79
  4466.1  178.56  4479.3  176.89  4515.5  175.94  4558.2  176.75  4622.4  173.88
  4661.2  173.94  4691.4  175.46  4707.9   172.7  4730.4  172.32  4771.2  171.73
  4782.8  172.73  4825.6  170.93  4891.8  171.16  4932.5  168.68  4994.8  167.89
  4995.1  167.39  4998.8  167.89  5031.3  170.98  5038.4  172.11  5160.3  173.32
    5322  172.22  5646.7  175.62  5852.7   176.9  5966.6   179.1    6203   179.5
#Mann= 8 ,-1 , 0
  4158.4     .05       0  4254.1     .07       0  4479.3    .035       0
  4730.4     .07       0  4994.8     .05       0  4998.8     .07       0
  5031.3    .035       0  5646.7     .05       0
Bank Sta=4994.8,4998.8
XS Rating Curve= 0 ,0
Exp/Cntr=0.3,0.1

Type RM Length L Ch R = 1 ,2718    ,1126,1126,1126
BEGIN DESCRIPTION:
Mapping XS b120991f
END DESCRIPTION:
XS GIS Cut Line= 5
      2501548.93       13499040.      2501601.01     13498316.01
      2500819.76     13497633.72      2500179.14     13497753.51
      2499450.74     13498450.69
#Sta/Elev= 30
  3872.3  192.46  3927.4  192.59  3957.5   189.4  3997.6  190.12  4037.7  186.71
  4057.8  187.46  4107.9  183.91    4158  183.68  4188.1   180.2  4228.2  180.68
  4258.3  177.75  4304.4  178.25  4348.5  175.47  4388.6  176.42  4444.2  173.06
    4519  174.32    4549  172.59  4604.1  172.77  4696.3  171.92  4879.6  170.49
    5019  166.17  5019.3  165.67  5023.1  166.17    5135  168.72  5255.5  167.98
  5453.6  169.99  6795.6  178.43  7117.9  179.39  7285.1  179.89  7295.4   179.7
#Mann= 9 ,-1 , 0
  3872.3     .05       0  4604.1     .07       0  4696.3     .12       0
    5019     .05       0  5023.1     .12       0  5453.6     .05       0
  6795.6     .12       0  7117.9     .05       0  7285.1     .07       0
Bank Sta=5019,5023.1
XS Rating Curve= 0 ,0
Exp/Cntr=0.3,0.1

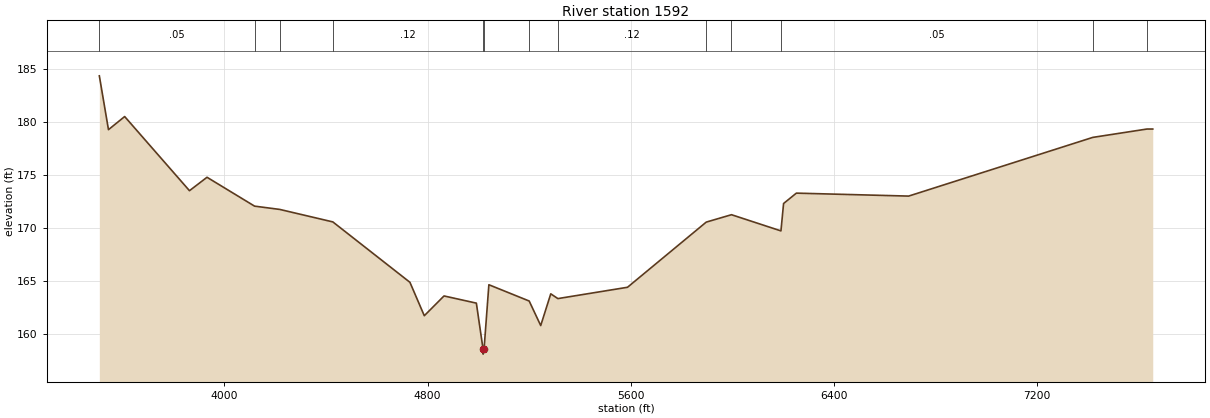
Type RM Length L Ch R = 1 ,1592    ,0,0,0
BEGIN DESCRIPTION:
Mapping XS 517a17ef
END DESCRIPTION:
XS GIS Cut Line= 5
      2501798.93     13498904.55      2502142.27      13497851.5
      2501708.47     13497398.96      2500288.51     13497576.43
      2499545.01     13498221.14
#Sta/Elev= 30
  3507.2  184.38  3543.2  179.29    3607  180.53  3862.3  173.52  3931.4  174.79
  4118.7  172.06  4217.9  171.75    4427  170.57  4730.7  164.86  4787.3   161.7
    4865  163.57  4992.4  162.89  5018.6  158.57  5018.9  158.07  5022.8  158.57
  5041.7  164.63  5200.5  163.09  5245.9  160.77  5285.5  163.77  5313.5  163.32
  5587.8  164.39  5897.9  170.55  5997.4  171.25  6192.2  169.72  6202.6  172.31
    6253  173.29  6695.3  173.01  7420.7  178.56  7634.1  179.35  7656.8  179.35
#Mann= 13 ,-1 , 0
  3507.2     .05       0  4118.7     .07       0  4217.9    .035       0
    4427     .12       0  5018.6     .05       0  5022.8     .12       0
  5200.5     .07       0  5313.5     .12       0  5897.9     .05       0
  5997.4     .07       0  6192.2     .05       0  7420.7     .12       0
  7634.1     .07       0
Bank Sta=5018.6,5022.8
XS Rating Curve= 0 ,0
Exp/Cntr=0.3,0.1

Chan Stop Cuts=-1
Use User Specified Reach Order=0
Composite Channel Slope=5