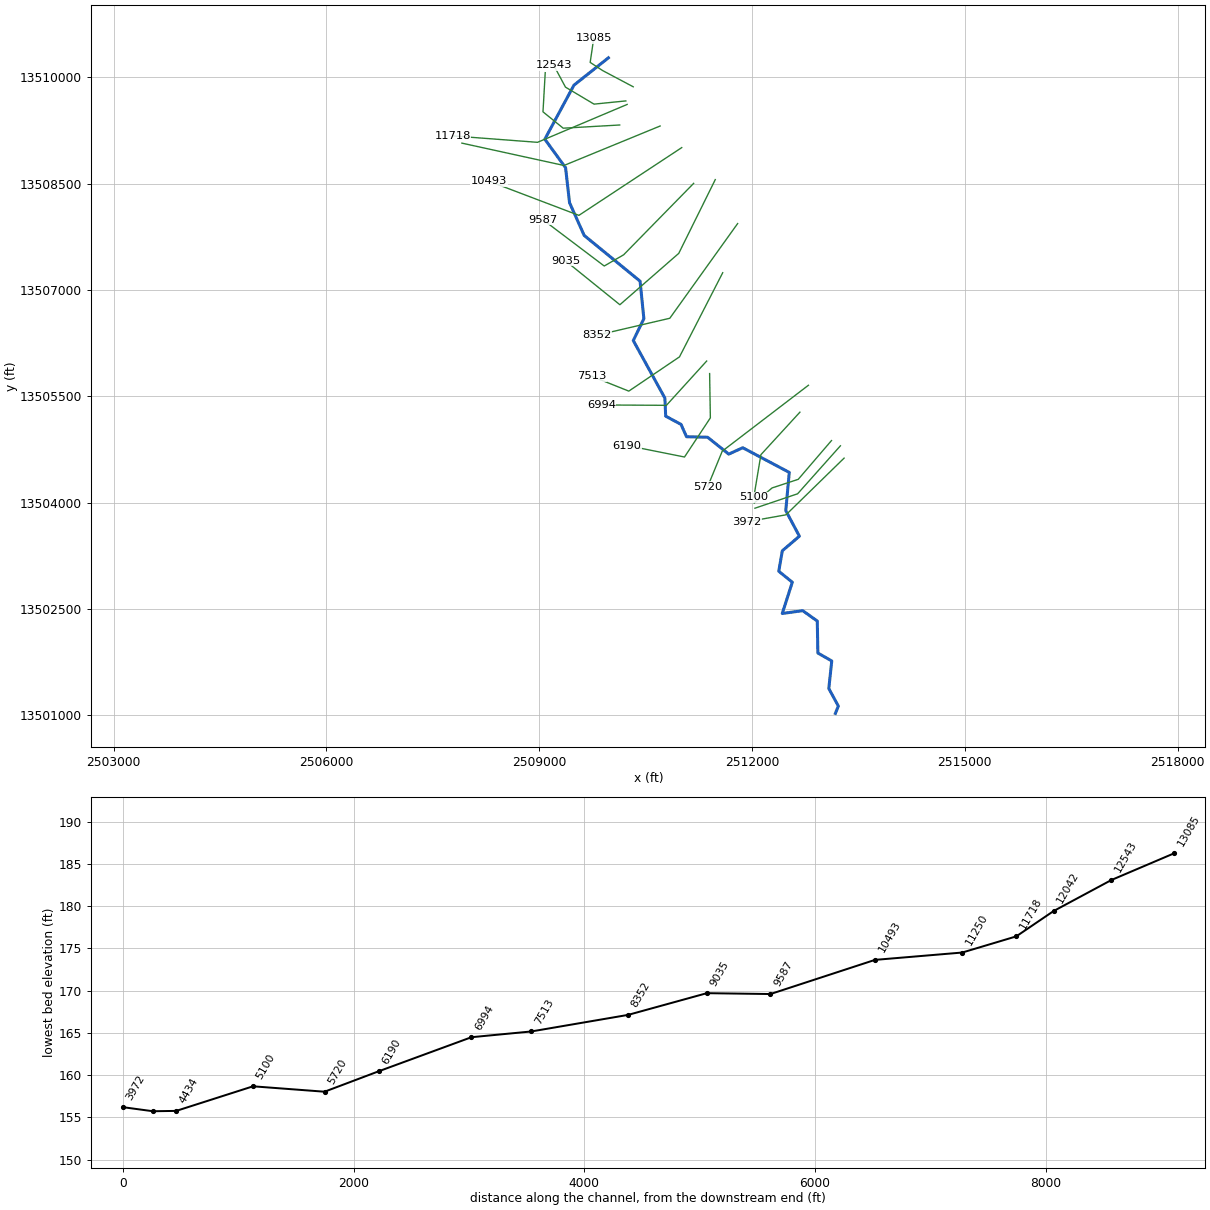
--- TRIB 3 TO FIFTEENMILE CREEK.prj (project) ---

Proj Title=TRIB 3 TO FIFTEENMILE CREEK Base Level Engineering
Current Plan=p01
Default Exp/Contr=0.3,0.1
English Units
Geom File=g01
Flow File=f01
Plan File=p01
Y Axis Title=Elevation
X Axis Title(PF)=Main Channel Distance
X Axis Title(XS)=Station
BEGIN DESCRIPTION:
TRIB 3 TO FIFTEENMILE CREEK
END DESCRIPTION:
DSS Export Rating Curves= 0
DSS Export Rating Curve Sorted= 0
DSS Export Volume Flow Curves= 0
DXF OffsetX= 0
DXF OffsetY= 0
DXF ScaleX= 1
DXF ScaleY= 10

--- TRIB 3 TO FIFTEENMILE CREEK.p01 (plan) ---

Plan Title=Multiple Run
Short Identifier=Multiple
Geom File=g01
Flow File=f01
Subcritical Flow
K Sum by GR= 0
Std Step Tol= 0.01
Critical Tol= 0.01
Num of Std Step Trials= 20
Max Error Tol= 0.3
Flow Tol Ratio= 0.001
Split Flow NTrial= 30
Split Flow Tol= 0.02
Split Flow Ratio= 0.02
Log Output Level= 0
Friction Slope Method= 1
Unsteady Friction Slope Method= 2
Unsteady Bridges Friction Slope Method= 1
Parabolic Critical Depth
Global Vel Dist=  1 , 1 , 1
Global Log Level= 0
CheckData=True
Encroach Param= -1, 0, 0, 0
BEGIN DESCRIPTION:
Multiple Run
END DESCRIPTION:

--- TRIB 3 TO FIFTEENMILE CREEK.f01 (steady flow) ---

Flow Title=Multiple
Number of Profiles=7
Profile Names=10-year,25-year,50-year,1pct_min,100-year,1pct_plu,500-year
River Rch & RM= TRIB 3 TO FIFTEE,Reach-1,13085
      56      74      87      50     100     200     131
River Rch & RM= TRIB 3 TO FIFTEE,Reach-1,11718
     745    1197    1601    1036    2068    4126    3411
River Rch & RM= TRIB 3 TO FIFTEE,Reach-1,10493
     829    1336    1792    1162    2318    4626    3839
River Rch & RM= TRIB 3 TO FIFTEE,Reach-1,6994
     863    1393    1871    1214    2422    4832    4015
River Rch & RM= TRIB 3 TO FIFTEE,Reach-1,4434
    1325    2189    2986    1965    3921    7824    6697
Boundary for River Rch & Prof#=TRIB 3 TO FIFTEE,Reach-1,1
Up Type=0
Dn Type=3
Dn Slope=0.005
Boundary for River Rch & Prof#=TRIB 3 TO FIFTEE,Reach-1,2
Up Type=0
Dn Type=3
Dn Slope=0.005
Boundary for River Rch & Prof#=TRIB 3 TO FIFTEE,Reach-1,3
Up Type=0
Dn Type=3
Dn Slope=0.005
Boundary for River Rch & Prof#=TRIB 3 TO FIFTEE,Reach-1,4
Up Type=0
Dn Type=3
Dn Slope=0.005
Boundary for River Rch & Prof#=TRIB 3 TO FIFTEE,Reach-1,5
Up Type=0
Dn Type=3
Dn Slope=0.005
Boundary for River Rch & Prof#=TRIB 3 TO FIFTEE,Reach-1,6
Up Type=0
Dn Type=3
Dn Slope=0.005
Boundary for River Rch & Prof#=TRIB 3 TO FIFTEE,Reach-1,7
Up Type=0
Dn Type=3
Dn Slope=0.005

--- TRIB 3 TO FIFTEENMILE CREEK.g01 (geometry) ---

Geom Title=Existing Conditions

River Reach=TRIB 3 TO FIFTEE,Reach-1
Reach XY= 30
      2509975.00     13510275.00      2509488.65     13509888.33
      2509078.60     13509126.49      2509371.18     13508723.42
      2509427.07     13508230.86      2509633.16     13507768.95
      2510421.39     13507123.50      2510475.07     13506593.77
      2510325.70     13506285.70      2510771.38     13505473.50
      2510782.49     13505218.93      2510999.01     13505102.32
      2511076.22     13504928.44      2511373.48     13504921.26
      2511671.71     13504683.05      2511868.89     13504773.21
      2512525.00     13504425.00      2512475.95     13503885.48
      2512667.93     13503524.99      2512427.05     13503319.16
      2512376.73     13503030.62      2512567.77     13502875.31
      2512426.19     13502434.25      2512714.38     13502474.40
      2512919.99     13502327.54      2512928.36     13501876.25
      2513124.02     13501764.74      2513082.53     13501374.99
      2513217.15     13501128.28      2513175.00     13501025.00

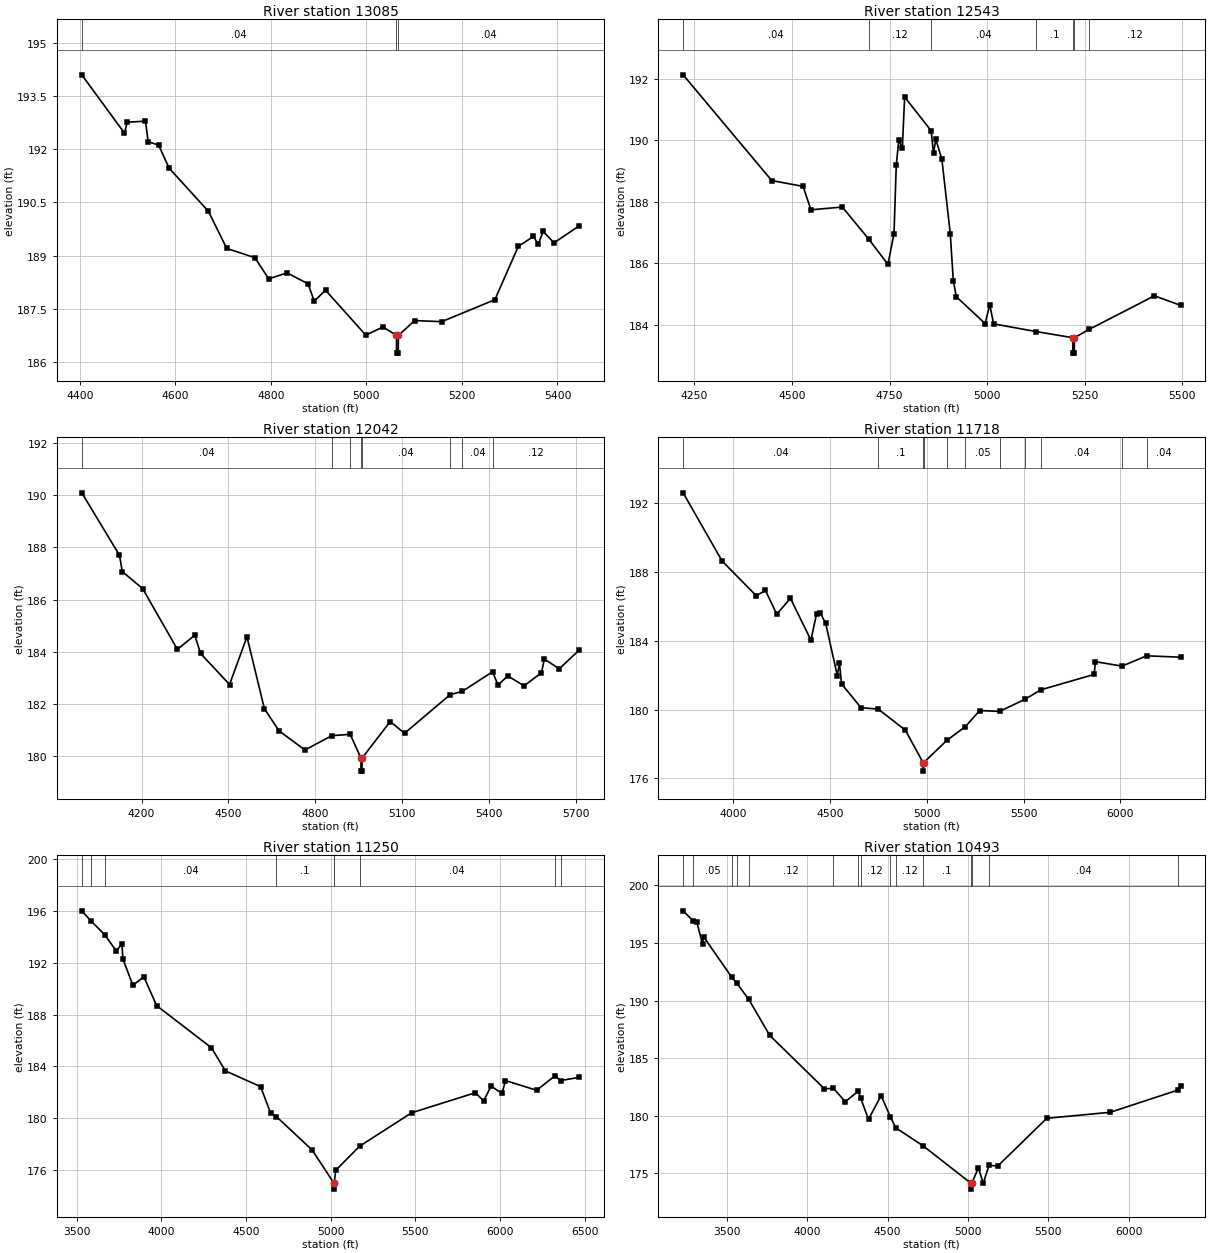
Type RM Length L Ch R = 1,13085,542,542,542
BEGIN DESCRIPTION:
LGII4686
END DESCRIPTION:
XS GIS Cut Line= 4
      2510324.98     13509865.98      2509890.25     13510096.93
      2509718.17     13510210.14      2509767.98     13510549.76
#Sta/Elev= 30
  4404.0  194.11  4493.4  192.46  4499.0  192.77  4537.3  192.80  4543.0  192.22
  4565.0  192.12  4586.9  191.47  4669.2  190.25  4707.5  189.20  4766.3  188.94
  4795.4  188.34  4833.7  188.51  4877.7  188.20  4890.7  187.71  4914.3  188.02
  4998.6  186.75  5034.7  186.98  5062.9  186.74  5063.1  186.24  5066.6  186.24
  5066.9  186.74  5101.0  187.16  5157.7  187.13  5268.9  187.75  5318.0  189.26
  5349.7  189.54  5359.8  189.32  5369.9  189.68  5392.9  189.36  5445.5  189.84
#Mann=3,-1,0
  4404.0    0.04       0  5062.9    0.04       0  5066.9    0.04       0
Bank Sta=5062.9,5066.9
Exp/Cntr=0.3,0.1

Type RM Length L Ch R = 1,12543,501,501,501
BEGIN DESCRIPTION:
LGII4685
END DESCRIPTION:
XS GIS Cut Line= 4
      2510220.78     13509666.73      2509772.51     13509621.45
      2509369.48     13509861.45      2509201.92     13510173.93
#Sta/Elev= 30
  4221.0  192.12  4447.9  188.69  4528.3  188.50  4548.4  187.74  4628.8  187.83
  4696.4  186.79  4745.6  185.97  4761.2  186.97  4767.0  189.19  4773.4  190.00
  4782.6  189.75  4788.4  191.40  4856.2  190.31  4862.4  189.57  4868.2  190.03
  4883.8  189.38  4905.3  186.97  4913.1  185.44  4920.8  184.92  4994.5  184.05
  5006.5  184.66  5016.3  184.04  5125.0  183.79  5219.3  183.59  5219.5  183.09
  5223.0  183.09  5223.3  183.59  5261.0  183.86  5428.3  184.95  5495.2  184.64
#Mann=7,-1,0
  4221.0    0.04       0  4696.4    0.12       0  4856.2    0.04       0
  5125.0     0.1       0  5219.3    0.04       0  5223.3     0.1       0
  5261.0    0.12       0
Bank Sta=5219.3,5223.3
Exp/Cntr=0.3,0.1

Type RM Length L Ch R = 1,12042,324,324,324
BEGIN DESCRIPTION:
LGII4684
END DESCRIPTION:
XS GIS Cut Line= 4
      2510134.78     13509327.10      2509337.78     13509281.82
      2509052.49     13509512.76      2509084.19     13510065.22
#Sta/Elev= 30
  3993.5  190.09  4123.6  187.70  4133.5  187.07  4203.6  186.42  4323.8  184.09
  4383.9  184.63  4403.9  183.93  4504.1  182.74  4564.2  184.57  4624.3  181.82
  4674.4  180.97  4764.5  180.23  4857.5  180.78  4921.0  180.83  4958.0  179.92
  4958.2  179.42  4961.7  179.42  4962.0  179.92  5059.1  181.32  5108.7  180.87
  5266.0  182.35  5308.5  182.48  5412.9  183.23  5431.5  182.72  5465.5  183.07
  5521.7  182.69  5581.8  183.19  5591.8  183.72  5643.0  183.34  5712.2  184.06
#Mann=8,-1,0
  3993.5    0.04       0  4857.5     0.1       0  4921.0    0.04       0
  4958.0    0.04       0  4962.0    0.04       0  5266.0    0.12       0
  5308.5    0.04       0  5412.9    0.12       0
Bank Sta=4958,4962
Exp/Cntr=0.3,0.1

Type RM Length L Ch R = 1,11718,468,468,468
BEGIN DESCRIPTION:
LGII4679
END DESCRIPTION:
XS GIS Cut Line= 3
      2510238.94     13509616.92      2508975.51     13509082.56
      2507780.02     13509173.13
#Sta/Elev= 30
  3740.3  192.59  3941.6  188.63  4118.3  186.61  4165.7  186.92  4224.0  185.54
  4295.0  186.46  4400.7  184.03  4429.8  185.55  4448.1  185.63  4477.2  185.00
  4537.2  181.97  4548.0  182.71  4559.1  181.49  4659.3  180.11  4749.3  180.02
  4888.8  178.80  4980.2  176.92  4980.5  176.42  4984.4  176.92  5102.3  178.20
  5198.3  179.00  5273.1  179.94  5376.4  179.89  5509.7  180.61  5587.7  181.14
  5864.7  182.04  5871.1  182.78  6008.9  182.52  6135.4  183.12  6311.0  183.04
#Mann=11,-1,0
  3740.3    0.04       0  4749.3     0.1       0  4980.2    0.05       0
  4984.4     0.1       0  5102.3    0.04       0  5198.3    0.05       0
  5376.4    0.04       0  5509.7    0.05       0  5587.7    0.04       0
  6008.9    0.05       0  6135.4    0.04       0
Bank Sta=4980.2,4984.4
Exp/Cntr=0.3,0.1

Type RM Length L Ch R = 1,11250,757,757,757
BEGIN DESCRIPTION:
Mapping XS 59188a20
END DESCRIPTION:
XS GIS Cut Line= 3
      2510704.10     13509312.71      2509348.68     13508755.83
      2507909.54     13509070.97
#Sta/Elev= 30
  3529.4  196.02  3584.1  195.23  3663.8  194.19  3733.8  192.91  3766.3  193.48
  3772.5  192.29  3831.3  190.26  3896.0  190.92  3971.7  188.69  4295.1  185.44
  4377.8  183.65  4585.8  182.43  4644.5  180.40  4678.9  180.12  4890.6  177.53
  5017.1  175.01  5017.3  174.51  5021.3  175.01  5029.2  175.96  5170.7  177.83
  5478.1  180.41  5854.5  181.96  5903.5  181.33  5947.3  182.47  6012.0  181.91
  6032.5  182.90  6216.7  182.15  6323.9  183.26  6358.6  182.90  6468.0  183.15
#Mann=9,-1,0
  3529.4    0.04       0  3584.1    0.05       0  3663.8    0.04       0
  4678.9     0.1       0  5017.1    0.05       0  5021.3     0.1       0
  5170.7    0.04       0  6323.9    0.05       0  6358.6    0.04       0
Bank Sta=5017.1,5021.3
Exp/Cntr=0.3,0.1

Type RM Length L Ch R = 1,10493,906,906,906
BEGIN DESCRIPTION:
Mapping XS 1f45451e
END DESCRIPTION:
XS GIS Cut Line= 3
      2511008.82     13509007.99      2509558.83     13508051.83
      2508288.69     13508534.70
#Sta/Elev= 30
  3227.3  197.80  3288.9  196.94  3312.1  196.85  3348.2  194.90  3354.2  195.56
  3529.6  192.04  3560.5  191.53  3635.8  190.11  3766.8  186.98  4106.3  182.35
  4163.0  182.39  4236.5  181.23  4318.1  182.15  4331.2  181.57  4381.0  179.70
  4459.3  181.76  4516.3  179.94  4551.1  178.96  4721.5  177.39  5019.6  174.14
  5019.9  173.64  5024.0  174.14  5064.6  175.49  5095.5  174.16  5130.6  175.70
  5185.9  175.65  5490.4  179.79  5885.3  180.31  6306.8  182.24  6323.0  182.57
#Mann=15,-1,0
  3227.3    0.12       0  3288.9    0.05       0  3529.6    0.12       0
  3560.5    0.05       0  3635.8    0.12       0  4163.0   0.013       0
  4318.1     0.1       0  4331.2    0.12       0  4516.3    0.05       0
  4551.1    0.12       0  4721.5     0.1       0  5019.6    0.05       0
  5024.0     0.1       0  5130.6    0.04       0  6306.8    0.03       0
Bank Sta=5019.6,5024
Exp/Cntr=0.3,0.1

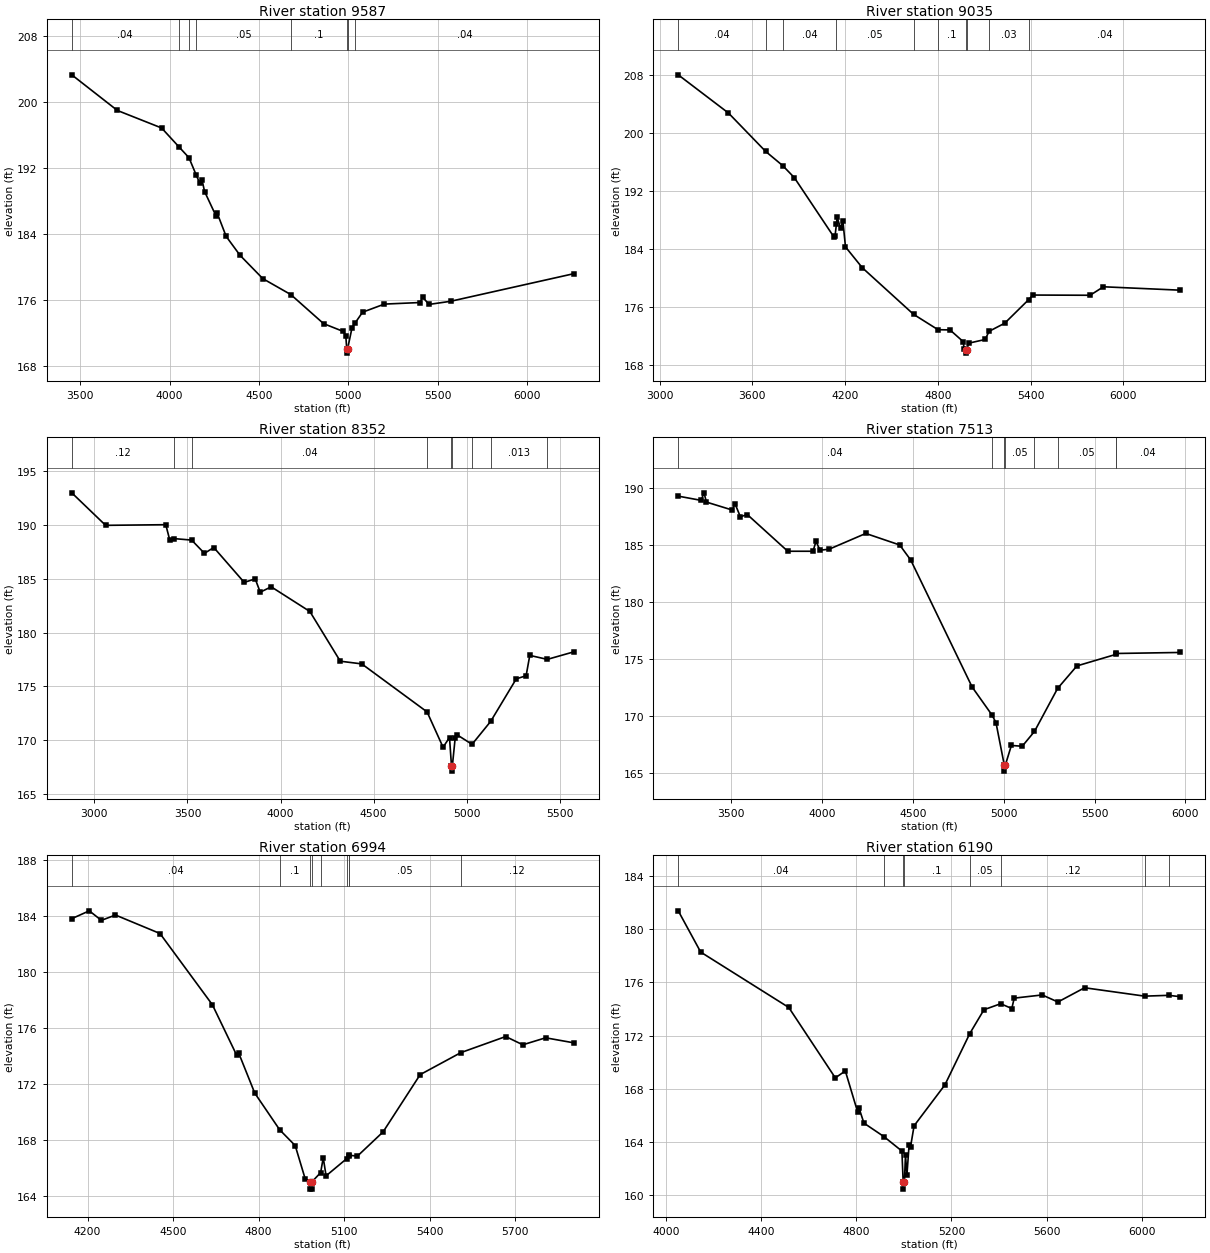
Type RM Length L Ch R = 1,9587,552,552,552
BEGIN DESCRIPTION:
Mapping XS 43e3b28d
END DESCRIPTION:
XS GIS Cut Line= 4
      2511176.97     13508503.64      2510189.28     13507494.94
      2509916.09     13507337.33      2509054.49     13507988.78
#Sta/Elev= 30
  3453.4  203.26  3708.4  198.95  3955.8  196.83  4051.3  194.58  4108.6  193.24
  4149.8  191.11  4168.0  190.20  4182.1  190.49  4196.3  189.13  4260.0  186.19
  4267.0  186.50  4316.6  183.72  4394.3  181.43  4521.6  178.61  4678.3  176.68
  4861.1  173.17  4971.6  172.22  4985.5  171.72  4990.9  170.10  4991.2  169.60
  4995.5  170.10  5020.5  172.68  5038.7  173.28  5079.4  174.55  5201.1  175.53
  5400.9  175.72  5415.5  176.36  5450.9  175.49  5571.6  175.87  6260.7  179.21
#Mann=8,-1,0
  3453.4    0.04       0  4051.3   0.013       0  4108.6    0.04       0
  4149.8    0.05       0  4678.3     0.1       0  4990.9    0.05       0
  4995.5     0.1       0  5038.7    0.04       0
Bank Sta=4990.9,4995.5
Exp/Cntr=0.3,0.1

Type RM Length L Ch R = 1,9035,683,683,683
BEGIN DESCRIPTION:
Mapping XS a9f01455
END DESCRIPTION:
XS GIS Cut Line= 4
      2511481.71     13508556.21      2510966.83     13507515.95
      2510136.74     13506790.94      2509370.38     13507410.33
#Sta/Elev= 30
  3120.6  208.08  3445.6  202.81  3685.5  197.53  3797.0  195.55  3871.7  193.90
  4126.2  185.77  4135.3  185.90  4144.0  187.50  4148.5  188.42  4170.8  186.94
  4185.8  187.92  4202.6  184.35  4311.2  181.48  4643.0  175.05  4801.3  172.93
  4878.9  172.90  4963.4  171.30  4971.0  170.26  4982.9  170.20  4983.2  169.70
  4987.5  170.20  4999.4  171.07  5105.8  171.58  5132.0  172.71  5233.0  173.83
  5386.9  177.06  5415.8  177.71  5785.2  177.68  5871.5  178.85  6368.8  178.38
#Mann=10,-1,0
  3120.6    0.04       0  3685.5   0.013       0  3797.0    0.04       0
  4144.0    0.05       0  4643.0    0.12       0  4801.3     0.1       0
  4982.9    0.05       0  4987.5     0.1       0  5132.0    0.03       0
  5386.9    0.04       0
Bank Sta=4982.9,4987.5
Exp/Cntr=0.3,0.1

Type RM Length L Ch R = 1,8352,839,839,839
BEGIN DESCRIPTION:
Mapping XS cc33d9a7
END DESCRIPTION:
XS GIS Cut Line= 3
      2511796.93     13507936.26      2510840.50     13506599.99
      2509814.50     13506360.79
#Sta/Elev= 30
  2878.8  192.98  3060.6  189.96  3383.7  190.02  3404.6  188.63  3426.5  188.73
  3522.8  188.59  3591.3  187.36  3641.7  187.90  3805.1  184.66  3864.0  184.99
  3891.1  183.75  3950.0  184.25  4157.6  181.96  4321.0  177.34  4436.5  177.09
  4787.3  172.63  4873.1  169.35  4907.7  170.25  4918.3  167.63  4918.7  167.13
  4923.1  167.63  4938.5  170.25  4948.7  170.50  5028.8  169.62  5128.9  171.75
  5266.3  175.70  5319.2  175.99  5338.9  177.88  5433.0  177.51  5575.6  178.21
#Mann=9,-1,0
  2878.8    0.12       0  3426.5   0.013       0  3522.8    0.04       0
  4787.3     0.1       0  4918.3    0.05       0  4923.1     0.1       0
  5028.8    0.04       0  5128.9   0.013       0  5433.0    0.04       0
Bank Sta=4918.3,4923.1
Exp/Cntr=0.3,0.1

Type RM Length L Ch R = 1,7513,519,519,519
BEGIN DESCRIPTION:
Mapping XS ccfae772
END DESCRIPTION:
XS GIS Cut Line= 4
      2511586.76     13507242.74      2510977.34     13506055.42
      2510262.83     13505572.07      2509738.74     13505781.71
#Sta/Elev= 30
  3210.0  189.27  3335.5  188.90  3352.1  189.56  3364.8  188.75  3507.4  188.05
  3522.2  188.61  3551.8  187.46  3589.6  187.66  3812.5  184.44  3951.2  184.44
  3967.8  185.30  3990.0  184.53  4040.0  184.62  4241.6  186.00  4428.2  184.99
  4488.9  183.67  4826.6  172.54  4936.6  170.07  4957.9  169.41  5003.9  165.67
  5004.3  165.17  5008.7  165.67  5042.4  167.42  5102.1  167.35  5169.6  168.65
  5296.8  172.42  5402.9  174.39  5617.1  175.40  5618.4  175.48  5971.7  175.57
#Mann=8,-1,0
  3210.0    0.04       0  4936.6    0.05       0  5003.9    0.05       0
  5008.7    0.05       0  5169.6    0.04       0  5296.8    0.05       0
  5617.1    0.12       0  5618.4    0.04       0
Bank Sta=5003.9,5008.7
Exp/Cntr=0.3,0.1

Type RM Length L Ch R = 1,6994,804,804,804
BEGIN DESCRIPTION:
Mapping XS 281eb187
END DESCRIPTION:
XS GIS Cut Line= 3
      2511360.34     13505996.43      2510792.66     13505371.47
      2509875.98     13505376.68
#Sta/Elev= 30
  4144.8  183.81  4206.2  184.37  4248.7  183.69  4298.1  184.07  4454.2  182.75
  4638.0  177.66  4723.1  174.06  4729.9  174.23  4786.6  171.35  4874.0  168.73
  4928.5  167.60  4963.7  165.21  4981.2  164.99  4981.5  164.49  4985.7  164.49
  4986.1  164.99  5017.7  165.67  5026.8  166.73  5036.8  165.44  5109.3  166.67
  5116.1  166.89  5117.1  166.91  5146.8  166.85  5236.8  168.58  5366.8  172.67
  5509.4  174.24  5666.8  175.39  5726.8  174.80  5806.8  175.30  5905.8  174.94
#Mann=9,-1,0
  4144.8    0.04       0  4874.0     0.1       0  4981.2    0.05       0
  4986.1     0.1       0  5017.7    0.04       0  5109.3     0.1       0
  5116.1    0.04       0  5117.1    0.05       0  5509.4    0.12       0
Bank Sta=4981.2,4986.1
Exp/Cntr=0.3,0.1

Type RM Length L Ch R = 1,6190,470,470,470
BEGIN DESCRIPTION:
Mapping XS ab3fd6ee
END DESCRIPTION:
XS GIS Cut Line= 4
      2511402.04     13505819.40      2511412.46     13505194.39
      2511047.87     13504642.30      2510240.56     13504803.76
#Sta/Elev= 30
  4052.1  181.37  4146.5  178.27  4516.6  174.11  4712.2  168.82  4754.3  169.34
  4805.5  166.29  4811.5  166.57  4832.5  165.42  4916.2  164.41  4992.1  163.32
  4997.5  160.96  4997.9  160.46  5002.5  160.96  5007.2  163.05  5013.1  161.50
  5022.2  163.76  5028.2  163.62  5043.3  165.22  5172.7  168.29  5277.4  172.15
  5336.9  173.94  5407.2  174.39  5453.9  174.03  5464.1  174.81  5581.7  175.05
  5647.7  174.52  5759.8  175.59  6012.1  174.96  6113.0  175.02  6162.1  174.92
#Mann=8,-1,0
  4052.1    0.04       0  4916.2     0.1       0  4997.5    0.05       0
  5002.5     0.1       0  5277.4    0.05       0  5407.2    0.12       0
  6012.1    0.05       0  6113.0    0.12       0
Bank Sta=4997.5,5002.5
Exp/Cntr=0.3,0.1

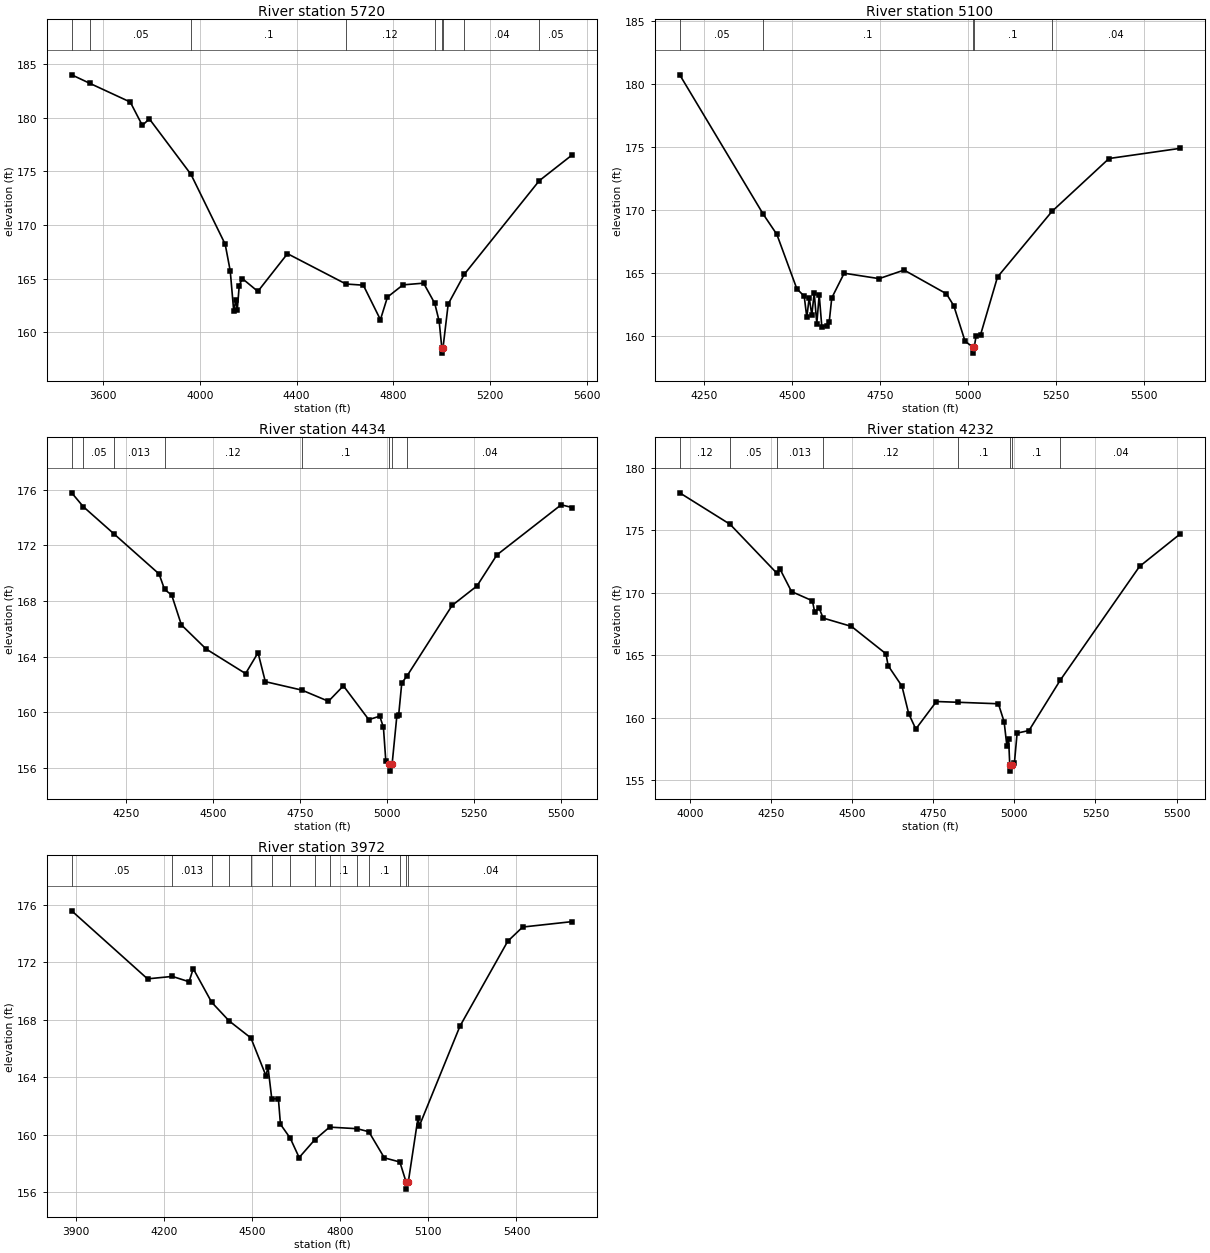
Type RM Length L Ch R = 1,5720,620,620,620
BEGIN DESCRIPTION:
TRIB 3 TO FIFTEENMILE CREEK 12.0
END DESCRIPTION:
XS GIS Cut Line= 3
      2512795.27     13505654.98      2511580.36     13504725.13
      2511374.99     13504224.97
#Sta/Elev= 30
  3469.9  184.01  3545.4  183.21  3712.1  181.47  3762.0  179.29  3791.0  179.90
  3963.2  174.72  4104.7  168.20  4125.6  165.71  4140.1  161.94  4148.3  162.98
  4154.6  162.08  4162.8  164.34  4175.4  165.00  4239.8  163.80  4362.3  167.32
  4604.2  164.49  4676.0  164.38  4746.7  161.16  4775.8  163.27  4840.1  164.41
  4925.3  164.57  4971.3  162.69  4989.7  161.01  5000.6  158.54  5001.0  158.04
  5005.6  158.54  5027.0  162.62  5094.4  165.42  5403.7  174.13  5540.5  176.55
#Mann=9,-1,0
  3469.9   0.013       0  3545.4    0.05       0  3963.2     0.1       0
  4604.2    0.12       0  4971.3     0.1       0  5000.6    0.05       0
  5005.6     0.1       0  5094.4    0.04       0  5403.7    0.05       0
Bank Sta=5000.6,5005.6
Exp/Cntr=0.3,0.1

Type RM Length L Ch R = 1,5100,666,666,666
BEGIN DESCRIPTION:
TRIB 3 TO FIFTEENMILE CREEK 11.0
END DESCRIPTION:
XS GIS Cut Line= 3
      2512675.00     13505275.00      2512125.00     13504675.00
      2512025.00     13504075.02
#Sta/Elev= 30
  4181.7  180.76  4419.2  169.69  4457.6  168.10  4514.4  163.78  4535.3  163.20
  4542.7  161.51  4549.5  163.09  4556.9  161.70  4563.7  163.45  4571.1  161.03
  4577.9  163.32  4585.3  160.78  4599.5  160.85  4606.2  161.12  4613.6  163.06
  4648.8  165.02  4748.1  164.59  4819.0  165.27  4939.2  163.39  4960.2  162.44
  4992.3  159.62  5013.4  159.18  5013.8  158.68  5018.5  159.18  5023.5  160.03
  5036.2  160.13  5084.4  164.72  5239.0  169.92  5401.2  174.12  5603.9  174.93
#Mann=5,-1,0
  4181.7    0.05       0  4419.2     0.1       0  5013.4    0.05       0
  5018.5     0.1       0  5239.0    0.04       0
Bank Sta=5013.4,5018.5
Exp/Cntr=0.3,0.1

Type RM Length L Ch R = 1,4434,202,202,202
BEGIN DESCRIPTION:
Mapping XS 33f0d9fe
END DESCRIPTION:
XS GIS Cut Line= 4
      2513120.23     13504874.27      2512651.49     13504327.41
      2512282.57     13504205.89      2512030.85     13503993.23
#Sta/Elev= 30
  4093.4  175.77  4126.5  174.78  4213.9  172.84  4344.4  169.94  4360.1  168.83
  4380.7  168.42  4408.5  166.28  4479.4  164.55  4592.9  162.78  4628.7  164.28
  4649.6  162.20  4755.0  161.59  4831.0  160.79  4873.9  161.90  4946.8  159.47
  4978.4  159.72  4988.9  158.91  4995.7  156.51  5006.2  156.27  5006.7  155.77
  5013.8  156.27  5027.5  159.75  5032.7  159.81  5041.6  162.11  5056.7  162.61
  5186.3  167.68  5257.7  169.08  5314.9  171.31  5499.5  174.91  5531.6  174.71
#Mann=8,-1,0
  4093.4    0.12       0  4126.5    0.05       0  4213.9   0.013       0
  4360.1    0.12       0  4755.0     0.1       0  5006.2    0.05       0
  5013.8     0.1       0  5056.7    0.04       0
Bank Sta=5006.2,5013.8
Exp/Cntr=0.3,0.1

Type RM Length L Ch R = 1,4232,260,260,260
BEGIN DESCRIPTION:
Mapping XS a9944025
END DESCRIPTION:
XS GIS Cut Line= 3
      2513246.14     13504800.54      2512642.81     13504123.42
      2512040.61     13503919.80
#Sta/Elev= 30
  3969.2  178.00  4124.4  175.48  4267.6  171.59  4278.5  171.88  4313.6  170.10
  4378.0  169.36  4384.7  168.50  4398.9  168.77  4410.9  167.98  4498.4  167.31
  4604.6  165.12  4611.3  164.17  4653.9  162.53  4674.8  160.32  4696.6  159.10
  4760.1  161.30  4825.6  161.24  4951.1  161.12  4968.8  159.67  4977.3  157.72
  4982.5  158.30  4986.1  156.23  4986.6  155.73  4993.7  156.23  5000.5  156.41
  5008.7  158.77  5045.4  158.98  5141.7  163.01  5386.0  172.11  5511.8  174.72
#Mann=8,-1,0
  3969.2    0.12       0  4124.4    0.05       0  4267.6   0.013       0
  4410.9    0.12       0  4825.6     0.1       0  4986.1    0.05       0
  4993.7     0.1       0  5141.7    0.04       0
Bank Sta=4986.1,4993.7
Exp/Cntr=0.3,0.1

Type RM Length L Ch R = 1,3972,0,0,0
BEGIN DESCRIPTION:
TRIB 3 TO FIFTEENMILE CREEK 8.0
END DESCRIPTION:
XS GIS Cut Line= 3
      2513298.16     13504626.87      2512478.77     13503826.57
      2511928.37     13503728.76
#Sta/Elev= 30
  3885.8  175.60  4143.9  170.86  4228.5  171.03  4285.3  170.66  4299.5  171.57
  4362.3  169.23  4421.7  167.93  4496.0  166.74  4547.1  164.11  4554.1  164.72
  4567.0  162.49  4589.4  162.52  4596.5  160.73  4629.8  159.76  4660.1  158.41
  4712.4  159.63  4763.5  160.53  4857.7  160.42  4897.3  160.21  4950.1  158.39
  5003.0  158.10  5024.1  156.71  5024.6  156.21  5031.7  156.71  5064.6  161.16
  5069.6  160.63  5207.7  167.57  5370.2  173.48  5421.0  174.47  5590.2  174.85
#Mann=14,-1,0
  3885.8    0.05       0  4228.5   0.013       0  4362.3    0.12       0
  4421.7   0.013       0  4496.0    0.12       0  4567.0   0.013       0
  4629.8    0.12       0  4712.4   0.013       0  4763.5     0.1       0
  4857.7   0.013       0  4897.3     0.1       0  5003.0   0.013       0
  5024.1    0.05       0  5031.7    0.04       0
Bank Sta=5024.1,5031.7
Exp/Cntr=0.3,0.1

Chan Stop Cuts=-1