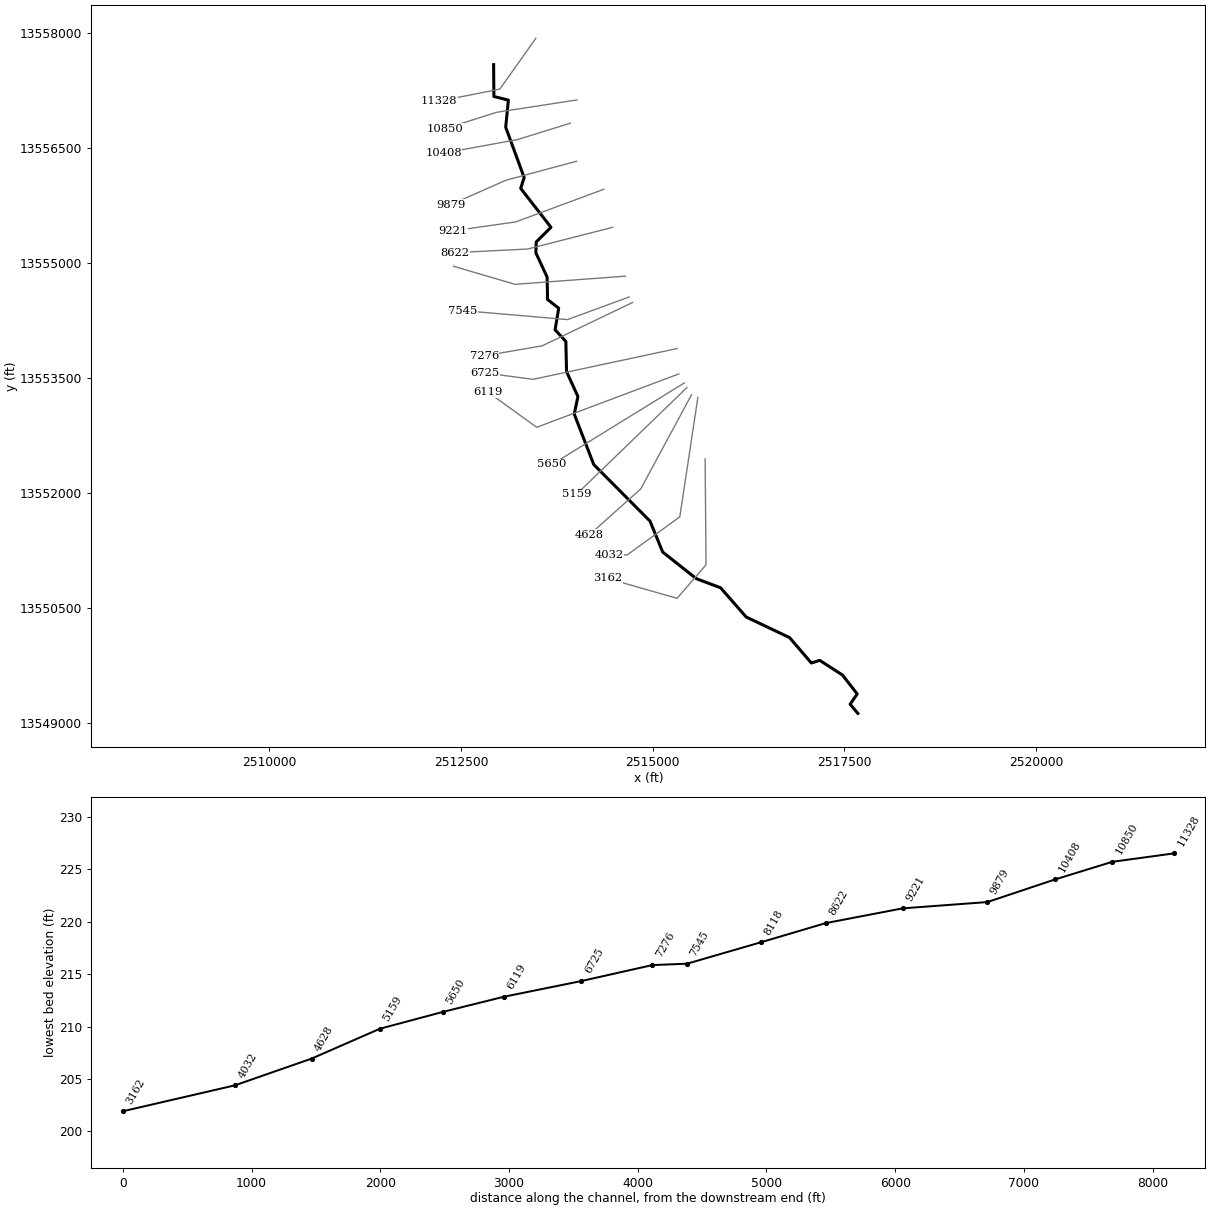
--- TRIB 3 TO FIVEMILE CREEK.prj (project) ---

Proj Title=TRIB 3 TO FIVEMILE CREEK Base Level Engineering
Current Plan=p01
Default Exp/Contr=0.3,0.1
English Units
Geom File=g01
Flow File=f01
Plan File=p01
BEGIN DESCRIPTION:
TRIB 3 TO FIVEMILE CREEK
END DESCRIPTION:

--- TRIB 3 TO FIVEMILE CREEK.p01 (plan) ---

Plan Title=Multiple Run
Short Identifier=Multiple
Geom File=g01
Flow File=f01
Subcritical Flow
K Sum by GR= 0
Std Step Tol= 0.01
Critical Tol= 0.01
Num of Std Step Trials= 20
Max Error Tol= 0.3
Flow Tol Ratio= 0.001
Split Flow NTrial= 30
Split Flow Tol= 0.02
Split Flow Ratio= 0.02
Log Output Level= 0
Friction Slope Method= 1
Unsteady Friction Slope Method= 2
Unsteady Bridges Friction Slope Method= 1
Parabolic Critical Depth
Global Vel Dist=  1 , 1 , 1
Global Log Level= 0
CheckData=True
Encroach Param= -1, 0, 0, 0
BEGIN DESCRIPTION:
Multiple Run
END DESCRIPTION:

--- TRIB 3 TO FIVEMILE CREEK.f01 (steady flow) ---

Flow Title=Multiple
Number of Profiles=7
Profile Names=10-year,25-year,50-year,1pct_min,100-year,1pct_plu,500-year
River Rch & RM= TRIB 3 TO FIVEMI,Reach-1,11328
     391     597     773     484     965    1925    1490
River Rch & RM= TRIB 3 TO FIVEMI,Reach-1,10850
     554     866    1138     722    1441    2874    2289
River Rch & RM= TRIB 3 TO FIVEMI,Reach-1,7545
     727    1156    1536     986    1967    3924    3198
Boundary for River Rch & Prof#=TRIB 3 TO FIVEMI,Reach-1,1
Up Type=0
Dn Type=3
Dn Slope=0.005
Boundary for River Rch & Prof#=TRIB 3 TO FIVEMI,Reach-1,2
Up Type=0
Dn Type=3
Dn Slope=0.005
Boundary for River Rch & Prof#=TRIB 3 TO FIVEMI,Reach-1,3
Up Type=0
Dn Type=3
Dn Slope=0.005
Boundary for River Rch & Prof#=TRIB 3 TO FIVEMI,Reach-1,4
Up Type=0
Dn Type=3
Dn Slope=0.005
Boundary for River Rch & Prof#=TRIB 3 TO FIVEMI,Reach-1,5
Up Type=0
Dn Type=3
Dn Slope=0.005
Boundary for River Rch & Prof#=TRIB 3 TO FIVEMI,Reach-1,6
Up Type=0
Dn Type=3
Dn Slope=0.005
Boundary for River Rch & Prof#=TRIB 3 TO FIVEMI,Reach-1,7
Up Type=0
Dn Type=3
Dn Slope=0.005

--- TRIB 3 TO FIVEMILE CREEK.g01 (geometry) ---

Geom Title=Existing Conditions

River Reach=TRIB 3 TO FIVEMI,Reach-1
Reach XY= 30
      2512925.00     13557591.91      2512928.53     13557175.99
      2513117.31     13557128.74      2513082.59     13556775.01
      2513323.18     13556118.88      2513278.34     13555976.72
      2513673.23     13555468.83      2513480.45     13555277.46
      2513476.19     13555135.50      2513622.74     13554819.06
      2513628.53     13554526.45      2513773.83     13554412.99
      2513727.06     13554130.85      2513867.18     13553978.41
      2513876.04     13553585.44      2514024.49     13553259.78
      2513976.63     13553031.04      2514230.82     13552372.72
      2514964.22     13551634.68      2515130.45     13551230.25
      2515568.94     13550883.14      2515884.71     13550764.25
      2516218.83     13550382.86      2516784.68     13550114.24
      2517068.93     13549782.49      2517178.40     13549817.17
      2517475.00     13549625.00      2517667.16     13549378.23
      2517574.50     13549245.17      2517675.00     13549125.00

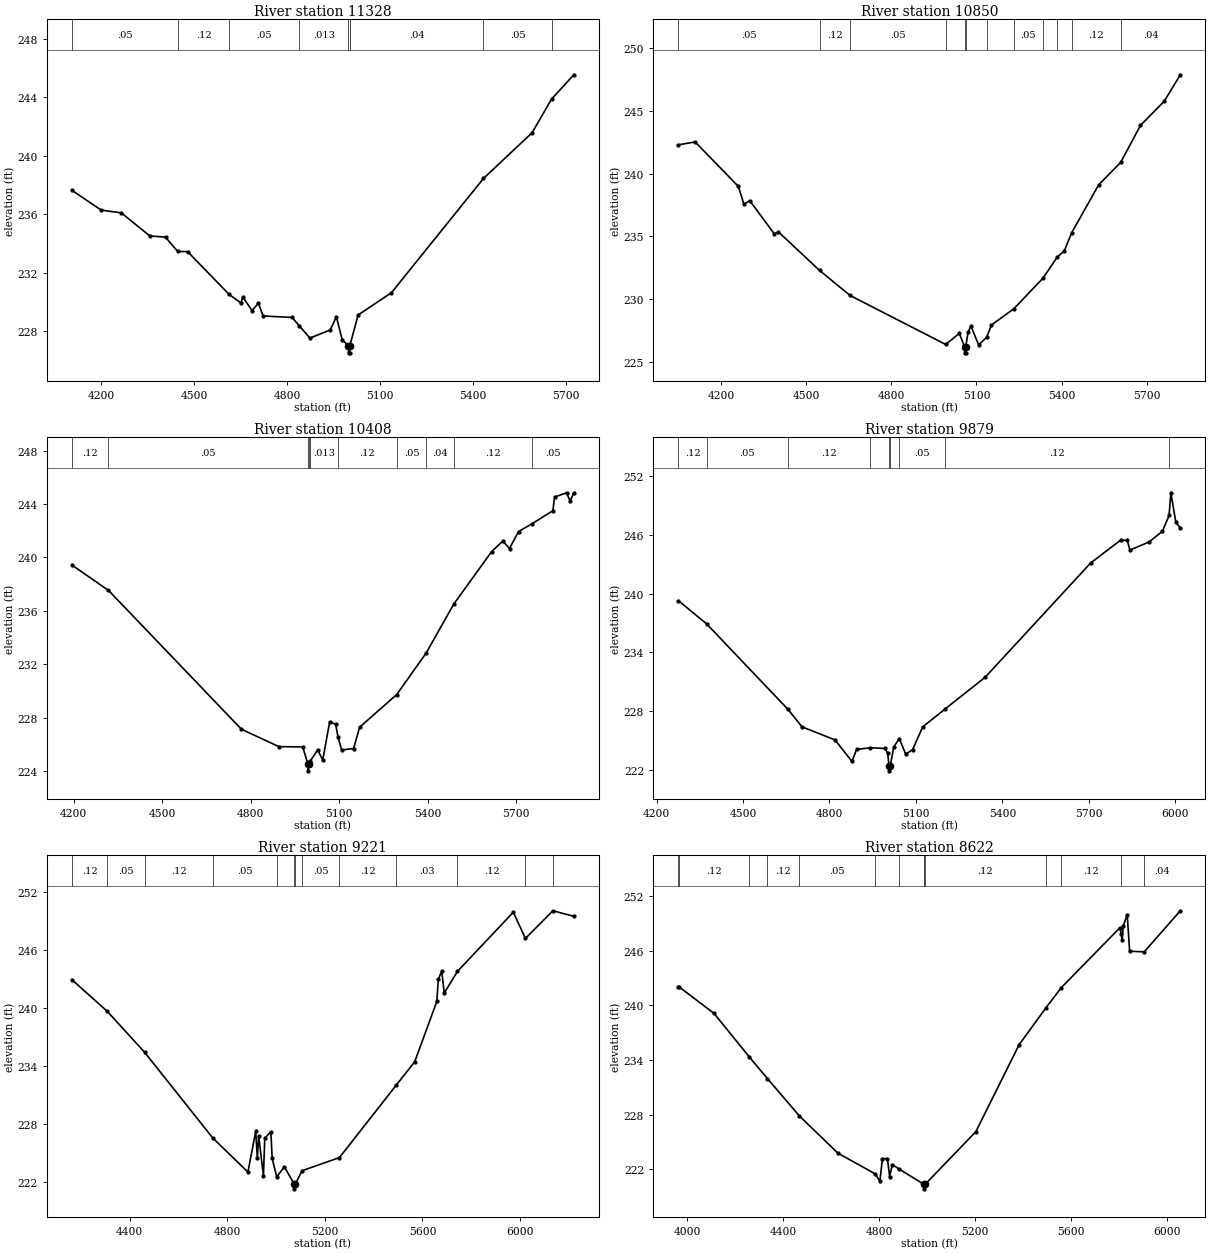
Type RM Length L Ch R = 1,11328,478,478,478
BEGIN DESCRIPTION:
LGII4545
END DESCRIPTION:
XS GIS Cut Line= 3
      2513475.65     13557935.05      2513006.03     13557272.37
      2512212.85     13557115.82
#Sta/Elev= 30
  4105.0  237.62  4199.1  236.27  4264.3  236.08  4356.6  234.50  4407.1  234.42
  4446.5  233.44  4478.4  233.43  4612.7  230.50  4650.7  229.92  4656.8  230.33
  4686.4  229.40  4707.3  229.91  4722.1  229.03  4815.9  228.93  4838.9  228.36
  4873.4  227.52  4938.7  228.07  4959.0  228.98  4977.7  227.39  4997.8  227.01
  4998.1  226.51  5001.6  226.51  5001.8  227.01  5002.7  227.03  5029.0  229.10
  5136.7  230.62  5433.8  238.43  5591.0  241.56  5653.8  243.86  5725.7  245.52
#Mann=9,-1,0
  4105.0    0.05       0  4446.5    0.12       0  4612.7    0.05       0
  4838.9   0.013       0  4997.8    0.03       0  5001.8   0.013       0
  5002.7    0.04       0  5433.8    0.05       0  5653.8    0.04       0
Bank Sta=4997.8,5001.8
Exp/Cntr=0.3,0.1

Type RM Length L Ch R = 1,10850,442,442,442
BEGIN DESCRIPTION:
LGII4544
END DESCRIPTION:
XS GIS Cut Line= 3
      2514013.17     13557131.47      2512964.28     13556969.70
      2512291.15     13556755.76
#Sta/Elev= 30
  4050.3  242.31  4109.2  242.54  4261.4  238.99  4281.2  237.56  4301.4  237.86
  4387.7  235.21  4402.6  235.36  4547.2  232.29  4654.7  230.29  4991.5  226.38
  5039.5  227.26  5058.1  226.21  5058.4  225.71  5062.2  225.71  5062.5  226.21
  5070.4  227.38  5080.5  227.84  5107.7  226.34  5135.5  226.94  5152.8  227.93
  5231.2  229.22  5333.5  231.65  5385.0  233.37  5408.8  233.83  5435.7  235.31
  5530.6  239.13  5608.0  240.91  5677.5  243.86  5761.4  245.79  5817.9  247.90
#Mann=12,-1,0
  4050.3    0.05       0  4547.2    0.12       0  4654.7    0.05       0
  4991.5   0.013       0  5058.1    0.03       0  5062.5   0.013       0
  5135.5    0.04       0  5231.2    0.05       0  5333.5    0.12       0
  5385.0    0.05       0  5435.7    0.12       0  5608.0    0.04       0
Bank Sta=5058.1,5062.5
Exp/Cntr=0.3,0.1

Type RM Length L Ch R = 1,10408,529,529,529
BEGIN DESCRIPTION:
LGII4543
END DESCRIPTION:
XS GIS Cut Line= 3
      2513923.90     13556826.88      2513238.93     13556614.30
      2512270.50     13556437.15
#Sta/Elev= 30
  4193.9  239.43  4317.8  237.54  4768.6  227.15  4895.7  225.85  4976.1  225.83
  4994.2  224.54  4994.5  224.04  4998.7  224.54  5001.5  224.75  5026.9  225.61
  5044.2  224.86  5067.6  227.69  5087.9  227.53  5096.1  226.56  5108.2  225.60
  5148.9  225.71  5169.2  227.30  5295.1  229.75  5394.5  232.84  5488.1  236.50
  5616.5  240.43  5654.8  241.23  5677.5  240.67  5708.0  241.94  5754.3  242.53
  5824.6  243.50  5830.0  244.52  5870.7  244.84  5882.9  244.23  5895.6  244.83
#Mann=10,-1,0
  4193.9    0.12       0  4317.8    0.05       0  4994.2    0.05       0
  4998.7    0.05       0  5001.5   0.013       0  5096.1    0.12       0
  5295.1    0.05       0  5394.5    0.04       0  5488.1    0.12       0
  5754.3    0.05       0
Bank Sta=4994.2,4998.7
Exp/Cntr=0.3,0.1

Type RM Length L Ch R = 1,9879,658,658,658
BEGIN DESCRIPTION:
LGII4542
END DESCRIPTION:
XS GIS Cut Line= 3
      2514006.56     13556330.86      2513085.40     13556082.86
      2512364.98     13555763.98
#Sta/Elev= 30
  4275.8  239.28  4373.3  236.91  4655.7  228.17  4704.7  226.37  4819.4  225.03
  4878.1  222.83  4894.1  224.06  4941.4  224.23  4992.0  224.16  5002.3  223.68
  5006.4  222.37  5006.7  221.87  5011.1  222.37  5023.1  224.32  5042.4  225.17
  5064.5  223.58  5088.6  224.04  5123.4  226.36  5199.8  228.16  5340.3  231.44
  5706.1  243.12  5810.2  245.46  5833.5  245.44  5842.6  244.45  5908.8  245.27
  5955.4  246.37  5978.6  247.99  5984.8  250.31  6002.0  247.31  6017.6  246.70
#Mann=9,-1,0
  4275.8    0.12       0  4373.3    0.05       0  4655.7    0.12       0
  4941.4   0.013       0  5006.4    0.03       0  5011.1   0.013       0
  5042.4    0.05       0  5199.8    0.12       0  5978.6    0.05       0
Bank Sta=5006.4,5011.1
Exp/Cntr=0.3,0.1

Type RM Length L Ch R = 1,9221,599,599,599
BEGIN DESCRIPTION:
LGII4541
END DESCRIPTION:
XS GIS Cut Line= 3
      2514360.85     13555964.75      2513215.31     13555539.60
      2512389.28     13555421.60
#Sta/Elev= 30
  4163.8  242.95  4307.4  239.70  4461.5  235.43  4740.8  226.54  4884.7  223.01
  4916.7  227.23  4923.4  224.42  4928.7  226.80  4948.4  222.61  4953.7  226.52
  4978.8  227.19  4984.1  224.43  5002.8  222.51  5034.0  223.56  5074.3  221.77
  5074.6  221.27  5079.1  221.77  5106.6  223.15  5259.7  224.51  5492.1  232.01
  5567.8  234.43  5658.7  240.70  5664.7  242.98  5678.9  243.86  5689.0  241.56
  5743.3  243.82  5971.9  249.95  6021.7  247.23  6134.3  250.10  6220.1  249.53
#Mann=13,-1,0
  4163.8    0.12       0  4307.4    0.05       0  4461.5    0.12       0
  4740.8    0.05       0  5002.8   0.013       0  5074.3    0.05       0
  5079.1   0.013       0  5106.6    0.05       0  5259.7    0.12       0
  5492.1    0.03       0  5743.3    0.12       0  6021.7    0.05       0
  6134.3    0.04       0
Bank Sta=5074.3,5079.1
Exp/Cntr=0.3,0.1

Type RM Length L Ch R = 1,8622,504,504,504
BEGIN DESCRIPTION:
LGII4540
END DESCRIPTION:
XS GIS Cut Line= 3
      2514479.02     13555468.75      2513368.84     13555185.30
      2512424.01     13555138.06
#Sta/Elev= 30
  3963.3  242.07  3964.4  242.07  4111.9  239.12  4258.5  234.35  4334.2  231.97
  4467.6  227.86  4628.0  223.78  4783.8  221.50  4802.7  220.69  4813.7  223.16
  4834.4  223.19  4843.6  221.20  4855.0  222.53  4884.5  222.01  4985.3  220.37
  4986.8  220.36  4987.1  219.86  4991.7  220.36  5203.0  226.14  5383.3  235.69
  5493.6  239.68  5558.9  241.95  5803.8  248.54  5808.6  247.81  5812.4  247.23
  5817.4  248.73  5833.8  249.97  5843.8  245.95  5904.6  245.88  6055.1  250.39
#Mann=14,-1,0
  3963.3    0.05       0  3964.4    0.12       0  4258.5    0.05       0
  4334.2    0.12       0  4467.6    0.05       0  4783.8   0.013       0
  4884.5    0.05       0  4985.3    0.12       0  4986.8    0.05       0
  4991.7    0.12       0  5493.6    0.03       0  5558.9    0.12       0
  5808.6    0.05       0  5904.6    0.04       0
Bank Sta=4986.8,4991.7
Exp/Cntr=0.3,0.1

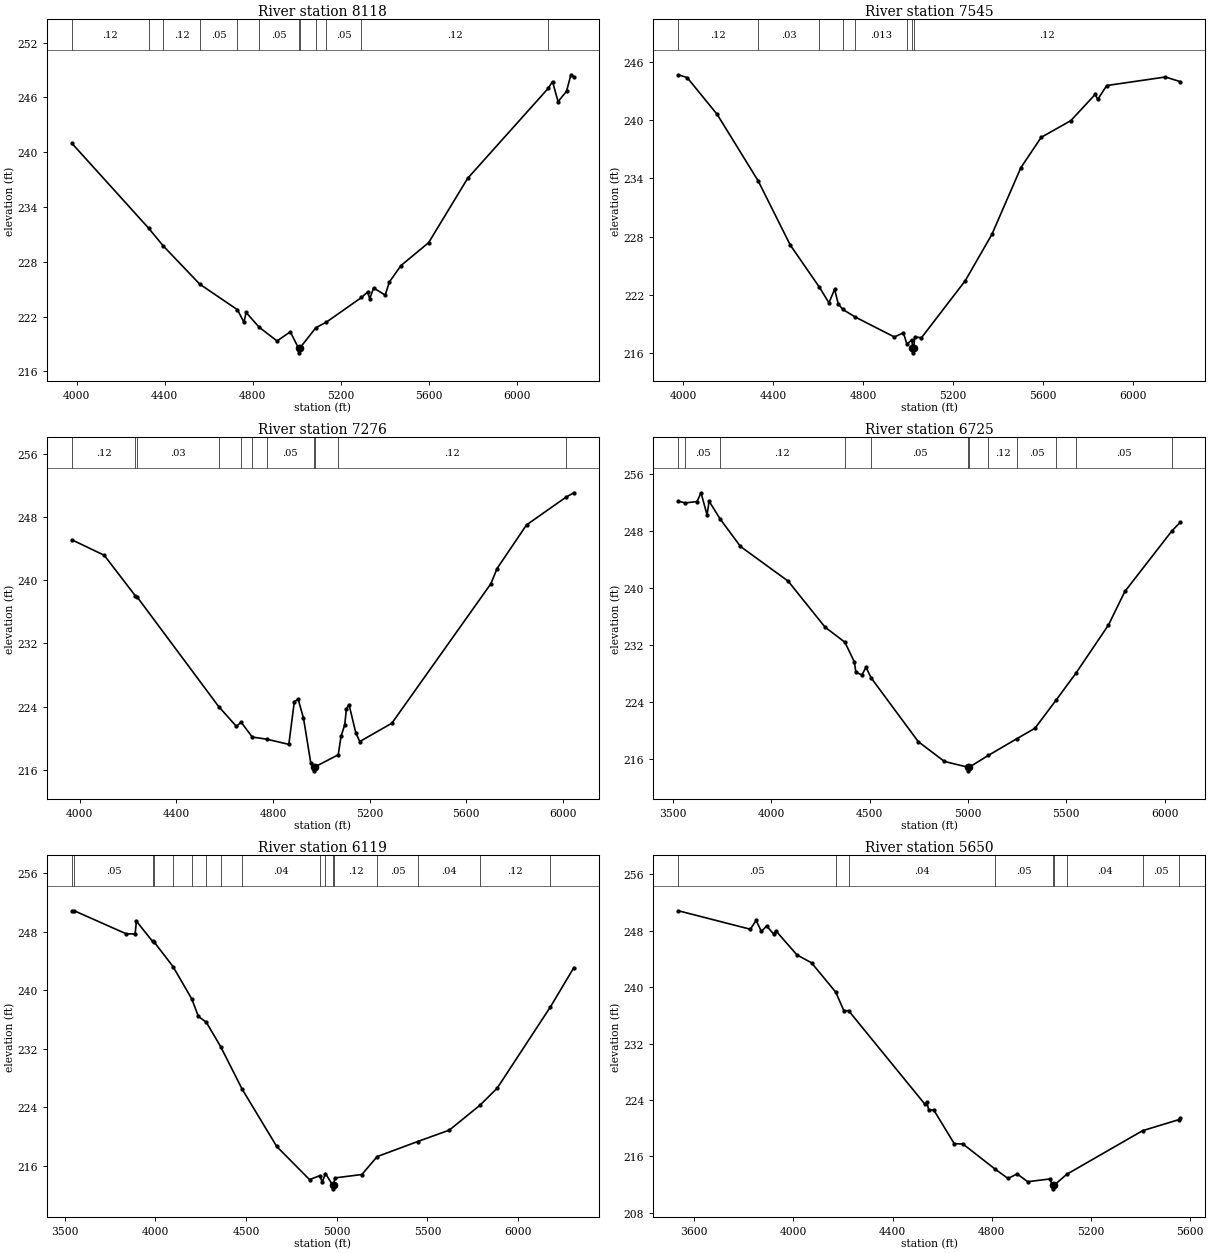
Type RM Length L Ch R = 1,8118,573,573,573
BEGIN DESCRIPTION:
LGII4539
END DESCRIPTION:
XS GIS Cut Line= 3
      2514644.30     13554831.00      2513203.50     13554724.71
      2512401.97     13554960.46
#Sta/Elev= 30
  3978.2  240.96  4326.4  231.68  4393.2  229.73  4558.8  225.55  4730.0  222.75
  4759.6  221.38  4769.6  222.45  4828.4  220.84  4910.0  219.33  4970.2  220.33
  5007.8  218.53  5008.2  218.03  5012.8  218.53  5086.7  220.79  5132.8  221.37
  5293.6  224.09  5321.1  224.68  5331.2  223.96  5348.6  225.13  5401.4  224.35
  5419.7  225.76  5472.7  227.58  5598.6  230.09  5775.8  237.13  6142.1  246.99
  6161.4  247.73  6186.7  245.53  6225.3  246.67  6244.8  248.47  6258.4  248.24
#Mann=12,-1,0
  3978.2    0.12       0  4326.4    0.05       0  4393.2    0.12       0
  4558.8    0.05       0  4730.0   0.013       0  4828.4    0.05       0
  5007.8    0.05       0  5012.8    0.05       0  5086.7    0.12       0
  5132.8    0.05       0  5293.6    0.12       0  6142.1    0.05       0
Bank Sta=5007.8,5012.8
Exp/Cntr=0.3,0.1

Type RM Length L Ch R = 1,7545,269,269,269
BEGIN DESCRIPTION:
LGII4538
END DESCRIPTION:
XS GIS Cut Line= 3
      2514691.51     13554559.36      2513888.47     13554264.13
      2512519.24     13554382.16
#Sta/Elev= 30
  3979.9  244.71  4018.8  244.42  4152.0  240.62  4334.5  233.74  4476.9  227.12
  4606.5  222.76  4648.7  221.15  4673.8  222.55  4690.0  221.05  4710.2  220.47
  4766.3  219.68  4939.3  217.63  4979.5  218.06  4995.3  216.88  5017.5  217.35
  5019.8  216.49  5020.2  215.99  5025.1  216.49  5029.7  217.63  5059.8  217.55
  5254.3  223.44  5372.8  228.23  5501.4  235.12  5591.8  238.25  5723.1  239.97
  5831.5  242.68  5842.7  242.16  5882.8  243.60  6143.8  244.48  6209.8  244.00
#Mann=8,-1,0
  3979.9    0.12       0  4334.5    0.03       0  4606.5   0.013       0
  4710.2    0.05       0  4766.3   0.013       0  4995.3    0.12       0
  5019.8    0.05       0  5025.1    0.12       0
Bank Sta=5019.8,5025.1
Exp/Cntr=0.3,0.1

Type RM Length L Ch R = 1,7276,551,551,551
BEGIN DESCRIPTION:
LGII4537
END DESCRIPTION:
XS GIS Cut Line= 3
      2514738.83     13554488.53      2513557.80     13553921.64
      2512801.92     13553791.72
#Sta/Elev= 30
  3967.8  245.11  4101.3  243.16  4229.9  238.03  4237.2  237.89  4575.5  223.98
  4648.7  221.48  4667.7  222.03  4713.9  220.14  4775.3  219.86  4865.3  219.21
  4888.0  224.61  4903.8  224.93  4926.0  222.54  4955.9  216.89  4967.7  216.36
  4968.1  215.86  4973.0  216.36  5069.7  217.89  5081.3  220.21  5096.8  221.72
  5103.5  223.70  5114.4  224.25  5142.6  220.65  5158.9  219.57  5291.7  221.89
  5701.3  239.55  5727.1  241.48  5848.9  247.00  6012.6  250.52  6044.8  251.07
#Mann=11,-1,0
  3967.8    0.12       0  4229.9   0.013       0  4237.2    0.03       0
  4575.5   0.013       0  4667.7    0.05       0  4713.9   0.013       0
  4775.3    0.05       0  4967.7    0.05       0  4973.0    0.05       0
  5069.7    0.12       0  6012.6    0.05       0
Bank Sta=4967.7,4973
Exp/Cntr=0.3,0.1

Type RM Length L Ch R = 1,6725,606,606,606
BEGIN DESCRIPTION:
LGII4536
END DESCRIPTION:
XS GIS Cut Line= 3
      2515317.45     13553886.20      2513439.70     13553484.67
      2512813.74     13553567.35
#Sta/Elev= 30
  3527.9  252.14  3563.3  251.91  3622.4  252.10  3642.9  253.33  3673.6  250.21
  3683.8  252.15  3739.2  249.69  3843.4  245.80  4085.7  240.94  4273.3  234.49
  4374.2  232.38  4421.8  229.65  4430.3  228.15  4461.0  227.79  4481.4  228.86
  4508.6  227.34  4747.3  218.43  4880.2  215.66  5000.3  214.84  5000.7  214.34
  5005.7  214.84  5103.8  216.51  5248.7  218.85  5340.4  220.31  5448.6  224.28
  5548.2  228.01  5714.0  234.78  5797.6  239.49  6037.1  248.00  6079.5  249.19
#Mann=12,-1,0
  3527.9    0.04       0  3563.3    0.05       0  3739.2    0.12       0
  4374.2   0.013       0  4508.6    0.05       0  5000.3    0.05       0
  5005.7    0.05       0  5103.8    0.12       0  5248.7    0.05       0
  5448.6    0.12       0  5548.2    0.05       0  6037.1    0.12       0
Bank Sta=5000.3,5005.7
Exp/Cntr=0.3,0.1

Type RM Length L Ch R = 1,6119,469,469,469
BEGIN DESCRIPTION:
LGII4535
END DESCRIPTION:
XS GIS Cut Line= 3
      2515341.14     13553555.55      2513486.94     13552858.74
      2512849.58     13553319.05
#Sta/Elev= 30
  3540.4  250.78  3553.1  250.85  3840.6  247.69  3888.8  247.69  3895.7  249.43
  3985.1  246.66  3992.3  246.62  4097.6  243.22  4201.6  238.77  4237.2  236.41
  4281.0  235.61  4360.3  232.27  4479.1  226.44  4669.4  218.62  4850.3  214.09
  4906.4  214.63  4920.2  213.74  4938.0  214.92  4977.9  213.33  4978.3  212.83
  4983.5  213.33  4989.1  214.32  5138.7  214.79  5223.1  217.24  5446.5  219.30
  5621.0  220.86  5790.9  224.29  5884.8  226.60  6178.2  237.71  6307.4  243.08
#Mann=17,-1,0
  3540.4    0.04       0  3553.1    0.05       0  3985.1    0.12       0
  3992.3    0.05       0  4097.6    0.04       0  4201.6   0.013       0
  4281.0    0.04       0  4360.3    0.05       0  4479.1    0.04       0
  4906.4    0.05       0  4938.0    0.12       0  4977.9    0.05       0
  4983.5    0.12       0  5223.1    0.05       0  5446.5    0.04       0
  5790.9    0.12       0  6178.2    0.04       0
Bank Sta=4977.9,4983.5
Exp/Cntr=0.3,0.1

Type RM Length L Ch R = 1,5650,491,491,491
BEGIN DESCRIPTION:
LGII4534
END DESCRIPTION:
XS GIS Cut Line= 2
      2515411.92     13553437.41      2513688.88     13552375.26
#Sta/Elev= 30
  3536.1  250.85  3826.2  248.23  3849.5  249.49  3870.7  247.92  3892.0  248.70
  3920.1  247.55  3928.7  248.03  4014.1  244.59  4072.9  243.47  4171.0  239.29
  4203.0  236.69  4222.6  236.67  4531.0  223.37  4539.0  223.67  4544.9  222.63
  4566.2  222.57  4648.5  217.81  4683.7  217.76  4814.7  214.16  4865.5  212.87
  4902.1  213.52  4944.7  212.41  5033.5  212.80  5045.0  211.90  5045.5  211.40
  5050.7  211.90  5102.5  213.47  5408.0  219.65  5554.7  221.22  5560.2  221.38
#Mann=9,-1,0
  3536.1    0.05       0  4171.0   0.013       0  4222.6    0.04       0
  4814.7    0.05       0  5045.0    0.05       0  5050.7    0.05       0
  5102.5    0.04       0  5408.0    0.05       0  5554.7    0.04       0
Bank Sta=5045,5050.7
Exp/Cntr=0.3,0.1

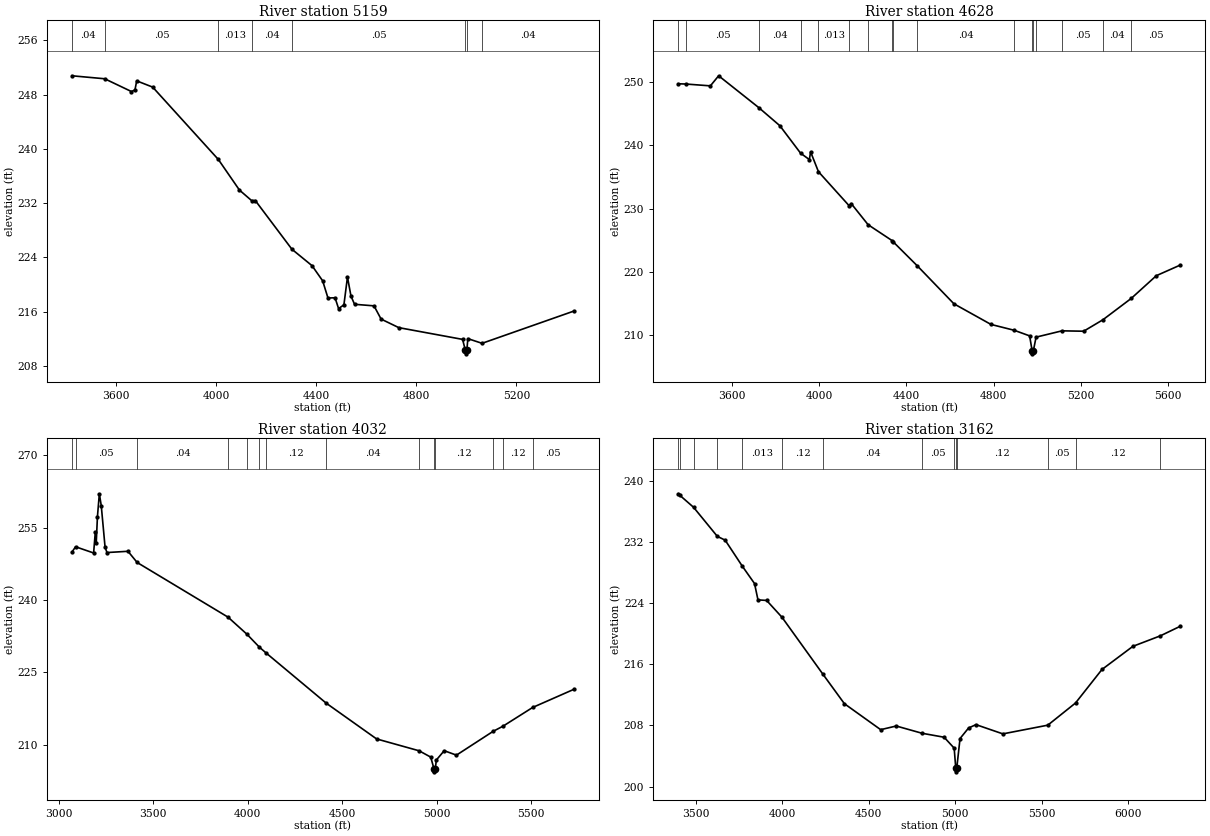
Type RM Length L Ch R = 1,5159,531,531,531
BEGIN DESCRIPTION:
LGII4533
END DESCRIPTION:
XS GIS Cut Line= 2
      2515447.36     13553378.35      2514006.61     13551984.84
#Sta/Elev= 30
  3424.9  250.76  3555.6  250.32  3662.4  248.44  3676.5  248.67  3683.5  250.01
  3747.3  249.09  4009.5  238.43  4093.8  233.92  4142.7  232.36  4157.3  232.37
  4303.4  225.20  4383.7  222.78  4426.1  220.55  4447.3  218.02  4475.6  218.05
  4489.7  216.46  4511.0  217.01  4525.2  221.10  4539.3  218.29  4553.5  217.09
  4631.2  216.86  4659.5  214.91  4730.2  213.65  4984.9  211.92  4996.2  210.29
  4996.6  209.79  5001.9  210.29  5006.0  212.03  5062.7  211.34  5429.3  216.09
#Mann=8,-1,0
  3424.9    0.04       0  3555.6    0.05       0  4009.5   0.013       0
  4142.7    0.04       0  4303.4    0.05       0  4996.2    0.05       0
  5001.9    0.05       0  5062.7    0.04       0
Bank Sta=4996.2,5001.9
Exp/Cntr=0.3,0.1

Type RM Length L Ch R = 1,4628,596,596,596
BEGIN DESCRIPTION:
LGII4532
END DESCRIPTION:
XS GIS Cut Line= 3
      2515506.44     13553283.91      2514845.08     13552055.67
      2514171.89     13551453.34
#Sta/Elev= 30
  3356.6  249.79  3391.1  249.75  3503.0  249.46  3540.8  251.06  3724.9  246.00
  3821.0  243.14  3916.0  238.78  3956.2  237.76  3961.9  238.99  3997.8  235.84
  4137.8  230.46  4147.7  230.79  4225.2  227.43  4334.9  224.91  4339.6  224.73
  4450.0  220.92  4618.2  214.88  4787.7  211.61  4894.0  210.68  4964.9  209.79
  4976.2  207.44  4976.7  206.94  4982.0  207.44  4994.4  209.59  5113.2  210.59
  5212.3  210.53  5300.6  212.35  5430.0  215.73  5545.0  219.34  5654.9  221.03
#Mann=17,-1,0
  3356.6    0.04       0  3391.1    0.05       0  3724.9    0.04       0
  3916.0    0.05       0  3997.8   0.013       0  4137.8    0.04       0
  4225.2    0.12       0  4334.9    0.04       0  4339.6    0.12       0
  4450.0    0.04       0  4894.0    0.05       0  4976.2    0.04       0
  4982.0    0.05       0  4994.4    0.04       0  5113.2    0.05       0
  5300.6    0.04       0  5430.0    0.05       0
Bank Sta=4976.2,4982
Exp/Cntr=0.3,0.1

Type RM Length L Ch R = 1,4032,870,870,870
BEGIN DESCRIPTION:
LGII4531
END DESCRIPTION:
XS GIS Cut Line= 4
      2515589.11     13553248.48      2515352.91     13551689.56
      2514667.93     13551193.54      2514431.76     13551193.54
#Sta/Elev= 30
  3068.7  249.93  3087.8  251.04  3183.5  249.75  3192.4  254.08  3197.4  251.87
  3203.7  257.27  3213.8  262.02  3223.9  259.58  3244.2  250.93  3254.3  249.84
  3365.5  250.10  3414.1  247.78  3895.5  236.45  3995.6  232.91  4061.6  230.23
  4095.7  229.07  4415.6  218.62  4682.4  211.21  4907.8  208.75  4969.3  207.44
  4987.2  204.89  4987.7  204.39  4993.1  204.89  4998.7  206.83  5040.5  208.77
  5105.4  207.85  5299.1  212.77  5352.8  213.87  5508.9  217.73  5727.3  221.49
#Mann=14,-1,0
  3068.7    0.04       0  3087.8    0.05       0  3414.1    0.04       0
  3895.5    0.05       0  3995.6    0.12       0  4061.6   0.013       0
  4095.7    0.12       0  4415.6    0.04       0  4907.8    0.12       0
  4987.2    0.05       0  4993.1    0.12       0  5299.1    0.05       0
  5352.8    0.12       0  5508.9    0.05       0
Bank Sta=4987.2,4993.1
Exp/Cntr=0.3,0.1

Type RM Length L Ch R = 1,3162,0,0,0
BEGIN DESCRIPTION:
LGII4530
END DESCRIPTION:
XS GIS Cut Line= 4
      2515683.58     13552445.41      2515695.39     13551063.63
      2515317.48     13550626.67      2514409.07     13550886.21
#Sta/Elev= 30
  3398.8  238.32  3407.0  238.12  3486.5  236.55  3624.2  232.74  3669.2  232.25
  3769.2  228.82  3839.2  226.57  3859.2  224.43  3909.2  224.36  3998.3  222.15
  4235.3  214.69  4359.2  210.84  4569.2  207.44  4659.3  207.92  4808.5  206.97
  4936.3  206.45  4994.5  205.02  5003.6  202.42  5004.0  201.92  5009.5  202.42
  5028.4  206.28  5077.8  207.66  5120.6  208.10  5276.3  206.89  5536.3  208.03
  5696.6  210.93  5849.7  215.32  6028.7  218.35  6188.2  219.73  6303.1  220.98
#Mann=14,-1,0
  3398.8    0.05       0  3407.0    0.12       0  3486.5    0.05       0
  3624.2    0.12       0  3769.2   0.013       0  3998.3    0.12       0
  4235.3    0.04       0  4808.5    0.05       0  4994.5    0.12       0
  5003.6    0.05       0  5009.5    0.12       0  5536.3    0.05       0
  5696.6    0.12       0  6188.2    0.05       0
Bank Sta=5003.6,5009.5
Exp/Cntr=0.3,0.1

Chan Stop Cuts=-1