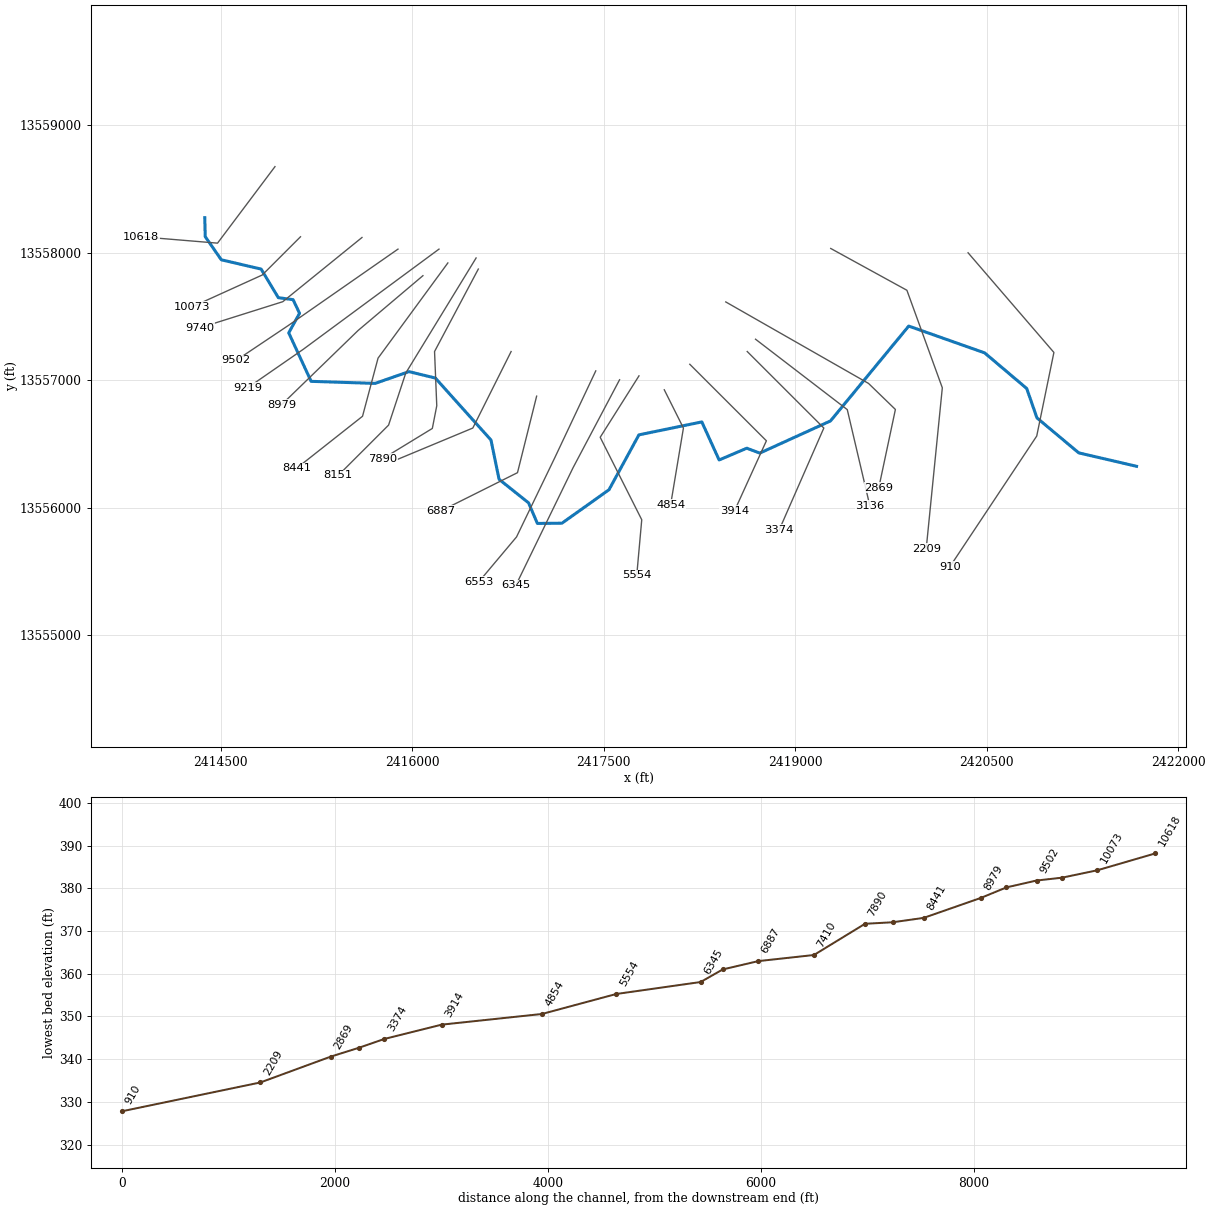
--- TRIB 3 TO SALT CREEK.prj (project) ---

Proj Title=TRIB 3 TO SALT CREEK Base Level Engineering
Current Plan=p01
Default Exp/Contr=0.3,0.1
English Units
Geom File=g01
Flow File=f01
Plan File=p01
BEGIN DESCRIPTION:
TRIB 3 TO SALT CREEK
END DESCRIPTION:

--- TRIB 3 TO SALT CREEK.p01 (plan) ---

Plan Title=Multiple Run
Short Identifier=Multiple
Geom File=g01
Flow File=f01
Subcritical Flow
K Sum by GR= 0
Std Step Tol= 0.01
Critical Tol= 0.01
Num of Std Step Trials= 20
Max Error Tol= 0.3
Flow Tol Ratio= 0.001
Split Flow NTrial= 30
Split Flow Tol= 0.02
Split Flow Ratio= 0.02
Log Output Level= 0
Friction Slope Method= 1
Unsteady Friction Slope Method= 2
Unsteady Bridges Friction Slope Method= 1
Parabolic Critical Depth
Global Vel Dist=  1 , 1 , 1
Global Log Level= 0
CheckData=True
Encroach Param= -1, 0, 0, 0
BEGIN DESCRIPTION:
Multiple Run
END DESCRIPTION:

--- TRIB 3 TO SALT CREEK.f01 (steady flow) ---

Flow Title=Multiple
Number of Profiles=7
Profile Names=10-year,25-year,50-year,1pct_min,100-year,1pct_plu,500-year
River Rch & RM= TRIB 3 TO SALT C,Reach-1,10618
     462     743     997     650    1297    2589    2172
River Rch & RM= TRIB 3 TO SALT C,Reach-1,8979
     694    1141    1551    1022    2040    4070    3495
River Rch & RM= TRIB 3 TO SALT C,Reach-1,2869
     806    1335    1826    1209    2412    4813    4175
Boundary for River Rch & Prof#=TRIB 3 TO SALT C,Reach-1,1
Up Type=0
Dn Type=3
Dn Slope=0.005
Boundary for River Rch & Prof#=TRIB 3 TO SALT C,Reach-1,2
Up Type=0
Dn Type=3
Dn Slope=0.005
Boundary for River Rch & Prof#=TRIB 3 TO SALT C,Reach-1,3
Up Type=0
Dn Type=3
Dn Slope=0.005
Boundary for River Rch & Prof#=TRIB 3 TO SALT C,Reach-1,4
Up Type=0
Dn Type=3
Dn Slope=0.005
Boundary for River Rch & Prof#=TRIB 3 TO SALT C,Reach-1,5
Up Type=0
Dn Type=3
Dn Slope=0.005
Boundary for River Rch & Prof#=TRIB 3 TO SALT C,Reach-1,6
Up Type=0
Dn Type=3
Dn Slope=0.005
Boundary for River Rch & Prof#=TRIB 3 TO SALT C,Reach-1,7
Up Type=0
Dn Type=3
Dn Slope=0.005

--- TRIB 3 TO SALT CREEK.g01 (geometry) ---

Geom Title=Existing Conditions

River Reach=TRIB 3 TO SALT C,Reach-1
Reach XY= 30
      2414375.00     13558275.00      2414378.51     13558126.45
      2414504.45     13557944.44      2414816.52     13557871.49
      2414951.30     13557647.37      2415066.88     13557631.67
      2415117.50     13557525.00      2415032.79     13557371.60
      2415208.29     13556991.20      2415709.61     13556975.09
      2415975.00     13557067.44      2416181.19     13557017.18
      2416617.19     13556531.19      2416680.82     13556222.69
      2416911.61     13556038.33      2416980.65     13555876.97
      2417173.45     13555878.75      2417542.13     13556141.45
      2417776.25     13556571.55      2418269.13     13556673.04
      2418404.71     13556374.61      2418621.71     13556466.90
      2418723.27     13556428.37      2419277.30     13556680.83
      2419890.16     13557424.64      2420484.79     13557214.48
      2420814.61     13556935.10      2420894.62     13556704.52
      2421222.30     13556430.36      2421675.00     13556325.00

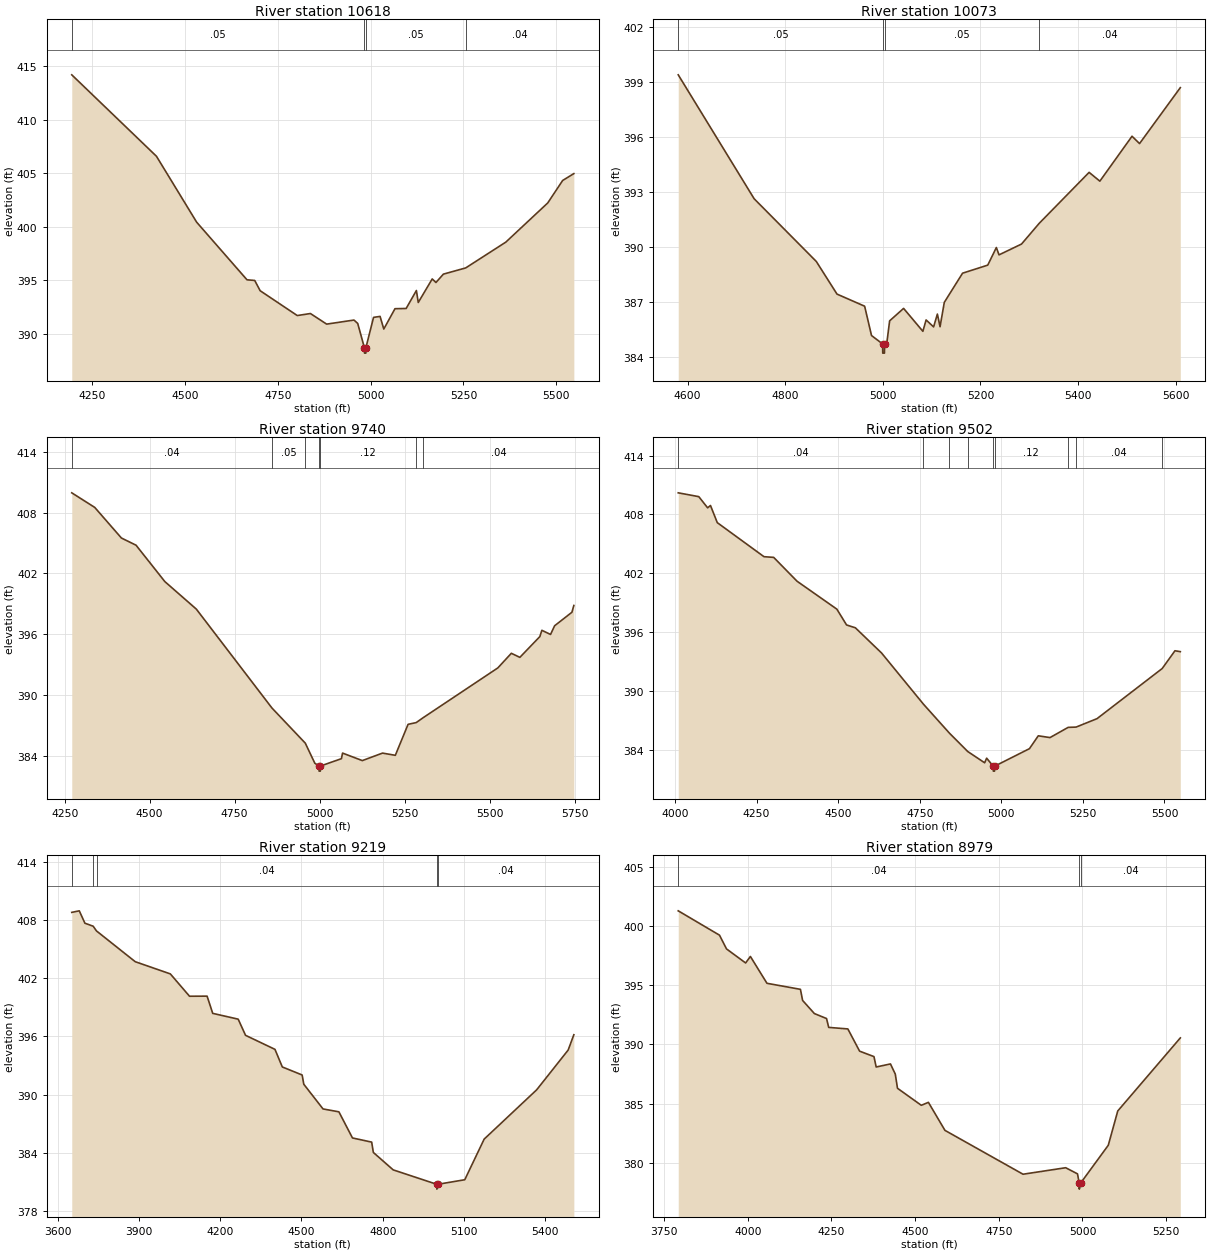
Type RM Length L Ch R = 1,10618,545,545,545
BEGIN DESCRIPTION:
TRIB 3 TO SALT CREEK 17.0
END DESCRIPTION:
XS GIS Cut Line= 3
      2414924.99     13558674.98      2414475.00     13558075.00
      2413874.96     13558125.00
#Sta/Elev= 30
  4195.1  414.18  4423.2  406.57  4531.5  400.41  4667.0  395.03  4687.8  394.97
  4702.4  394.01  4802.4  391.69  4837.8  391.88  4881.5  390.89  4955.1  391.27
  4965.2  390.95  4983.2  388.68  4983.5  388.18  4987.0  388.18  4987.2  388.68
  5007.8  391.52  5025.4  391.61  5035.4  390.43  5065.5  392.33  5095.6  392.35
  5123.2  394.03  5128.2  392.91  5165.8  395.11  5175.9  394.78  5195.9  395.56
  5256.0  396.14  5364.0  398.55  5476.9  402.21  5517.1  404.31  5547.2  404.95
#Mann=4,-1,0
  4195.1    0.05       0  4983.2    0.05       0  4987.2    0.05       0
  5256.0    0.04       0
Bank Sta=4983.2,4987.2
Exp/Cntr=0.3,0.1

Type RM Length L Ch R = 1,10073,333,333,333
BEGIN DESCRIPTION:
TRIB 3 TO SALT CREEK 16.0
END DESCRIPTION:
XS GIS Cut Line= 3
      2415124.97     13558124.97      2414825.00     13557825.00
      2414274.97     13557574.99
#Sta/Elev= 30
  4580.9  399.41  4736.4  392.65  4863.7  389.23  4906.1  387.45  4962.7  386.79
  4976.8  385.19  4999.6  384.73  4999.8  384.23  5003.3  384.23  5003.6  384.73
  5007.9  384.73  5013.9  385.99  5042.5  386.67  5082.0  385.42  5088.6  386.04
  5104.0  385.66  5111.7  386.36  5117.2  385.67  5125.9  387.00  5163.3  388.59
  5214.9  389.03  5232.5  389.99  5238.0  389.59  5284.1  390.18  5320.3  391.31
  5422.5  394.09  5444.5  393.61  5510.4  396.06  5525.8  395.66  5609.3  398.71
#Mann=4,-1,0
  4580.9    0.05       0  4999.6    0.05       0  5003.6    0.05       0
  5320.3    0.04       0
Bank Sta=4999.6,5003.6
Exp/Cntr=0.3,0.1

Type RM Length L Ch R = 1,9740,238,238,238
BEGIN DESCRIPTION:
Mapping XS e369517b
END DESCRIPTION:
XS GIS Cut Line= 3
      2415606.65     13558119.27      2414985.97     13557615.77
      2414339.59     13557411.88
#Sta/Elev= 30
  4271.0  409.96  4338.6  408.52  4417.0  405.50  4460.1  404.79  4544.8  401.20
  4637.5  398.48  4859.9  388.72  4958.0  385.25  4986.0  383.27  4998.3  382.99
  4998.6  382.49  5002.1  382.49  5002.3  382.99  5064.3  383.72  5067.6  384.27
  5125.8  383.53  5185.2  384.27  5222.8  384.05  5260.4  387.11  5284.2  387.28
  5305.0  387.77  5524.5  392.68  5564.1  394.12  5589.2  393.72  5648.0  395.77
  5653.9  396.39  5679.4  395.98  5691.5  396.84  5742.3  398.17  5748.0  398.84
#Mann=7,-1,0
  4271.0    0.04       0  4859.9    0.05       0  4958.0    0.12       0
  4998.3    0.05       0  5002.3    0.12       0  5284.2    0.05       0
  5305.0    0.04       0
Bank Sta=4998.3,5002.3
Exp/Cntr=0.3,0.1

Type RM Length L Ch R = 1,9502,283,283,283
BEGIN DESCRIPTION:
Mapping XS cc78d67c
END DESCRIPTION:
XS GIS Cut Line= 3
      2415888.75     13558028.11      2415029.37     13557429.14
      2414621.35     13557155.68
#Sta/Elev= 30
  4009.8  410.20  4072.8  409.81  4099.9  408.67  4108.6  408.91  4129.5  407.16
  4272.6  403.69  4302.3  403.62  4373.9  401.19  4496.0  398.34  4525.7  396.73
  4552.7  396.44  4633.0  393.87  4761.2  388.66  4841.0  385.70  4897.0  383.83
  4948.9  382.68  4955.0  383.15  4975.3  382.33  4975.6  381.83  4979.1  381.83
  4979.3  382.33  5086.2  384.12  5113.2  385.43  5149.2  385.25  5204.8  386.29
  5229.2  386.32  5293.3  387.18  5493.0  392.29  5532.1  394.10  5548.5  394.01
#Mann=9,-1,0
  4009.8    0.04       0  4761.2    0.05       0  4841.0   0.013       0
  4897.0    0.12       0  4975.3    0.05       0  4979.3    0.12       0
  5204.8   0.013       0  5229.2    0.04       0  5493.0   0.013       0
Bank Sta=4975.3,4979.3
Exp/Cntr=0.3,0.1

Type RM Length L Ch R = 1,9219,240,240,240
BEGIN DESCRIPTION:
Mapping XS 4ac6d084
END DESCRIPTION:
XS GIS Cut Line= 3
      2416209.95     13558028.12      2415146.56     13557242.51
      2414710.06     13556939.99
#Sta/Elev= 30
  3652.2  408.83  3679.9  408.99  3700.7  407.71  3731.2  407.40  3743.5  406.91
  3886.5  403.73  4016.0  402.47  4086.9  400.16  4151.7  400.17  4172.5  398.39
  4266.5  397.79  4293.6  396.12  4402.2  394.67  4429.3  392.85  4502.5  392.02
  4508.7  391.06  4579.6  388.51  4638.2  388.21  4688.3  385.51  4759.2  385.08
  4765.4  384.01  4838.6  382.21  4999.5  380.72  4999.7  380.22  5003.5  380.72
  5102.8  381.19  5174.4  385.39  5368.3  390.49  5484.5  394.60  5505.4  396.18
#Mann=5,-1,0
  3652.2    0.04       0  3731.2   0.013       0  3743.5    0.04       0
  4999.5    0.04       0  5003.5    0.04       0
Bank Sta=4999.5,5003.5
Exp/Cntr=0.3,0.1

Type RM Length L Ch R = 1,8979,538,538,538
BEGIN DESCRIPTION:
Mapping XS e5eaa102
END DESCRIPTION:
XS GIS Cut Line= 3
      2416084.05     13557819.76      2415576.24     13557390.08
      2414977.27     13556808.46
#Sta/Elev= 30
  3792.3  401.30  3915.6  399.24  3936.5  398.08  3993.6  396.89  4007.9  397.44
  4057.4  395.17  4157.4  394.66  4163.9  393.72  4199.1  392.61  4235.4  392.19
  4241.9  391.44  4299.1  391.31  4334.2  389.43  4377.1  388.97  4383.7  388.09
  4426.4  388.35  4440.8  387.49  4447.4  386.29  4518.5  384.85  4539.8  385.10
  4589.2  382.73  4822.5  379.02  4949.9  379.57  4985.3  379.05  4990.3  378.26
  4990.6  377.76  4994.3  378.26  5077.2  381.47  5105.5  384.37  5292.4  390.55
#Mann=3,-1,0
  3792.3    0.04       0  4990.3    0.04       0  4994.3    0.04       0
Bank Sta=4990.3,4994.3
Exp/Cntr=0.3,0.1

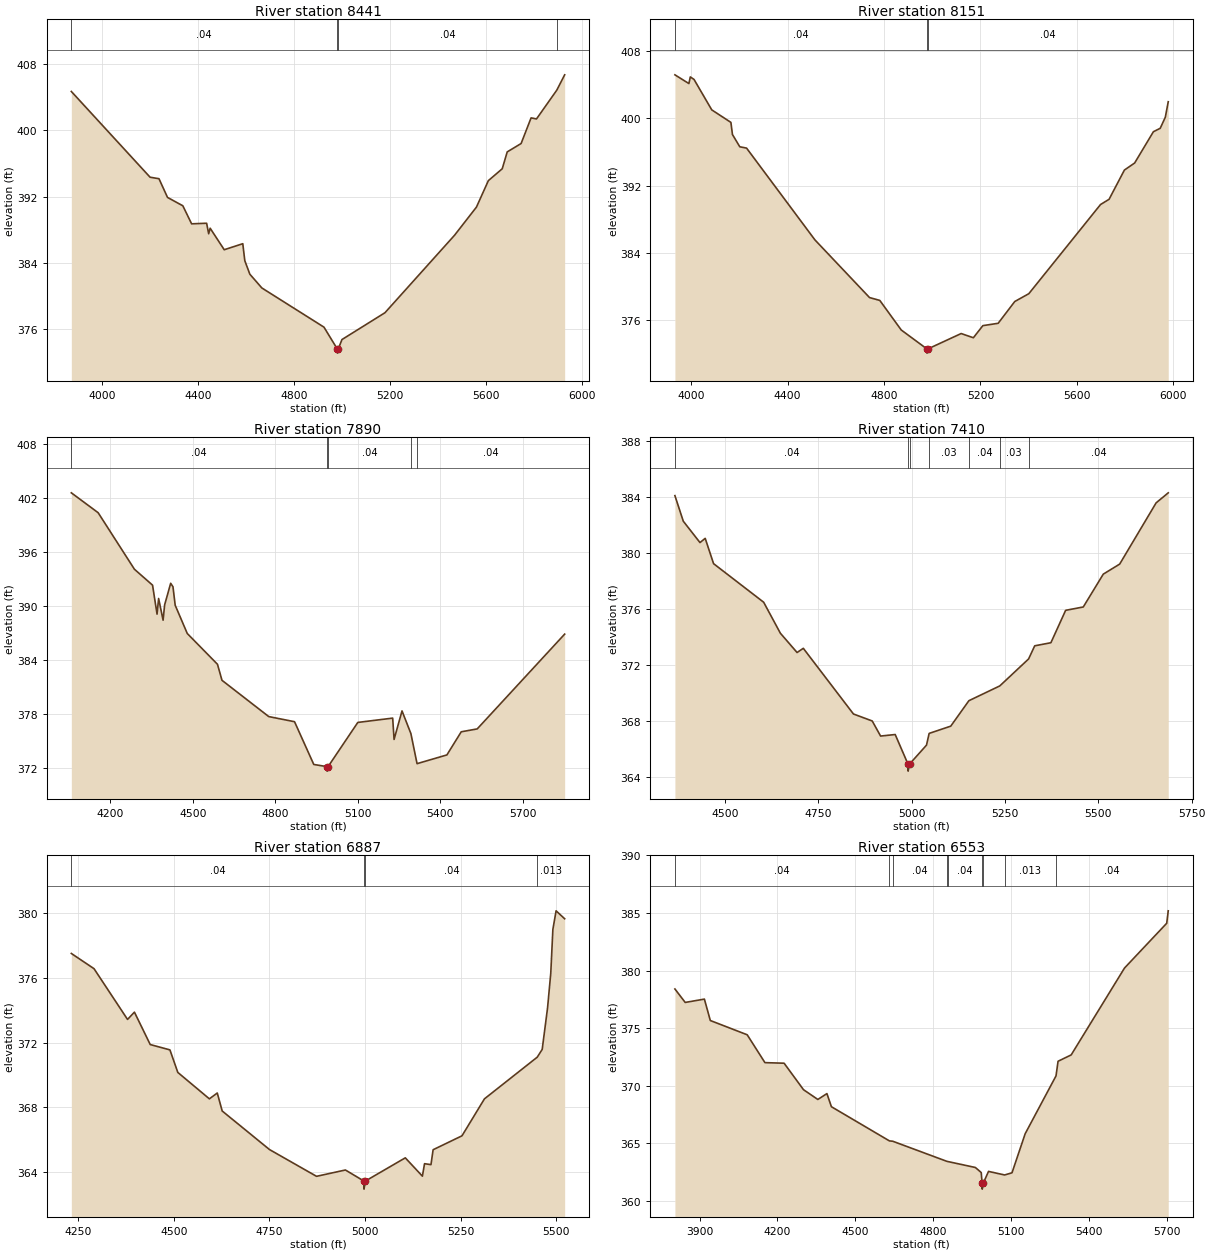
Type RM Length L Ch R = 1,8441,290,290,290
BEGIN DESCRIPTION:
Mapping XS 8b911dd4
END DESCRIPTION:
XS GIS Cut Line= 4
      2416279.38     13557919.60      2415732.49     13557173.07
      2415610.97     13556717.34      2415094.92     13556309.70
#Sta/Elev= 30
  3871.8  404.69  4199.8  394.33  4236.9  394.15  4272.4  391.89  4336.2  390.88
  4372.8  388.70  4435.3  388.77  4443.8  387.50  4450.0  388.17  4508.6  385.57
  4585.9  386.30  4594.3  384.25  4615.2  382.62  4665.4  380.95  4924.0  376.22
  4979.5  373.58  4979.8  373.08  4983.5  373.58  4999.0  374.72  5178.1  377.96
  5467.6  387.31  5559.1  390.72  5608.8  393.92  5666.5  395.35  5687.3  397.39
  5745.1  398.40  5786.7  401.50  5809.2  401.37  5893.8  404.85  5926.5  406.70
#Mann=4,-1,0
  3871.8    0.04       0  4979.5    0.04       0  4983.5    0.04       0
  5893.8    0.05       0
Bank Sta=4979.5,4983.5
Exp/Cntr=0.3,0.1

Type RM Length L Ch R = 1,8151,261,261,261
BEGIN DESCRIPTION:
Mapping XS 26cda084
END DESCRIPTION:
XS GIS Cut Line= 4
      2416500.72     13557958.65      2415949.51     13557055.88
      2415814.96     13556647.89      2415420.00     13556252.93
#Sta/Elev= 30
  3932.8  405.17  3990.8  404.13  3996.6  404.92  4012.1  404.62  4085.6  401.00
  4165.0  399.51  4171.4  398.07  4201.8  396.61  4230.0  396.45  4513.5  385.53
  4739.9  378.67  4782.5  378.33  4871.5  374.81  4977.9  372.56  4978.1  372.06
  4981.9  372.56  5119.9  374.39  5170.5  373.89  5209.9  375.33  5273.4  375.61
  5342.2  378.20  5400.5  379.13  5697.9  389.74  5733.3  390.36  5796.9  393.84
  5839.4  394.68  5917.1  398.40  5945.4  398.81  5966.6  400.13  5978.7  401.97
#Mann=3,-1,0
  3932.8    0.04       0  4977.9    0.04       0  4981.9    0.04       0
Bank Sta=4977.9,4981.9
Exp/Cntr=0.3,0.1

Type RM Length L Ch R = 1,7890,480,480,480
BEGIN DESCRIPTION:
Mapping XS 933fc6f9
END DESCRIPTION:
XS GIS Cut Line= 5
      2416518.08     13557871.83      2416175.20     13557225.15
      2416192.56     13556799.80      2416157.84     13556621.85
      2415768.63     13556384.00
#Sta/Elev= 30
  4058.0  402.62  4155.6  400.41  4287.6  394.13  4353.6  392.36  4369.9  389.14
  4375.6  390.88  4391.9  388.47  4397.5  390.17  4419.5  392.57  4427.9  392.18
  4435.9  390.13  4479.9  386.99  4589.8  383.57  4606.2  381.79  4776.4  377.76
  4870.2  377.19  4940.2  372.44  4988.3  372.20  4988.5  371.70  4992.3  372.20
  5100.4  377.11  5227.3  377.59  5232.4  375.22  5261.3  378.39  5293.6  375.87
  5316.0  372.53  5424.6  373.50  5476.8  376.07  5534.9  376.39  5853.1  386.92
#Mann=5,-1,0
  4058.0    0.04       0  4988.3    0.04       0  4992.3    0.04       0
  5293.6    0.05       0  5316.0    0.04       0
Bank Sta=4988.3,4992.3
Exp/Cntr=0.3,0.1

Type RM Length L Ch R = 1,7410,523,523,523
BEGIN DESCRIPTION:
TRIB 3 TO SALT CREEK 11.0
END DESCRIPTION:
XS GIS Cut Line= 3
      2416775.02     13557225.04      2416475.00     13556625.00
      2415874.97     13556374.99
#Sta/Elev= 30
  4366.4  384.11  4388.8  382.28  4433.5  380.75  4447.5  381.05  4469.9  379.24
  4604.0  376.48  4648.8  374.26  4693.5  372.88  4710.2  373.18  4844.4  368.48
  4894.7  367.98  4917.1  366.90  4956.2  367.01  4990.5  364.89  4990.8  364.39
  4994.5  364.89  5040.0  366.25  5047.1  367.09  5105.0  367.61  5153.5  369.43
  5236.3  370.49  5313.4  372.42  5329.8  373.36  5373.1  373.58  5412.6  375.90
  5459.8  376.14  5513.4  378.49  5557.3  379.21  5654.8  383.59  5687.3  384.31
#Mann=7,-1,0
  4366.4    0.04       0  4990.5    0.04       0  4994.5    0.04       0
  5047.1    0.03       0  5153.5    0.04       0  5236.3    0.03       0
  5313.4    0.04       0
Bank Sta=4990.5,4994.5
Exp/Cntr=0.3,0.1

Type RM Length L Ch R = 1,6887,334,334,334
BEGIN DESCRIPTION:
TRIB 3 TO SALT CREEK 10.0
END DESCRIPTION:
XS GIS Cut Line= 3
      2416975.00     13556875.00      2416825.00     13556275.00
      2416224.99     13555975.00
#Sta/Elev= 30
  4232.4  377.50  4291.7  376.56  4379.3  373.43  4397.3  373.88  4438.6  371.88
  4490.1  371.55  4510.7  370.16  4593.2  368.53  4613.8  368.89  4626.7  367.78
  4750.4  365.40  4873.2  363.75  4948.7  364.14  4997.0  363.46  4997.3  362.96
  5001.0  363.46  5105.2  364.89  5149.9  363.76  5155.5  364.53  5172.3  364.47
  5177.9  365.39  5253.4  366.25  5312.1  368.53  5450.0  371.10  5463.0  371.58
  5477.0  374.14  5485.4  376.28  5490.9  378.98  5499.3  380.13  5521.7  379.64
#Mann=4,-1,0
  4232.4    0.04       0  4997.0    0.04       0  5001.0    0.04       0
  5450.0   0.013       0
Bank Sta=4997,5001
Exp/Cntr=0.3,0.1

Type RM Length L Ch R = 1,6553,208,208,208
BEGIN DESCRIPTION:
Mapping XS dc64b5cf
END DESCRIPTION:
XS GIS Cut Line= 4
      2417438.21     13557073.21      2417117.04     13556391.82
      2416817.56     13555771.16      2416522.58     13555419.79
#Sta/Elev= 30
  3805.2  378.40  3844.9  377.23  3918.8  377.52  3941.6  375.66  4083.8  374.42
  4152.1  372.00  4226.0  371.95  4300.7  369.65  4356.0  368.80  4391.0  369.31
  4408.3  368.17  4631.9  365.20  4644.8  365.17  4853.8  363.42  4858.4  363.40
  4963.1  362.89  4985.7  362.45  4989.2  361.51  4989.5  361.01  4993.2  361.51
  5013.8  362.55  5075.8  362.24  5104.3  362.43  5155.0  365.82  5273.9  370.85
  5281.8  372.12  5332.3  372.67  5537.9  380.22  5700.5  384.11  5706.4  385.19
#Mann=9,-1,0
  3805.2    0.04       0  4631.9   0.013       0  4644.8    0.04       0
  4853.8   0.013       0  4858.4    0.04       0  4989.2    0.04       0
  4993.2    0.04       0  5075.8   0.013       0  5273.9    0.04       0
Bank Sta=4989.2,4993.2
Exp/Cntr=0.3,0.1

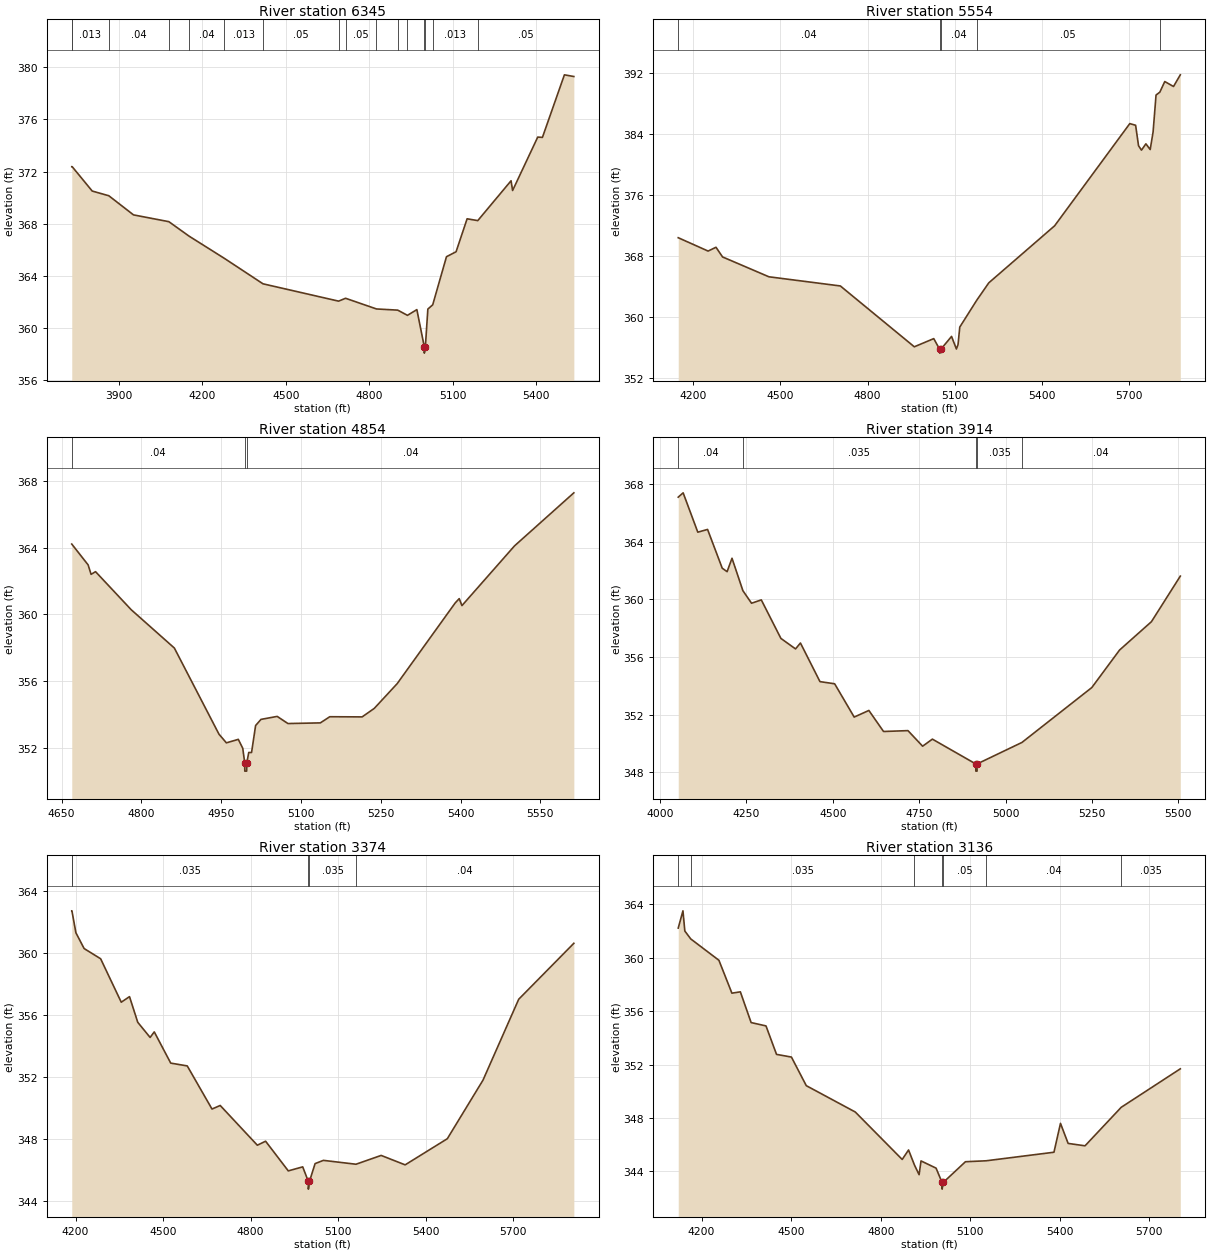
Type RM Length L Ch R = 1,6345,791,791,791
BEGIN DESCRIPTION:
Mapping XS bd49fc4b
END DESCRIPTION:
XS GIS Cut Line= 3
      2417624.85     13557003.79      2417260.27     13556313.69
      2416813.21     13555393.52
#Sta/Elev= 30
  3731.5  372.37  3733.0  372.37  3804.9  370.50  3864.5  370.14  3953.3  368.67
  4080.2  368.15  4152.8  367.04  4279.9  365.33  4418.4  363.38  4690.0  362.05
  4715.0  362.27  4826.1  361.45  4902.4  361.36  4937.3  360.96  4971.1  361.40
  4997.7  358.56  4998.0  358.06  5001.7  358.56  5010.6  361.44  5028.1  361.77
  5077.5  365.46  5112.0  365.84  5151.6  368.37  5189.9  368.23  5309.5  371.29
  5315.0  370.54  5405.3  374.64  5422.2  374.62  5501.1  379.42  5535.0  379.29
#Mann=16,-1,0
  3731.5    0.04       0  3733.0   0.013       0  3864.5    0.04       0
  4080.2   0.013       0  4152.8    0.04       0  4279.9   0.013       0
  4418.4    0.05       0  4690.0   0.013       0  4715.0    0.05       0
  4826.1    0.12       0  4902.4   0.013       0  4937.3    0.12       0
  4997.7    0.05       0  5001.7    0.12       0  5028.1   0.013       0
  5189.9    0.05       0
Bank Sta=4997.7,5001.7
Exp/Cntr=0.3,0.1

Type RM Length L Ch R = 1,5554,700,700,700
BEGIN DESCRIPTION:
Mapping XS 3fb2e78e
END DESCRIPTION:
XS GIS Cut Line= 4
      2417776.75     13557034.15      2417472.95     13556552.41
      2417798.47     13555905.71      2417759.41     13555471.70
#Sta/Elev= 30
  4148.0  370.39  4250.9  368.64  4278.0  369.14  4300.7  367.87  4460.4  365.27
  4706.4  364.07  4961.1  356.10  5028.1  357.17  5048.5  355.77  5048.7  355.27
  5052.5  355.77  5089.4  357.46  5106.1  355.81  5111.7  356.39  5117.7  358.68
  5176.0  362.19  5217.7  364.48  5444.4  371.95  5703.3  385.34  5723.4  385.12
  5733.4  382.44  5743.5  381.86  5758.8  382.69  5773.6  381.94  5783.6  384.26
  5793.7  389.08  5806.8  389.46  5823.8  390.85  5853.9  390.20  5877.3  391.73
#Mann=5,-1,0
  4148.0    0.04       0  5048.5    0.04       0  5052.5    0.04       0
  5176.0    0.05       0  5806.8   0.013       0
Bank Sta=5048.5,5052.5
Exp/Cntr=0.3,0.1

Type RM Length L Ch R = 1,4854,940,940,940
BEGIN DESCRIPTION:
TRIB 3 TO SALT CREEK 6.0
END DESCRIPTION:
XS GIS Cut Line= 3
      2417975.02     13556924.96      2418125.00     13556625.00
      2418025.01     13556025.04
#Sta/Elev= 30
  4669.2  364.23  4699.9  362.98  4705.5  362.41  4713.9  362.57  4781.0  360.28
  4862.0  357.98  4945.9  352.80  4959.8  352.28  4982.2  352.49  4990.6  351.95
  4994.2  351.08  4994.4  350.58  4997.9  350.58  4998.2  351.08  5001.8  351.70
  5007.1  351.70  5014.7  353.32  5024.8  353.69  5055.3  353.87  5075.5  353.44
  5136.4  353.48  5154.1  353.85  5214.9  353.84  5237.7  354.35  5280.8  355.84
  5389.8  360.69  5397.4  360.95  5402.5  360.53  5501.3  364.12  5612.8  367.31
#Mann=3,-1,0
  4669.2    0.04       0  4994.2    0.04       0  4998.2    0.04       0
Bank Sta=4994.2,4998.2
Exp/Cntr=0.3,0.1

Type RM Length L Ch R = 1,3914,540,540,540
BEGIN DESCRIPTION:
TRIB 3 TO SALT CREEK 4.0
END DESCRIPTION:
XS GIS Cut Line= 3
      2418174.99     13557125.01      2418775.00     13556525.00
      2418525.00     13555974.99
#Sta/Elev= 30
  4052.9  367.10  4067.1  367.40  4109.5  364.67  4137.8  364.86  4180.2  362.17
  4194.3  361.93  4208.5  362.86  4240.0  360.61  4265.0  359.74  4293.3  359.97
  4349.9  357.30  4392.3  356.57  4406.5  356.98  4463.0  354.30  4505.5  354.15
  4562.0  351.84  4604.5  352.30  4646.9  350.84  4717.6  350.90  4760.0  349.82
  4788.3  350.31  4913.7  348.59  4914.0  348.09  4917.5  348.09  4917.7  348.59
  5047.4  350.08  5249.6  353.89  5329.8  356.49  5422.1  358.46  5505.6  361.62
#Mann=5,-1,0
  4052.9    0.04       0  4240.0   0.035       0  4913.7   0.035       0
  4917.7   0.035       0  5047.4    0.04       0
Bank Sta=4913.7,4917.7
Exp/Cntr=0.3,0.1

Type RM Length L Ch R = 1,3374,238,238,238
BEGIN DESCRIPTION:
TRIB 3 TO SALT CREEK 3.0
END DESCRIPTION:
XS GIS Cut Line= 3
      2418624.99     13557225.01      2419225.00     13556625.00
      2418874.98     13555824.96
#Sta/Elev= 30
  4186.8  362.74  4187.3  362.74  4201.0  361.32  4229.2  360.30  4285.8  359.64
  4356.5  356.83  4384.8  357.19  4413.1  355.53  4455.5  354.55  4469.7  354.91
  4526.2  352.89  4582.8  352.71  4667.7  349.92  4695.9  350.15  4823.2  347.58
  4851.5  347.84  4929.3  345.92  4978.8  346.18  4998.0  345.24  4998.2  344.74
  5002.0  345.24  5021.2  346.39  5049.8  346.60  5161.5  346.35  5247.8  346.92
  5330.1  346.31  5474.7  348.00  5597.1  351.79  5719.5  357.02  5908.6  360.64
#Mann=5,-1,0
  4186.8    0.04       0  4187.3   0.035       0  4998.0   0.035       0
  5002.0   0.035       0  5161.5    0.04       0
Bank Sta=4998,5002
Exp/Cntr=0.3,0.1

Type RM Length L Ch R = 1,3136,267,267,267
BEGIN DESCRIPTION:
Mapping XS 37206146
END DESCRIPTION:
XS GIS Cut Line= 3
      2418689.97     13557321.50      2419408.71     13556769.42
      2419585.80     13556014.20
#Sta/Elev= 30
  4121.7  362.21  4137.5  363.50  4143.8  361.99  4163.5  361.40  4258.0  359.80
  4301.5  357.34  4329.8  357.44  4365.9  355.14  4415.7  354.89  4451.0  352.76
  4500.9  352.56  4550.7  350.42  4714.8  348.45  4872.0  344.90  4893.3  345.61
  4913.1  344.48  4928.6  343.76  4935.1  344.79  4985.5  344.25  5005.5  343.18
  5005.8  342.68  5009.5  343.18  5083.9  344.73  5153.2  344.80  5380.4  345.44
  5402.3  347.60  5427.9  346.10  5484.5  345.92  5605.7  348.80  5803.7  351.68
#Mann=7,-1,0
  4121.7    0.04       0  4163.5   0.035       0  4913.1    0.05       0
  5005.5    0.05       0  5009.5    0.05       0  5153.2    0.04       0
  5605.7   0.035       0
Bank Sta=5005.5,5009.5
Exp/Cntr=0.3,0.1

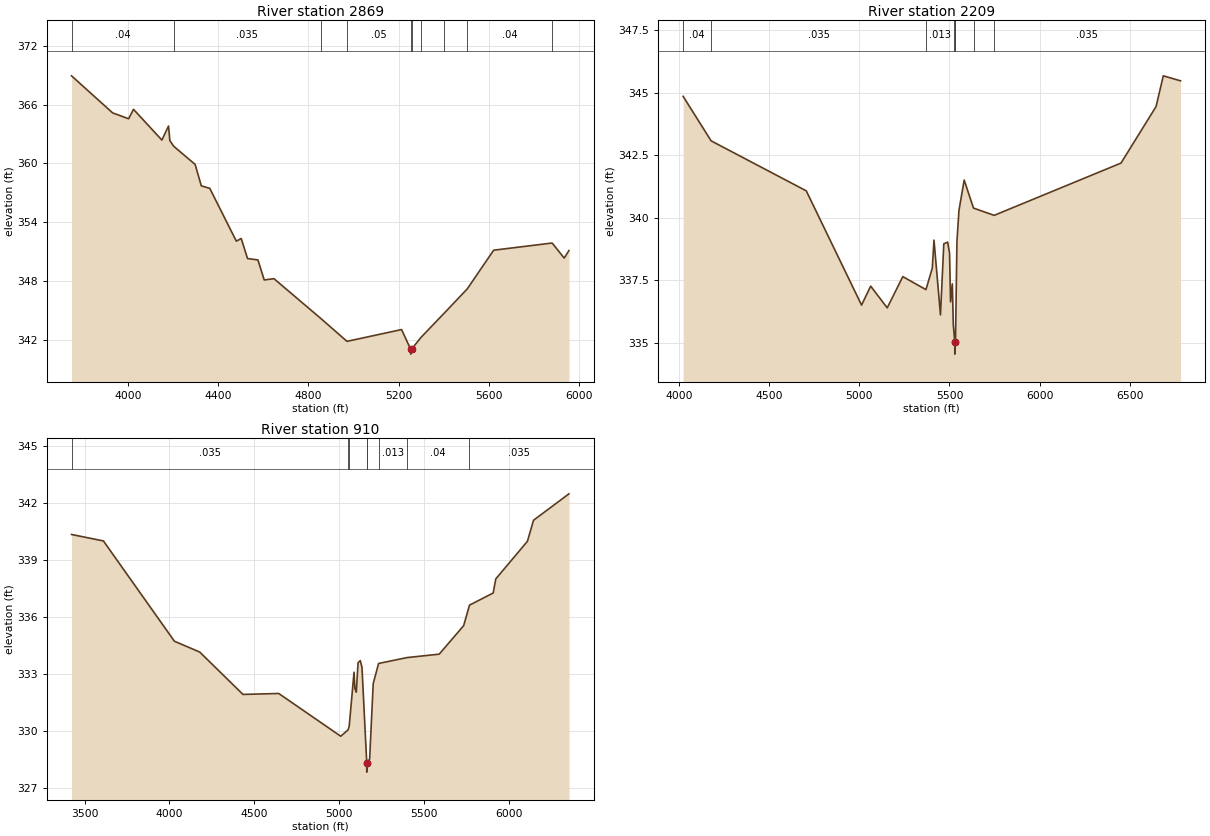
Type RM Length L Ch R = 1,2869,660,660,660
BEGIN DESCRIPTION:
TRIB 3 TO SALT CREEK 2.0
END DESCRIPTION:
XS GIS Cut Line= 4
      2418456.81     13557613.92      2419575.00     13556975.00
      2419785.71     13556770.78      2419655.81     13556158.19
#Sta/Elev= 30
  3748.5  368.92  3930.7  365.15  4001.9  364.55  4023.5  365.51  4149.5  362.38
  4179.0  363.81  4184.8  362.33  4201.9  361.75  4297.1  359.90  4324.4  357.72
  4361.9  357.47  4479.9  352.09  4501.5  352.36  4529.6  350.32  4575.7  350.18
  4603.7  348.14  4646.9  348.27  4855.8  344.20  4971.0  341.89  5213.2  343.09
  5253.6  341.09  5253.9  340.59  5257.6  341.09  5299.3  342.29  5403.3  344.78
  5504.7  347.23  5621.9  351.17  5881.4  351.90  5934.8  350.37  5956.0  351.13
#Mann=10,-1,0
  3748.5    0.04       0  4201.9   0.035       0  4855.8    0.04       0
  4971.0    0.05       0  5253.6    0.05       0  5257.6    0.05       0
  5299.3    0.04       0  5403.3   0.013       0  5504.7    0.04       0
  5881.4   0.035       0
Bank Sta=5253.6,5257.6
Exp/Cntr=0.3,0.1

Type RM Length L Ch R = 1,2209,1299,1299,1299
BEGIN DESCRIPTION:
LGII4629
END DESCRIPTION:
XS GIS Cut Line= 4
      2419279.14     13558033.17      2419875.92     13557705.37
      2420153.30     13556940.47      2420027.23     13555679.78
#Sta/Elev= 30
  4021.4  344.86  4176.8  343.08  4705.1  341.08  5012.0  336.51  5062.6  337.27
  5154.5  336.40  5241.0  337.65  5369.5  337.13  5404.7  337.99  5414.1  339.11
  5450.1  336.12  5468.6  338.96  5489.8  339.03  5500.5  338.59  5506.0  336.64
  5515.9  337.36  5521.4  335.72  5527.8  335.18  5529.4  335.05  5529.7  334.55
  5533.5  335.05  5541.5  339.05  5552.8  340.30  5581.7  341.51  5633.5  340.39
  5748.3  340.10  6452.3  342.19  6647.0  344.45  6687.2  345.68  6782.9  345.48
#Mann=8,-1,0
  4021.4    0.04       0  4176.8   0.035       0  5369.5   0.013       0
  5527.8    0.04       0  5529.4   0.035       0  5533.5    0.04       0
  5633.5   0.013       0  5748.3   0.035       0
Bank Sta=5529.4,5533.5
Exp/Cntr=0.3,0.1

Type RM Length L Ch R = 1,910,0,0,0
BEGIN DESCRIPTION:
LGII4628
END DESCRIPTION:
XS GIS Cut Line= 4
      2420355.05     13557999.54      2421027.47     13557217.85
      2420892.98     13556562.23      2420213.24     13555538.42
#Sta/Elev= 30
  3423.5  340.32  3611.3  339.98  4029.4  334.70  4178.6  334.13  4433.2  331.90
  4643.7  331.95  5008.8  329.70  5051.6  330.03  5058.7  330.22  5087.1  333.07
  5092.2  332.21  5100.6  332.02  5110.8  333.57  5123.9  333.68  5133.9  333.33
  5161.9  328.31  5162.1  327.81  5166.1  328.31  5179.0  328.50  5200.1  332.47
  5231.7  333.53  5399.6  333.84  5588.7  334.02  5732.7  335.52  5767.1  336.60
  5906.7  337.24  5921.8  337.98  6108.2  339.96  6144.3  341.07  6352.8  342.46
#Mann=8,-1,0
  3423.5   0.035       0  5051.6   0.013       0  5058.7    0.05       0
  5161.9   0.035       0  5166.1    0.05       0  5231.7   0.013       0
  5399.6    0.04       0  5767.1   0.035       0
Bank Sta=5161.9,5166.1
Exp/Cntr=0.3,0.1

Chan Stop Cuts=-1