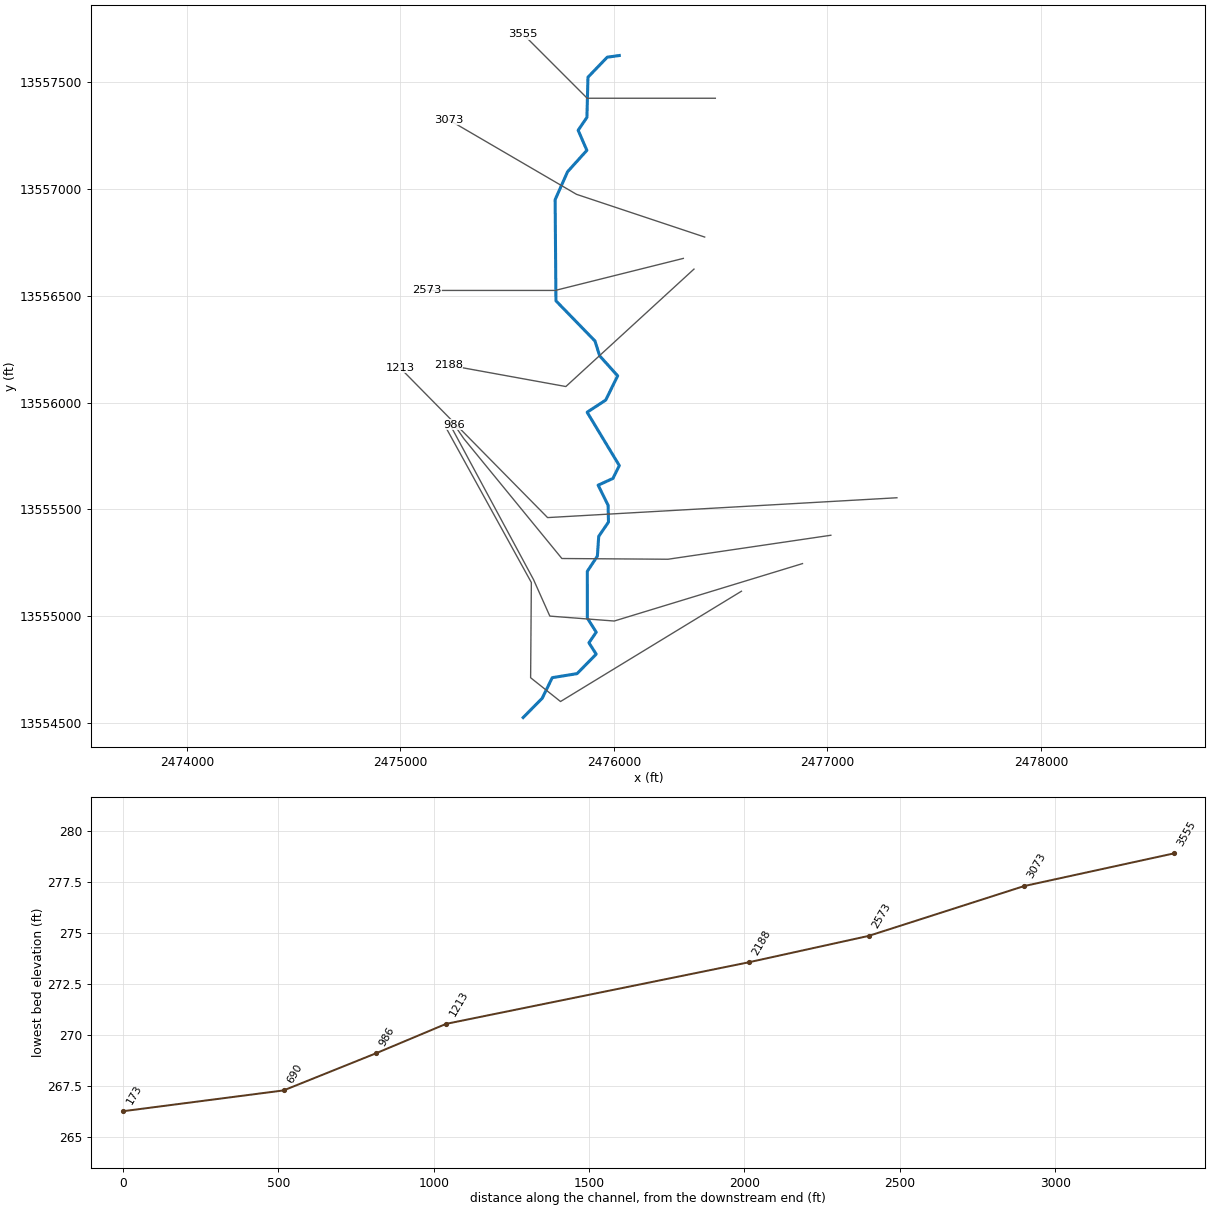
--- TRIB 3 TO SHILOH CREEK.prj (project) ---

Proj Title=TRIB 3 TO SHILOH CREEK Base Level Engineering
Current Plan=p01
Default Exp/Contr=0.3,0.1
English Units
Geom File=g01
Flow File=f01
Plan File=p01
BEGIN DESCRIPTION:
TRIB 3 TO SHILOH CREEK
END DESCRIPTION:

--- TRIB 3 TO SHILOH CREEK.p01 (plan) ---

Plan Title=Multiple Run
Short Identifier=Multiple
Geom File=g01
Flow File=f01
Subcritical Flow
K Sum by GR= 0
Std Step Tol= 0.01
Critical Tol= 0.01
Num of Std Step Trials= 20
Max Error Tol= 0.3
Flow Tol Ratio= 0.001
Split Flow NTrial= 30
Split Flow Tol= 0.02
Split Flow Ratio= 0.02
Log Output Level= 0
Friction Slope Method= 1
Unsteady Friction Slope Method= 2
Unsteady Bridges Friction Slope Method= 1
Parabolic Critical Depth
Global Vel Dist=  1 , 1 , 1
Global Log Level= 0
CheckData=True
Encroach Param= -1, 0, 0, 0
BEGIN DESCRIPTION:
Multiple Run
END DESCRIPTION:

--- TRIB 3 TO SHILOH CREEK.f01 (steady flow) ---

Flow Title=Multiple
Number of Profiles=7
Profile Names=10-year,25-year,50-year,1pct_min,100-year,1pct_plu,500-year
River Rch & RM= TRIB 3 TO SHILOH,Reach-1,3555
     472     750     997     643    1283    2560    2103
River Rch & RM= TRIB 3 TO SHILOH,Reach-1,1213
     445     706     937     603    1203    2401    1966
Boundary for River Rch & Prof#=TRIB 3 TO SHILOH,Reach-1,1
Up Type=0
Dn Type=3
Dn Slope=0.005
Boundary for River Rch & Prof#=TRIB 3 TO SHILOH,Reach-1,2
Up Type=0
Dn Type=3
Dn Slope=0.005
Boundary for River Rch & Prof#=TRIB 3 TO SHILOH,Reach-1,3
Up Type=0
Dn Type=3
Dn Slope=0.005
Boundary for River Rch & Prof#=TRIB 3 TO SHILOH,Reach-1,4
Up Type=0
Dn Type=3
Dn Slope=0.005
Boundary for River Rch & Prof#=TRIB 3 TO SHILOH,Reach-1,5
Up Type=0
Dn Type=3
Dn Slope=0.005
Boundary for River Rch & Prof#=TRIB 3 TO SHILOH,Reach-1,6
Up Type=0
Dn Type=3
Dn Slope=0.005
Boundary for River Rch & Prof#=TRIB 3 TO SHILOH,Reach-1,7
Up Type=0
Dn Type=3
Dn Slope=0.005

--- TRIB 3 TO SHILOH CREEK.g01 (geometry) ---

Geom Title=Existing Conditions

River Reach=TRIB 3 TO SHILOH,Reach-1
Reach XY= 30
      2476025.00     13557625.00      2475968.76     13557617.25
      2475878.52     13557523.55      2475873.62     13557335.44
      2475832.59     13557274.99      2475873.34     13557181.05
      2475783.16     13557081.05      2475724.79     13556950.09
      2475728.54     13556476.46      2475911.37     13556288.21
      2475933.20     13556218.95      2476017.70     13556125.08
      2475961.46     13556011.47      2475874.63     13555954.63
      2476025.39     13555704.73      2475995.47     13555644.70
      2475926.20     13555612.98      2475972.80     13555519.06
      2475974.62     13555440.27      2475928.86     13555373.40
      2475922.64     13555280.98      2475875.52     13555209.78
      2475875.65     13554990.16      2475917.22     13554924.90
      2475883.04     13554874.99      2475917.02     13554821.65
      2475827.45     13554730.53      2475711.35     13554711.74
      2475664.28     13554615.31      2475575.00     13554525.00

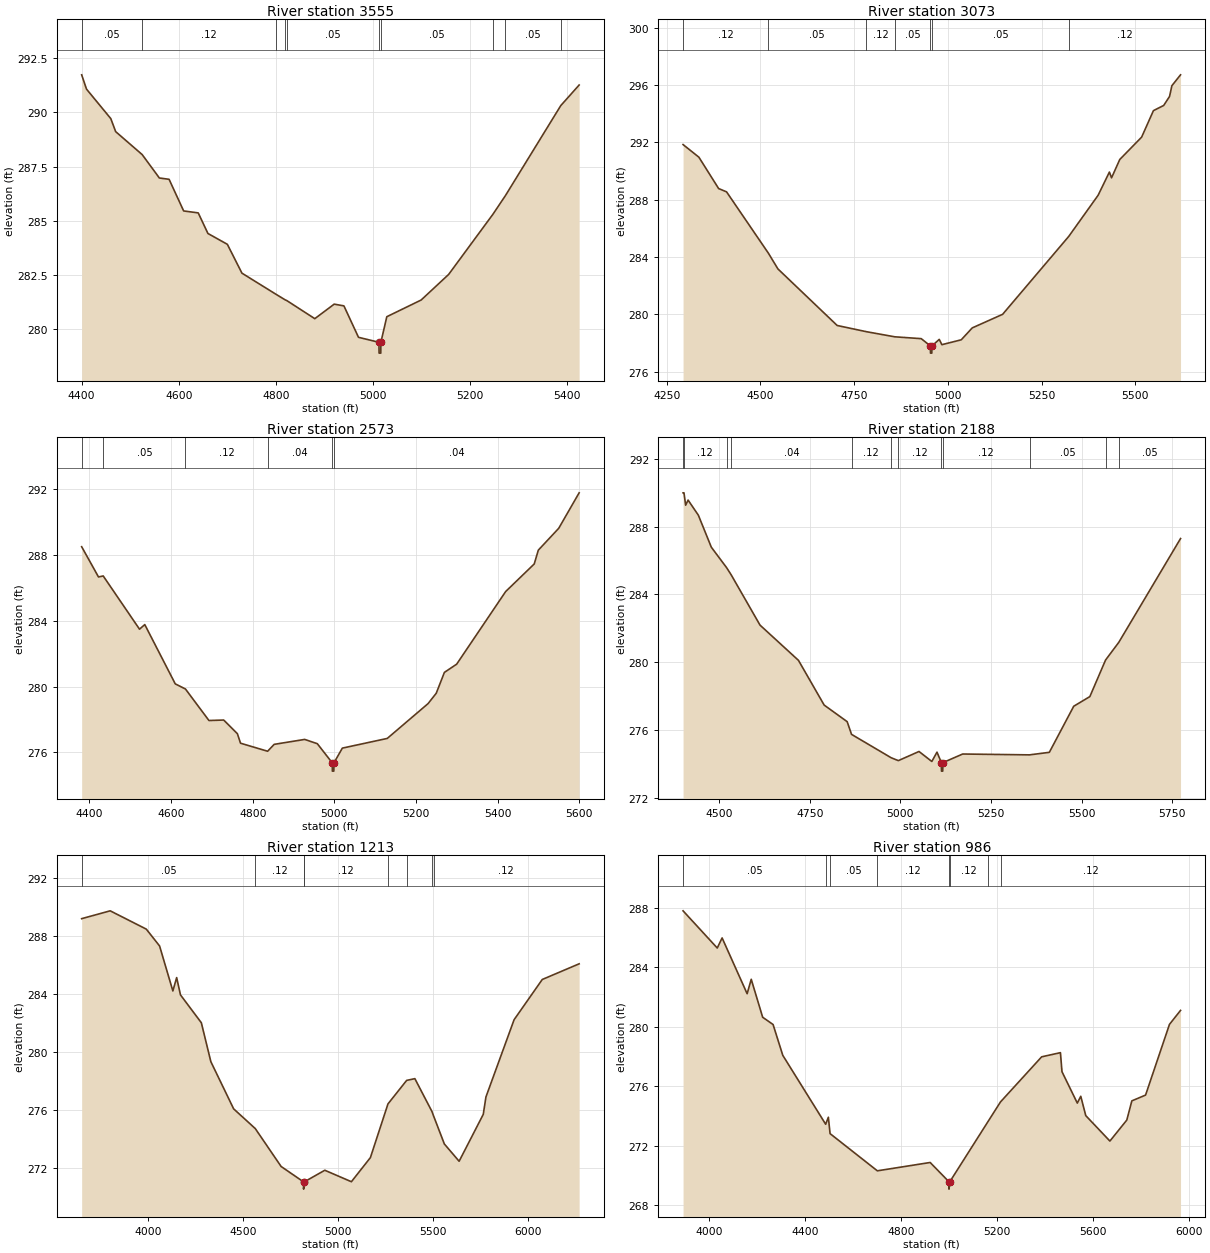
Type RM Length L Ch R = 1,3555,482,482,482
BEGIN DESCRIPTION:
TRIB 3 TO SHILOH CREEK 5.0
END DESCRIPTION:
XS GIS Cut Line= 3
      2476474.99     13557425.00      2475875.00     13557425.00
      2475574.97     13557725.03
#Sta/Elev= 30
  4400.0  291.73  4410.0  291.07  4460.0  289.71  4470.0  289.11  4524.6  288.05
  4560.0  286.97  4580.0  286.91  4610.0  285.45  4640.0  285.36  4660.0  284.41
  4700.0  283.91  4730.0  282.58  4800.5  281.60  4819.6  281.34  4822.0  281.32
  4880.0  280.48  4920.0  281.15  4940.0  281.07  4970.0  279.62  5012.1  279.39
  5012.4  278.89  5015.9  278.89  5016.1  279.39  5028.3  280.57  5099.0  281.34
  5155.6  282.52  5246.9  285.30  5272.6  286.16  5386.5  290.31  5424.3  291.26
#Mann=10,-1,0
  4400.0    0.05       0  4524.6    0.12       0  4800.5    0.05       0
  4819.6    0.12       0  4822.0    0.05       0  5012.1    0.05       0
  5016.1    0.05       0  5246.9    0.12       0  5272.6    0.05       0
  5386.5    0.12       0
Bank Sta=5012.1,5016.1
Exp/Cntr=0.3,0.1

Type RM Length L Ch R = 1,3073,500,500,500
BEGIN DESCRIPTION:
TRIB 3 TO SHILOH CREEK 4.0
END DESCRIPTION:
XS GIS Cut Line= 3
      2476425.04     13556774.99      2475825.00     13556975.00
      2475225.02     13557324.99
#Sta/Elev= 30
  4293.6  291.85  4335.8  290.97  4388.5  288.78  4409.6  288.55  4521.4  284.26
  4546.6  283.17  4704.7  279.22  4782.0  278.79  4858.1  278.43  4929.0  278.30
  4953.5  277.79  4953.7  277.29  4957.2  277.29  4957.5  277.79  4977.0  278.25
  4984.0  277.88  5035.7  278.22  5065.0  279.05  5146.1  280.00  5322.5  285.44
  5400.8  288.31  5430.9  289.93  5436.7  289.53  5458.6  290.81  5516.9  292.37
  5548.4  294.22  5575.7  294.58  5591.4  295.21  5597.6  295.96  5620.7  296.72
#Mann=7,-1,0
  4293.6    0.12       0  4521.4    0.05       0  4782.0    0.12       0
  4858.1    0.05       0  4953.5    0.05       0  4957.5    0.05       0
  5322.5    0.12       0
Bank Sta=4953.5,4957.5
Exp/Cntr=0.3,0.1

Type RM Length L Ch R = 1,2573,385,385,385
BEGIN DESCRIPTION:
TRIB 3 TO SHILOH CREEK 3.0
END DESCRIPTION:
XS GIS Cut Line= 3
      2476325.00     13556675.00      2475725.00     13556525.00
      2475124.96     13556525.00
#Sta/Elev= 30
  4381.1  288.51  4422.3  286.67  4433.9  286.73  4522.8  283.49  4535.7  283.77
  4610.4  280.16  4635.3  279.85  4692.9  277.93  4729.0  277.96  4762.5  277.13
  4770.2  276.55  4836.6  276.06  4852.7  276.48  4927.4  276.78  4958.3  276.52
  4995.0  275.35  4995.2  274.85  4998.7  274.85  4999.0  275.35  5019.6  276.25
  5129.6  276.84  5229.6  278.96  5249.6  279.59  5269.6  280.86  5299.6  281.36
  5419.6  285.78  5489.6  287.46  5499.6  288.30  5549.6  289.63  5599.6  291.79
#Mann=6,-1,0
  4381.1    0.12       0  4433.9    0.05       0  4635.3    0.12       0
  4836.6    0.04       0  4995.0    0.04       0  4999.0    0.04       0
Bank Sta=4995,4999
Exp/Cntr=0.3,0.1

Type RM Length L Ch R = 1,2188,975,975,975
BEGIN DESCRIPTION:
TRIB 3 TO SHILOH CREEK 2.0
END DESCRIPTION:
XS GIS Cut Line= 3
      2476375.00     13556625.00      2475775.00     13556075.00
      2475224.96     13556175.01
#Sta/Elev= 30
  4400.1  289.99  4402.6  289.99  4407.2  289.26  4414.0  289.56  4442.3  288.67
  4478.1  286.78  4520.0  285.58  4532.6  285.16  4612.5  282.18  4718.6  280.10
  4789.5  277.46  4853.0  276.48  4865.1  275.73  4974.4  274.35  4994.3  274.18
  5051.3  274.72  5086.7  274.13  5100.9  274.68  5113.1  274.06  5113.3  273.56
  5116.8  273.56  5117.1  274.06  5171.8  274.57  5356.3  274.52  5411.0  274.67
  5478.3  277.39  5522.8  277.96  5566.2  280.12  5602.6  281.16  5773.1  287.29
#Mann=12,-1,0
  4400.1    0.05       0  4402.6    0.12       0  4520.0    0.05       0
  4532.6    0.04       0  4865.1    0.12       0  4974.4    0.05       0
  4994.3    0.12       0  5113.1    0.05       0  5117.1    0.12       0
  5356.3    0.05       0  5566.2    0.12       0  5602.6    0.05       0
Bank Sta=5113.1,5117.1
Exp/Cntr=0.3,0.1

Type RM Length L Ch R = 1,1213,227,227,227
BEGIN DESCRIPTION:
TRIB 3 TO SHILOH CREEK 1.0
END DESCRIPTION:
XS GIS Cut Line= 3
      2477325.22     13555554.18      2475689.44     13555461.29
      2474997.99     13556163.07
#Sta/Elev= 30
  3648.4  289.17  3798.9  289.71  3989.2  288.45  4059.3  287.29  4129.4  284.19
  4149.4  285.11  4169.5  283.92  4279.6  282.00  4329.7  279.32  4449.9  276.07
  4564.1  274.71  4700.3  272.10  4818.5  271.04  4818.8  270.54  4822.5  271.04
  4930.7  271.84  5070.9  271.05  5171.1  272.71  5263.8  276.41  5362.4  278.03
  5405.7  278.15  5495.7  275.89  5504.4  275.58  5561.2  273.65  5639.1  272.46
  5766.4  275.69  5780.5  276.89  5929.0  282.21  6077.5  284.98  6272.0  286.06
#Mann=8,-1,0
  3648.4    0.05       0  4564.1    0.12       0  4818.5    0.05       0
  4822.5    0.12       0  5263.8    0.05       0  5362.4    0.12       0
  5495.7    0.05       0  5504.4    0.12       0
Bank Sta=4818.5,4822.5
Exp/Cntr=0.3,0.1

Type RM Length L Ch R = 1,986,296,296,296
BEGIN DESCRIPTION:
3
END DESCRIPTION:
XS GIS Cut Line= 5
      2477015.88     13555378.61      2476253.36     13555266.28
      2475756.37     13555269.68      2475296.83     13555831.35
      2475252.59     13555896.00
#Sta/Elev= 30
  3892.4  287.79  4034.8  285.29  4055.0  285.97  4159.2  282.22  4176.3  283.19
  4223.9  280.64  4267.3  280.15  4307.7  278.08  4486.3  273.45  4497.5  273.92
  4504.6  272.82  4701.5  270.32  4921.5  270.88  4999.5  269.59  4999.8  269.09
  5003.5  269.59  5161.6  273.61  5214.4  274.95  5385.8  277.98  5464.0  278.26
  5470.5  276.98  5534.3  274.87  5548.7  275.33  5569.5  274.03  5670.0  272.32
  5740.4  273.73  5761.4  275.02  5818.6  275.41  5918.1  280.16  5964.2  281.10
#Mann=8,-1,0
  3892.4    0.05       0  4486.3    0.12       0  4504.6    0.05       0
  4701.5    0.12       0  4999.5    0.05       0  5003.5    0.12       0
  5161.6    0.05       0  5214.4    0.12       0
Bank Sta=4999.5,5003.5
Exp/Cntr=0.3,0.1

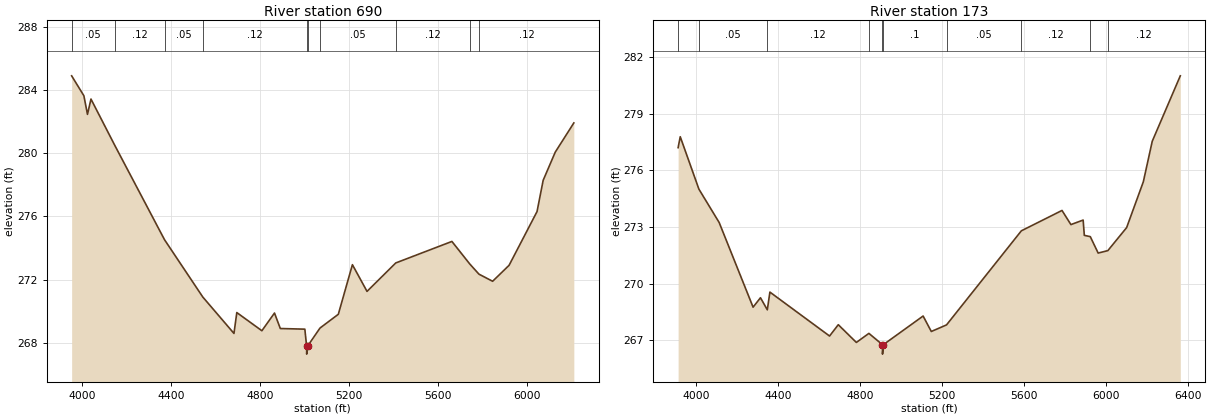
Type RM Length L Ch R = 1,690,517,517,517
BEGIN DESCRIPTION:
2
END DESCRIPTION:
XS GIS Cut Line= 5
      2476883.14     13555245.86      2476001.46     13554976.93
      2475700.00     13555000.00      2475623.61     13555170.96
      2475221.93     13555916.46
#Sta/Elev= 30
  3952.6  284.89  4007.6  283.63  4023.8  282.45  4039.5  283.42  4147.3  280.47
  4370.2  274.52  4542.5  270.89  4682.5  268.59  4695.3  269.91  4808.0  268.76
  4864.7  269.88  4890.9  268.90  5001.2  268.86  5009.2  267.78  5009.5  267.28
  5013.2  267.78  5069.4  268.93  5151.7  269.80  5215.1  272.94  5280.8  271.25
  5410.1  273.05  5662.5  274.41  5743.1  272.98  5784.2  272.34  5845.6  271.89
  5919.6  272.90  6045.3  276.30  6072.9  278.28  6127.2  280.06  6210.8  281.91
#Mann=10,-1,0
  3952.6    0.05       0  4147.3    0.12       0  4370.2    0.05       0
  4542.5    0.12       0  5009.2    0.05       0  5013.2    0.12       0
  5069.4    0.05       0  5410.1    0.12       0  5743.1    0.05       0
  5784.2    0.12       0
Bank Sta=5009.2,5013.2
Exp/Cntr=0.3,0.1

Type RM Length L Ch R = 1,173,0,0,0
BEGIN DESCRIPTION:
1
END DESCRIPTION:
XS GIS Cut Line= 5
      2476597.16     13555116.49      2475750.00     13554600.00
      2475610.00     13554711.42      2475613.40     13555157.35
      2475211.74     13555885.79
#Sta/Elev= 30
  3912.9  277.21  3923.3  277.79  4014.3  275.01  4113.1  273.24  4278.5  268.75
  4314.5  269.25  4347.9  268.61  4360.5  269.55  4651.4  267.22  4694.0  267.82
  4782.1  266.88  4843.2  267.36  4909.5  266.76  4909.7  266.26  4913.5  266.76
  5107.6  268.28  5147.6  267.46  5221.8  267.81  5586.7  272.80  5784.9  273.88
  5828.4  273.13  5888.0  273.37  5893.7  272.56  5922.9  272.49  5961.2  271.62
  6008.5  271.75  6100.1  272.97  6181.5  275.40  6225.0  277.55  6361.8  281.02
#Mann=10,-1,0
  3912.9    0.12       0  4014.3    0.05       0  4347.9    0.12       0
  4843.2     0.1       0  4909.5    0.05       0  4913.5     0.1       0
  5221.8    0.05       0  5586.7    0.12       0  5922.9    0.05       0
  6008.5    0.12       0
Bank Sta=4909.5,4913.5
Exp/Cntr=0.3,0.1

Chan Stop Cuts=-1