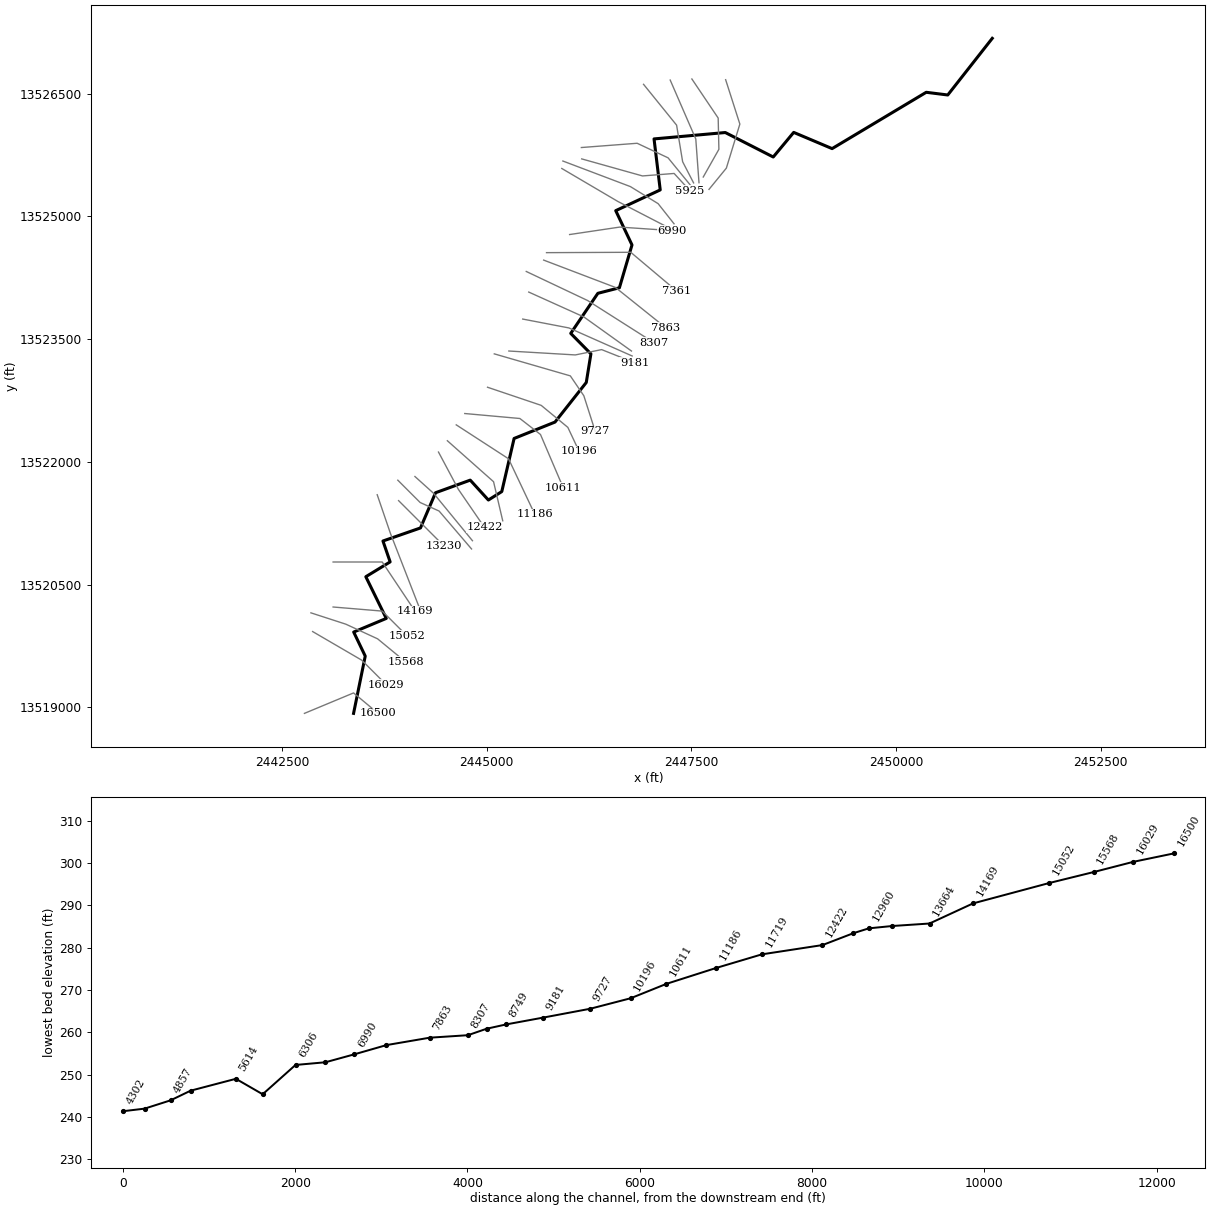
--- TRIB 3 TO SMITH CREEK.prj (project) ---

Proj Title=TRIB 3 TO SMITH CREEK Base Level Engineering
Current Plan=p01
Default Exp/Contr=0.3,0.1
English Units
Geom File=g01
Flow File=f01
Plan File=p01
BEGIN DESCRIPTION:
TRIB 3 TO SMITH CREEK
END DESCRIPTION:

--- TRIB 3 TO SMITH CREEK.p01 (plan) ---

Plan Title=Multiple Run
Short Identifier=Multiple
Geom File=g01
Flow File=f01
Subcritical Flow
K Sum by GR= 0
Std Step Tol= 0.01
Critical Tol= 0.01
Num of Std Step Trials= 20
Max Error Tol= 0.3
Flow Tol Ratio= 0.001
Split Flow NTrial= 30
Split Flow Tol= 0.02
Split Flow Ratio= 0.02
Log Output Level= 0
Friction Slope Method= 1
Unsteady Friction Slope Method= 2
Unsteady Bridges Friction Slope Method= 1
Parabolic Critical Depth
Global Vel Dist=  1 , 1 , 1
Global Log Level= 0
CheckData=True
Encroach Param= -1, 0, 0, 0
BEGIN DESCRIPTION:
Multiple Run
END DESCRIPTION:

--- TRIB 3 TO SMITH CREEK.f01 (steady flow) ---

Flow Title=Multiple
Number of Profiles=7
Profile Names=10-year,25-year,50-year,1pct_min,100-year,1pct_plu,500-year
River Rch & RM= TRIB 3 TO SMITH ,Reach-1,16500
     452     717     951     612    1222    2438    1993
River Rch & RM= TRIB 3 TO SMITH ,Reach-1,14169
     701    1139    1536    1003    2001    3993    3362
River Rch & RM= TRIB 3 TO SMITH ,Reach-1,10196
     942    1556    2122    1400    2793    5572    4789
River Rch & RM= TRIB 3 TO SMITH ,Reach-1,7863
    1105    1839    2520    1668    3329    6642    5755
River Rch & RM= TRIB 3 TO SMITH ,Reach-1,3561
    1304    2188    3014    2006    4002    7985    6987
Boundary for River Rch & Prof#=TRIB 3 TO SMITH ,Reach-1,1
Up Type=0
Dn Type=3
Dn Slope=0.005
Boundary for River Rch & Prof#=TRIB 3 TO SMITH ,Reach-1,2
Up Type=0
Dn Type=3
Dn Slope=0.005
Boundary for River Rch & Prof#=TRIB 3 TO SMITH ,Reach-1,3
Up Type=0
Dn Type=3
Dn Slope=0.005
Boundary for River Rch & Prof#=TRIB 3 TO SMITH ,Reach-1,4
Up Type=0
Dn Type=3
Dn Slope=0.005
Boundary for River Rch & Prof#=TRIB 3 TO SMITH ,Reach-1,5
Up Type=0
Dn Type=3
Dn Slope=0.005
Boundary for River Rch & Prof#=TRIB 3 TO SMITH ,Reach-1,6
Up Type=0
Dn Type=3
Dn Slope=0.005
Boundary for River Rch & Prof#=TRIB 3 TO SMITH ,Reach-1,7
Up Type=0
Dn Type=3
Dn Slope=0.005

--- TRIB 3 TO SMITH CREEK.g01 (geometry) ---

Geom Title=Existing Conditions

River Reach=TRIB 3 TO SMITH ,Reach-1
Reach XY= 30
      2443375.00     13518925.00      2443517.47     13519624.99
      2443376.57     13519918.96      2443774.45     13520085.63
      2443524.52     13520595.16      2443821.57     13520776.22
      2443733.95     13521031.69      2444192.14     13521191.28
      2444376.22     13521621.57      2444799.88     13521775.54
      2445021.38     13521532.48      2445185.11     13521635.65
      2445335.48     13522284.85      2445835.16     13522485.28
      2446216.86     13522968.94      2446273.38     13523318.97
      2446027.14     13523569.03      2446358.32     13524058.78
      2446621.47     13524126.45      2446775.24     13524650.08
      2446576.61     13525068.98      2447120.01     13525322.45
      2447044.42     13525945.75      2447914.52     13526023.81
      2448500.13     13525724.70      2448750.03     13526025.51
      2449219.06     13525827.26      2450368.38     13526515.59
      2450631.48     13526482.69      2451175.00     13527175.00

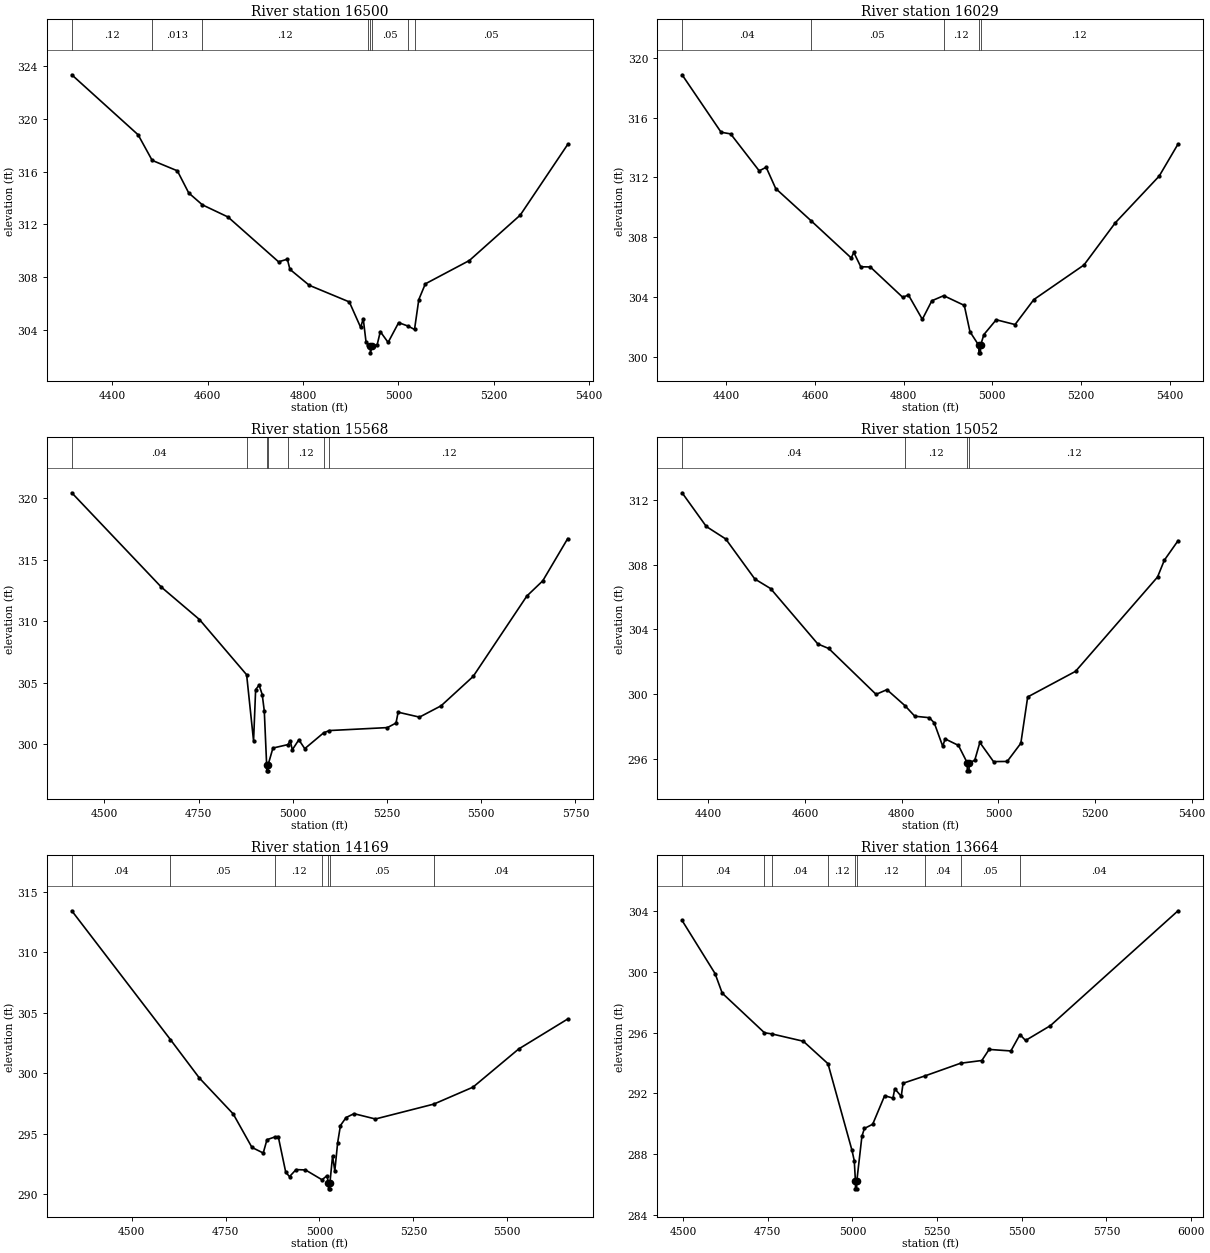
Type RM Length L Ch R = 1,16500,471,471,471
BEGIN DESCRIPTION:
TRIB 3 TO SMITH CREEK 29.0
END DESCRIPTION:
XS GIS Cut Line= 3
      2442775.01     13518925.00      2443375.00     13519175.00
      2443675.00     13518925.00
#Sta/Elev= 30
  4314.6  323.35  4453.8  318.80  4483.3  316.86  4536.1  316.07  4560.0  314.39
  4588.6  313.49  4642.3  312.57  4748.5  309.17  4766.9  309.37  4772.3  308.60
  4812.9  307.39  4896.9  306.13  4920.7  304.20  4926.1  304.86  4932.1  303.06
  4936.9  302.90  4940.9  302.77  4941.2  302.27  4944.9  302.77  4955.4  302.89
  4961.9  303.88  4978.3  303.06  5000.4  304.56  5020.7  304.29  5033.7  304.04
  5042.7  306.31  5056.4  307.50  5148.8  309.27  5255.5  312.71  5355.1  318.07
#Mann=8,-1,0
  4314.6    0.12       0  4483.3   0.013       0  4588.6    0.12       0
  4936.9    0.05       0  4940.9    0.05       0  4944.9    0.05       0
  5020.7    0.12       0  5033.7    0.05       0
Bank Sta=4940.9,4944.9
Exp/Cntr=0.3,0.1

Type RM Length L Ch R = 1,16029,461,461,461
BEGIN DESCRIPTION:
TRIB 3 TO SMITH CREEK 28.0
END DESCRIPTION:
XS GIS Cut Line= 3
      2442875.03     13519924.98      2443475.00     13519575.00
      2443775.03     13519274.97
#Sta/Elev= 30
  4300.2  318.86  4388.2  315.02  4409.7  314.91  4474.2  312.44  4489.9  312.68
  4511.4  311.26  4590.7  309.12  4681.8  306.62  4687.6  306.99  4703.3  306.03
  4724.8  306.02  4798.0  303.99  4810.8  304.15  4842.2  302.52  4863.7  303.76
  4890.5  304.10  4936.9  303.45  4949.7  301.69  4969.6  300.78  4969.9  300.28
  4973.4  300.28  4973.6  300.78  4981.1  301.50  5008.9  302.49  5051.4  302.17
  5093.8  303.84  5206.9  306.15  5277.6  308.97  5376.6  312.09  5419.1  314.23
#Mann=5,-1,0
  4300.2    0.04       0  4590.7    0.05       0  4890.5    0.12       0
  4969.6    0.05       0  4973.6    0.12       0
Bank Sta=4969.6,4973.6
Exp/Cntr=0.3,0.1

Type RM Length L Ch R = 1,15568,516,516,516
BEGIN DESCRIPTION:
Mapping XS 0ab1f974
END DESCRIPTION:
XS GIS Cut Line= 4
      2442854.21     13520153.54      2443280.15     13520015.30
      2443668.69     13519835.97      2444008.66     13519555.78
#Sta/Elev= 30
  4413.3  320.43  4651.1  312.77  4752.3  310.14  4877.4  305.66  4895.8  300.29
  4901.3  304.45  4910.5  304.82  4918.8  304.05  4924.3  302.71  4930.5  298.36
  4930.8  297.86  4934.3  297.86  4934.5  298.36  4947.2  299.71  4987.1  299.99
  4993.1  300.31  4998.6  299.57  5016.0  300.38  5031.7  299.66  5081.6  300.94
  5096.8  301.13  5251.0  301.37  5273.9  301.74  5279.5  302.62  5336.2  302.22
  5393.6  303.14  5478.6  305.52  5621.2  312.05  5663.3  313.28  5729.6  316.71
#Mann=7,-1,0
  4413.3    0.04       0  4877.4    0.05       0  4930.5    0.05       0
  4934.5    0.05       0  4987.1    0.12       0  5081.6    0.05       0
  5096.8    0.12       0
Bank Sta=4930.5,4934.5
Exp/Cntr=0.3,0.1

Type RM Length L Ch R = 1,15052,883,883,883
BEGIN DESCRIPTION:
TRIB 3 TO SMITH CREEK 26.0
END DESCRIPTION:
XS GIS Cut Line= 3
      2443125.03     13520225.00      2443725.00     13520175.00
      2444024.99     13519875.01
#Sta/Elev= 30
  4345.4  312.43  4395.5  310.35  4435.7  309.58  4495.9  307.11  4528.5  306.52
  4626.3  303.10  4648.9  302.82  4746.8  299.99  4769.3  300.28  4806.7  299.29
  4827.0  298.64  4857.1  298.55  4867.2  298.23  4884.7  296.79  4889.8  297.24
  4917.3  296.84  4935.4  295.77  4935.7  295.27  4939.2  295.27  4939.4  295.77
  4951.0  295.92  4961.6  297.02  4989.9  295.84  5018.2  295.85  5046.4  296.97
  5060.6  299.83  5159.6  301.41  5329.3  307.23  5343.4  308.27  5371.7  309.47
#Mann=4,-1,0
  4345.4    0.04       0  4806.7    0.12       0  4935.4    0.05       0
  4939.4    0.12       0
Bank Sta=4935.4,4939.4
Exp/Cntr=0.3,0.1

Type RM Length L Ch R = 1,14169,505,505,505
BEGIN DESCRIPTION:
TRIB 3 TO SMITH CREEK 25.0
END DESCRIPTION:
XS GIS Cut Line= 3
      2443124.96     13520775.00      2443725.00     13520775.00
      2444124.97     13520175.04
#Sta/Elev= 30
  4340.1  313.43  4602.9  302.79  4680.1  299.61  4770.1  296.65  4820.1  293.88
  4850.1  293.42  4860.1  294.52  4881.4  294.75  4890.1  294.78  4910.1  291.83
  4920.1  291.47  4937.6  292.05  4962.7  292.02  5006.7  291.21  5019.8  291.54
  5023.8  290.96  5024.0  290.46  5027.5  290.46  5027.8  290.96  5034.8  293.17
  5040.8  291.94  5048.3  294.26  5055.8  295.69  5070.8  296.35  5091.9  296.67
  5149.0  296.23  5304.5  297.46  5408.9  298.86  5530.5  302.01  5661.2  304.49
#Mann=7,-1,0
  4340.1    0.04       0  4602.9    0.05       0  4881.4    0.12       0
  5006.7    0.05       0  5023.8    0.05       0  5027.8    0.05       0
  5304.5    0.04       0
Bank Sta=5023.8,5027.8
Exp/Cntr=0.3,0.1

Type RM Length L Ch R = 1,13664,434,434,434
BEGIN DESCRIPTION:
TRIB 3 TO SMITH CREEK 24.0
END DESCRIPTION:
XS GIS Cut Line= 3
      2443663.69     13521597.14      2443825.00     13521125.00
      2444175.00     13520225.00
#Sta/Elev= 30
  4496.8  303.40  4594.2  299.90  4615.3  298.61  4740.0  296.00  4762.4  295.92
  4854.8  295.44  4927.6  293.96  4998.4  288.26  5005.3  287.56  5008.7  286.21
  5008.9  285.71  5012.4  285.71  5012.7  286.21  5027.9  289.18  5035.2  289.69
  5059.7  289.97  5095.0  291.85  5119.5  291.69  5124.9  292.31  5144.0  291.81
  5149.4  292.67  5214.7  293.16  5319.3  293.99  5382.0  294.17  5403.5  294.90
  5467.8  294.80  5494.6  295.88  5511.1  295.49  5584.7  296.47  5961.4  304.04
#Mann=9,-1,0
  4496.8    0.04       0  4740.0    0.05       0  4762.4    0.04       0
  4927.6    0.12       0  5008.7    0.05       0  5012.7    0.12       0
  5214.7    0.04       0  5319.3    0.05       0  5494.6    0.04       0
Bank Sta=5008.7,5012.7
Exp/Cntr=0.3,0.1

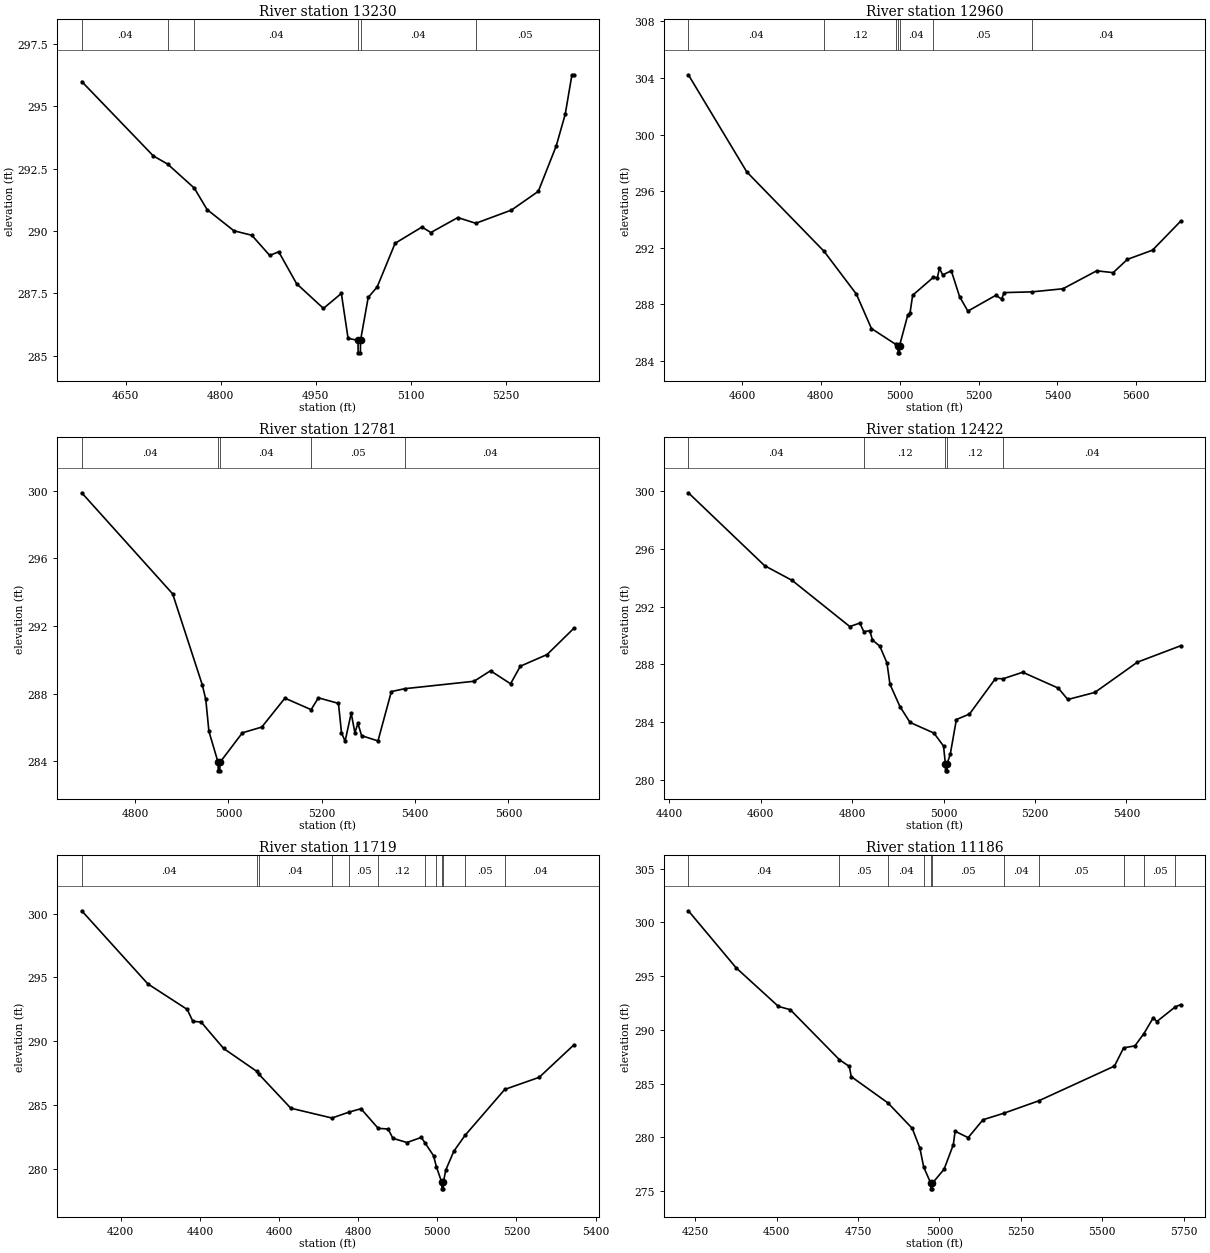
Type RM Length L Ch R = 1,13230,270,270,270
BEGIN DESCRIPTION:
TRIB 3 TO SMITH CREEK 23.0
END DESCRIPTION:
XS GIS Cut Line= 3
      2443925.01     13521524.99      2444225.00     13521225.00
      2444475.00     13520975.00
#Sta/Elev= 30
  4580.4  295.99  4693.5  293.01  4716.2  292.68  4758.2  291.72  4778.4  290.86
  4820.8  290.01  4849.1  289.83  4877.4  289.02  4891.5  289.17  4919.8  287.89
  4962.2  286.90  4990.5  287.50  5001.1  285.70  5016.8  285.62  5017.0  285.12
  5020.5  285.12  5020.8  285.62  5032.9  287.34  5047.1  287.76  5075.4  289.51
  5117.8  290.16  5131.9  289.94  5174.4  290.54  5202.8  290.31  5259.2  290.84
  5301.6  291.59  5329.9  293.41  5344.1  294.68  5354.7  296.26  5358.2  296.26
#Mann=6,-1,0
  4580.4    0.04       0  4716.2    0.12       0  4758.2    0.04       0
  5016.8    0.04       0  5020.8    0.04       0  5202.8    0.05       0
Bank Sta=5016.8,5020.8
Exp/Cntr=0.3,0.1

Type RM Length L Ch R = 1,12960,179,179,179
BEGIN DESCRIPTION:
Mapping XS 82d317f7
END DESCRIPTION:
XS GIS Cut Line= 4
      2443915.26     13521774.96      2444188.00     13521502.22
      2444419.63     13521397.61      2444815.63     13520934.37
#Sta/Elev= 30
  4463.9  304.23  4612.2  297.36  4808.4  291.74  4890.2  288.72  4928.3  286.29
  4989.5  285.18  4995.6  285.07  4995.9  284.57  4999.4  284.57  4999.6  285.07
  5020.7  287.26  5026.2  287.38  5032.9  288.64  5085.0  289.90  5095.6  289.89
  5100.9  290.55  5109.1  290.08  5131.0  290.37  5151.9  288.55  5173.0  287.52
  5244.1  288.64  5258.4  288.37  5265.1  288.83  5335.2  288.88  5414.2  289.10
  5499.9  290.37  5541.6  290.24  5577.8  291.18  5641.5  291.83  5713.2  293.89
#Mann=7,-1,0
  4463.9    0.04       0  4808.4    0.12       0  4989.5    0.04       0
  4995.6    0.04       0  4999.6    0.04       0  5085.0    0.05       0
  5335.2    0.04       0
Bank Sta=4995.6,4999.6
Exp/Cntr=0.3,0.1

Type RM Length L Ch R = 1,12781,359,359,359
BEGIN DESCRIPTION:
Mapping XS 859ff8d8
END DESCRIPTION:
XS GIS Cut Line= 3
      2444124.48     13521819.79      2444352.38     13521614.30
      2444826.85     13521035.22
#Sta/Elev= 30
  4685.4  299.88  4880.3  293.90  4943.8  288.52  4951.3  287.66  4958.0  285.77
  4977.7  283.93  4977.9  283.43  4981.4  283.43  4981.7  283.93  5029.8  285.68
  5071.4  286.02  5120.9  287.73  5177.1  287.05  5192.7  287.75  5235.7  287.42
  5242.2  285.69  5249.9  285.18  5263.0  286.84  5270.9  285.69  5277.4  286.24
  5285.3  285.51  5320.4  285.20  5349.1  288.12  5378.0  288.29  5526.4  288.73
  5561.6  289.35  5604.6  288.58  5625.5  289.62  5682.9  290.31  5740.9  291.88
#Mann=5,-1,0
  4685.4    0.04       0  4977.7    0.04       0  4981.7    0.04       0
  5177.1    0.05       0  5378.0    0.04       0
Bank Sta=4977.7,4981.7
Exp/Cntr=0.3,0.1

Type RM Length L Ch R = 1,12422,703,703,703
BEGIN DESCRIPTION:
Mapping XS 14aba1cd
END DESCRIPTION:
XS GIS Cut Line= 3
      2444412.17     13522118.63      2444654.99     13521662.87
      2444972.40     13521199.83
#Sta/Elev= 30
  4441.4  299.91  4608.4  294.85  4668.6  293.83  4794.7  290.63  4816.7  290.87
  4825.3  290.28  4838.6  290.34  4844.3  289.70  4860.6  289.26  4876.1  288.10
  4882.6  286.63  4904.5  285.08  4926.5  283.98  4978.9  283.24  4999.9  282.34
  5003.9  281.12  5004.2  280.62  5007.7  280.62  5007.9  281.12  5014.8  281.80
  5028.0  284.18  5056.7  284.56  5113.5  287.02  5130.4  287.01  5173.2  287.46
  5251.0  286.36  5271.9  285.57  5331.1  286.06  5424.3  288.16  5519.2  289.30
#Mann=5,-1,0
  4441.4    0.04       0  4825.3    0.12       0  5003.9    0.05       0
  5007.9    0.12       0  5130.4    0.04       0
Bank Sta=5003.9,5007.9
Exp/Cntr=0.3,0.1

Type RM Length L Ch R = 1,11719,533,533,533
BEGIN DESCRIPTION:
Mapping XS b0293ff1
END DESCRIPTION:
XS GIS Cut Line= 3
      2444520.53     13522256.87      2445084.63     13521756.27
      2445196.49     13521279.00
#Sta/Elev= 30
  4101.5  300.22  4268.6  294.49  4368.1  292.49  4382.3  291.56  4403.2  291.50
  4460.1  289.43  4543.7  287.64  4548.4  287.44  4629.8  284.75  4733.7  283.98
  4776.8  284.44  4807.1  284.71  4850.7  283.17  4875.8  283.12  4887.8  282.39
  4923.4  282.06  4959.7  282.46  4969.4  282.01  4990.5  281.03  4997.7  280.17
  5011.4  278.93  5011.7  278.43  5015.2  278.43  5015.4  278.93  5021.3  279.89
  5041.9  281.38  5069.9  282.61  5170.5  286.22  5257.6  287.17  5345.9  289.73
#Mann=12,-1,0
  4101.5    0.04       0  4543.7    0.05       0  4548.4    0.04       0
  4733.7    0.12       0  4776.8    0.05       0  4850.7    0.12       0
  4969.4    0.05       0  4997.7    0.12       0  5011.4    0.05       0
  5015.4    0.12       0  5069.9    0.05       0  5170.5    0.04       0
Bank Sta=5011.4,5015.4
Exp/Cntr=0.3,0.1

Type RM Length L Ch R = 1,11186,575,575,575
BEGIN DESCRIPTION:
Mapping XS d02b340f
END DESCRIPTION:
XS GIS Cut Line= 3
      2444628.87     13522451.14      2445267.70     13522036.47
      2445588.16     13521358.28
#Sta/Elev= 30
  4229.3  301.07  4376.0  295.76  4505.9  292.17  4542.1  291.87  4693.1  287.21
  4723.4  286.59  4729.3  285.64  4842.1  283.19  4916.5  280.83  4940.0  278.99
  4951.8  277.22  4973.8  275.70  4974.0  275.20  4977.5  275.20  4977.8  275.70
  5014.4  277.03  5042.7  279.31  5048.2  280.56  5088.2  279.96  5133.8  281.63
  5197.4  282.23  5304.9  283.39  5537.3  286.62  5565.6  288.32  5600.1  288.50
  5627.7  289.64  5656.7  291.13  5667.2  290.76  5724.5  292.14  5741.0  292.34
#Mann=11,-1,0
  4229.3    0.04       0  4693.1    0.05       0  4842.1    0.04       0
  4951.8    0.05       0  4973.8    0.05       0  4977.8    0.05       0
  5197.4    0.04       0  5304.9    0.05       0  5565.6    0.12       0
  5627.7    0.05       0  5724.5    0.12       0
Bank Sta=4973.8,4977.8
Exp/Cntr=0.3,0.1

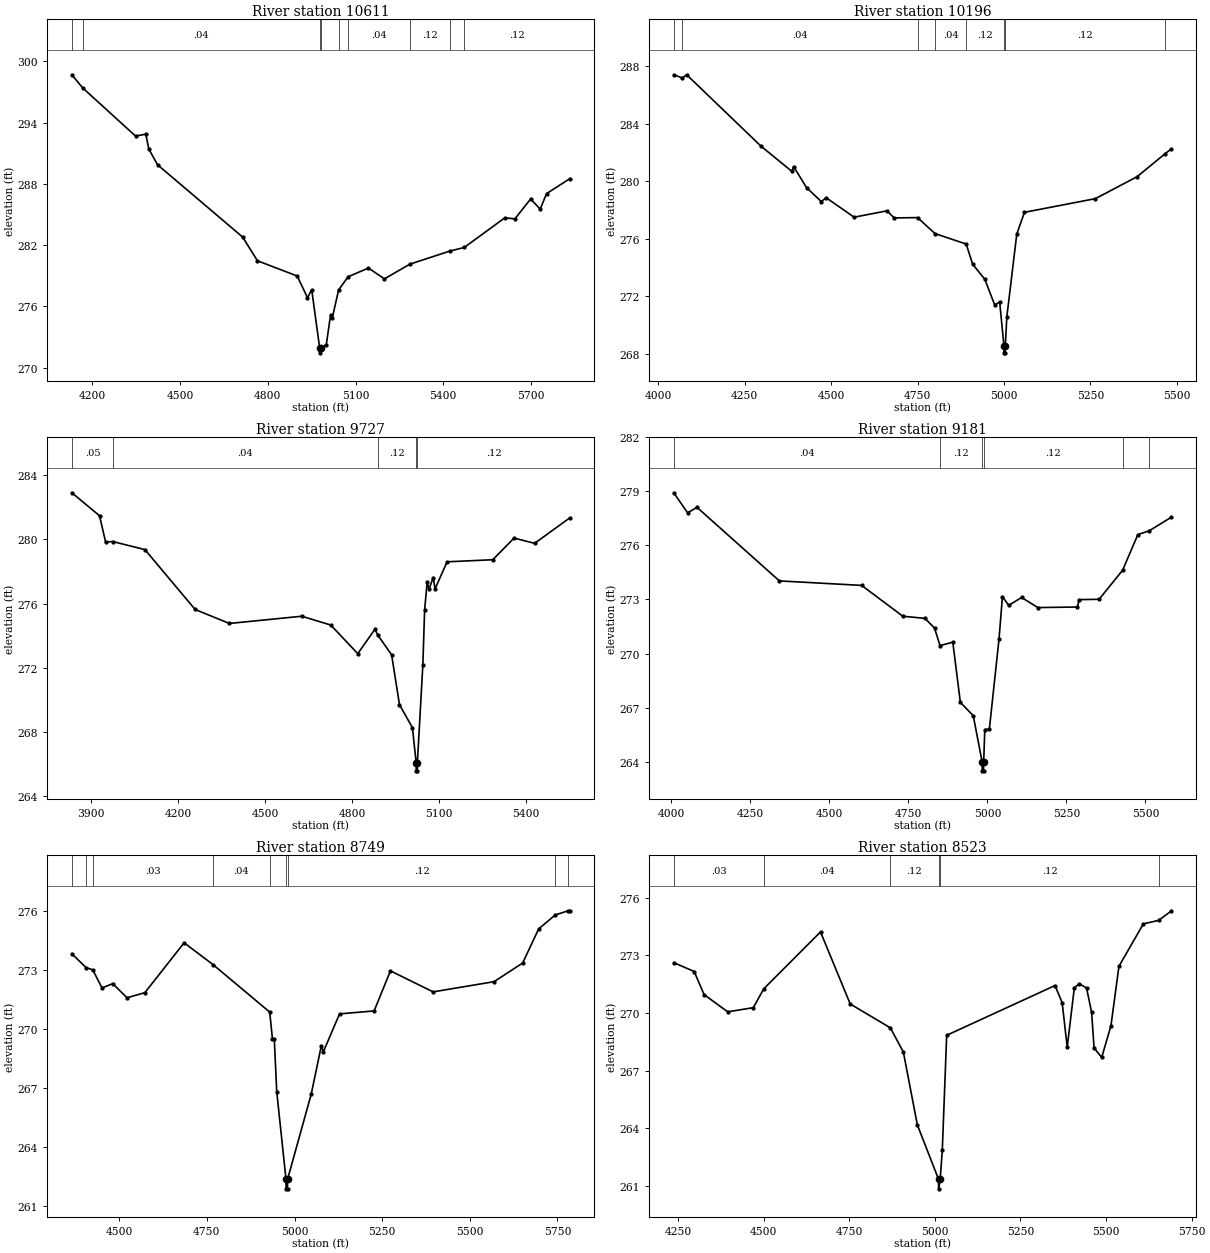
Type RM Length L Ch R = 1,10611,415,415,415
BEGIN DESCRIPTION:
Mapping XS 1ec52398
END DESCRIPTION:
XS GIS Cut Line= 4
      2444733.09     13522589.62      2445405.88     13522528.85
      2445657.62     13522333.54      2445935.41     13521682.47
#Sta/Elev= 30
  4130.0  298.67  4167.1  297.38  4347.9  292.67  4382.9  292.86  4393.0  291.41
  4423.1  289.86  4714.3  282.78  4764.5  280.47  4900.4  278.98  4935.7  276.86
  4950.2  277.63  4977.2  271.96  4977.4  271.46  4981.2  271.96  5000.0  272.25
  5014.5  275.15  5020.8  274.91  5042.1  277.62  5074.9  278.91  5144.3  279.76
  5198.7  278.70  5285.9  280.14  5422.6  281.42  5471.6  281.77  5610.4  284.67
  5644.9  284.57  5698.8  286.52  5731.4  285.52  5753.1  287.04  5832.0  288.49
#Mann=9,-1,0
  4130.0    0.05       0  4167.1    0.04       0  4977.2    0.04       0
  4981.2    0.04       0  5042.1    0.05       0  5074.9    0.04       0
  5285.9    0.12       0  5422.6    0.05       0  5471.6    0.12       0
Bank Sta=4977.2,4981.2
Exp/Cntr=0.3,0.1

Type RM Length L Ch R = 1,10196,469,469,469
BEGIN DESCRIPTION:
Mapping XS 811b1171
END DESCRIPTION:
XS GIS Cut Line= 4
      2445010.96     13522910.78      2445666.30     13522689.44
      2445991.82     13522420.34      2446130.35     13522125.97
#Sta/Elev= 30
  4045.0  287.41  4069.9  287.19  4082.4  287.41  4297.4  282.44  4386.5  280.69
  4391.8  281.02  4429.2  279.55  4471.5  278.59  4486.1  278.85  4566.5  277.50
  4661.5  277.94  4682.6  277.45  4750.1  277.47  4800.5  276.36  4890.7  275.63
  4909.3  274.23  4944.5  273.18  4973.2  271.39  4987.5  271.60  4999.8  268.56
  5000.1  268.06  5003.6  268.06  5003.8  268.56  5008.3  270.58  5037.0  276.33
  5059.2  277.84  5264.4  278.79  5385.1  280.32  5465.0  281.90  5484.4  282.26
#Mann=8,-1,0
  4045.0    0.05       0  4069.9    0.04       0  4750.1    0.12       0
  4800.5    0.04       0  4890.7    0.12       0  4999.8    0.05       0
  5003.8    0.12       0  5465.0   0.013       0
Bank Sta=4999.8,5003.8
Exp/Cntr=0.3,0.1

Type RM Length L Ch R = 1,9727,546,546,546
BEGIN DESCRIPTION:
Mapping XS 29e3a803
END DESCRIPTION:
XS GIS Cut Line= 4
      2445093.40     13523318.78      2446022.20     13523049.68
      2446187.13     13522806.63      2446326.01     13522372.64
#Sta/Elev= 30
  3833.2  282.90  3928.6  281.47  3949.4  279.84  3974.7  279.86  4085.1  279.36
  4258.3  275.63  4376.3  274.76  4626.1  275.21  4726.1  274.66  4819.0  272.88
  4878.4  274.40  4887.6  274.05  4935.8  272.81  4963.0  269.70  5007.6  268.27
  5020.5  266.08  5020.8  265.58  5024.4  265.58  5024.6  266.08  5043.6  272.20
  5049.6  275.59  5058.5  277.36  5064.6  276.89  5079.5  277.62  5085.5  276.91
  5127.1  278.60  5284.6  278.73  5358.1  280.08  5428.9  279.75  5549.6  281.33
#Mann=5,-1,0
  3833.2    0.05       0  3974.7    0.04       0  4887.6    0.12       0
  5020.5    0.05       0  5024.6    0.12       0
Bank Sta=5020.5,5024.6
Exp/Cntr=0.3,0.1

Type RM Length L Ch R = 1,9181,432,432,432
BEGIN DESCRIPTION:
Mapping XS 3d32a670
END DESCRIPTION:
XS GIS Cut Line= 4
      2445271.32     13523353.50      2446082.97     13523305.76
      2446404.15     13523370.86      2446807.81     13523210.27
#Sta/Elev= 30
  4007.3  278.92  4051.1  277.81  4081.1  278.11  4341.6  274.03  4602.0  273.78
  4732.2  272.07  4802.4  271.95  4832.6  271.41  4850.0  270.44  4890.4  270.63
  4914.3  267.29  4955.1  266.55  4983.3  263.99  4983.6  263.49  4987.7  263.49
  4988.1  263.99  4991.7  265.78  5006.1  265.81  5036.7  270.81  5047.5  273.16
  5067.3  272.67  5108.1  273.11  5159.7  272.55  5284.6  272.58  5290.0  272.99
  5353.5  273.01  5427.7  274.62  5476.1  276.60  5512.0  276.81  5582.5  277.57
#Mann=6,-1,0
  4007.3    0.04       0  4850.0    0.12       0  4983.3    0.05       0
  4988.1    0.12       0  5427.7    0.05       0  5512.0    0.03       0
Bank Sta=4983.3,4988.1
Exp/Cntr=0.3,0.1

Type RM Length L Ch R = 1,8749,226,226,226
BEGIN DESCRIPTION:
Mapping XS c5a860bf
END DESCRIPTION:
XS GIS Cut Line= 3
      2445440.58     13523744.13      2446004.84     13523635.62
      2446777.37     13523292.75
#Sta/Elev= 30
  4364.9  273.84  4405.2  273.14  4424.6  273.02  4450.9  272.10  4481.4  272.32
  4522.2  271.60  4573.1  271.86  4685.1  274.40  4767.5  273.29  4929.3  270.87
  4937.0  269.51  4942.3  269.51  4949.3  266.82  4975.6  262.37  4975.9  261.87
  4980.0  261.87  4980.4  262.37  5047.8  266.70  5076.5  269.16  5082.0  268.84
  5128.5  270.78  5227.1  270.93  5273.6  272.97  5395.4  271.90  5569.2  272.42
  5650.8  273.37  5696.5  275.11  5744.0  275.82  5780.7  276.03  5784.7  276.03
#Mann=9,-1,0
  4364.9    0.03       0  4405.2    0.04       0  4424.6    0.03       0
  4767.5    0.04       0  4929.3    0.12       0  4975.6    0.05       0
  4980.4    0.12       0  5744.0    0.05       0  5780.7    0.03       0
Bank Sta=4975.6,4980.4
Exp/Cntr=0.3,0.1

Type RM Length L Ch R = 1,8523,216,216,216
BEGIN DESCRIPTION:
Mapping XS 70569076
END DESCRIPTION:
XS GIS Cut Line= 3
      2445514.35     13524074.01      2446187.13     13523770.17
      2446768.76     13523353.48
#Sta/Elev= 30
  4237.4  272.62  4297.1  272.16  4325.9  270.96  4395.1  270.06  4469.9  270.28
  4500.3  271.26  4666.0  274.22  4752.8  270.47  4869.9  269.23  4908.0  267.97
  4948.8  264.18  5010.7  261.35  5011.1  260.85  5015.6  261.35  5021.7  262.85
  5034.5  268.84  5350.9  271.43  5371.8  270.54  5386.5  268.22  5407.4  271.32
  5422.2  271.52  5443.1  271.30  5457.8  270.03  5465.0  268.18  5487.3  267.69
  5514.3  269.34  5537.6  272.43  5608.9  274.64  5653.7  274.82  5691.1  275.32
#Mann=6,-1,0
  4237.4    0.03       0  4500.3    0.04       0  4869.9    0.12       0
  5010.7    0.05       0  5015.6    0.12       0  5653.7    0.05       0
Bank Sta=5010.7,5015.6
Exp/Cntr=0.3,0.1

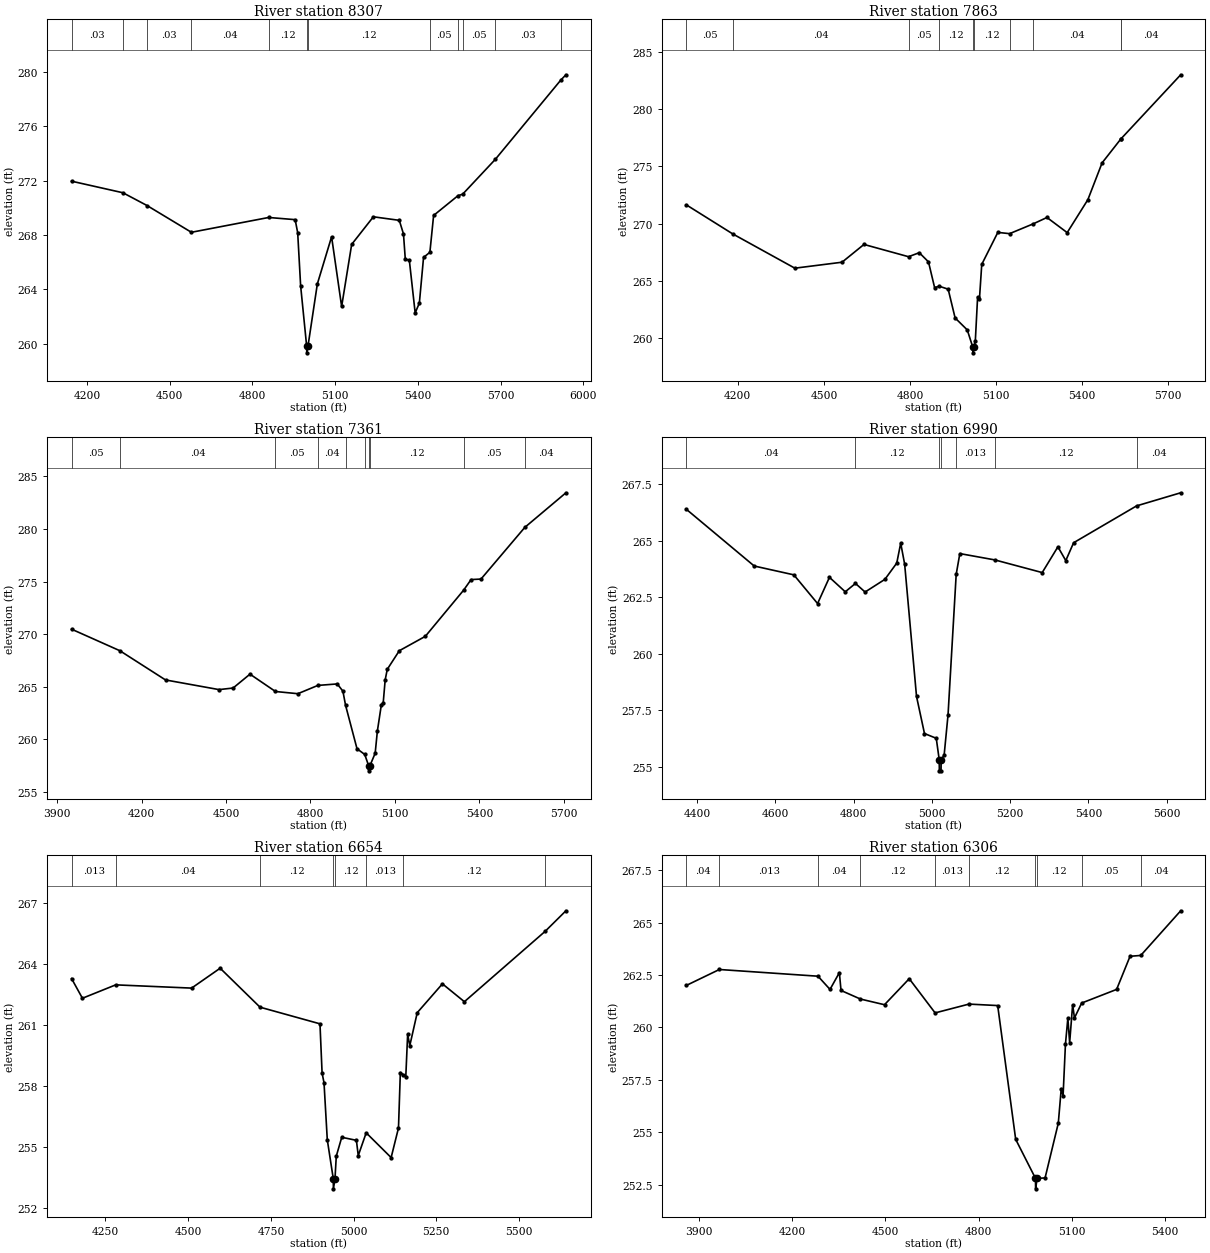
Type RM Length L Ch R = 1,8307,444,444,444
BEGIN DESCRIPTION:
Mapping XS 546cbc78
END DESCRIPTION:
XS GIS Cut Line= 3
      2445483.98     13524325.74      2446234.88     13523969.82
      2447046.50     13523453.34
#Sta/Elev= 30
  4144.2  271.96  4330.3  271.11  4417.8  270.17  4578.8  268.20  4859.1  269.29
  4955.1  269.13  4964.3  268.17  4975.0  264.26  4996.8  259.83  4997.2  259.33
  5001.7  259.83  5035.6  264.40  5087.3  267.87  5123.7  262.74  5160.1  267.31
  5238.8  269.34  5332.8  269.08  5348.0  268.08  5354.6  266.22  5369.2  266.15
  5390.4  262.27  5405.6  262.99  5420.8  266.35  5443.8  266.73  5457.3  269.44
  5546.1  270.90  5562.5  271.00  5681.2  273.57  5918.6  279.40  5937.2  279.79
#Mann=12,-1,0
  4144.2    0.03       0  4330.3    0.05       0  4417.8    0.03       0
  4578.8    0.04       0  4859.1    0.12       0  4996.8    0.05       0
  5001.7    0.12       0  5443.8    0.05       0  5546.1    0.12       0
  5562.5    0.05       0  5681.2    0.03       0  5918.6    0.04       0
Bank Sta=4996.8,5001.7
Exp/Cntr=0.3,0.1

Type RM Length L Ch R = 1,7863,502,502,502
BEGIN DESCRIPTION:
Mapping XS 91824b6c
END DESCRIPTION:
XS GIS Cut Line= 3
      2445696.65     13524464.63      2446573.42     13524130.41
      2447185.34     13523640.00
#Sta/Elev= 30
  4020.7  271.64  4182.2  269.11  4398.8  266.12  4563.2  266.64  4639.6  268.19
  4794.9  267.12  4832.3  267.47  4864.4  266.67  4885.8  264.42  4901.3  264.55
  4933.0  264.29  4957.2  261.78  4999.5  260.74  5018.7  259.24  5019.1  258.74
  5023.7  259.24  5027.6  259.77  5035.6  263.62  5042.0  263.44  5050.0  266.45
  5106.0  269.24  5147.0  269.13  5229.9  269.99  5277.2  270.54  5347.7  269.22
  5419.7  272.09  5469.3  275.30  5533.9  277.36  5534.2  277.37  5743.2  282.98
#Mann=10,-1,0
  4020.7    0.05       0  4182.2    0.04       0  4794.9    0.05       0
  4901.3    0.12       0  5018.7    0.05       0  5023.7    0.12       0
  5147.0    0.05       0  5229.9    0.04       0  5533.9    0.03       0
  5534.2    0.04       0
Bank Sta=5018.7,5023.7
Exp/Cntr=0.3,0.1

Type RM Length L Ch R = 1,7361,371,371,371
BEGIN DESCRIPTION:
Mapping XS 44fb188e
END DESCRIPTION:
XS GIS Cut Line= 3
      2445731.36     13524555.76      2446760.05     13524560.10
      2447315.61     13524091.34
#Sta/Elev= 30
  3951.5  270.47  4123.0  268.42  4285.1  265.64  4475.1  264.72  4525.1  264.87
  4585.1  266.19  4675.6  264.54  4755.1  264.33  4826.3  265.12  4895.1  265.26
  4915.1  264.57  4924.6  263.22  4965.2  259.09  4992.6  258.55  5006.3  257.49
  5006.7  256.99  5011.3  257.49  5029.7  258.67  5037.4  260.76  5051.7  263.29
  5058.3  263.49  5065.2  265.64  5072.6  266.65  5115.4  268.42  5207.8  269.79
  5343.4  274.17  5370.3  275.19  5405.5  275.24  5561.2  280.16  5707.1  283.45
#Mann=10,-1,0
  3951.5    0.05       0  4123.0    0.04       0  4675.6    0.05       0
  4826.3    0.04       0  4924.6   0.013       0  4992.6    0.12       0
  5006.3    0.05       0  5011.3    0.12       0  5343.4    0.05       0
  5561.2    0.04       0
Bank Sta=5006.3,5011.3
Exp/Cntr=0.3,0.1

Type RM Length L Ch R = 1,6990,336,336,336
BEGIN DESCRIPTION:
Mapping XS ba832532
END DESCRIPTION:
XS GIS Cut Line= 3
      2446013.48     13524777.11      2446625.50     13524868.26
      2447267.87     13524824.86
#Sta/Elev= 30
  4373.0  266.39  4546.4  263.88  4647.5  263.49  4708.2  262.22  4738.5  263.38
  4778.9  262.74  4804.9  263.11  4829.5  262.73  4880.1  263.29  4910.4  264.01
  4920.5  264.89  4930.6  263.96  4960.9  258.11  4981.2  256.47  5011.3  256.26
  5018.8  255.32  5019.2  254.82  5023.5  254.82  5023.8  255.32  5031.4  255.51
  5041.4  257.30  5062.2  263.51  5071.5  264.43  5161.0  264.15  5281.9  263.59
  5322.0  264.73  5342.1  264.12  5362.1  264.91  5522.9  266.54  5635.6  267.12
#Mann=7,-1,0
  4373.0    0.04       0  4804.9    0.12       0  5018.8    0.05       0
  5023.8    0.12       0  5062.2   0.013       0  5161.0    0.12       0
  5522.9    0.04       0
Bank Sta=5018.8,5023.8
Exp/Cntr=0.3,0.1

Type RM Length L Ch R = 1,6654,348,348,348
BEGIN DESCRIPTION:
Mapping XS 4fdedf70
END DESCRIPTION:
XS GIS Cut Line= 3
      2445918.01     13525584.42      2446603.80     13525180.76
      2447224.09     13524859.77
#Sta/Elev= 30
  4147.6  263.30  4180.4  262.33  4281.0  262.99  4510.4  262.83  4596.7  263.81
  4717.2  261.89  4898.4  261.07  4904.8  258.64  4910.6  258.17  4920.5  255.36
  4938.6  253.44  4939.0  252.94  4943.8  253.44  4947.7  254.55  4964.2  255.48
  5008.5  255.33  5014.1  254.58  5038.1  255.70  5113.5  254.48  5135.7  255.94
  5141.3  258.67  5150.5  258.56  5157.8  258.47  5163.4  260.55  5169.9  260.00
  5192.4  261.62  5268.5  263.04  5334.9  262.16  5579.2  265.63  5641.8  266.64
#Mann=8,-1,0
  4147.6   0.013       0  4281.0    0.04       0  4717.2    0.12       0
  4938.6    0.05       0  4943.8    0.12       0  5038.1   0.013       0
  5150.5    0.12       0  5579.2    0.04       0
Bank Sta=4938.6,4943.8
Exp/Cntr=0.3,0.1

Type RM Length L Ch R = 1,6306,381,381,381
BEGIN DESCRIPTION:
Mapping XS 01656df6
END DESCRIPTION:
XS GIS Cut Line= 4
      2445931.07     13525675.55      2446755.71     13525363.05
      2447094.25     13525154.72      2447288.53     13524908.63
#Sta/Elev= 30
  3858.4  262.00  3964.8  262.76  4282.6  262.44  4321.3  261.81  4351.5  262.61
  4356.8  261.76  4419.5  261.35  4496.9  261.08  4576.6  262.32  4660.0  260.69
  4769.1  261.11  4861.6  261.04  4919.6  254.66  4983.4  252.80  4983.8  252.30
  4988.7  252.80  5014.3  252.82  5056.9  255.43  5066.4  257.08  5072.3  256.73
  5079.9  259.19  5087.7  260.44  5093.5  259.27  5103.1  261.08  5109.0  260.45
  5132.2  261.16  5244.8  261.81  5288.1  263.39  5322.6  263.43  5451.3  265.56
#Mann=10,-1,0
  3858.4    0.04       0  3964.8   0.013       0  4282.6    0.04       0
  4419.5    0.12       0  4660.0   0.013       0  4769.1    0.12       0
  4983.4    0.05       0  4988.7    0.12       0  5132.2    0.05       0
  5322.6    0.04       0
Bank Sta=4983.4,4988.7
Exp/Cntr=0.3,0.1

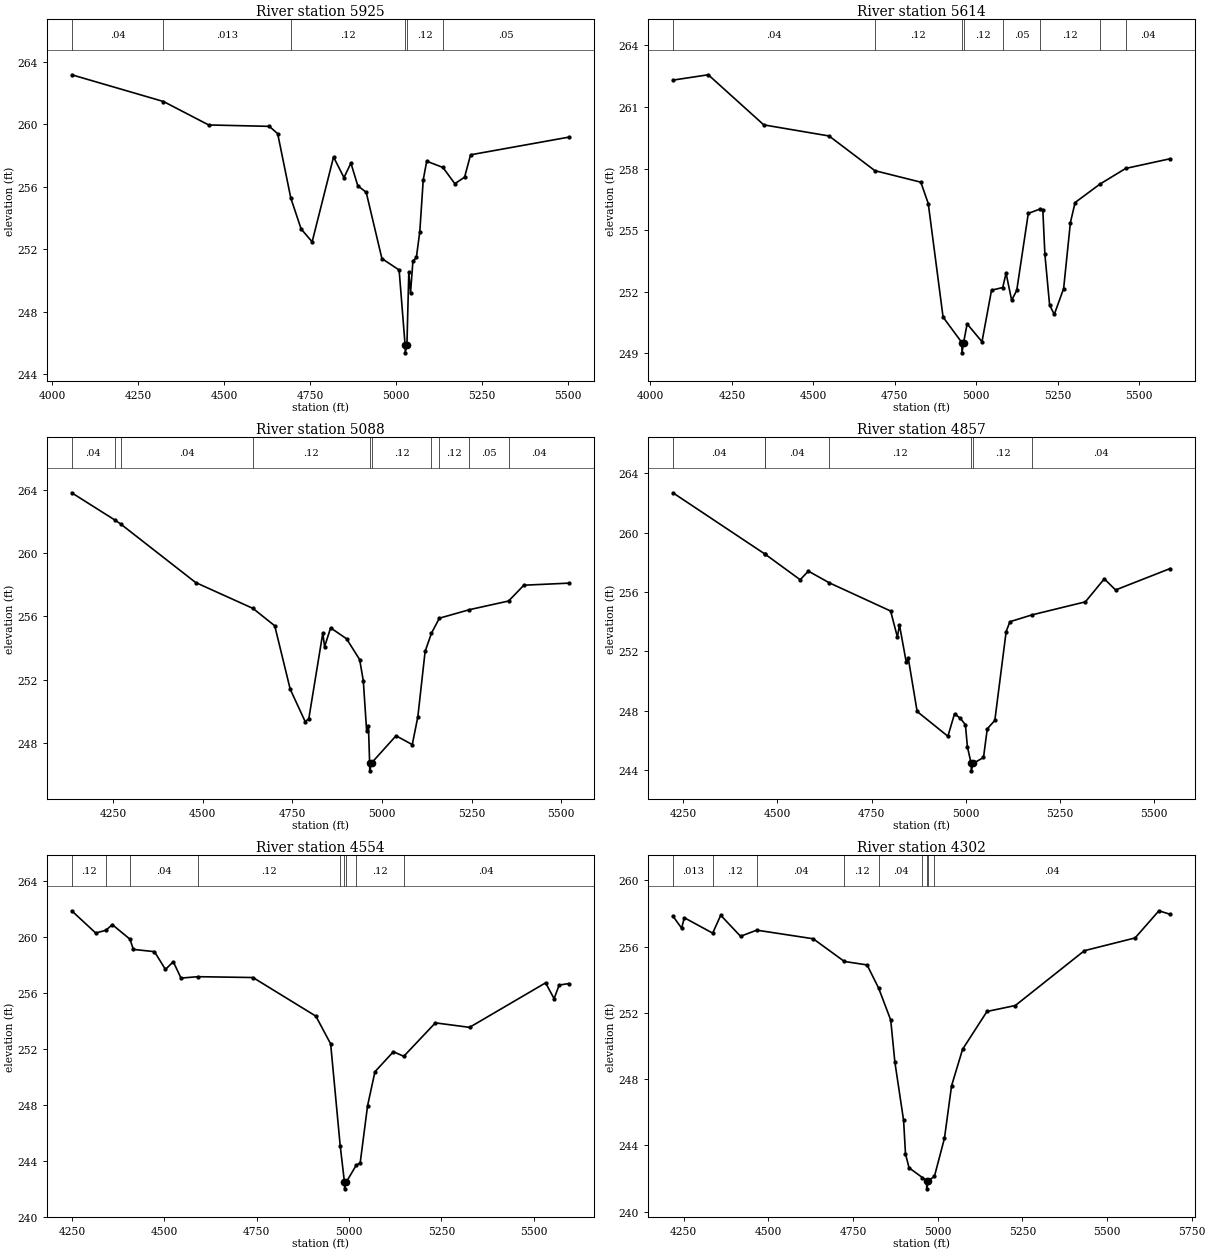
Type RM Length L Ch R = 1,5925,311,311,311
BEGIN DESCRIPTION:
Mapping XS a6c25cbd
END DESCRIPTION:
XS GIS Cut Line= 4
      2446161.12     13525701.58      2446903.28     13525493.26
      2447289.56     13525523.64      2447484.90     13525310.94
#Sta/Elev= 30
  4056.7  263.17  4323.8  261.46  4455.4  259.96  4632.0  259.87  4656.3  259.40
  4694.4  255.29  4724.4  253.31  4756.6  252.48  4818.9  257.91  4849.3  256.59
  4869.4  257.52  4889.5  256.07  4914.0  255.65  4959.7  251.41  5009.8  250.68
  5027.2  245.88  5027.6  245.38  5032.5  245.88  5038.0  250.56  5043.0  249.22
  5049.9  251.23  5060.0  251.48  5070.0  253.14  5080.0  256.45  5090.1  257.64
  5137.4  257.24  5172.0  256.20  5200.4  256.62  5217.8  258.05  5503.8  259.18
#Mann=6,-1,0
  4056.7    0.04       0  4323.8   0.013       0  4694.4    0.12       0
  5027.2    0.05       0  5032.5    0.12       0  5137.4    0.05       0
Bank Sta=5027.2,5032.5
Exp/Cntr=0.3,0.1

Type RM Length L Ch R = 1,5614,526,526,526
BEGIN DESCRIPTION:
Mapping XS 3d78de21
END DESCRIPTION:
XS GIS Cut Line= 4
      2446156.76     13525840.48      2446838.17     13525892.56
      2447215.78     13525714.61      2447484.85     13525384.78
#Sta/Elev= 30
  4069.0  262.31  4177.6  262.57  4348.1  260.13  4548.6  259.59  4689.3  257.90
  4830.3  257.34  4853.1  256.30  4898.6  250.77  4956.3  249.53  4956.7  249.03
  4961.6  249.53  4972.5  250.44  5018.1  249.57  5047.4  252.08  5081.8  252.21
  5092.0  252.91  5109.2  251.59  5124.8  252.07  5160.3  255.82  5197.7  256.04
  5204.9  255.99  5211.3  253.82  5225.7  251.36  5240.1  250.90  5268.8  252.16
  5289.6  255.37  5304.0  256.35  5380.7  257.25  5459.5  258.01  5595.5  258.48
#Mann=8,-1,0
  4069.0    0.04       0  4689.3    0.12       0  4956.3    0.05       0
  4961.6    0.12       0  5081.8    0.05       0  5197.7    0.12       0
  5380.7    0.05       0  5459.5    0.04       0
Bank Sta=4956.3,4961.6
Exp/Cntr=0.3,0.1

Type RM Length L Ch R = 1,5088,231,231,231
BEGIN DESCRIPTION:
Mapping XS 094bfa68
END DESCRIPTION:
XS GIS Cut Line= 4
      2446916.32     13526613.02      2447319.94     13526113.92
      2447393.73     13525666.87      2447527.36     13525408.23
#Sta/Elev= 30
  4135.2  263.82  4255.9  262.09  4271.4  261.85  4480.7  258.14  4640.7  256.50
  4701.3  255.40  4744.4  251.39  4786.1  249.34  4796.3  249.52  4835.3  254.94
  4840.3  254.08  4857.1  255.27  4901.5  254.58  4938.1  253.26  4948.3  251.91
  4957.5  248.76  4962.6  249.04  4965.9  246.72  4966.3  246.22  4971.3  246.72
  5039.5  248.44  5084.8  247.88  5100.3  249.64  5120.6  253.78  5138.3  254.93
  5160.2  255.88  5244.0  256.42  5353.4  256.97  5395.9  257.97  5521.3  258.10
#Mann=10,-1,0
  4135.2    0.04       0  4255.9    0.05       0  4271.4    0.04       0
  4640.7    0.12       0  4965.9    0.05       0  4971.3    0.12       0
  5138.3    0.05       0  5160.2    0.12       0  5244.0    0.05       0
  5353.4    0.04       0
Bank Sta=4965.9,4971.3
Exp/Cntr=0.3,0.1

Type RM Length L Ch R = 1,4857,303,303,303
BEGIN DESCRIPTION:
Mapping XS 220d3a51
END DESCRIPTION:
XS GIS Cut Line= 3
      2447241.82     13526665.14      2447554.32     13525944.65
      2447593.38     13525410.82
#Sta/Elev= 30
  4222.3  262.69  4466.2  258.57  4466.3  258.57  4560.4  256.83  4582.2  257.41
  4637.9  256.62  4800.7  254.72  4818.7  252.96  4824.1  253.79  4842.2  251.27
  4847.6  251.54  4871.1  247.95  4952.8  246.28  4970.4  247.79  4985.5  247.50
  4999.3  247.06  5004.7  245.56  5014.6  244.45  5015.0  243.95  5020.0  244.45
  5047.4  244.85  5057.4  246.78  5077.5  247.35  5107.6  253.34  5117.6  254.00
  5176.1  254.46  5318.1  255.34  5368.3  256.89  5398.3  256.14  5542.9  257.58
#Mann=7,-1,0
  4222.3    0.04       0  4466.2   0.013       0  4466.3    0.04       0
  4637.9    0.12       0  5014.6    0.05       0  5020.0    0.12       0
  5176.1    0.04       0
Bank Sta=5014.6,5020
Exp/Cntr=0.3,0.1

Type RM Length L Ch R = 1,4554,252,252,252
BEGIN DESCRIPTION:
Mapping XS 39801ad8
END DESCRIPTION:
XS GIS Cut Line= 4
      2447506.56     13526678.18      2447827.76     13526200.72
      2447836.44     13525818.78      2447645.46     13525480.22
#Sta/Elev= 30
  4248.9  261.85  4313.9  260.26  4341.6  260.46  4358.9  260.86  4406.6  259.82
  4415.9  259.09  4472.9  258.93  4502.8  257.66  4523.9  258.21  4544.9  257.04
  4590.3  257.14  4739.8  257.08  4910.1  254.32  4950.1  252.34  4976.0  245.05
  4987.4  242.48  4987.8  241.98  4992.8  242.48  5019.5  243.67  5030.1  243.83
  5050.1  247.92  5070.1  250.35  5120.1  251.78  5148.1  251.45  5233.7  253.84
  5326.3  253.52  5532.2  256.70  5555.2  255.57  5568.9  256.54  5595.1  256.65
#Mann=9,-1,0
  4248.9    0.12       0  4341.6   0.013       0  4406.6    0.04       0
  4590.3    0.12       0  4976.0    0.04       0  4987.4    0.04       0
  4992.8    0.04       0  5019.5    0.12       0  5148.1    0.04       0
Bank Sta=4987.4,4992.8
Exp/Cntr=0.3,0.1

Type RM Length L Ch R = 1,4302,192,192,192
BEGIN DESCRIPTION:
Mapping XS 58d7d69a
END DESCRIPTION:
XS GIS Cut Line= 4
      2447918.90     13526669.48      2448092.51     13526126.94
      2447927.58     13525588.74      2447715.58     13525329.15
#Sta/Elev= 30
  4218.4  257.84  4244.1  257.11  4252.1  257.74  4335.8  256.81  4359.6  257.89
  4418.1  256.62  4466.0  256.99  4632.6  256.47  4724.6  255.10  4791.7  254.89
  4825.8  253.49  4861.5  251.56  4873.7  249.03  4899.5  245.50  4905.1  243.48
  4915.6  242.64  4955.0  242.05  4967.4  241.87  4967.9  241.37  4972.9  241.87
  4990.5  242.12  5020.2  244.43  5041.1  247.59  5073.7  249.80  5145.7  252.08
  5229.4  252.44  5433.2  255.75  5583.0  256.52  5653.3  258.16  5686.1  257.95
#Mann=9,-1,0
  4218.4   0.013       0  4335.8    0.12       0  4466.0    0.04       0
  4724.6    0.12       0  4825.8    0.04       0  4955.0    0.05       0
  4967.4    0.04       0  4972.9    0.05       0  4990.5    0.04       0
Bank Sta=4967.4,4972.9
Exp/Cntr=0.3,0.1