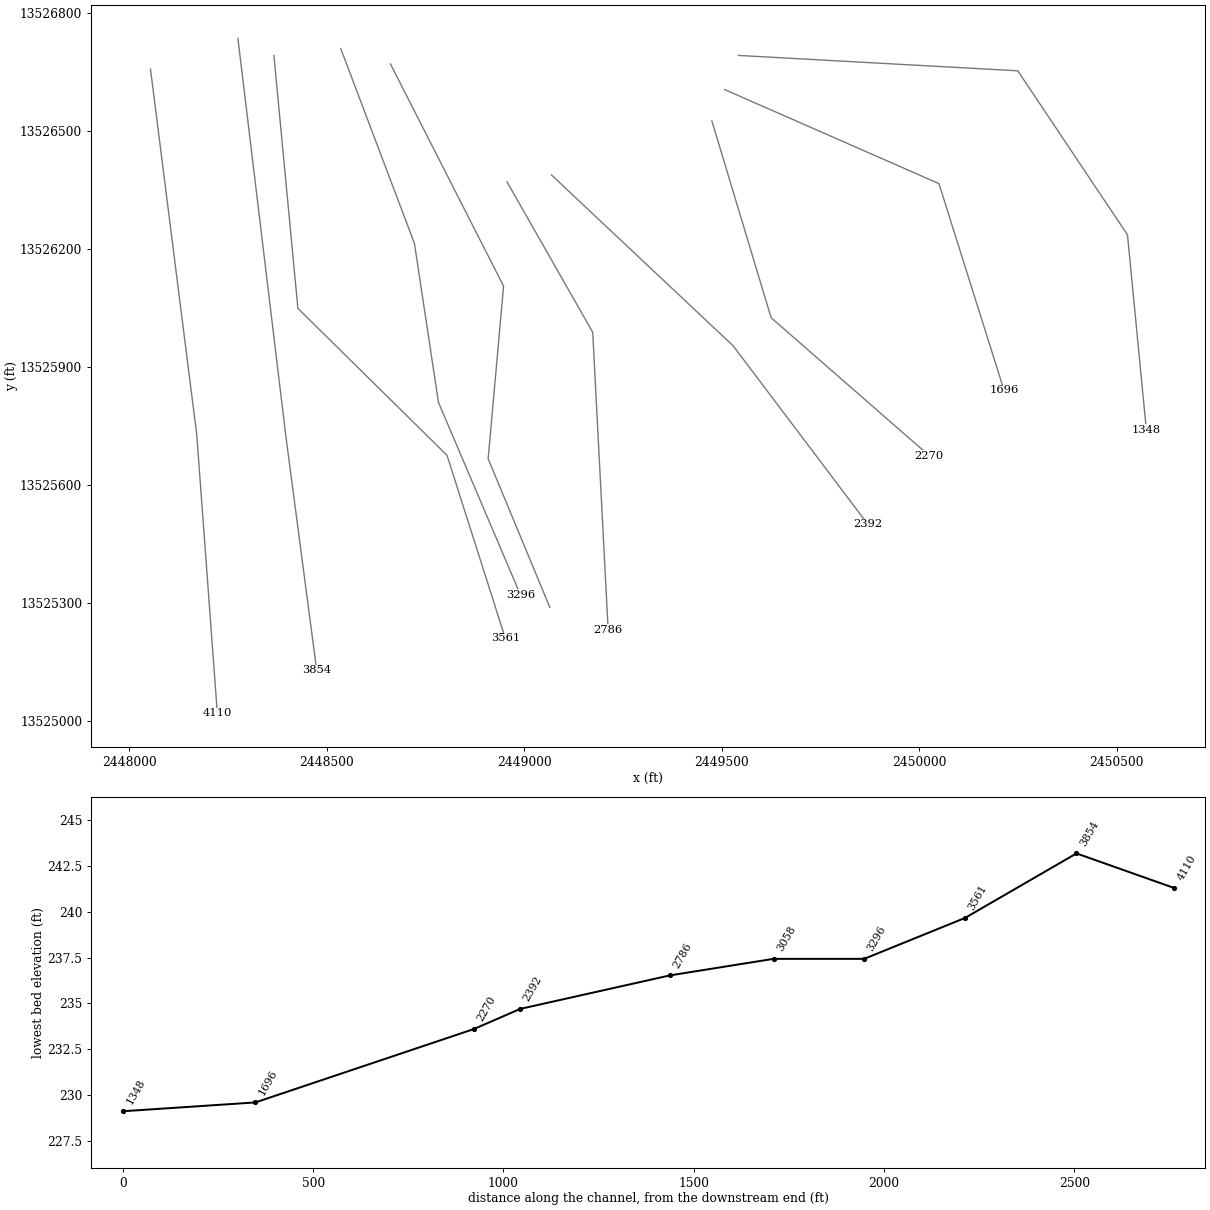
HEC-RAS study TRIB 3 TO SMITH CREEK.prj: TRIB 3 TO SMITH CREEK Base Level Engineering

--- TRIB 3 TO SMITH CREEK.g01 (geometry) --- (continued)

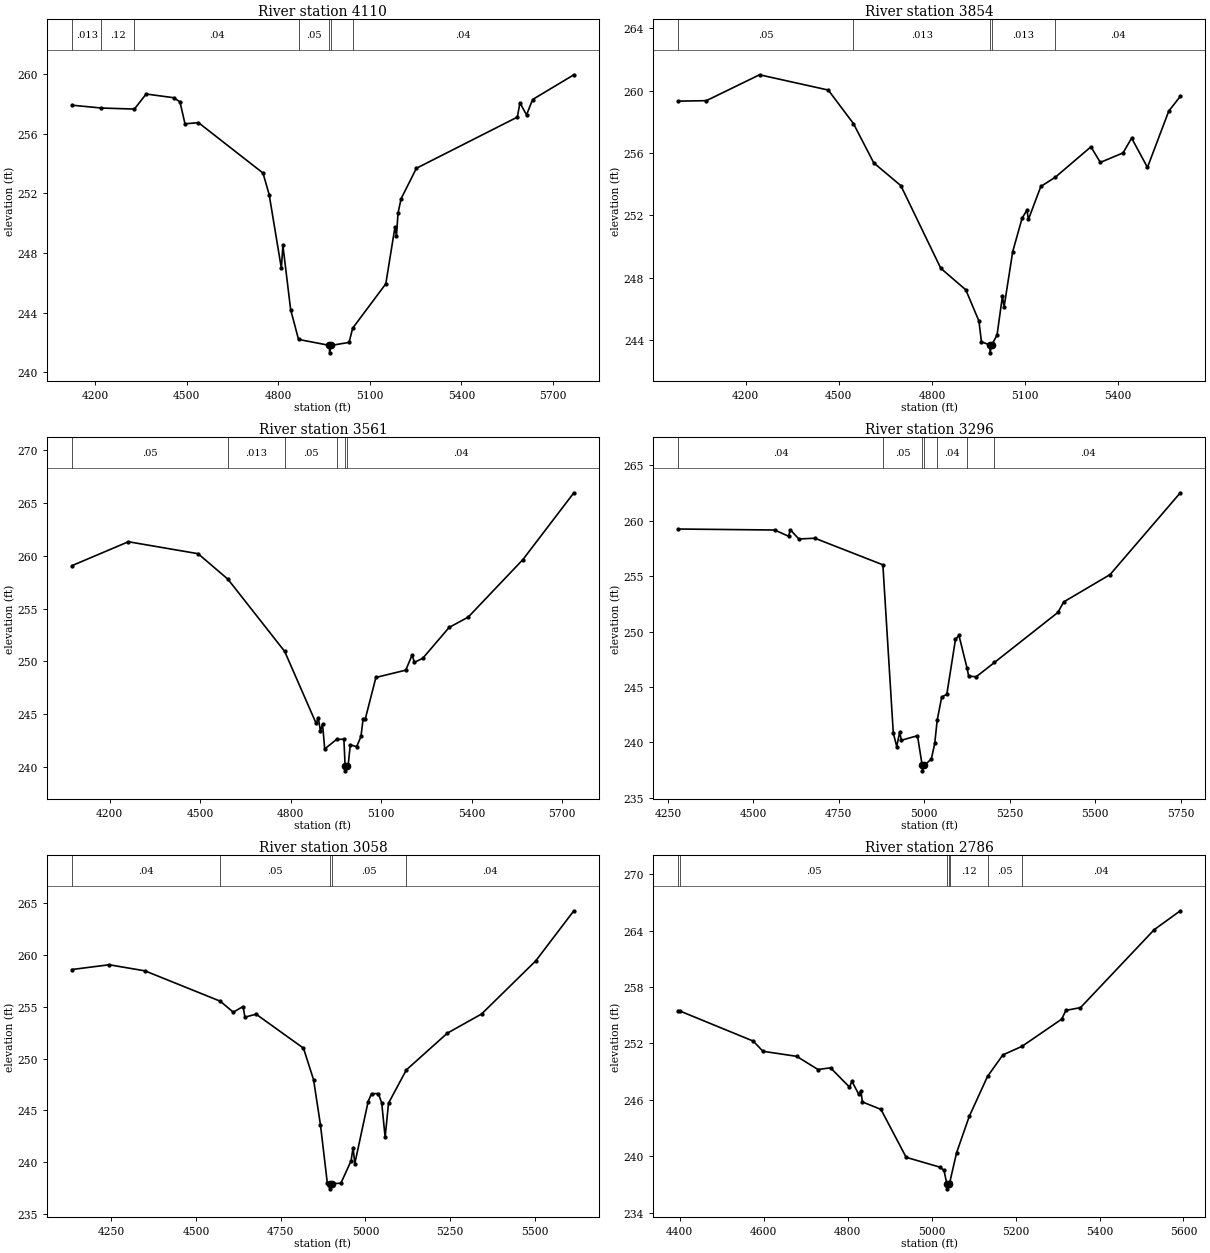
Type RM Length L Ch R = 1,4110,256,256,256
BEGIN DESCRIPTION:
Mapping XS c0df3704
END DESCRIPTION:
XS GIS Cut Line= 3
      2448053.46     13526656.41      2448170.64     13525727.63
      2448222.72     13525020.18
#Sta/Elev= 30
  4123.3  257.91  4219.6  257.72  4328.0  257.65  4366.6  258.66  4457.3  258.41
  4477.5  258.13  4493.9  256.66  4538.0  256.74  4749.6  253.36  4769.8  251.92
  4809.9  246.97  4814.9  248.50  4840.3  244.20  4866.1  242.20  4967.5  241.80
  4968.0  241.30  4973.2  241.80  5031.9  242.00  5043.5  242.95  5152.3  245.93
  5182.2  249.72  5187.2  249.16  5192.4  250.68  5202.5  251.64  5252.6  253.68
  5583.5  257.11  5592.0  258.07  5613.6  257.26  5633.6  258.29  5768.8  259.95
#Mann=7,-1,0
  4123.3   0.013       0  4219.6    0.12       0  4328.0    0.04       0
  4866.1    0.05       0  4967.5    0.05       0  4973.2    0.05       0
  5043.5    0.04       0
Bank Sta=4967.5,4973.2
Exp/Cntr=0.3,0.1

Type RM Length L Ch R = 1,3854,293,293,293
BEGIN DESCRIPTION:
Mapping XS 5c87eaea
END DESCRIPTION:
XS GIS Cut Line= 3
      2448274.81     13526734.58      2448396.33     13525723.29
      2448474.37     13525129.36
#Sta/Elev= 30
  3983.1  259.32  4073.3  259.35  4244.5  261.01  4466.1  260.03  4547.2  257.88
  4612.7  255.36  4700.0  253.90  4828.7  248.60  4909.3  247.22  4951.6  245.22
  4959.7  243.89  4987.0  243.68  4987.5  243.18  4992.7  243.68  5010.0  244.32
  5027.5  246.83  5032.5  246.10  5060.5  249.67  5090.7  251.81  5106.2  252.33
  5111.2  251.74  5151.2  253.85  5197.7  254.44  5312.6  256.39  5342.9  255.39
  5416.1  256.00  5443.7  256.95  5494.8  255.07  5563.4  258.68  5600.7  259.63
#Mann=5,-1,0
  3983.1    0.05       0  4547.2   0.013       0  4987.0    0.03       0
  4992.7   0.013       0  5197.7    0.04       0
Bank Sta=4987,4992.7
Exp/Cntr=0.3,0.1

Type RM Length L Ch R = 1,3561,265,265,265
BEGIN DESCRIPTION:
Mapping XS 743c128a
END DESCRIPTION:
XS GIS Cut Line= 4
      2448365.95     13526691.19      2448426.72     13526048.81
      2448804.32     13525675.55      2448951.89     13525211.13
#Sta/Elev= 30
  4075.5  259.06  4262.5  261.32  4493.5  260.19  4592.4  257.78  4780.6  250.95
  4884.9  244.14  4891.9  244.69  4899.0  243.44  4906.1  244.06  4913.2  241.73
  4952.5  242.63  4976.8  242.65  4980.8  240.16  4981.3  239.66  4987.0  240.16
  4990.9  240.17  4998.0  242.12  5019.2  241.95  5033.4  242.91  5040.5  244.56
  5047.5  244.54  5082.9  248.49  5181.9  249.18  5203.1  250.63  5210.2  249.91
  5238.5  250.31  5325.7  253.22  5388.7  254.19  5570.0  259.63  5739.0  265.95
#Mann=6,-1,0
  4075.5    0.05       0  4592.4   0.013       0  4780.6    0.05       0
  4952.5    0.04       0  4980.8    0.04       0  4987.0    0.04       0
Bank Sta=4980.8,4987
Exp/Cntr=0.3,0.1

Type RM Length L Ch R = 1,3296,238,238,238
BEGIN DESCRIPTION:
Mapping XS 62f1b263
END DESCRIPTION:
XS GIS Cut Line= 4
      2448535.22     13526708.55      2448721.85     13526213.74
      2448782.62     13525810.10      2448990.41     13525320.93
#Sta/Elev= 30
  4280.8  259.25  4562.5  259.16  4603.0  258.60  4608.3  259.18  4633.2  258.35
  4680.0  258.42  4879.0  256.02  4909.5  240.84  4919.6  239.62  4928.1  240.93
  4933.2  240.19  4980.3  240.60  4994.0  237.93  4994.5  237.43  5000.2  237.93
  5020.7  238.49  5030.8  239.90  5037.8  241.98  5051.1  244.08  5066.1  244.34
  5091.5  249.30  5101.6  249.65  5125.3  246.70  5130.0  245.97  5152.2  245.92
  5205.5  247.21  5391.0  251.72  5408.1  252.67  5543.8  255.14  5749.3  262.52
#Mann=7,-1,0
  4280.8    0.04       0  4879.0    0.05       0  4994.0    0.05       0
  5000.2    0.05       0  5037.8    0.04       0  5125.3    0.05       0
  5205.5    0.04       0
Bank Sta=4994,5000.2
Exp/Cntr=0.3,0.1

Type RM Length L Ch R = 1,3058,272,272,272
BEGIN DESCRIPTION:
Mapping XS 5663b294
END DESCRIPTION:
XS GIS Cut Line= 4
      2448661.10     13526669.46      2448947.55     13526105.24
      2448908.49     13525666.87      2449064.57     13525289.67
#Sta/Elev= 30
  4133.8  258.60  4243.6  259.06  4349.3  258.47  4571.6  255.54  4609.8  254.48
  4638.7  255.03  4644.3  254.00  4677.1  254.29  4817.0  251.01  4846.9  247.95
  4867.2  243.59  4887.3  238.01  4894.2  237.93  4894.7  237.43  4900.4  237.93
  4927.4  237.97  4957.6  240.14  4963.4  241.42  4968.5  239.87  5007.8  245.85
  5017.8  246.62  5037.9  246.62  5047.9  245.73  5058.0  242.40  5068.0  245.70
  5120.6  248.91  5241.7  252.46  5342.7  254.31  5502.3  259.43  5614.9  264.27
#Mann=5,-1,0
  4133.8    0.04       0  4571.6    0.05       0  4894.2    0.05       0
  4900.4    0.05       0  5120.6    0.04       0
Bank Sta=4894.2,4900.4
Exp/Cntr=0.3,0.1

Type RM Length L Ch R = 1,2786,394,394,394
BEGIN DESCRIPTION:
Mapping XS 20ddad1f
END DESCRIPTION:
XS GIS Cut Line= 3
      2448956.23     13526370.00      2449173.24     13525988.05
      2449212.31     13525232.85
#Sta/Elev= 30
  4397.0  255.44  4400.5  255.44  4575.3  252.24  4598.3  251.16  4678.8  250.62
  4729.5  249.22  4759.3  249.40  4804.5  247.35  4810.3  247.97  4826.1  246.62
  4831.9  246.90  4835.2  245.77  4879.4  244.98  4939.5  239.88  5019.6  238.84
  5029.6  238.50  5036.5  237.03  5037.0  236.53  5042.7  237.03  5043.8  237.31
  5059.6  240.37  5089.7  244.23  5133.3  248.49  5169.8  250.77  5215.6  251.69
  5310.0  254.58  5320.0  255.51  5354.7  255.80  5530.3  264.09  5592.5  266.10
#Mann=7,-1,0
  4397.0    0.04       0  4400.5    0.05       0  5036.5    0.05       0
  5042.7    0.05       0  5043.8    0.12       0  5133.3    0.05       0
  5215.6    0.04       0
Bank Sta=5036.5,5042.7
Exp/Cntr=0.3,0.1

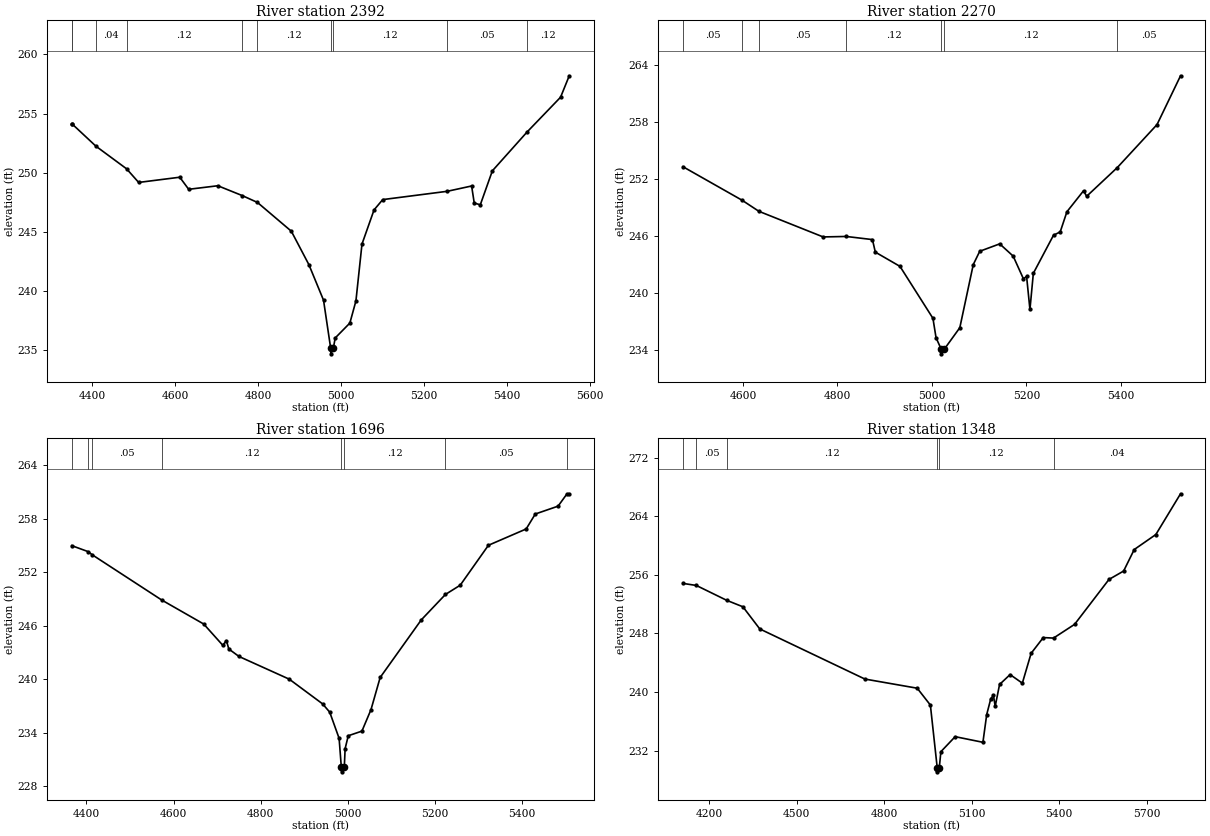
Type RM Length L Ch R = 1,2392,122,122,122
BEGIN DESCRIPTION:
Mapping XS 427db038
END DESCRIPTION:
XS GIS Cut Line= 3
      2449069.05     13526387.38      2449529.15     13525953.33
      2449870.14     13525500.11
#Sta/Elev= 30
  4350.2  254.11  4351.4  254.11  4408.6  252.24  4482.5  250.33  4511.6  249.18
  4610.7  249.62  4632.2  248.60  4702.5  248.90  4761.3  248.07  4798.0  247.49
  4879.7  245.06  4922.0  242.24  4957.4  239.23  4974.5  235.20  4975.0  234.70
  4981.2  235.20  4985.5  236.04  5020.9  237.30  5035.5  239.17  5050.1  243.97
  5079.2  246.86  5100.1  247.73  5255.6  248.43  5314.5  248.88  5320.8  247.44
  5335.4  247.29  5364.5  250.16  5448.2  253.44  5529.0  256.38  5549.9  258.19
#Mann=10,-1,0
  4350.2    0.04       0  4351.4    0.05       0  4408.6    0.04       0
  4482.5    0.12       0  4761.3    0.05       0  4798.0    0.12       0
  4974.5    0.05       0  4981.2    0.12       0  5255.6    0.05       0
  5448.2    0.12       0
Bank Sta=4974.5,4981.2
Exp/Cntr=0.3,0.1

Type RM Length L Ch R = 1,2270,574,574,574
BEGIN DESCRIPTION:
TRIB 3 TO SMITH CREEK 4.0
END DESCRIPTION:
XS GIS Cut Line= 3
      2449474.99     13526525.02      2449625.00     13526025.00
      2450024.96     13525675.03
#Sta/Elev= 30
  4473.0  253.30  4598.2  249.77  4633.6  248.61  4769.7  245.91  4818.6  245.96
  4874.1  245.63  4880.2  244.31  4932.4  242.81  5002.2  237.34  5008.8  235.29
  5019.7  234.10  5020.2  233.60  5026.4  234.10  5059.1  236.35  5087.6  243.00
  5101.3  244.40  5143.6  245.18  5172.1  243.89  5193.9  241.49  5200.5  241.76
  5207.6  238.27  5214.8  242.08  5257.5  246.09  5271.7  246.44  5285.9  248.56
  5321.1  250.77  5327.7  250.19  5392.5  253.21  5476.7  257.74  5526.5  262.88
#Mann=7,-1,0
  4473.0    0.05       0  4598.2    0.12       0  4633.6    0.05       0
  4818.6    0.12       0  5019.7    0.05       0  5026.4    0.12       0
  5392.5    0.05       0
Bank Sta=5019.7,5026.4
Exp/Cntr=0.3,0.1

Type RM Length L Ch R = 1,1696,348,348,348
BEGIN DESCRIPTION:
Mapping XS a773bc72
END DESCRIPTION:
XS GIS Cut Line= 3
      2449507.42     13526604.38      2450049.98     13526365.65
      2450214.90     13525840.50
#Sta/Elev= 30
  4366.1  254.99  4403.6  254.32  4413.6  253.95  4572.7  248.89  4669.4  246.19
  4713.1  243.81  4721.6  244.33  4727.0  243.39  4750.4  242.55  4866.0  240.00
  4942.5  237.23  4958.9  236.30  4980.5  233.36  4985.6  230.10  4986.1  229.60
  4992.4  230.10  4994.3  232.20  5001.5  233.65  5032.9  234.17  5053.8  236.59
  5074.8  240.19  5169.2  246.65  5224.8  249.51  5258.8  250.55  5323.6  255.03
  5410.3  256.86  5431.3  258.54  5483.6  259.42  5504.1  260.80  5509.3  260.81
#Mann=8,-1,0
  4366.1    0.05       0  4403.6    0.04       0  4413.6    0.05       0
  4572.7    0.12       0  4985.6    0.05       0  4992.4    0.12       0
  5224.8    0.05       0  5504.1    0.04       0
Bank Sta=4985.6,4992.4
Exp/Cntr=0.3,0.1

Type RM Length L Ch R = 1,1348,0,0,0
BEGIN DESCRIPTION:
Mapping XS f796c3f2
END DESCRIPTION:
XS GIS Cut Line= 4
      2449542.16     13526691.18      2450249.63     13526652.11
      2450527.41     13526235.45      2450575.15     13525740.66
#Sta/Elev= 30
  4109.7  254.83  4155.4  254.55  4259.7  252.52  4315.1  251.64  4372.9  248.62
  4733.5  241.78  4913.0  240.53  4958.1  238.23  4981.7  229.62  4982.2  229.12
  4988.5  229.62  4994.1  231.87  5043.1  233.92  5138.3  233.15  5151.3  236.94
  5165.4  239.11  5174.4  239.55  5180.4  238.06  5195.4  241.04  5231.5  242.39
  5273.5  241.22  5303.6  245.29  5345.3  247.44  5380.4  247.37  5452.6  249.24
  5570.6  255.37  5620.9  256.52  5657.2  259.45  5731.4  261.50  5816.1  267.06
#Mann=6,-1,0
  4109.7    0.04       0  4155.4    0.05       0  4259.7    0.12       0
  4981.7    0.05       0  4988.5    0.12       0  5380.4    0.04       0
Bank Sta=4981.7,4988.5
Exp/Cntr=0.3,0.1

Chan Stop Cuts=-1