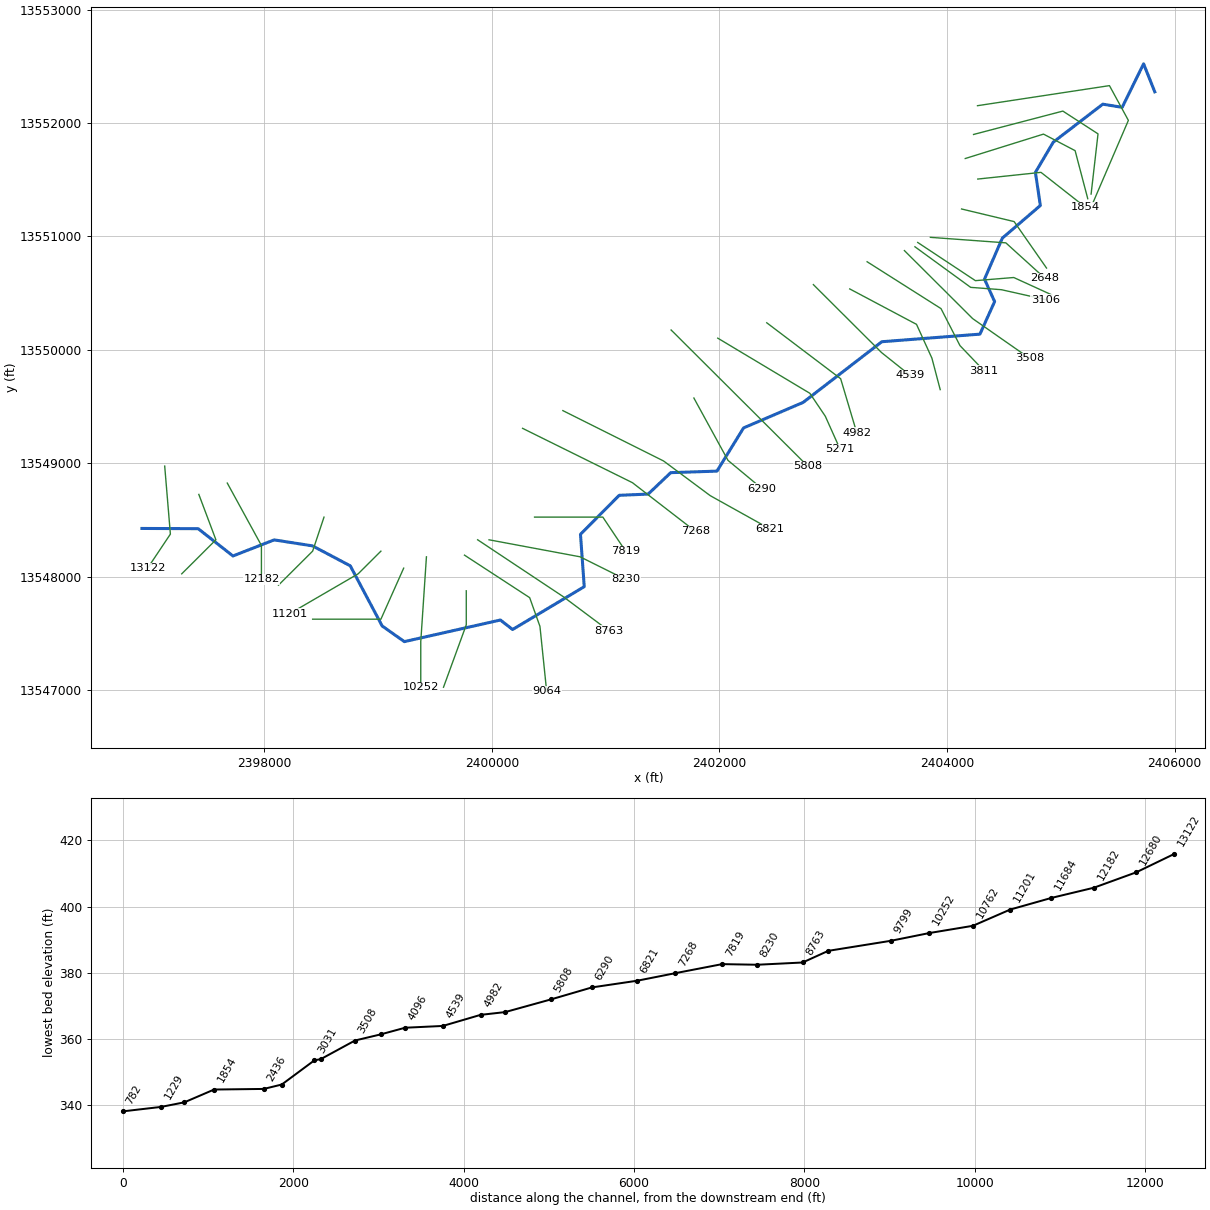
--- TRIB 3 TO THOMAS CREEK.prj (project) ---

Proj Title=TRIB 3 TO THOMAS CREEK Base Level Engineering
Current Plan=p01
Default Exp/Contr=0.3,0.1
English Units
Geom File=g01
Flow File=f01
Plan File=p01
BEGIN DESCRIPTION:
TRIB 3 TO THOMAS CREEK
END DESCRIPTION:

--- TRIB 3 TO THOMAS CREEK.p01 (plan) ---

Plan Title=Multiple Run
Short Identifier=Multiple
Geom File=g01
Flow File=f01
Subcritical Flow
K Sum by GR= 0
Std Step Tol= 0.01
Critical Tol= 0.01
Num of Std Step Trials= 20
Max Error Tol= 0.3
Flow Tol Ratio= 0.001
Split Flow NTrial= 30
Split Flow Tol= 0.02
Split Flow Ratio= 0.02
Log Output Level= 0
Friction Slope Method= 1
Unsteady Friction Slope Method= 2
Unsteady Bridges Friction Slope Method= 1
Parabolic Critical Depth
Global Vel Dist=  1 , 1 , 1
Global Log Level= 0
CheckData=True
Encroach Param= -1, 0, 0, 0
BEGIN DESCRIPTION:
Multiple Run
END DESCRIPTION:

--- TRIB 3 TO THOMAS CREEK.f01 (steady flow) ---

Flow Title=Multiple
Number of Profiles=7
Profile Names=10-year,25-year,50-year,1pct_min,100-year,1pct_plu,500-year
River Rch & RM= TRIB 3 TO THOMAS,Reach-1,13122
     435     700     937     609    1216    2426    2025
River Rch & RM= TRIB 3 TO THOMAS,Reach-1,11684
     613     998    1348     882    1760    3512    2971
River Rch & RM= TRIB 3 TO THOMAS,Reach-1,10252
    1080    1814    2501    1666    3324    6632    5822
River Rch & RM= TRIB 3 TO THOMAS,Reach-1,6290
    1331    2251    3117    2085    4161    8302    7346
River Rch & RM= TRIB 3 TO THOMAS,Reach-1,3106
    1265    2138    2961    1982    3954    7889    6996
Boundary for River Rch & Prof#=TRIB 3 TO THOMAS,Reach-1,1
Up Type=0
Dn Type=3
Dn Slope=0.005
Boundary for River Rch & Prof#=TRIB 3 TO THOMAS,Reach-1,2
Up Type=0
Dn Type=3
Dn Slope=0.005
Boundary for River Rch & Prof#=TRIB 3 TO THOMAS,Reach-1,3
Up Type=0
Dn Type=3
Dn Slope=0.005
Boundary for River Rch & Prof#=TRIB 3 TO THOMAS,Reach-1,4
Up Type=0
Dn Type=3
Dn Slope=0.005
Boundary for River Rch & Prof#=TRIB 3 TO THOMAS,Reach-1,5
Up Type=0
Dn Type=3
Dn Slope=0.005
Boundary for River Rch & Prof#=TRIB 3 TO THOMAS,Reach-1,6
Up Type=0
Dn Type=3
Dn Slope=0.005
Boundary for River Rch & Prof#=TRIB 3 TO THOMAS,Reach-1,7
Up Type=0
Dn Type=3
Dn Slope=0.005

--- TRIB 3 TO THOMAS CREEK.g01 (geometry) ---

Geom Title=Existing Conditions

River Reach=TRIB 3 TO THOMAS,Reach-1
Reach XY= 30
      2396925.00     13548425.00      2397419.14     13548422.95
      2397724.90     13548182.33      2398086.94     13548324.19
      2398423.53     13548271.44      2398755.53     13548095.54
      2399036.09     13547565.00      2399230.88     13547427.12
      2400075.10     13547617.66      2400181.95     13547533.85
      2400811.60     13547911.64      2400778.54     13548373.54
      2401118.83     13548717.14      2401373.57     13548728.07
      2401571.68     13548916.96      2401977.75     13548930.42
      2402211.67     13549311.35      2402735.00     13549536.24
      2403426.46     13550071.46      2404288.67     13550138.22
      2404417.67     13550425.10      2404328.67     13550623.41
      2404485.48     13550984.80      2404819.61     13551272.56
      2404776.19     13551564.50      2404933.15     13551831.07
      2405368.26     13552165.87      2405538.73     13552138.16
      2405726.68     13552521.92      2405825.00     13552275.00

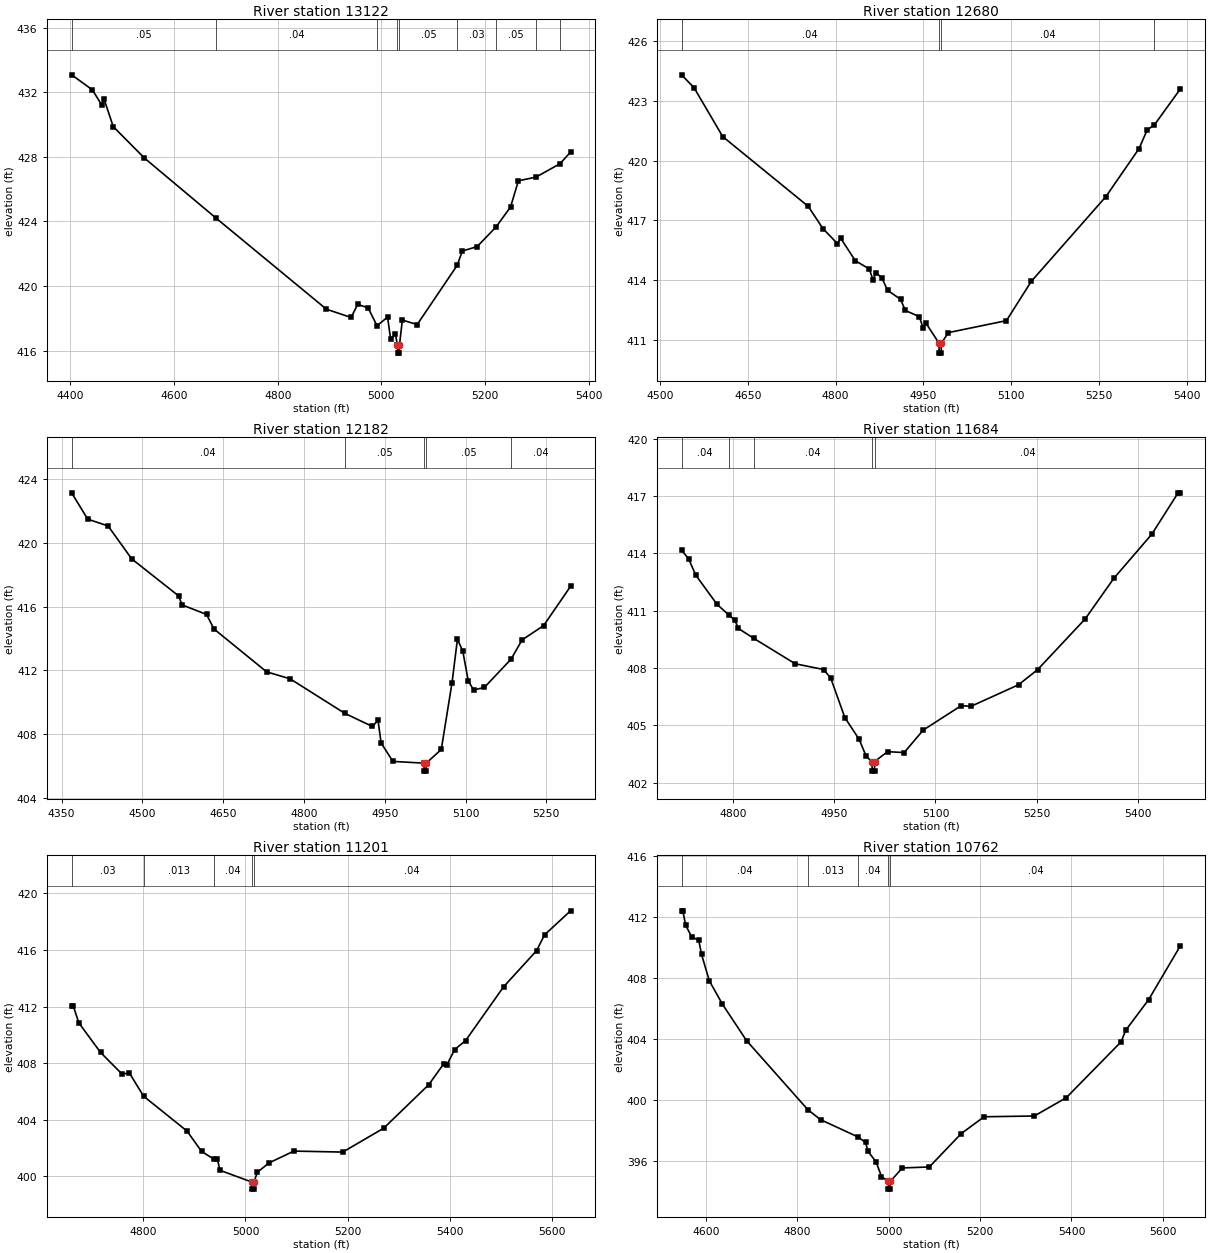
Type RM Length L Ch R = 1,13122,442,442,442
BEGIN DESCRIPTION:
TRIB 3 TO THOMAS CREEK 25.0
END DESCRIPTION:
XS GIS Cut Line= 3
      2397125.00     13548974.99      2397175.00     13548375.00
      2396975.01     13548075.02
#Sta/Elev= 30
  4402.4  433.09  4442.5  432.16  4460.1  431.24  4465.1  431.58  4482.7  429.88
  4542.9  427.93  4681.4  424.20  4894.1  418.56  4941.7  418.05  4954.3  418.86
  4974.4  418.65  4991.6  417.54  5012.0  418.07  5018.0  416.69  5027.0  417.04
  5031.0  416.34  5031.3  415.84  5034.8  415.84  5035.0  416.34  5040.5  417.89
  5069.1  417.61  5146.3  421.28  5156.2  422.17  5184.7  422.44  5221.3  423.66
  5249.3  424.90  5264.4  426.52  5298.3  426.75  5344.7  427.58  5365.0  428.30
#Mann=9,-1,0
  4402.4    0.05       0  4681.4    0.04       0  4991.6    0.05       0
  5031.0    0.05       0  5035.0    0.05       0  5146.3    0.03       0
  5221.3    0.05       0  5298.3    0.03       0  5344.7    0.05       0
Bank Sta=5031,5035
Exp/Cntr=0.3,0.1

Type RM Length L Ch R = 1,12680,498,498,498
BEGIN DESCRIPTION:
TRIB 3 TO THOMAS CREEK 24.0
END DESCRIPTION:
XS GIS Cut Line= 3
      2397425.00     13548725.01      2397575.00     13548325.00
      2397274.98     13548024.98
#Sta/Elev= 30
  4537.1  424.30  4558.5  423.65  4607.4  421.20  4753.4  417.70  4778.3  416.59
  4803.2  415.83  4808.6  416.11  4833.5  414.98  4857.5  414.56  4863.7  414.03
  4869.1  414.36  4878.9  414.12  4888.7  413.49  4910.9  413.04  4918.9  412.48
  4943.0  412.17  4949.2  411.61  4954.5  411.83  4976.5  410.84  4976.7  410.34
  4980.2  410.34  4980.5  410.84  4992.6  411.37  5091.6  411.97  5134.0  413.94
  5261.3  418.19  5317.9  420.60  5332.0  421.55  5343.9  421.78  5388.6  423.60
#Mann=4,-1,0
  4537.1    0.04       0  4976.5    0.04       0  4980.5    0.04       0
  5343.9    0.05       0
Bank Sta=4976.5,4980.5
Exp/Cntr=0.3,0.1

Type RM Length L Ch R = 1,12182,498,498,498
BEGIN DESCRIPTION:
TRIB 3 TO THOMAS CREEK 23.0
END DESCRIPTION:
XS GIS Cut Line= 3
      2397675.01     13548824.98      2397975.00     13548275.00
      2397975.00     13547974.97
#Sta/Elev= 30
  4368.5  423.14  4398.4  421.49  4436.3  421.06  4480.0  419.00  4567.3  416.67
  4573.5  416.11  4619.1  415.51  4632.8  414.60  4730.6  411.91  4774.3  411.47
  4876.1  409.30  4927.1  408.48  4937.5  408.88  4943.2  407.45  4965.1  406.29
  5023.0  406.18  5023.2  405.68  5026.7  405.68  5027.0  406.18  5055.0  407.04
  5075.0  411.24  5085.0  413.96  5095.0  413.20  5105.0  411.35  5115.0  410.77
  5135.0  410.93  5184.7  412.71  5205.0  413.91  5245.0  414.81  5295.0  417.27
#Mann=5,-1,0
  4368.5    0.04       0  4876.1    0.05       0  5023.0    0.05       0
  5027.0    0.05       0  5184.7    0.04       0
Bank Sta=5023,5027
Exp/Cntr=0.3,0.1

Type RM Length L Ch R = 1,11684,483,483,483
BEGIN DESCRIPTION:
TRIB 3 TO THOMAS CREEK 22.0
END DESCRIPTION:
XS GIS Cut Line= 3
      2398525.00     13548525.00      2398425.00     13548225.00
      2398125.00     13547925.00
#Sta/Elev= 30
  4723.1  414.17  4733.6  413.71  4744.2  412.86  4775.8  411.33  4792.8  410.79
  4802.2  410.50  4807.4  410.07  4829.9  409.56  4891.8  408.22  4933.9  407.92
  4944.5  407.47  4965.5  405.40  4986.6  404.27  4997.2  403.37  5005.7  403.10
  5006.0  402.60  5009.5  402.60  5009.7  403.10  5028.8  403.62  5053.5  403.57
  5081.8  404.75  5138.3  406.03  5152.5  405.99  5223.2  407.12  5251.5  407.91
  5322.2  410.57  5364.6  412.69  5421.2  415.01  5460.1  417.17  5463.6  417.17
#Mann=5,-1,0
  4723.1    0.04       0  4792.8   0.013       0  4829.9    0.04       0
  5005.7    0.04       0  5009.7    0.04       0
Bank Sta=5005.7,5009.7
Exp/Cntr=0.3,0.1

Type RM Length L Ch R = 1,11201,439,439,439
BEGIN DESCRIPTION:
TRIB 3 TO THOMAS CREEK 21.0
END DESCRIPTION:
XS GIS Cut Line= 3
      2399024.99     13548224.99      2398825.00     13548025.00
      2398224.96     13547674.98
#Sta/Elev= 30
  4659.4  412.01  4662.9  412.01  4673.5  410.85  4716.0  408.76  4758.4  407.22
  4772.5  407.31  4800.5  405.66  4885.7  403.19  4913.9  401.76  4938.9  401.19
  4945.1  401.19  4950.1  400.42  5012.6  399.59  5012.8  399.09  5016.3  399.09
  5016.6  399.59  5023.3  400.28  5046.0  400.94  5094.8  401.78  5190.7  401.71
  5270.9  403.40  5359.0  406.47  5388.4  407.95  5394.1  407.84  5409.9  408.96
  5431.4  409.60  5505.8  413.40  5570.3  415.95  5586.0  417.07  5636.9  418.77
#Mann=5,-1,0
  4659.4    0.03       0  4800.5   0.013       0  4938.9    0.04       0
  5012.6    0.04       0  5016.6    0.04       0
Bank Sta=5012.6,5016.6
Exp/Cntr=0.3,0.1

Type RM Length L Ch R = 1,10762,510,510,510
BEGIN DESCRIPTION:
TRIB 3 TO THOMAS CREEK 20.0
END DESCRIPTION:
XS GIS Cut Line= 3
      2399225.01     13548075.03      2399025.00     13547625.00
      2398424.98     13547625.00
#Sta/Elev= 30
  4546.2  412.40  4549.0  412.40  4555.1  411.46  4568.1  410.71  4583.9  410.46
  4590.0  409.54  4607.1  407.81  4635.8  406.28  4688.5  403.90  4822.5  399.38
  4850.6  398.72  4931.7  397.60  4949.1  397.23  4954.6  396.64  4972.3  395.95
  4984.0  394.99  4999.1  394.67  4999.3  394.17  5002.8  394.17  5003.1  394.67
  5029.8  395.56  5088.7  395.62  5158.7  397.81  5208.7  398.91  5318.7  398.96
  5388.7  400.16  5508.7  403.82  5518.7  404.57  5568.7  406.57  5638.7  410.12
#Mann=5,-1,0
  4546.2    0.04       0  4822.5   0.013       0  4931.7    0.04       0
  4999.1    0.04       0  5003.1    0.04       0
Bank Sta=4999.1,5003.1
Exp/Cntr=0.3,0.1

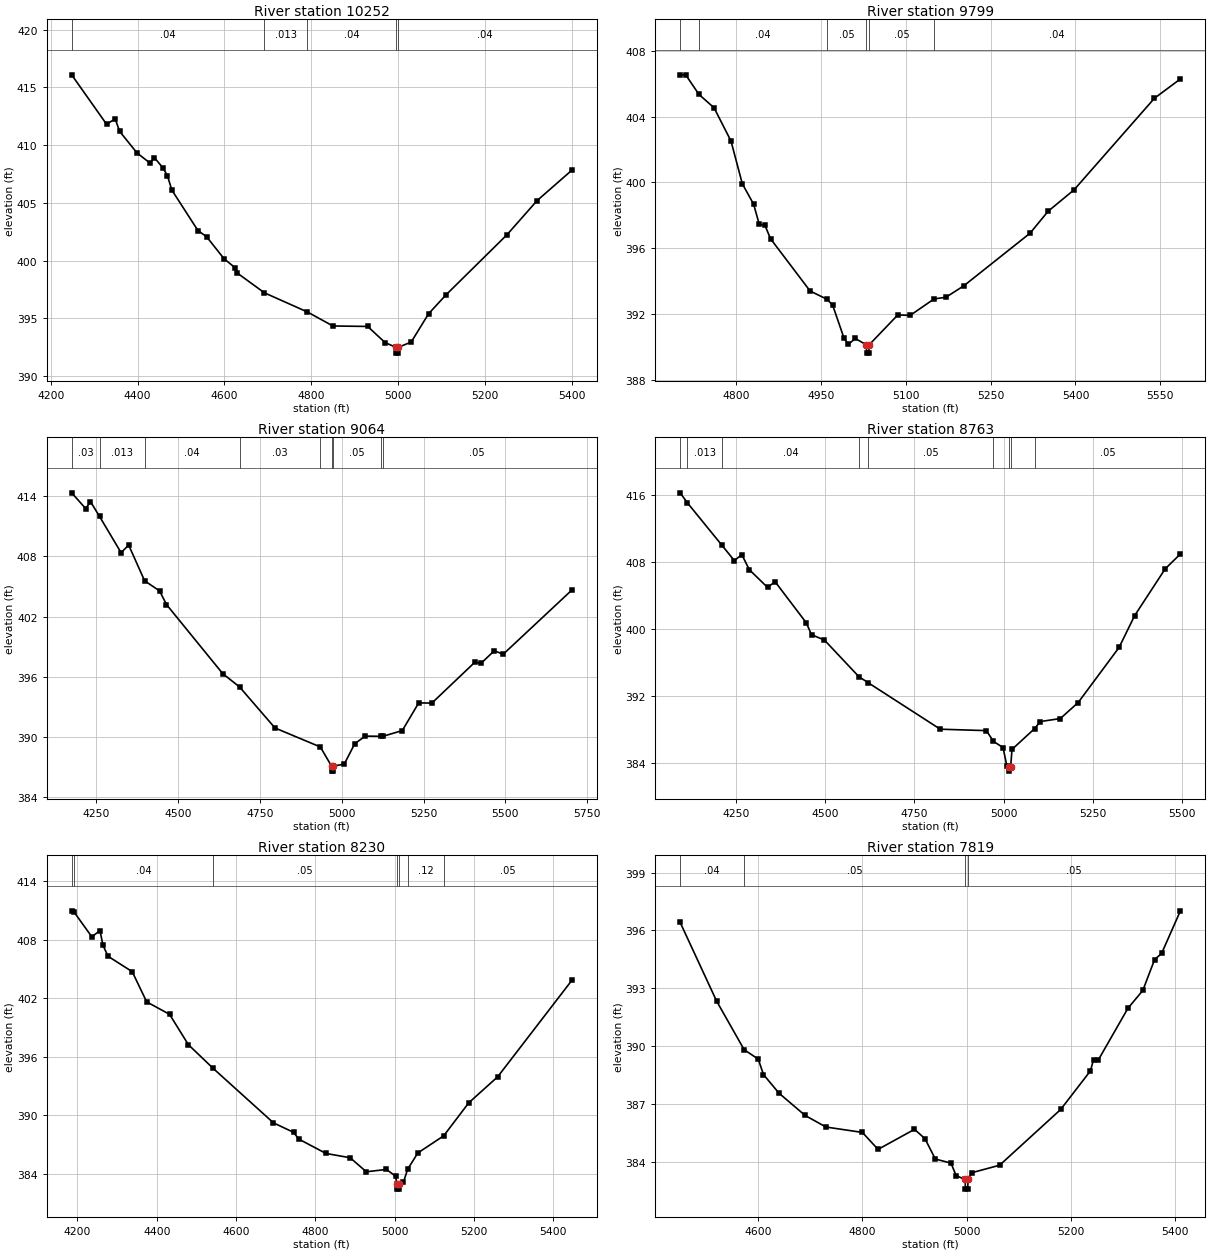
Type RM Length L Ch R = 1,10252,453,453,453
BEGIN DESCRIPTION:
TRIB 3 TO THOMAS CREEK 19.0
END DESCRIPTION:
XS GIS Cut Line= 3
      2399425.00     13548175.02      2399375.00     13547425.00
      2399375.00     13547024.98
#Sta/Elev= 30
  4248.3  416.08  4328.5  411.81  4348.5  412.26  4358.6  411.19  4398.7  409.32
  4428.7  408.44  4438.7  408.91  4458.8  408.01  4468.8  407.34  4478.8  406.11
  4539.0  402.60  4559.0  402.06  4599.1  400.16  4624.2  399.39  4629.2  398.93
  4692.1  397.21  4791.1  395.55  4849.7  394.34  4929.8  394.30  4969.9  392.90
  4995.1  392.49  4995.4  391.99  4999.5  391.99  4999.9  392.49  5030.0  392.95
  5070.0  395.40  5110.0  397.03  5250.0  402.22  5320.0  405.20  5400.0  407.83
#Mann=5,-1,0
  4248.3    0.04       0  4692.1   0.013       0  4791.1    0.04       0
  4995.1    0.04       0  4999.9    0.04       0
Bank Sta=4995.1,4999.9
Exp/Cntr=0.3,0.1

Type RM Length L Ch R = 1,9799,735,735,735
BEGIN DESCRIPTION:
TRIB 3 TO THOMAS CREEK 18.0
END DESCRIPTION:
XS GIS Cut Line= 3
      2399775.00     13547875.03      2399775.00     13547575.00
      2399574.99     13547024.97
#Sta/Elev= 30
  4700.4  406.53  4710.4  406.52  4733.7  405.34  4760.4  404.53  4790.4  402.51
  4810.4  399.92  4830.4  398.68  4840.4  397.46  4850.4  397.40  4860.4  396.58
  4930.4  393.41  4960.8  392.90  4970.4  392.54  4990.4  390.55  4997.9  390.17
  5010.4  390.53  5030.0  390.14  5030.3  389.64  5034.4  389.64  5034.8  390.14
  5085.6  391.96  5107.5  391.93  5149.8  392.93  5170.7  393.03  5202.6  393.73
  5319.7  396.92  5351.6  398.25  5397.5  399.55  5539.8  405.11  5585.7  406.28
#Mann=6,-1,0
  4700.4   0.013       0  4733.7    0.04       0  4960.8    0.05       0
  5030.0    0.05       0  5034.8    0.05       0  5149.8    0.04       0
Bank Sta=5030,5034.8
Exp/Cntr=0.3,0.1

Type RM Length L Ch R = 1,9064,301,301,301
BEGIN DESCRIPTION:
Mapping XS f8e0bac0
END DESCRIPTION:
XS GIS Cut Line= 4
      2399759.23     13548189.74      2400332.17     13547814.72
      2400422.45     13547561.25      2400481.38     13546989.21
#Sta/Elev= 30
  4174.5  414.33  4217.3  412.76  4232.0  413.45  4259.6  411.98  4325.4  408.37
  4348.7  409.12  4397.5  405.56  4443.1  404.56  4464.2  403.20  4636.0  396.32
  4687.5  394.99  4795.9  390.90  4934.4  389.01  4968.7  387.10  4969.1  386.60
  4973.4  386.60  4973.7  387.10  5007.6  387.30  5039.4  389.32  5071.3  390.09
  5118.7  390.07  5124.6  390.06  5184.9  390.64  5235.1  393.40  5275.4  393.38
  5406.0  397.43  5426.1  397.36  5466.4  398.60  5493.1  398.24  5703.4  404.65
#Mann=9,-1,0
  4174.5    0.03       0  4259.6   0.013       0  4397.5    0.04       0
  4687.5    0.03       0  4934.4    0.05       0  4968.7    0.05       0
  4973.7    0.05       0  5118.7    0.12       0  5124.6    0.05       0
Bank Sta=4968.7,4973.7
Exp/Cntr=0.3,0.1

Type RM Length L Ch R = 1,8763,533,533,533
BEGIN DESCRIPTION:
TRIB 3 TO THOMAS CREEK 16.0
END DESCRIPTION:
XS GIS Cut Line= 3
      2399874.96     13548325.03      2400625.00     13547825.00
      2401024.97     13547525.02
#Sta/Elev= 30
  4093.8  416.27  4113.5  415.11  4211.3  409.99  4245.6  408.19  4266.6  408.90
  4287.6  407.10  4338.7  404.99  4359.8  405.67  4446.9  400.78  4461.9  399.35
  4498.0  398.71  4594.4  394.35  4621.4  393.60  4822.5  388.08  4951.7  387.91
  4971.6  386.62  4998.4  385.89  5008.8  383.74  5014.6  383.58  5015.0  383.08
  5019.7  383.58  5023.4  385.67  5087.0  388.16  5102.5  388.99  5158.8  389.35
  5208.8  391.26  5323.4  397.83  5367.1  401.63  5452.5  407.20  5495.2  408.98
#Mann=9,-1,0
  4093.8    0.03       0  4113.5   0.013       0  4211.3    0.04       0
  4594.4    0.03       0  4621.4    0.05       0  4971.6    0.12       0
  5014.6    0.05       0  5019.7    0.12       0  5087.0    0.05       0
Bank Sta=5014.6,5019.7
Exp/Cntr=0.3,0.1

Type RM Length L Ch R = 1,8230,411,411,411
BEGIN DESCRIPTION:
TRIB 3 TO THOMAS CREEK 15.0
END DESCRIPTION:
XS GIS Cut Line= 3
      2399974.96     13548325.01      2400775.00     13548175.00
      2401175.01     13547975.00
#Sta/Elev= 30
  4185.6  410.95  4192.4  410.78  4236.5  408.28  4256.9  408.93  4264.5  407.42
  4277.2  406.29  4338.2  404.71  4374.7  401.61  4432.4  400.33  4479.8  397.22
  4542.2  394.79  4694.3  389.20  4745.2  388.22  4757.9  387.54  4826.6  386.06
  4887.7  385.62  4928.4  384.18  4979.2  384.42  5002.4  383.72  5005.4  382.90
  5005.8  382.40  5010.2  382.40  5010.6  382.90  5021.9  383.10  5032.6  384.44
  5058.3  386.11  5123.5  387.87  5186.8  391.26  5259.5  393.92  5446.8  403.83
#Mann=7,-1,0
  4185.6   0.013       0  4192.4    0.04       0  4542.2    0.05       0
  5005.4    0.05       0  5010.6    0.05       0  5032.6    0.12       0
  5123.5    0.05       0
Bank Sta=5005.4,5010.6
Exp/Cntr=0.3,0.1

Type RM Length L Ch R = 1,7819,551,551,551
BEGIN DESCRIPTION:
TRIB 3 TO THOMAS CREEK 14.0
END DESCRIPTION:
XS GIS Cut Line= 3
      2400375.00     13548525.00      2400975.00     13548525.00
      2401175.02     13548224.97
#Sta/Elev= 30
  4450.0  396.42  4520.0  392.34  4572.9  389.82  4600.0  389.33  4610.0  388.53
  4640.0  387.56  4690.0  386.41  4730.0  385.81  4800.0  385.53  4830.0  384.65
  4900.0  385.69  4920.0  385.21  4940.0  384.15  4970.0  383.94  4980.0  383.29
  4997.3  383.09  4997.7  382.59  5002.3  382.59  5002.7  383.09  5010.0  383.44
  5063.5  383.83  5180.7  386.72  5237.8  388.72  5243.8  389.30  5252.8  389.28
  5309.9  391.97  5338.4  392.89  5361.0  394.49  5374.5  394.81  5410.6  397.02
#Mann=4,-1,0
  4450.0    0.04       0  4572.9    0.05       0  4997.3    0.05       0
  5002.7    0.05       0
Bank Sta=4997.3,5002.7
Exp/Cntr=0.3,0.1

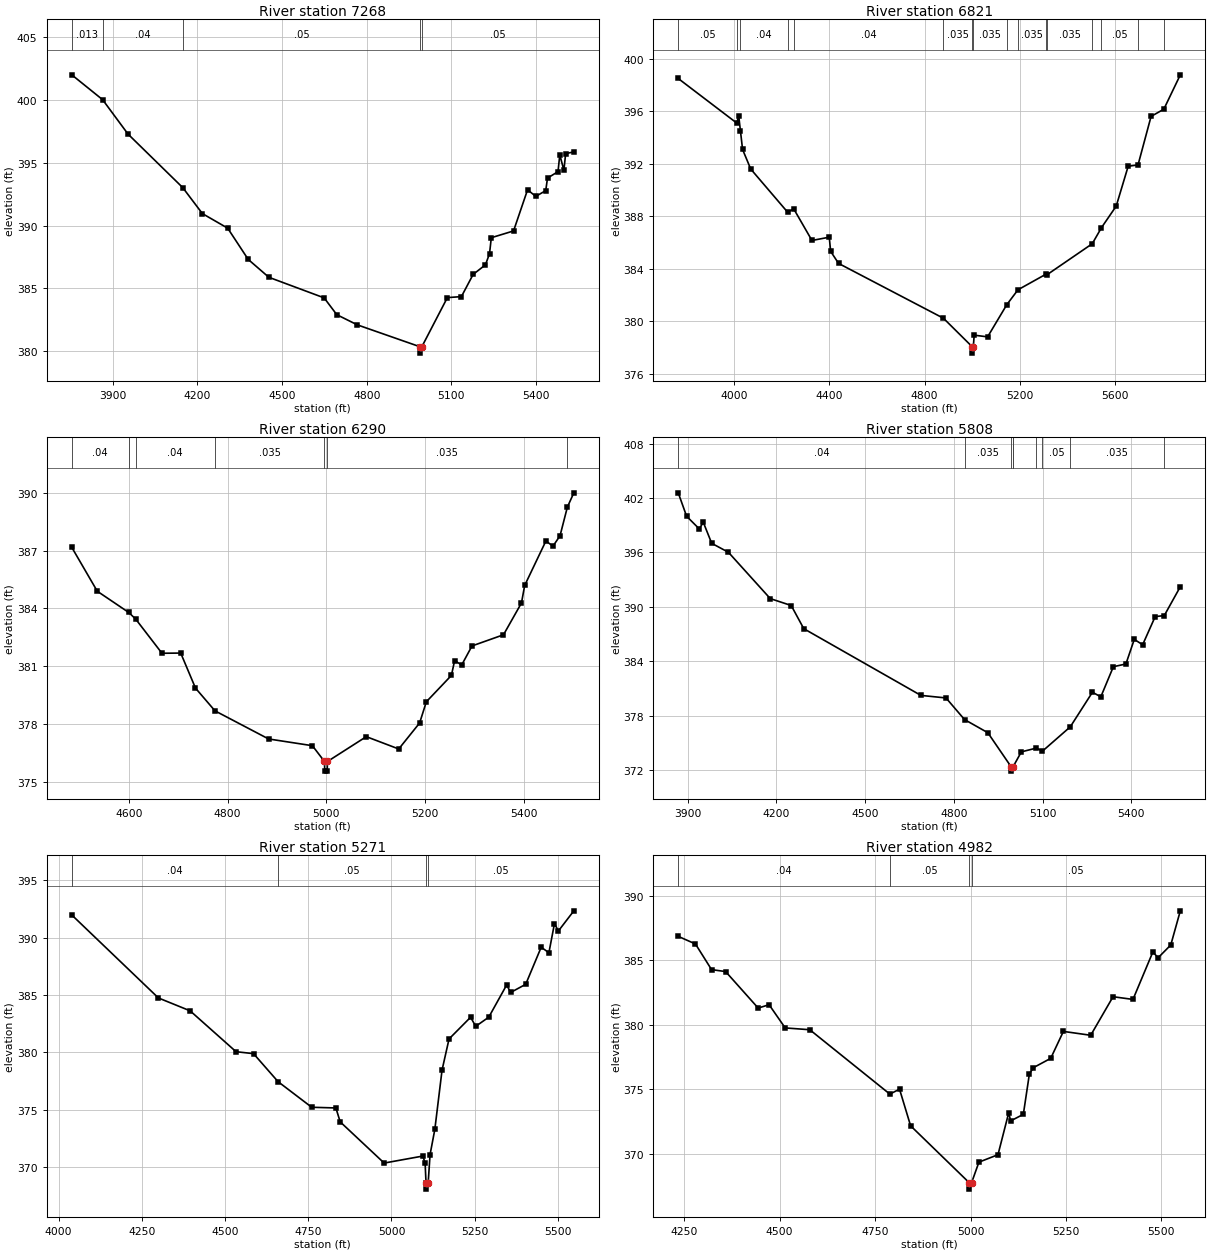
Type RM Length L Ch R = 1,7268,447,447,447
BEGIN DESCRIPTION:
Mapping XS 50c3364e
END DESCRIPTION:
XS GIS Cut Line= 3
      2400269.69     13549307.77      2401234.95     13548828.61
      2401789.00     13548399.22
#Sta/Elev= 30
  3755.1  402.01  3864.4  400.03  3954.4  397.29  4148.2  393.03  4217.8  390.96
  4307.4  389.80  4380.2  387.31  4453.2  385.89  4649.1  384.25  4694.0  382.91
  4766.8  382.10  4989.6  380.35  4990.0  379.85  4995.1  380.35  5085.6  384.27
  5135.4  384.35  5177.0  386.12  5220.5  386.88  5235.0  387.77  5241.3  389.04
  5320.1  389.58  5369.8  392.86  5398.8  392.33  5434.1  392.79  5440.4  393.79
  5477.6  394.30  5483.9  395.64  5498.4  394.41  5504.7  395.74  5533.7  395.87
#Mann=5,-1,0
  3755.1   0.013       0  3864.4    0.04       0  4148.2    0.05       0
  4989.6    0.05       0  4995.1    0.05       0
Bank Sta=4989.6,4995.1
Exp/Cntr=0.3,0.1

Type RM Length L Ch R = 1,6821,531,531,531
BEGIN DESCRIPTION:
Mapping XS e80f6b21
END DESCRIPTION:
XS GIS Cut Line= 4
      2400623.83     13549464.03      2401509.25     13549019.59
      2401918.97     13548714.03      2402445.78     13548419.44
#Sta/Elev= 30
  3767.1  398.51  4012.7  395.11  4020.7  395.66  4027.8  394.54  4036.9  393.10
  4071.0  391.61  4226.1  388.31  4251.1  388.58  4327.8  386.16  4400.4  386.41
  4406.2  385.33  4439.5  384.41  4879.2  380.23  4999.1  378.07  4999.6  377.57
  5004.6  378.07  5008.1  378.94  5064.4  378.81  5145.1  381.27  5191.8  382.40
  5311.2  383.61  5313.0  383.54  5503.2  385.91  5542.0  387.14  5603.7  388.78
  5653.9  391.82  5695.2  391.92  5749.9  395.62  5803.4  396.17  5872.5  398.79
#Mann=16,-1,0
  3767.1    0.05       0  4012.7   0.013       0  4027.8    0.04       0
  4226.1    0.05       0  4251.1    0.04       0  4879.2   0.035       0
  4999.1   0.035       0  5004.6   0.035       0  5145.1    0.05       0
  5191.8   0.035       0  5311.2   0.013       0  5313.0   0.035       0
  5503.2   0.013       0  5542.0    0.05       0  5695.2   0.013       0
  5803.4    0.04       0
Bank Sta=4999.1,5004.6
Exp/Cntr=0.3,0.1

Type RM Length L Ch R = 1,6290,482,482,482
BEGIN DESCRIPTION:
TRIB 3 TO THOMAS CREEK 11.0
END DESCRIPTION:
XS GIS Cut Line= 3
      2401775.01     13549574.98      2402075.00     13549025.00
      2402375.01     13548774.99
#Sta/Elev= 30
  4484.5  387.17  4536.2  384.89  4599.8  383.79  4613.8  383.45  4667.2  381.67
  4705.2  381.68  4735.1  379.86  4774.6  378.68  4883.2  377.22  4971.9  376.87
  4996.4  376.05  4996.9  375.55  5001.9  375.55  5002.4  376.05  5081.1  377.34
  5146.8  376.70  5189.1  378.05  5202.7  379.15  5253.5  380.52  5260.0  381.29
  5274.3  381.06  5295.2  382.05  5359.0  382.63  5395.4  384.28  5401.9  385.19
  5444.9  387.50  5459.2  387.23  5473.5  387.77  5488.4  389.26  5501.5  390.00
#Mann=7,-1,0
  4484.5    0.04       0  4599.8   0.035       0  4613.8    0.04       0
  4774.6   0.035       0  4996.4   0.035       0  5002.4   0.035       0
  5488.4    0.05       0
Bank Sta=4996.4,5002.4
Exp/Cntr=0.3,0.1

Type RM Length L Ch R = 1,5808,537,537,537
BEGIN DESCRIPTION:
TRIB 3 TO THOMAS CREEK 10.0
END DESCRIPTION:
XS GIS Cut Line= 3
      2401574.99     13550175.01      2402375.00     13549375.00
      2402775.02     13548974.98
#Sta/Elev= 30
  3868.6  402.57  3896.9  399.99  3939.3  398.61  3953.5  399.31  3981.7  397.01
  4038.3  396.02  4179.7  390.92  4250.5  390.16  4292.9  387.61  4688.9  380.26
  4773.7  379.98  4836.3  377.60  4915.1  376.15  4993.4  372.42  4993.9  371.92
  4999.5  372.42  5000.8  372.42  5028.3  374.04  5079.3  374.46  5099.7  374.12
  5193.8  376.80  5268.7  380.61  5297.0  380.10  5339.4  383.42  5381.8  383.72
  5410.1  386.43  5438.4  385.84  5480.8  388.94  5511.5  389.05  5565.7  392.23
#Mann=9,-1,0
  3868.6    0.04       0  4836.3   0.035       0  4993.4   0.035       0
  4999.5   0.035       0  5000.8    0.05       0  5079.3   0.035       0
  5099.7    0.05       0  5193.8   0.035       0  5511.5    0.05       0
Bank Sta=4993.4,4999.5
Exp/Cntr=0.3,0.1

Type RM Length L Ch R = 1,5271,289,289,289
BEGIN DESCRIPTION:
Mapping XS 58b888aa
END DESCRIPTION:
XS GIS Cut Line= 4
      2401984.93     13550102.93      2402793.97     13549616.81
      2402929.39     13549415.42      2403060.67     13549121.77
#Sta/Elev= 30
  4039.6  391.97  4299.9  384.74  4395.1  383.62  4533.1  380.06  4585.6  379.89
  4659.3  377.45  4760.4  375.22  4833.0  375.16  4845.9  373.95  4978.0  370.36
  5094.1  370.97  5101.0  370.37  5103.8  368.59  5104.3  368.09  5110.1  368.59
  5115.9  371.10  5130.2  373.29  5151.9  378.46  5172.9  381.17  5237.6  383.06
  5253.1  382.27  5292.3  383.07  5345.9  385.87  5358.0  385.22  5403.2  385.93
  5449.7  389.16  5472.9  388.68  5489.5  391.21  5501.5  390.58  5547.8  392.33
#Mann=4,-1,0
  4039.6    0.04       0  4659.3    0.05       0  5103.8    0.05       0
  5110.1    0.05       0
Bank Sta=5103.8,5110.1
Exp/Cntr=0.3,0.1

Type RM Length L Ch R = 1,4982,443,443,443
BEGIN DESCRIPTION:
Mapping XS d20c181a
END DESCRIPTION:
XS GIS Cut Line= 3
      2402415.47     13550238.36      2403064.81     13549745.28
      2403207.17     13549266.11
#Sta/Elev= 30
  4234.3  386.85  4279.4  386.26  4321.6  384.27  4358.4  384.12  4443.7  381.29
  4472.3  381.55  4514.5  379.75  4578.9  379.61  4788.6  374.62  4814.0  375.00
  4843.0  372.16  4996.5  367.75  4997.0  367.25  5002.8  367.75  5021.9  369.34
  5071.9  369.92  5099.9  373.16  5105.1  372.54  5138.3  373.05  5154.2  376.19
  5164.7  376.67  5210.0  377.39  5243.2  379.48  5314.8  379.18  5373.3  382.17
  5425.5  381.96  5477.6  385.64  5491.3  385.19  5524.5  386.18  5549.5  388.83
#Mann=4,-1,0
  4234.3    0.04       0  4788.6    0.05       0  4996.5    0.05       0
  5002.8    0.05       0
Bank Sta=4996.5,5002.8
Exp/Cntr=0.3,0.1

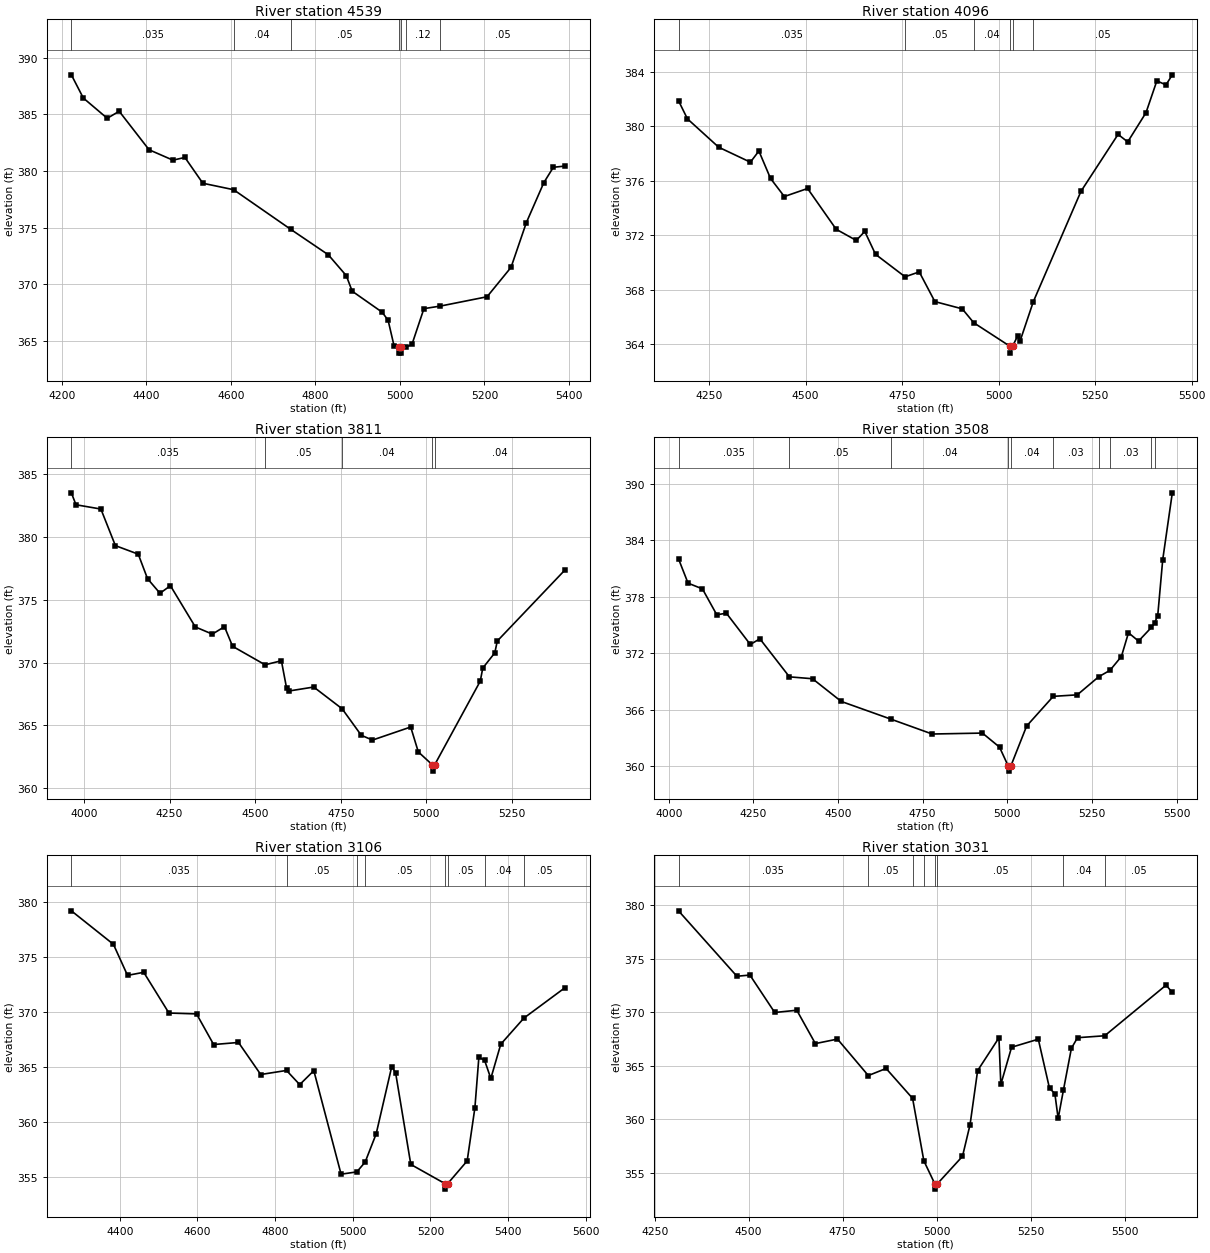
Type RM Length L Ch R = 1,4539,443,443,443
BEGIN DESCRIPTION:
TRIB 3 TO THOMAS CREEK 7.0
END DESCRIPTION:
XS GIS Cut Line= 3
      2402824.98     13550575.02      2403425.00     13549975.00
      2403674.99     13549775.01
#Sta/Elev= 30
  4222.4  388.49  4250.7  386.44  4307.3  384.65  4335.6  385.27  4406.3  381.87
  4462.8  380.95  4491.1  381.19  4533.6  378.91  4606.4  378.34  4741.9  374.83
  4830.5  372.59  4873.0  370.75  4887.1  369.37  4957.8  367.52  4972.0  366.81
  4986.1  364.55  4997.0  364.40  4997.5  363.90  5003.0  363.90  5003.5  364.40
  5014.9  364.43  5028.5  364.67  5056.8  367.83  5096.0  368.06  5206.2  368.88
  5263.0  371.48  5299.1  375.42  5340.7  378.97  5363.1  380.32  5391.1  380.43
#Mann=7,-1,0
  4222.4   0.035       0  4606.4    0.04       0  4741.9    0.05       0
  4997.0    0.05       0  5003.5    0.05       0  5014.9    0.12       0
  5096.0    0.05       0
Bank Sta=4997,5003.5
Exp/Cntr=0.3,0.1

Type RM Length L Ch R = 1,4096,285,285,285
BEGIN DESCRIPTION:
Mapping XS 3f4468c7
END DESCRIPTION:
XS GIS Cut Line= 4
      2403144.63     13550536.97      2403731.47     13550224.45
      2403866.89     13549925.84      2403939.54     13549649.07
#Sta/Elev= 30
  4171.0  381.88  4194.1  380.55  4275.0  378.47  4357.2  377.37  4379.2  378.19
  4409.3  376.18  4445.1  374.85  4505.3  375.44  4579.3  372.45  4631.4  371.63
  4653.4  372.29  4681.3  370.61  4757.8  368.96  4794.5  369.32  4835.0  367.14
  4905.8  366.61  4935.6  365.59  5029.6  363.86  5030.1  363.36  5036.2  363.86
  5049.8  364.65  5055.3  364.22  5090.0  367.14  5213.3  375.23  5309.4  379.41
  5334.4  378.86  5381.7  381.00  5409.9  383.34  5433.4  383.04  5449.9  383.78
#Mann=6,-1,0
  4171.0   0.035       0  4757.8    0.05       0  4935.6    0.04       0
  5029.6    0.04       0  5036.2    0.04       0  5090.0    0.05       0
Bank Sta=5029.6,5036.2
Exp/Cntr=0.3,0.1

Type RM Length L Ch R = 1,3811,303,303,303
BEGIN DESCRIPTION:
Mapping XS 5cd86651
END DESCRIPTION:
XS GIS Cut Line= 4
      2403297.45     13550776.53      2403946.75     13550363.34
      2404113.42     13550036.95      2404325.23     13549814.72
#Sta/Elev= 30
  3962.9  383.50  3976.4  382.55  4049.2  382.21  4091.6  379.30  4158.4  378.62
  4185.5  376.67  4221.9  375.51  4252.4  376.11  4325.2  372.83  4374.9  372.26
  4410.4  372.85  4434.1  371.29  4529.0  369.82  4576.7  370.14  4591.9  367.96
  4600.1  367.74  4671.2  368.05  4754.2  366.32  4810.2  364.21  4842.9  363.83
  4954.6  364.87  4976.8  362.89  5017.9  361.86  5018.4  361.36  5024.6  361.86
  5157.9  368.52  5165.2  369.56  5200.4  370.77  5207.6  371.71  5406.0  377.38
#Mann=5,-1,0
  3962.9   0.035       0  4529.0    0.05       0  4754.2    0.04       0
  5017.9    0.04       0  5024.6    0.04       0
Bank Sta=5017.9,5024.6
Exp/Cntr=0.3,0.1

Type RM Length L Ch R = 1,3508,402,402,402
BEGIN DESCRIPTION:
TRIB 3 TO THOMAS CREEK 5.0
END DESCRIPTION:
XS GIS Cut Line= 3
      2403625.03     13550874.97      2404225.00     13550275.00
      2404724.99     13549925.01
#Sta/Elev= 30
  4028.8  382.04  4057.0  379.46  4099.5  378.85  4141.9  376.10  4170.2  376.27
  4240.9  372.95  4269.2  373.55  4356.5  369.51  4424.7  369.31  4509.6  366.90
  4657.8  365.00  4778.3  363.44  4926.6  363.54  4977.1  362.05  5003.4  360.00
  5003.9  359.50  5010.1  360.00  5057.3  364.29  5135.9  367.44  5206.9  367.60
  5270.1  369.52  5303.4  370.20  5337.2  371.67  5358.1  374.19  5387.8  373.31
  5425.9  374.76  5435.2  375.25  5444.5  376.00  5459.3  381.96  5487.6  389.05
#Mann=10,-1,0
  4028.8   0.035       0  4356.5    0.05       0  4657.8    0.04       0
  5003.4    0.04       0  5010.1    0.04       0  5135.9    0.03       0
  5270.1    0.04       0  5303.4    0.03       0  5425.9    0.04       0
  5435.2    0.03       0
Bank Sta=5003.4,5010.1
Exp/Cntr=0.3,0.1

Type RM Length L Ch R = 1,3106,75,75,75
BEGIN DESCRIPTION:
Mapping XS 844809ca
END DESCRIPTION:
XS GIS Cut Line= 4
      2403717.57     13550908.48      2404207.17     13550550.84
      2404478.00     13550530.00      2404861.74     13550443.57
#Sta/Elev= 30
  4275.4  379.22  4383.7  376.17  4420.0  373.34  4461.7  373.62  4526.6  369.91
  4597.7  369.83  4641.7  367.04  4705.7  367.23  4762.9  364.31  4829.3  364.68
  4863.3  363.39  4899.6  364.66  4969.8  355.23  5010.3  355.44  5031.7  356.33
  5060.1  358.90  5100.2  365.03  5110.2  364.46  5149.3  356.12  5237.4  354.37
  5237.9  353.87  5244.3  354.37  5294.4  356.44  5314.3  361.28  5324.5  365.87
  5339.1  365.62  5355.3  363.95  5380.9  367.07  5440.5  369.45  5546.7  372.23
#Mann=8,-1,0
  4275.4   0.035       0  4829.3    0.05       0  5010.3    0.04       0
  5031.7    0.05       0  5237.4    0.05       0  5244.3    0.05       0
  5339.1    0.04       0  5440.5    0.05       0
Bank Sta=5237.4,5244.3
Exp/Cntr=0.3,0.1

Type RM Length L Ch R = 1,3031,383,383,383
BEGIN DESCRIPTION:
Mapping XS 1b6f0230
END DESCRIPTION:
XS GIS Cut Line= 4
      2403741.86     13550946.69      2404248.83     13550609.86
      2404585.64     13550637.64      2404918.98     13550484.86
#Sta/Elev= 30
  4313.4  379.45  4468.7  373.35  4503.3  373.46  4569.3  369.97  4628.0  370.18
  4677.4  367.07  4736.2  367.49  4818.2  364.09  4865.5  364.75  4936.0  361.96
  4965.9  356.14  4995.0  354.00  4995.5  353.50  5001.9  354.00  5068.7  356.56
  5088.8  359.51  5108.9  364.55  5165.6  367.61  5170.6  363.26  5199.2  366.73
  5270.3  367.48  5300.1  362.90  5314.3  362.41  5323.1  360.09  5337.2  362.75
  5358.3  366.63  5374.6  367.62  5446.9  367.80  5610.1  372.52  5626.7  371.84
#Mann=8,-1,0
  4313.4   0.035       0  4818.2    0.05       0  4936.0    0.12       0
  4965.9    0.05       0  4995.0    0.05       0  5001.9    0.05       0
  5337.2    0.04       0  5446.9    0.05       0
Bank Sta=4995,5001.9
Exp/Cntr=0.3,0.1

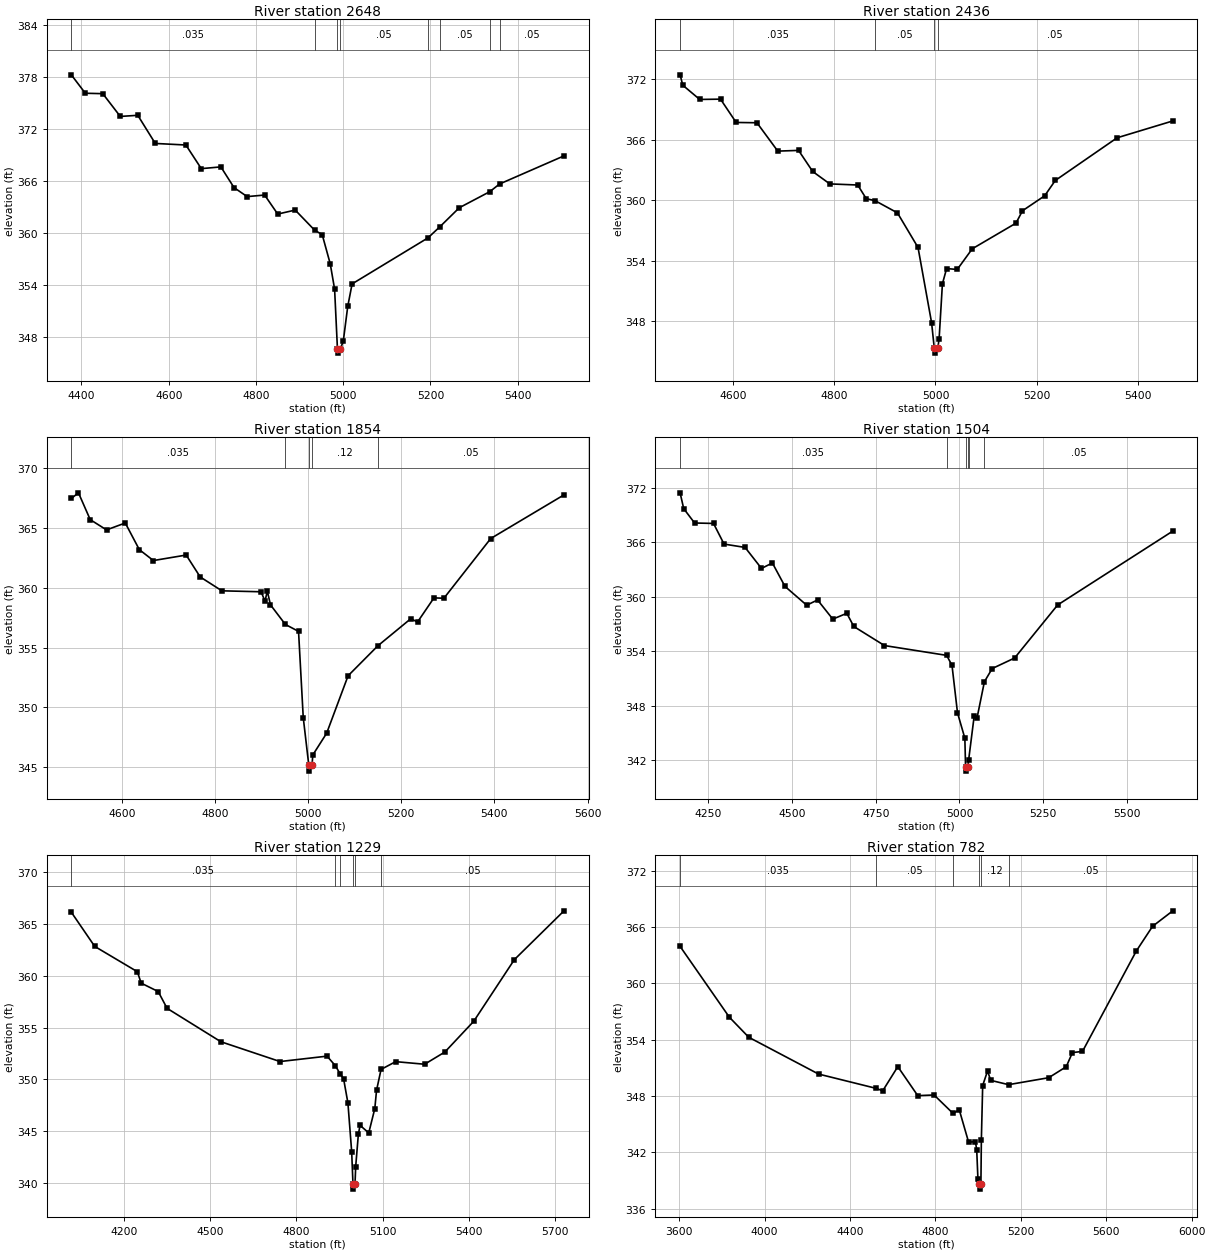
Type RM Length L Ch R = 1,2648,212,212,212
BEGIN DESCRIPTION:
Mapping XS 596281a1
END DESCRIPTION:
XS GIS Cut Line= 3
      2403853.03     13550991.81      2404516.20     13550943.20
      2404859.94     13550630.70
#Sta/Elev= 30
  4376.7  378.23  4408.8  376.11  4448.9  376.06  4489.0  373.44  4529.1  373.57
  4569.2  370.33  4639.4  370.15  4674.7  367.43  4719.6  367.63  4749.7  365.25
  4779.8  364.21  4819.9  364.39  4849.9  362.20  4890.0  362.66  4934.4  360.35
  4951.9  359.83  4970.3  356.47  4980.3  353.56  4986.8  346.69  4987.3  346.19
  4993.8  346.69  5000.3  347.61  5010.4  351.56  5020.4  354.16  5194.1  359.45
  5221.9  360.75  5266.2  362.93  5336.1  364.78  5358.4  365.66  5506.2  368.90
#Mann=8,-1,0
  4376.7   0.035       0  4934.4    0.05       0  4986.8    0.05       0
  4993.8    0.05       0  5194.1    0.12       0  5221.9    0.05       0
  5336.1    0.12       0  5358.4    0.05       0
Bank Sta=4986.8,4993.8
Exp/Cntr=0.3,0.1

Type RM Length L Ch R = 1,2436,582,582,582
BEGIN DESCRIPTION:
Mapping XS af621ee8
END DESCRIPTION:
XS GIS Cut Line= 3
      2404127.28     13551241.81      2404589.11     13551130.70
      2404873.81     13550721.01
#Sta/Elev= 30
  4495.2  372.44  4500.5  371.41  4534.0  370.00  4575.1  370.03  4606.0  367.72
  4647.1  367.69  4688.3  364.88  4729.4  364.95  4757.3  362.86  4791.1  361.63
  4846.3  361.52  4863.1  360.17  4880.9  359.96  4924.8  358.76  4965.5  355.33
  4992.3  347.88  4997.6  345.36  4998.1  344.86  5004.6  345.36  5007.2  346.28
  5013.7  351.73  5022.0  353.24  5043.0  353.15  5072.7  355.20  5159.1  357.74
  5172.0  358.97  5215.8  360.45  5236.8  361.97  5359.0  366.20  5469.1  367.87
#Mann=4,-1,0
  4495.2   0.035       0  4880.9    0.05       0  4997.6    0.05       0
  5004.6    0.05       0
Bank Sta=4997.6,5004.6
Exp/Cntr=0.3,0.1

Type RM Length L Ch R = 1,1854,350,350,350
BEGIN DESCRIPTION:
Mapping XS 399417ed
END DESCRIPTION:
XS GIS Cut Line= 3
      2404269.70     13551505.70      2404825.22     13551564.72
      2405217.59     13551255.69
#Sta/Elev= 30
  4491.4  367.47  4506.8  367.94  4532.0  365.70  4567.1  364.84  4607.3  365.42
  4637.5  363.19  4667.7  362.28  4738.1  362.74  4768.2  360.91  4814.8  359.75
  4899.0  359.67  4907.3  358.89  4912.4  359.72  4919.1  358.58  4951.1  356.94
  4979.4  356.36  4989.5  349.16  5001.4  345.18  5001.9  344.68  5008.4  345.18
  5010.0  346.03  5039.8  347.85  5085.8  352.65  5149.9  355.16  5220.5  357.42
  5234.9  357.14  5270.2  359.16  5291.6  359.13  5392.1  364.12  5549.5  367.77
#Mann=5,-1,0
  4491.4   0.035       0  4951.1    0.12       0  5001.4    0.05       0
  5008.4    0.12       0  5149.9    0.05       0
Bank Sta=5001.4,5008.4
Exp/Cntr=0.3,0.1

Type RM Length L Ch R = 1,1504,275,275,275
BEGIN DESCRIPTION:
Mapping XS d603f5d5
END DESCRIPTION:
XS GIS Cut Line= 4
      2404159.68     13551686.76      2404847.16     13551902.03
      2405124.93     13551756.20      2405236.06     13551332.55
#Sta/Elev= 30
  4165.3  371.44  4176.1  369.70  4208.6  368.12  4265.2  368.07  4296.6  365.80
  4359.5  365.43  4408.5  363.12  4441.0  363.72  4478.7  361.14  4543.6  359.07
  4576.0  359.65  4621.5  357.54  4663.4  358.18  4684.3  356.73  4776.0  354.63
  4961.7  353.55  4977.7  352.45  4994.1  347.23  5016.1  344.43  5018.2  341.31
  5018.7  340.81  5025.3  341.31  5027.3  342.00  5043.8  346.83  5052.7  346.70
  5074.5  350.65  5097.8  352.10  5164.8  353.26  5293.4  359.10  5637.4  367.23
#Mann=6,-1,0
  4165.3   0.035       0  4961.7    0.05       0  5018.2    0.05       0
  5025.3    0.05       0  5027.3    0.12       0  5074.5    0.05       0
Bank Sta=5018.2,5025.3
Exp/Cntr=0.3,0.1

Type RM Length L Ch R = 1,1229,447,447,447
BEGIN DESCRIPTION:
Mapping XS d95a2b48
END DESCRIPTION:
XS GIS Cut Line= 4
      2404232.69     13551898.89      2405017.26     13552104.93
      2405326.32     13551904.18      2405265.57     13551373.26
#Sta/Elev= 30
  4016.7  366.12  4098.2  362.82  4246.5  360.38  4259.7  359.28  4318.9  358.47
  4349.9  356.85  4537.0  353.63  4742.8  351.72  4906.5  352.24  4935.8  351.30
  4951.4  350.56  4963.9  350.07  4979.0  347.73  4992.1  343.03  4996.6  339.92
  4997.1  339.42  5003.7  339.92  5006.1  341.60  5015.3  344.69  5021.2  345.57
  5051.5  344.84  5072.6  347.19  5078.6  348.94  5094.3  350.96  5145.1  351.71
  5245.9  351.46  5316.4  352.64  5417.0  355.61  5557.9  361.54  5730.8  366.25
#Mann=6,-1,0
  4016.7   0.035       0  4935.8    0.05       0  4951.4    0.12       0
  4996.6    0.05       0  5003.7    0.12       0  5094.3    0.05       0
Bank Sta=4996.6,5003.7
Exp/Cntr=0.3,0.1

Type RM Length L Ch R = 1,782,0,0,0
BEGIN DESCRIPTION:
Mapping XS 7585302d
END DESCRIPTION:
XS GIS Cut Line= 4
      2404267.08     13552152.48      2405426.70     13552329.46
      2405593.11     13552023.05      2405283.55     13551300.83
#Sta/Elev= 30
  3604.2  363.94  3834.8  356.40  3925.8  354.26  4252.6  350.34  4523.3  348.81
  4553.0  348.55  4623.8  351.13  4717.2  348.04  4793.7  348.11  4882.9  346.14
  4911.5  346.54  4955.3  343.09  4987.2  343.13  4993.3  342.29  4999.0  339.18
  5005.9  338.58  5006.4  338.08  5013.0  338.58  5015.1  343.32  5021.3  349.12
  5044.1  350.67  5058.8  349.67  5142.4  349.21  5330.5  349.95  5412.6  351.12
  5441.6  352.63  5488.7  352.75  5740.8  363.45  5816.9  366.08  5911.7  367.73
#Mann=6,-1,0
  3604.2   0.035       0  4523.3    0.05       0  4882.9    0.12       0
  5005.9    0.05       0  5013.0    0.12       0  5142.4    0.05       0
Bank Sta=5005.9,5013
Exp/Cntr=0.3,0.1

Chan Stop Cuts=-1