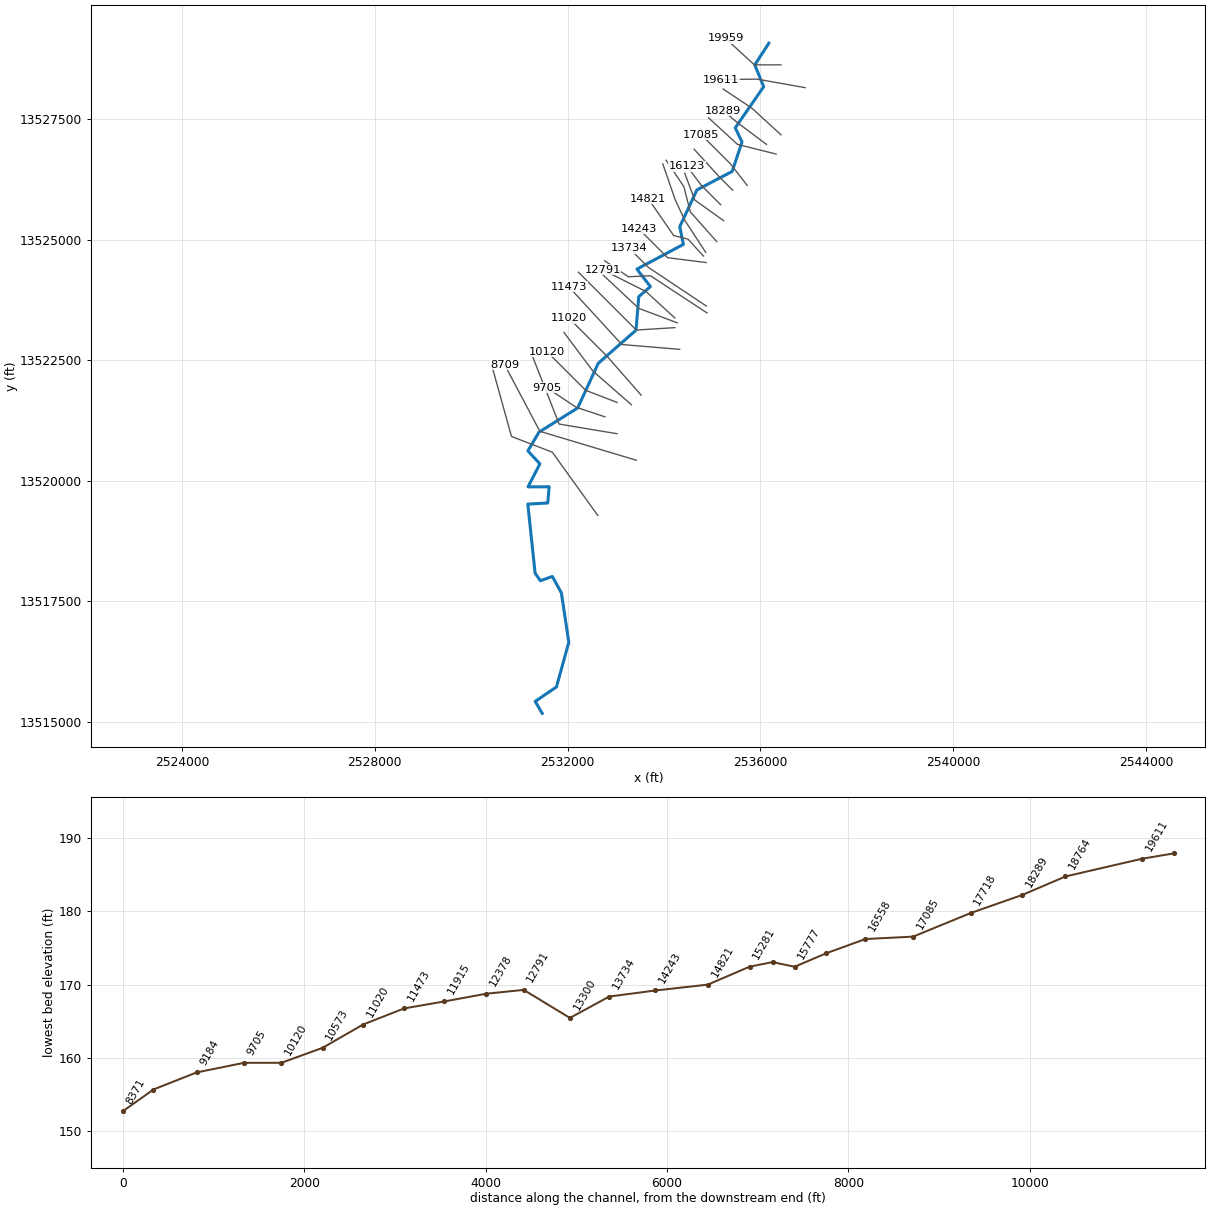
--- TRIB 3 TO TWELVEMILE CREEK.prj (project) ---

Proj Title=TRIB 3 TO TWELVEMILE CREEK Base Level Engineering
Current Plan=p01
Default Exp/Contr=0.3,0.1
English Units
Geom File=g01
Flow File=f01
Plan File=p01
BEGIN DESCRIPTION:
TRIB 3 TO TWELVEMILE CREEK
END DESCRIPTION:

--- TRIB 3 TO TWELVEMILE CREEK.p01 (plan) ---

Plan Title=Multiple Run
Short Identifier=Multiple
Geom File=g01
Flow File=f01
Subcritical Flow
K Sum by GR= 0
Std Step Tol= 0.01
Critical Tol= 0.01
Num of Std Step Trials= 20
Max Error Tol= 0.3
Flow Tol Ratio= 0.001
Split Flow NTrial= 30
Split Flow Tol= 0.02
Split Flow Ratio= 0.02
Log Output Level= 0
Friction Slope Method= 1
Unsteady Friction Slope Method= 2
Unsteady Bridges Friction Slope Method= 1
Parabolic Critical Depth
Global Vel Dist=  1 , 1 , 1
Global Log Level= 0
CheckData=True
Encroach Param= -1, 0, 0, 0
BEGIN DESCRIPTION:
Multiple Run
END DESCRIPTION:

--- TRIB 3 TO TWELVEMILE CREEK.f01 (steady flow) ---

Flow Title=Multiple
Number of Profiles=7
Profile Names=10-year,25-year,50-year,1pct_min,100-year,1pct_plu,500-year
River Rch & RM= TRIB 3 TO TWELVE,Reach-1,19959
     747    1197    1601    1036    2066    4122    3401
River Rch & RM= TRIB 3 TO TWELVE,Reach-1,16558
     869    1400    1879    1219    2433    4854    4031
River Rch & RM= TRIB 3 TO TWELVE,Reach-1,13734
    1023    1667    2253    1471    2935    5855    4927
River Rch & RM= TRIB 3 TO TWELVE,Reach-1,11915
    1200    1970    2677    1755    3502    6987    5932
River Rch & RM= TRIB 3 TO TWELVE,Reach-1,9184
    1233    2026    2755    1807    3606    7194    6115
Boundary for River Rch & Prof#=TRIB 3 TO TWELVE,Reach-1,1
Up Type=0
Dn Type=3
Dn Slope=0.005
Boundary for River Rch & Prof#=TRIB 3 TO TWELVE,Reach-1,2
Up Type=0
Dn Type=3
Dn Slope=0.005
Boundary for River Rch & Prof#=TRIB 3 TO TWELVE,Reach-1,3
Up Type=0
Dn Type=3
Dn Slope=0.005
Boundary for River Rch & Prof#=TRIB 3 TO TWELVE,Reach-1,4
Up Type=0
Dn Type=3
Dn Slope=0.005
Boundary for River Rch & Prof#=TRIB 3 TO TWELVE,Reach-1,5
Up Type=0
Dn Type=3
Dn Slope=0.005
Boundary for River Rch & Prof#=TRIB 3 TO TWELVE,Reach-1,6
Up Type=0
Dn Type=3
Dn Slope=0.005
Boundary for River Rch & Prof#=TRIB 3 TO TWELVE,Reach-1,7
Up Type=0
Dn Type=3
Dn Slope=0.005

--- TRIB 3 TO TWELVEMILE CREEK.g01 (geometry) ---

Geom Title=Existing Conditions

River Reach=TRIB 3 TO TWELVE,Reach-1
Reach XY= 30
      2536175.00     13529075.00      2535882.75     13528624.91
      2536067.50     13528171.87      2535477.14     13527319.03
      2535618.00     13527024.78      2535413.90     13526414.92
      2534682.82     13526031.19      2534326.70     13525269.36
      2534402.16     13524901.42      2533438.24     13524388.76
      2533718.12     13524025.03      2533477.06     13523819.15
      2533419.48     13523122.57      2532635.78     13522434.68
      2532208.51     13521507.95      2531407.86     13521008.55
      2531176.58     13520618.95      2531425.54     13520350.12
      2531179.99     13519872.37      2531617.66     13519875.10
      2531589.09     13519538.34      2531175.62     13519515.32
      2531326.25     13518084.70      2531435.33     13517925.87
      2531685.05     13518014.98      2531871.24     13517673.44
      2532025.50     13516650.03      2531769.16     13515722.71
      2531327.99     13515423.60      2531475.00     13515175.00

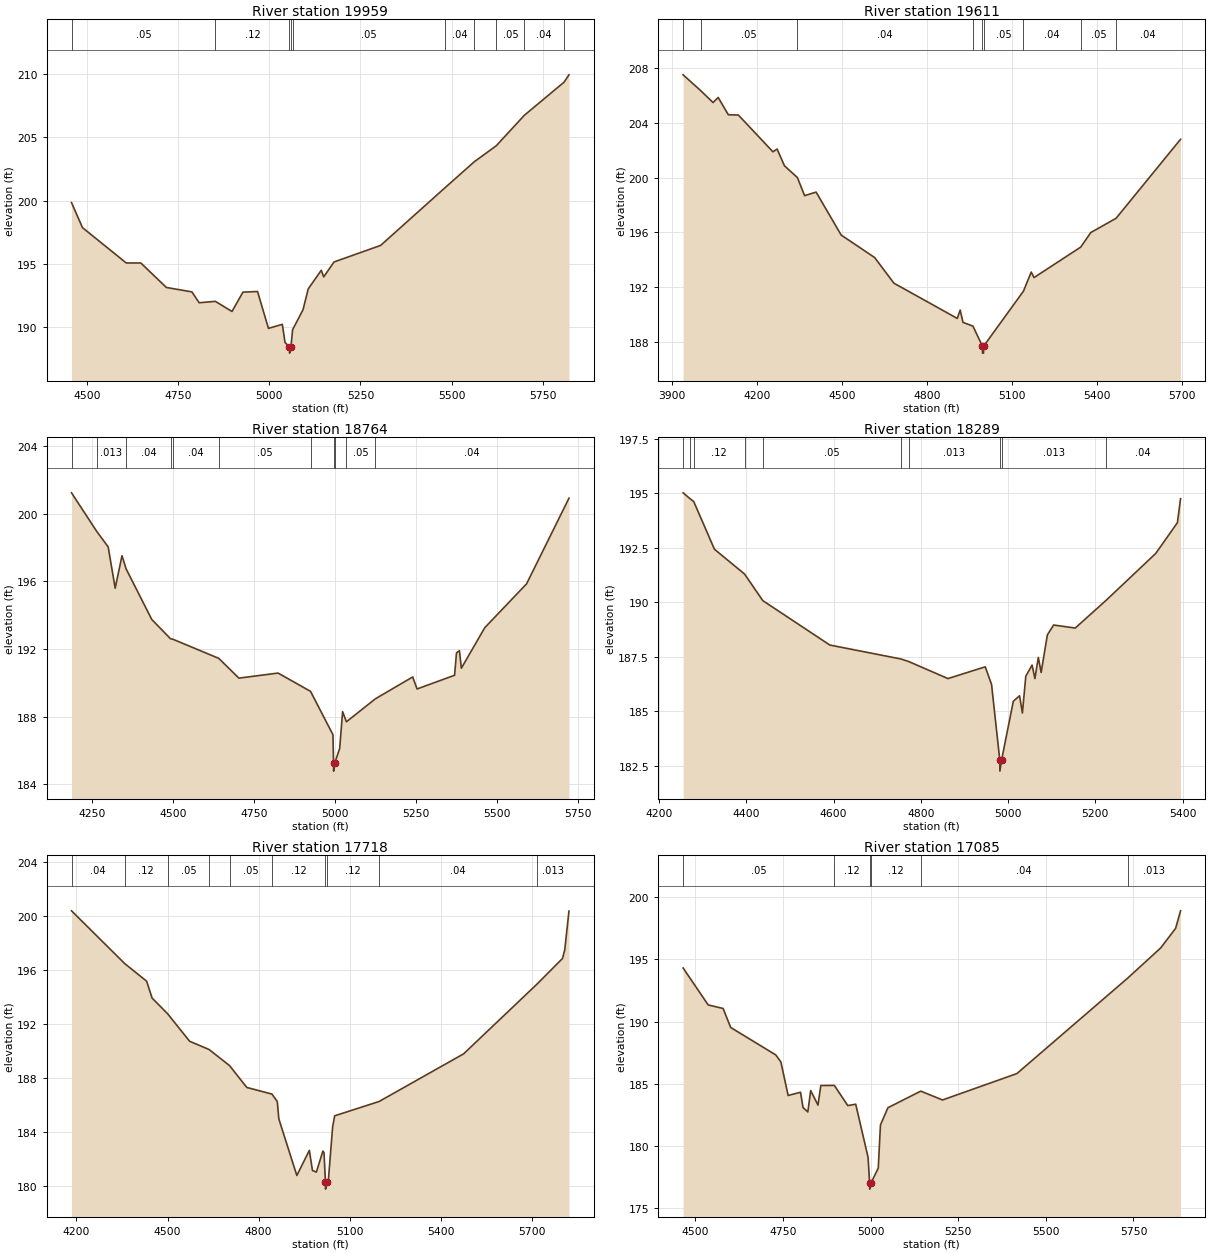
Type RM Length L Ch R = 1,19959,348,348,348
BEGIN DESCRIPTION:
TRIB 3 TO TWELVEMILE CREEK 32.0
END DESCRIPTION:
XS GIS Cut Line= 3
      2536424.97     13528625.00      2535875.00     13528625.00
      2535275.01     13529175.00
#Sta/Elev= 30
  4457.8  199.84  4487.8  197.86  4607.8  195.06  4647.8  195.06  4717.8  193.12
  4787.8  192.77  4807.8  191.91  4852.1  192.02  4897.8  191.22  4927.8  192.75
  4967.8  192.80  4997.8  189.88  5035.8  190.20  5043.2  188.76  5055.4  188.42
  5055.7  187.92  5059.4  188.42  5064.0  189.78  5092.6  191.36  5106.7  193.00
  5142.5  194.48  5149.3  193.96  5177.6  195.14  5305.3  196.45  5481.2  201.00
  5562.3  203.08  5622.7  204.35  5699.2  206.75  5808.3  209.38  5821.7  209.96
#Mann=10,-1,0
  4457.8    0.05       0  4852.1    0.12       0  5055.4    0.05       0
  5059.4    0.12       0  5064.0    0.05       0  5481.2    0.04       0
  5562.3   0.013       0  5622.7    0.05       0  5699.2    0.04       0
  5808.3    0.05       0
Bank Sta=5055.4,5059.4
Exp/Cntr=0.3,0.1

Type RM Length L Ch R = 1,19611,847,847,847
BEGIN DESCRIPTION:
Mapping XS 259c0d0b
END DESCRIPTION:
XS GIS Cut Line= 3
      2536926.66     13528152.01      2535931.87     13528329.09
      2535188.58     13528318.69
#Sta/Elev= 30
  3940.8  207.49  4002.1  206.35  4046.3  205.47  4064.4  205.84  4100.2  204.58
  4135.5  204.56  4257.4  201.88  4272.2  202.08  4298.0  200.86  4343.7  200.00
  4369.1  198.68  4409.7  198.94  4498.0  195.81  4616.0  194.17  4684.0  192.30
  4907.4  189.73  4917.6  190.34  4927.7  189.44  4962.7  189.17  4996.1  187.70
  4996.4  187.20  4999.9  187.20  5000.1  187.70  5140.8  191.72  5168.1  193.11
  5178.1  192.71  5342.6  194.93  5378.1  195.99  5467.3  197.03  5694.6  202.79
#Mann=9,-1,0
  3940.8   0.013       0  4002.1    0.05       0  4343.7    0.04       0
  4962.7    0.05       0  4996.1    0.05       0  5000.1    0.05       0
  5140.8    0.04       0  5342.6    0.05       0  5467.3    0.04       0
Bank Sta=4996.1,5000.1
Exp/Cntr=0.3,0.1

Type RM Length L Ch R = 1,18764,475,475,475
BEGIN DESCRIPTION:
TRIB 3 TO TWELVEMILE CREEK 30.0
END DESCRIPTION:
XS GIS Cut Line= 3
      2536424.99     13527175.01      2535825.00     13527725.00
      2535225.03     13528124.98
#Sta/Elev= 30
  4186.3  201.23  4263.7  198.96  4299.4  198.03  4321.0  195.59  4342.0  197.51
  4354.8  196.73  4433.9  193.74  4491.7  192.60  4499.2  192.57  4640.7  191.44
  4702.7  190.27  4823.6  190.57  4923.8  189.49  4993.1  186.92  4994.8  185.27
  4995.1  184.77  4998.8  185.27  5013.8  186.11  5022.8  188.29  5034.6  187.69
  5124.2  189.05  5239.1  190.34  5252.6  189.63  5368.3  190.44  5374.3  191.77
  5383.3  191.89  5389.3  190.86  5461.4  193.25  5590.6  195.85  5721.3  200.91
#Mann=11,-1,0
  4186.3    0.05       0  4263.7   0.013       0  4354.8    0.04       0
  4491.7    0.05       0  4499.2    0.04       0  4640.7    0.05       0
  4923.8    0.12       0  4994.8    0.05       0  4998.8    0.12       0
  5034.6    0.05       0  5124.2    0.04       0
Bank Sta=4994.8,4998.8
Exp/Cntr=0.3,0.1

Type RM Length L Ch R = 1,18289,571,571,571
BEGIN DESCRIPTION:
TRIB 3 TO TWELVEMILE CREEK 29.0
END DESCRIPTION:
XS GIS Cut Line= 3
      2536124.96     13526975.03      2535525.00     13527425.00
      2535224.97     13527675.02
#Sta/Elev= 30
  4254.8  195.03  4270.1  194.77  4279.1  194.63  4326.6  192.44  4395.7  191.30
  4437.5  190.08  4591.2  188.04  4754.2  187.40  4772.3  187.28  4862.0  186.50
  4947.5  187.04  4962.0  186.23  4980.9  182.75  4981.1  182.25  4984.9  182.75
  5011.9  185.46  5026.2  185.71  5032.7  184.92  5040.5  186.61  5054.9  187.12
  5061.4  186.50  5069.2  187.47  5075.7  186.78  5090.0  188.51  5104.3  188.96
  5153.8  188.82  5223.9  190.08  5338.6  192.25  5388.1  193.66  5395.3  194.76
#Mann=10,-1,0
  4254.8    0.04       0  4270.1    0.05       0  4279.1    0.12       0
  4395.7   0.013       0  4437.5    0.05       0  4754.2    0.04       0
  4772.3   0.013       0  4980.9    0.03       0  4984.9   0.013       0
  5223.9    0.04       0
Bank Sta=4980.9,4984.9
Exp/Cntr=0.3,0.1

Type RM Length L Ch R = 1,17718,633,633,633
BEGIN DESCRIPTION:
TRIB 3 TO TWELVEMILE CREEK 28.0
END DESCRIPTION:
XS GIS Cut Line= 3
      2536325.02     13526775.00      2535525.00     13526975.00
      2534924.98     13527525.02
#Sta/Elev= 30
  4183.7  200.38  4359.5  196.46  4431.1  195.17  4449.1  193.92  4500.1  192.76
  4572.8  190.72  4636.7  190.11  4704.2  188.92  4761.0  187.30  4843.8  186.81
  4861.5  186.26  4866.6  184.97  4925.9  180.78  4967.1  182.64  4977.4  181.15
  4990.3  181.03  5011.7  182.59  5015.4  182.48  5020.2  180.27  5020.5  179.77
  5024.3  180.27  5029.6  180.37  5043.8  184.38  5050.6  185.20  5196.9  186.26
  5475.4  189.79  5717.4  194.96  5801.0  196.85  5808.4  197.48  5822.3  200.36
#Mann=10,-1,0
  4183.7    0.04       0  4359.5    0.12       0  4500.1    0.05       0
  4636.7   0.013       0  4704.2    0.05       0  4843.8    0.12       0
  5020.2    0.05       0  5024.3    0.12       0  5196.9    0.04       0
  5717.4   0.013       0
Bank Sta=5020.2,5024.3
Exp/Cntr=0.3,0.1

Type RM Length L Ch R = 1,17085,527,527,527
BEGIN DESCRIPTION:
TRIB 3 TO TWELVEMILE CREEK 27.0
END DESCRIPTION:
XS GIS Cut Line= 3
      2535724.99     13526125.01      2535375.00     13526575.00
      2534775.00     13527175.00
#Sta/Elev= 30
  4465.6  194.31  4537.1  191.34  4579.6  191.06  4601.3  189.53  4729.8  187.33
  4744.3  186.77  4765.1  184.07  4800.4  184.33  4807.6  183.10  4821.2  182.75
  4829.4  184.46  4850.2  183.30  4858.3  184.87  4896.9  184.88  4935.2  183.26
  4957.8  183.37  4993.1  179.10  4997.4  177.05  4997.7  176.55  5001.5  177.05
  5022.1  178.24  5028.4  181.71  5049.8  183.09  5143.3  184.42  5205.4  183.71
  5417.5  185.83  5733.2  193.49  5827.6  195.92  5870.1  197.49  5884.2  198.90
#Mann=6,-1,0
  4465.6    0.05       0  4896.9    0.12       0  4997.4    0.05       0
  5001.5    0.12       0  5143.3    0.04       0  5733.2   0.013       0
Bank Sta=4997.4,5001.5
Exp/Cntr=0.3,0.1

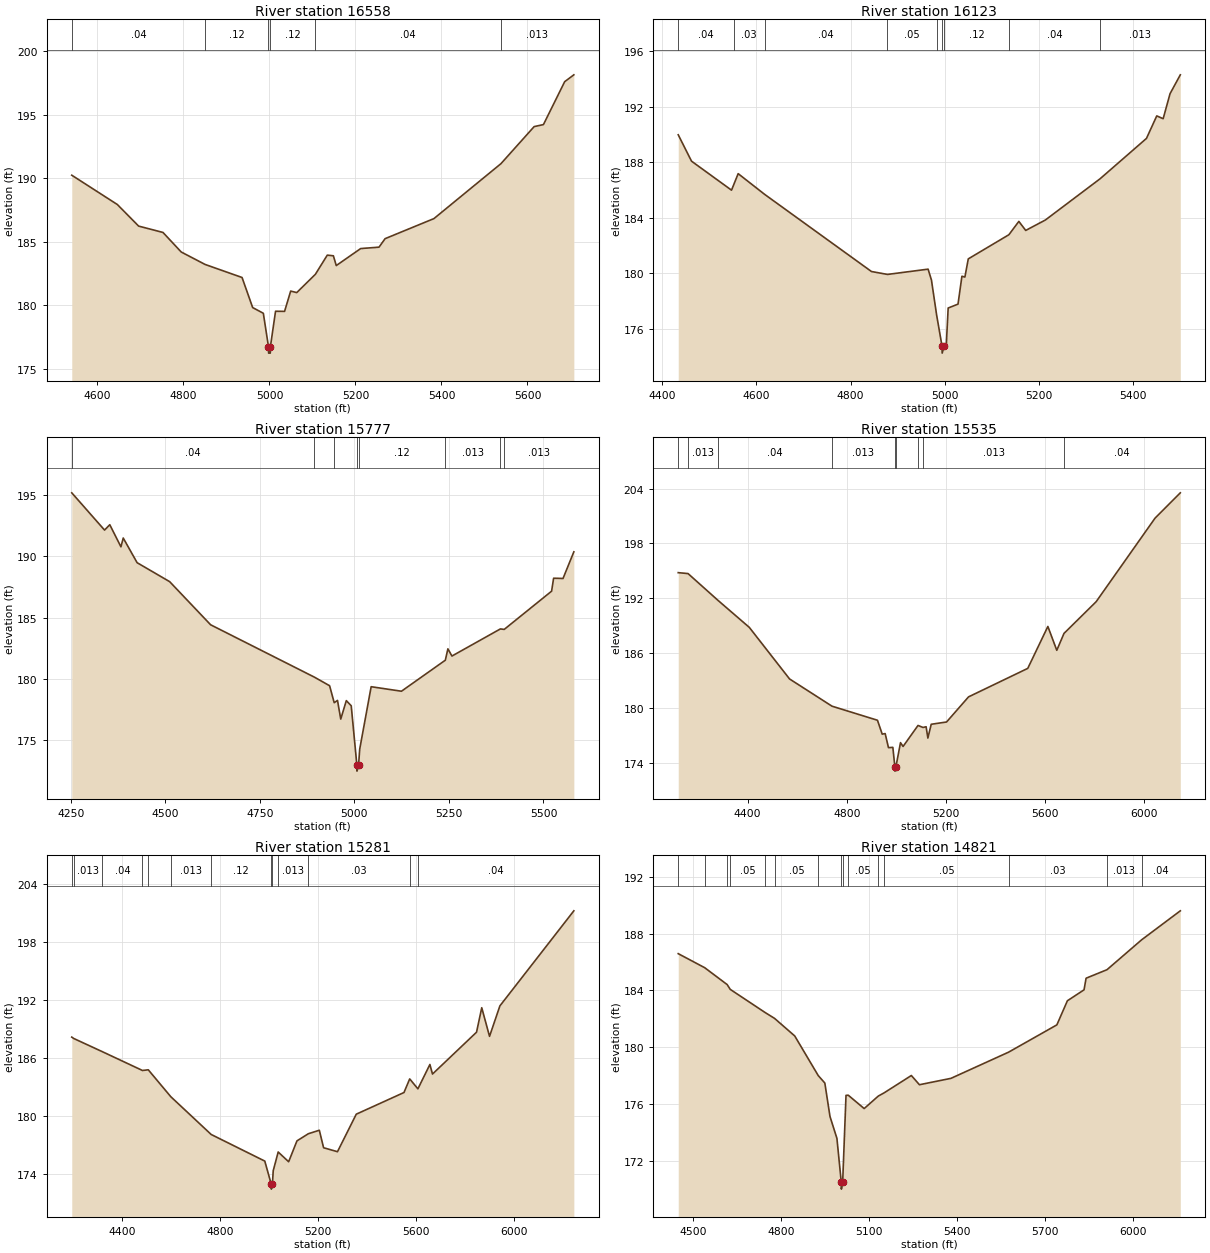
Type RM Length L Ch R = 1,16558,435,435,435
BEGIN DESCRIPTION:
TRIB 3 TO TWELVEMILE CREEK 26.0
END DESCRIPTION:
XS GIS Cut Line= 3
      2535424.99     13526025.01      2535125.00     13526325.00
      2534624.97     13526875.04
#Sta/Elev= 30
  4540.3  190.24  4646.3  187.93  4695.8  186.23  4752.4  185.73  4794.8  184.19
  4850.2  183.21  4936.3  182.18  4961.0  179.81  4985.8  179.36  4997.8  176.72
  4998.1  176.22  5001.9  176.22  5002.2  176.72  5014.2  179.52  5035.2  179.51
  5049.4  181.11  5063.5  180.99  5106.8  182.43  5134.5  183.94  5148.7  183.89
  5155.4  183.12  5212.2  184.46  5254.8  184.57  5269.0  185.24  5382.5  186.82
  5538.4  191.15  5615.6  194.07  5637.2  194.23  5686.6  197.61  5707.9  198.15
#Mann=6,-1,0
  4540.3    0.04       0  4850.2    0.12       0  4997.8    0.05       0
  5002.2    0.12       0  5106.8    0.04       0  5538.4   0.013       0
Bank Sta=4997.8,5002.2
Exp/Cntr=0.3,0.1

Type RM Length L Ch R = 1,16123,346,346,346
BEGIN DESCRIPTION:
TRIB 3 TO TWELVEMILE CREEK 25.0
END DESCRIPTION:
XS GIS Cut Line= 3
      2535174.97     13525725.03      2534775.00     13526125.00
      2534475.03     13526524.96
#Sta/Elev= 30
  4434.1  189.99  4462.3  188.09  4547.2  186.00  4552.3  186.43  4561.3  187.19
  4617.4  185.70  4844.2  180.14  4878.2  179.93  4964.4  180.31  4971.5  179.53
  4982.5  177.01  4994.0  174.76  4994.3  174.26  4998.4  174.76  5002.9  174.76
  5007.0  177.51  5027.9  177.79  5036.2  179.80  5042.5  179.74  5049.7  181.05
  5135.9  182.79  5157.0  183.75  5171.6  183.10  5213.3  183.85  5329.4  186.82
  5427.9  189.73  5449.7  191.35  5463.3  191.15  5477.9  192.95  5499.7  194.31
#Mann=9,-1,0
  4434.1    0.04       0  4552.3    0.03       0  4617.4    0.04       0
  4878.2    0.05       0  4982.5    0.12       0  4994.0    0.05       0
  4998.4    0.12       0  5135.9    0.04       0  5329.4   0.013       0
Bank Sta=4994,4998.4
Exp/Cntr=0.3,0.1

Type RM Length L Ch R = 1,15777,242,242,242
BEGIN DESCRIPTION:
Mapping XS eb55945f
END DESCRIPTION:
XS GIS Cut Line= 3
      2535235.55     13525394.25      2534638.30     13525821.35
      2534430.00     13526376.83
#Sta/Elev= 30
  4252.8  195.21  4339.5  192.16  4353.3  192.60  4382.8  190.79  4388.9  191.51
  4425.6  189.49  4511.6  187.94  4619.9  184.41  4894.5  180.12  4934.5  179.42
  4946.7  178.03  4955.4  178.22  4964.0  176.69  4978.7  178.20  4991.7  177.78
  5006.6  172.93  5006.9  172.43  5011.1  172.93  5014.2  174.24  5044.4  179.34
  5124.5  178.97  5240.5  181.51  5247.3  182.44  5258.0  181.85  5386.1  184.07
  5396.2  184.03  5521.5  187.16  5526.8  188.22  5551.7  188.20  5580.3  190.38
#Mann=8,-1,0
  4252.8    0.04       0  4894.5    0.05       0  4946.7    0.12       0
  5006.6    0.05       0  5011.1    0.12       0  5240.5   0.013       0
  5386.1    0.04       0  5396.2   0.013       0
Bank Sta=5006.6,5011.1
Exp/Cntr=0.3,0.1

Type RM Length L Ch R = 1,15535,254,254,254
BEGIN DESCRIPTION:
Mapping XS fd2b08d9
END DESCRIPTION:
XS GIS Cut Line= 4
      2535093.33     13524959.30      2534544.72     13525577.35
      2534412.77     13526098.19      2534044.74     13526646.77
#Sta/Elev= 30
  4120.6  194.80  4160.1  194.70  4282.0  191.74  4407.1  188.81  4569.5  183.16
  4740.6  180.18  4923.9  178.64  4943.0  177.12  4954.9  177.18  4968.3  175.64
  4985.9  175.67  4993.9  173.57  4994.2  173.07  4998.4  173.57  5016.8  176.19
  5027.1  175.77  5087.4  178.07  5107.6  177.85  5120.0  177.93  5127.1  176.69
  5140.6  178.20  5202.5  178.45  5291.1  181.20  5529.9  184.32  5610.9  188.91
  5646.9  186.30  5676.0  188.15  5805.6  191.62  6043.1  200.77  6144.9  203.54
#Mann=9,-1,0
  4120.6    0.04       0  4160.1   0.013       0  4282.0    0.04       0
  4740.6   0.013       0  4993.9    0.03       0  4998.4   0.013       0
  5087.4    0.12       0  5107.6   0.013       0  5676.0    0.04       0
Bank Sta=4993.9,4998.4
Exp/Cntr=0.3,0.1

Type RM Length L Ch R = 1,15281,460,460,460
BEGIN DESCRIPTION:
Mapping XS ab3a9c37
END DESCRIPTION:
XS GIS Cut Line= 4
      2534864.17     13524737.06      2534433.60     13525396.80
      2534232.22     13525827.35      2533975.33     13526570.25
#Sta/Elev= 30
  4194.9  188.16  4202.8  188.02  4319.2  186.66  4483.4  184.71  4507.2  184.78
  4599.0  182.00  4764.0  178.09  4982.7  175.34  5009.2  172.94  5009.5  172.44
  5013.9  172.94  5017.1  174.34  5037.4  176.28  5080.1  175.27  5114.0  177.43
  5160.6  178.17  5205.3  178.53  5222.7  176.72  5279.4  176.31  5356.1  180.19
  5550.8  182.43  5574.2  183.84  5607.6  182.81  5656.6  185.33  5667.2  184.34
  5847.0  188.67  5868.2  191.20  5900.0  188.24  5942.3  191.39  6244.1  201.22
#Mann=13,-1,0
  4194.9    0.04       0  4202.8   0.013       0  4319.2    0.04       0
  4483.4   0.013       0  4507.2    0.05       0  4599.0   0.013       0
  4764.0    0.12       0  5009.2    0.05       0  5013.9    0.12       0
  5037.4   0.013       0  5160.6    0.03       0  5574.2   0.013       0
  5607.6    0.04       0
Bank Sta=5009.2,5013.9
Exp/Cntr=0.3,0.1

Type RM Length L Ch R = 1,14821,578,578,578
BEGIN DESCRIPTION:
Mapping XS 80e7de85
END DESCRIPTION:
XS GIS Cut Line= 4
      2534818.85     13524658.16      2534499.41     13525008.85
      2534200.80     13525085.24      2533673.01     13525849.15
#Sta/Elev= 30
  4449.0  186.59  4539.3  185.60  4615.8  184.41  4626.4  184.07  4745.9  182.43
  4777.1  182.03  4846.0  180.79  4926.3  177.99  4948.6  177.47  4966.2  175.11
  4989.8  173.57  5004.6  170.49  5005.0  169.99  5009.4  170.49  5020.8  176.60
  5028.5  176.61  5082.7  175.67  5130.8  176.55  5150.9  176.78  5243.5  178.00
  5271.0  177.35  5378.5  177.80  5575.3  179.65  5739.4  181.57  5775.3  183.27
  5832.0  184.04  5839.0  184.86  5910.3  185.46  6027.9  187.56  6160.1  189.61
#Mann=15,-1,0
  4449.0    0.04       0  4539.3   0.013       0  4615.8    0.04       0
  4626.4    0.05       0  4745.9    0.04       0  4777.1    0.05       0
  4926.3    0.12       0  5004.6    0.05       0  5009.4    0.12       0
  5028.5    0.05       0  5130.8    0.12       0  5150.9    0.05       0
  5575.3    0.03       0  5910.3   0.013       0  6027.9    0.04       0
Bank Sta=5004.6,5009.4
Exp/Cntr=0.3,0.1

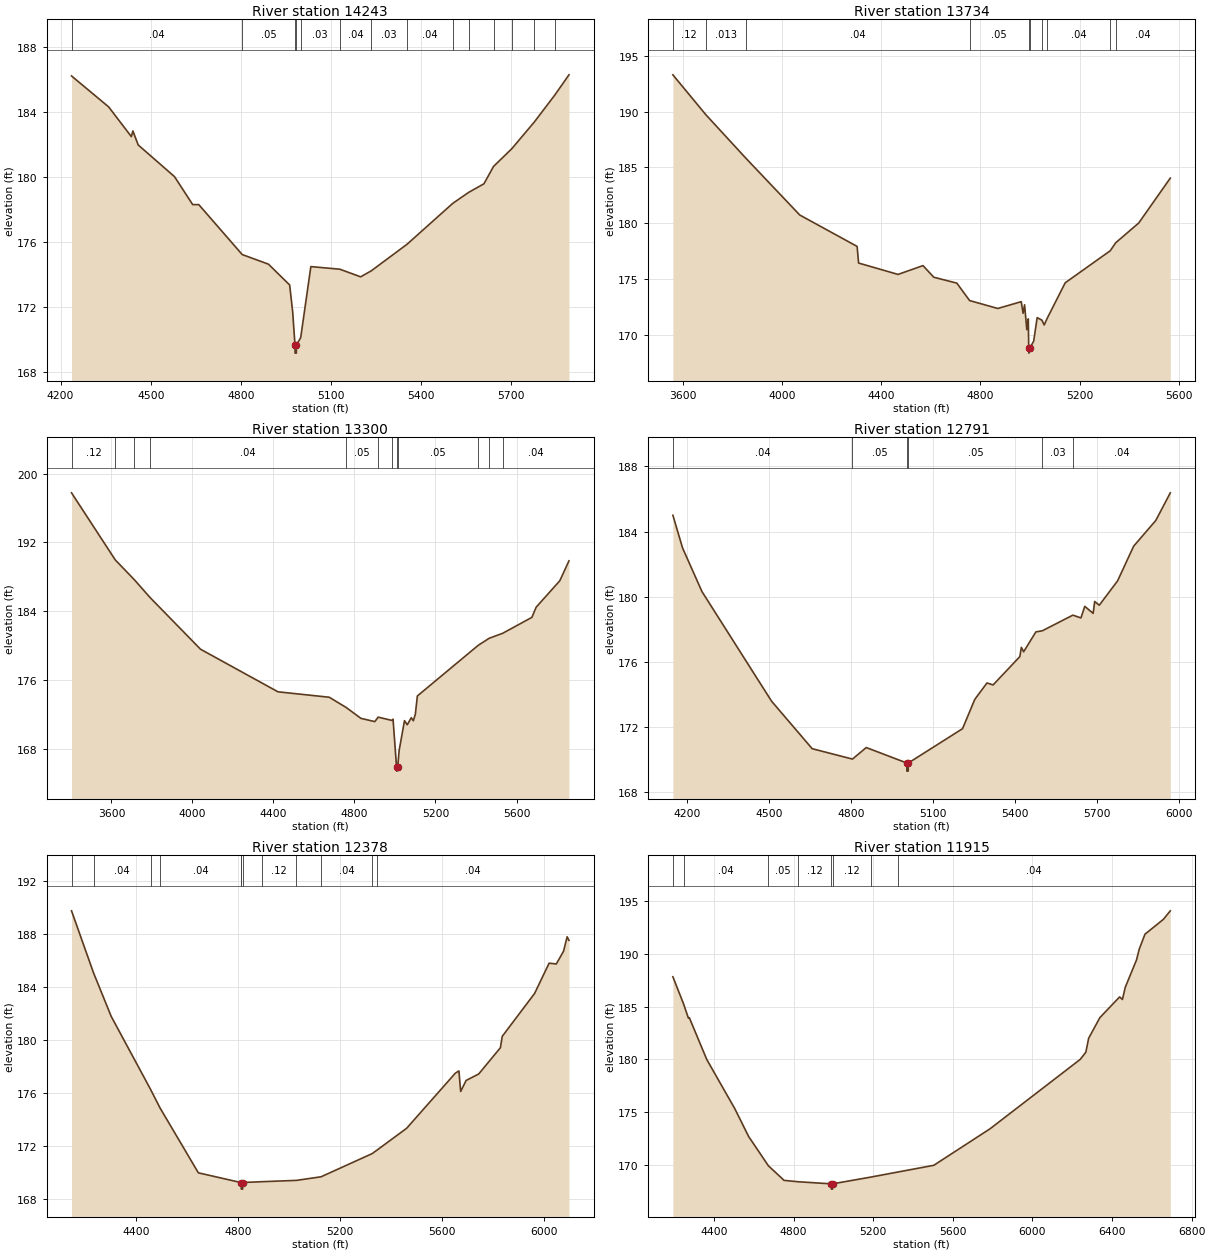
Type RM Length L Ch R = 1,14243,509,509,509
BEGIN DESCRIPTION:
TRIB 3 TO TWELVEMILE CREEK 21.0
END DESCRIPTION:
XS GIS Cut Line= 3
      2534874.98     13524525.00      2534075.00     13524625.00
      2533475.03     13525224.97
#Sta/Elev= 30
  4236.7  186.23  4360.1  184.33  4435.7  182.50  4440.8  182.85  4458.4  181.99
  4579.3  180.04  4639.8  178.32  4660.0  178.32  4804.5  175.25  4891.7  174.66
  4962.3  173.38  4972.4  171.72  4980.0  169.69  4980.4  169.19  4984.5  169.19
  4984.8  169.69  4999.0  170.14  5032.8  174.51  5129.2  174.35  5198.5  173.88
  5233.8  174.25  5352.6  175.88  5505.0  178.40  5558.4  179.08  5608.6  179.60
  5640.6  180.67  5701.4  181.76  5776.2  183.40  5844.5  185.06  5891.4  186.30
#Mann=14,-1,0
  4236.7    0.04       0  4804.5    0.05       0  4980.0    0.03       0
  4984.8    0.05       0  4999.0    0.03       0  5129.2    0.04       0
  5233.8    0.03       0  5352.6    0.04       0  5505.0    0.05       0
  5558.4    0.04       0  5640.6    0.03       0  5701.4    0.04       0
  5776.2    0.03       0  5844.5    0.04       0
Bank Sta=4980,4984.8
Exp/Cntr=0.3,0.1

Type RM Length L Ch R = 1,13734,434,434,434
BEGIN DESCRIPTION:
TRIB 3 TO TWELVEMILE CREEK 20.0
END DESCRIPTION:
XS GIS Cut Line= 3
      2534875.01     13523624.99      2533675.00     13524425.00
      2533275.01     13524824.99
#Sta/Elev= 30
  3558.5  193.29  3691.5  189.72  3854.0  185.80  4070.8  180.73  4302.2  177.92
  4308.2  176.43  4467.4  175.41  4568.1  176.20  4611.6  175.16  4704.8  174.63
  4756.2  173.07  4870.0  172.36  4964.7  172.97  4972.2  171.93  4978.2  172.69
  4987.2  170.46  4993.2  171.43  4994.9  168.86  4995.4  168.36  5000.5  168.86
  5014.9  169.43  5029.0  171.54  5048.4  171.31  5057.3  170.88  5069.1  171.46
  5142.2  174.66  5323.9  177.53  5346.2  178.25  5439.1  180.02  5566.4  184.04
#Mann=10,-1,0
  3558.5    0.12       0  3691.5   0.013       0  3854.0    0.04       0
  4756.2    0.05       0  4994.9    0.05       0  5000.5    0.05       0
  5048.4    0.03       0  5069.1    0.04       0  5323.9    0.03       0
  5346.2    0.04       0
Bank Sta=4994.9,5000.5
Exp/Cntr=0.3,0.1

Type RM Length L Ch R = 1,13300,509,509,509
BEGIN DESCRIPTION:
Mapping XS 04d0de82
END DESCRIPTION:
XS GIS Cut Line= 4
      2534891.91     13523480.15      2533718.33     13524250.97
      2533259.99     13524230.13      2532768.47     13524562.43
#Sta/Elev= 30
  3402.8  197.76  3618.7  189.97  3712.5  187.68  3790.9  185.59  4039.6  179.60
  4422.3  174.65  4675.4  174.02  4758.4  172.84  4831.7  171.57  4900.3  171.19
  4917.0  171.71  4984.6  171.33  4990.4  171.47  5007.6  165.94  5008.0  165.44
  5013.3  165.94  5020.4  167.83  5046.9  171.30  5060.5  170.82  5080.5  171.65
  5090.5  171.29  5100.5  172.05  5110.5  174.17  5411.0  180.05  5465.2  180.87
  5532.0  181.45  5676.1  183.30  5697.1  184.48  5813.9  187.55  5859.0  189.86
#Mann=12,-1,0
  3402.8    0.12       0  3618.7    0.04       0  3712.5   0.013       0
  3790.9    0.04       0  4758.4    0.05       0  4917.0    0.03       0
  4984.6    0.05       0  5007.6    0.05       0  5013.3    0.05       0
  5411.0    0.03       0  5465.2    0.05       0  5532.0    0.04       0
Bank Sta=5007.6,5013.3
Exp/Cntr=0.3,0.1

Type RM Length L Ch R = 1,12791,413,413,413
BEGIN DESCRIPTION:
TRIB 3 TO TWELVEMILE CREEK 18.0
END DESCRIPTION:
XS GIS Cut Line= 3
      2534225.03     13523374.97      2533625.00     13523925.00
      2532725.01     13524374.99
#Sta/Elev= 30
  4148.4  185.00  4183.9  182.99  4254.8  180.31  4509.5  173.57  4658.1  170.65
  4805.5  170.01  4856.0  170.72  5004.3  169.77  5004.7  169.27  5009.5  169.27
  5010.0  169.77  5208.4  171.88  5253.1  173.68  5297.8  174.69  5320.2  174.57
  5418.0  176.31  5423.6  176.88  5432.0  176.61  5476.7  177.83  5500.5  177.90
  5612.0  178.86  5641.6  178.69  5655.6  179.40  5686.3  178.97  5691.9  179.70
  5708.7  179.47  5775.8  180.97  5834.5  183.10  5915.5  184.68  5968.6  186.38
#Mann=6,-1,0
  4148.4    0.04       0  4805.5    0.05       0  5004.3    0.05       0
  5010.0    0.05       0  5500.5    0.03       0  5612.0    0.04       0
Bank Sta=5004.3,5010
Exp/Cntr=0.3,0.1

Type RM Length L Ch R = 1,12378,463,463,463
BEGIN DESCRIPTION:
TRIB 3 TO TWELVEMILE CREEK 17.0
END DESCRIPTION:
XS GIS Cut Line= 3
      2534274.98     13523275.01      2533475.00     13523575.00
      2532674.98     13524325.02
#Sta/Elev= 30
  4145.6  189.75  4231.9  185.07  4301.3  181.78  4455.5  176.28  4492.3  174.89
  4643.1  169.98  4809.1  169.25  4811.1  169.25  4811.6  168.75  4816.4  168.75
  4816.9  169.25  4891.4  169.31  5027.8  169.41  5124.2  169.68  5324.7  171.43
  5342.0  171.67  5459.9  173.34  5650.9  177.50  5665.0  177.67  5671.9  176.12
  5693.3  176.95  5742.7  177.44  5827.7  179.42  5835.0  180.28  5962.0  183.52
  6018.7  185.80  6047.0  185.74  6075.3  186.70  6089.5  187.79  6096.6  187.52
#Mann=12,-1,0
  4145.6   0.013       0  4231.9    0.04       0  4455.5    0.05       0
  4492.3    0.04       0  4809.1    0.05       0  4811.1    0.05       0
  4816.9    0.05       0  4891.4    0.12       0  5027.8    0.05       0
  5124.2    0.04       0  5324.7    0.05       0  5342.0    0.04       0
Bank Sta=4811.1,4816.9
Exp/Cntr=0.3,0.1

Type RM Length L Ch R = 1,11915,442,442,442
BEGIN DESCRIPTION:
TRIB 3 TO TWELVEMILE CREEK 16.0
END DESCRIPTION:
XS GIS Cut Line= 3
      2534224.98     13523175.00      2533425.00     13523125.00
      2532225.00     13524325.00
#Sta/Elev= 30
  4194.1  187.84  4248.0  185.26  4271.7  183.93  4276.7  183.96  4364.4  179.99
  4504.7  175.34  4574.8  172.68  4673.7  169.91  4752.7  168.52  4823.5  168.39
  4990.2  168.19  4990.7  167.69  4995.6  167.69  4996.1  168.19  5190.6  168.84
  5326.2  169.32  5504.8  169.95  5787.6  173.42  6240.1  180.00  6268.4  180.68
  6282.6  182.01  6339.1  183.97  6438.1  185.93  6452.3  185.69  6466.4  186.84
  6523.0  189.44  6537.1  190.49  6565.4  191.88  6657.3  193.28  6692.7  194.10
#Mann=8,-1,0
  4194.1   0.013       0  4248.0    0.04       0  4673.7    0.05       0
  4823.5    0.12       0  4990.2    0.05       0  4996.1    0.12       0
  5190.6    0.05       0  5326.2    0.04       0
Bank Sta=4990.2,4996.1
Exp/Cntr=0.3,0.1

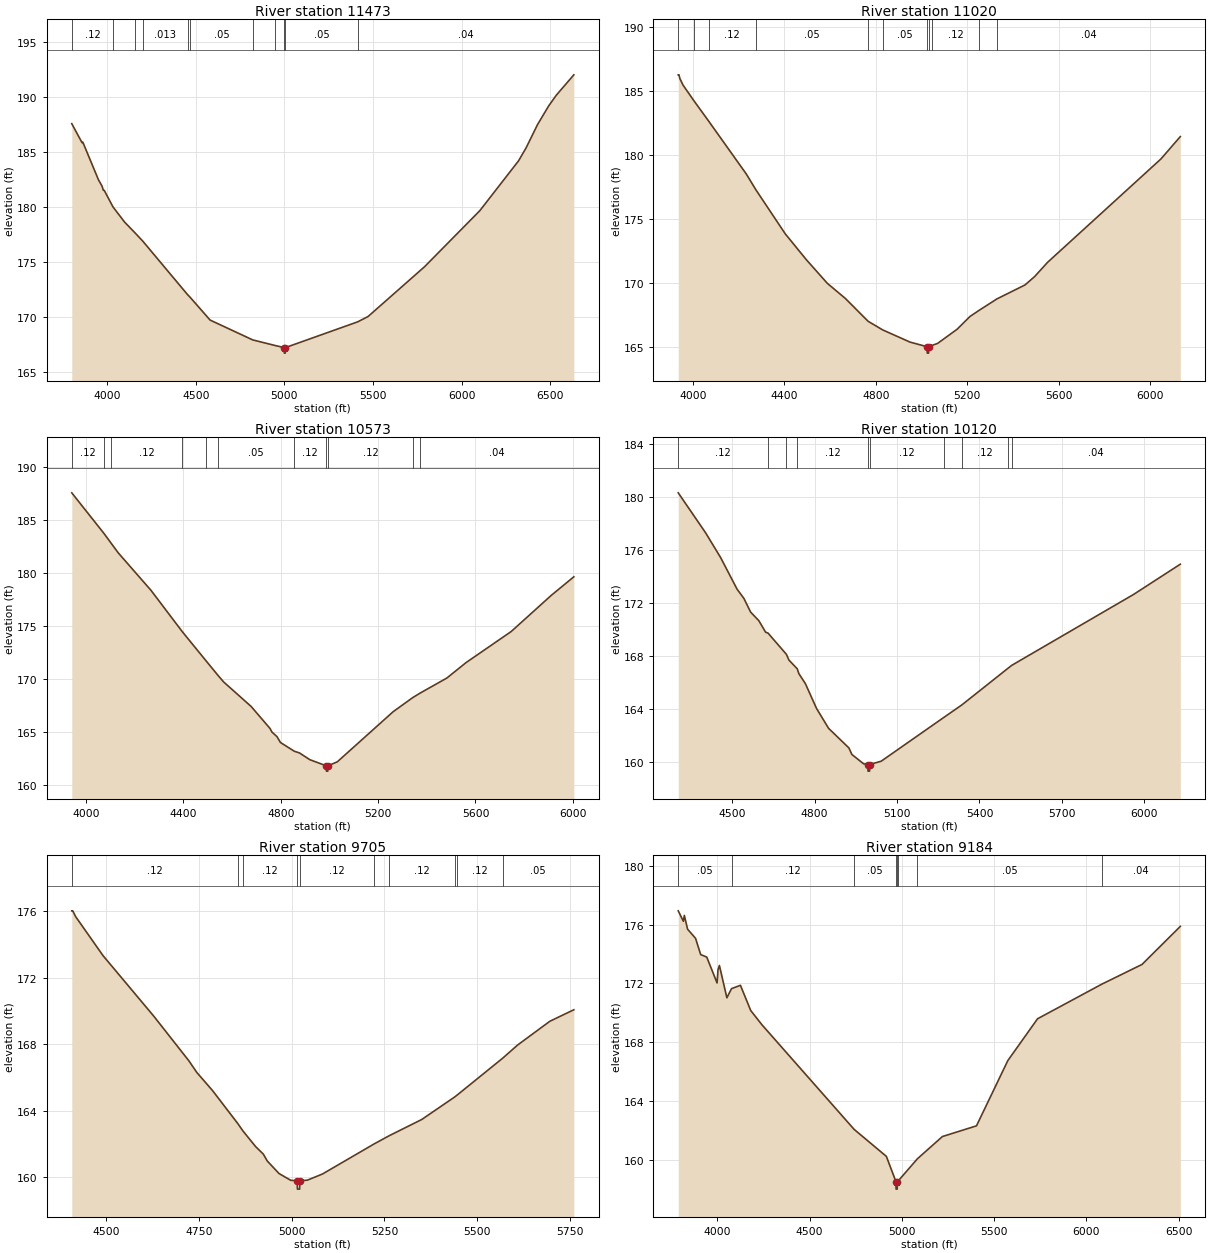
Type RM Length L Ch R = 1,11473,453,453,453
BEGIN DESCRIPTION:
TRIB 3 TO TWELVEMILE CREEK 15.0
END DESCRIPTION:
XS GIS Cut Line= 3
      2534324.96     13522725.00      2533125.00     13522825.00
      2532025.00     13524025.00
#Sta/Elev= 30
  3800.7  187.56  3858.4  185.84  3863.4  185.87  3951.2  182.47  3971.3  181.90
  3978.8  181.52  3983.8  181.51  4033.5  180.00  4099.2  178.62  4157.0  177.66
  4201.9  176.89  4453.7  172.05  4468.2  171.81  4580.9  169.74  4821.4  167.94
  4948.2  167.43  4999.3  167.24  4999.8  166.74  5004.8  166.74  5005.3  167.24
  5413.7  169.58  5471.9  170.06  5790.7  174.58  6102.1  179.66  6321.0  184.19
  6363.6  185.37  6427.7  187.47  6491.2  189.18  6533.7  190.14  6632.7  191.99
#Mann=11,-1,0
  3800.7    0.12       0  4033.5    0.05       0  4157.0    0.12       0
  4201.9   0.013       0  4453.7    0.04       0  4468.2    0.05       0
  4821.4    0.12       0  4948.2    0.05       0  4999.3    0.05       0
  5005.3    0.05       0  5413.7    0.04       0
Bank Sta=4999.3,5005.3
Exp/Cntr=0.3,0.1

Type RM Length L Ch R = 1,11020,447,447,447
BEGIN DESCRIPTION:
TRIB 3 TO TWELVEMILE CREEK 14.0
END DESCRIPTION:
XS GIS Cut Line= 3
      2533524.98     13521775.02      2532825.00     13522575.00
      2532024.97     13523375.03
#Sta/Elev= 30
  3936.4  186.26  3939.7  186.26  3943.5  185.97  3957.7  185.45  4006.8  184.19
  4069.7  182.64  4233.9  178.52  4276.1  177.28  4403.8  173.86  4495.9  171.84
  4587.9  169.99  4666.7  168.81  4766.7  167.02  4830.3  166.35  4949.6  165.40
  5024.4  165.04  5024.9  164.54  5030.5  164.54  5031.0  165.04  5045.7  165.14
  5070.1  165.30  5155.0  166.40  5211.5  167.40  5249.7  167.86  5329.1  168.77
  5451.9  169.86  5494.4  170.52  5550.9  171.63  6045.9  179.69  6130.8  181.44
#Mann=11,-1,0
  3936.4    0.12       0  4006.8    0.05       0  4069.7    0.12       0
  4276.1    0.05       0  4766.7    0.12       0  4830.3    0.05       0
  5024.4    0.05       0  5031.0    0.05       0  5045.7    0.12       0
  5249.7    0.05       0  5329.1    0.04       0
Bank Sta=5024.4,5031
Exp/Cntr=0.3,0.1

Type RM Length L Ch R = 1,10573,453,453,453
BEGIN DESCRIPTION:
TRIB 3 TO TWELVEMILE CREEK 13.0
END DESCRIPTION:
XS GIS Cut Line= 3
      2533325.01     13521574.99      2532525.00     13522275.00
      2531925.02     13523074.97
#Sta/Elev= 30
  3941.2  187.60  4073.5  183.77  4101.0  182.91  4132.5  181.93  4267.2  178.39
  4395.5  174.50  4491.0  171.81  4540.6  170.42  4565.3  169.76  4678.2  167.45
  4756.0  165.37  4763.6  165.04  4784.5  164.60  4798.7  164.05  4856.1  163.22
  4876.6  163.07  4919.3  162.43  4987.1  161.85  4987.6  161.35  4993.3  161.35
  4993.8  161.85  5032.4  162.23  5261.5  166.95  5342.5  168.29  5373.3  168.72
  5482.4  170.13  5561.5  171.59  5746.9  174.52  5911.5  177.93  6004.2  179.68
#Mann=11,-1,0
  3941.2    0.12       0  4073.5    0.05       0  4101.0    0.12       0
  4395.5    0.05       0  4491.0   0.013       0  4540.6    0.05       0
  4856.1    0.12       0  4987.1    0.05       0  4993.8    0.12       0
  5342.5    0.05       0  5373.3    0.04       0
Bank Sta=4987.1,4993.8
Exp/Cntr=0.3,0.1

Type RM Length L Ch R = 1,10120,415,415,415
BEGIN DESCRIPTION:
TRIB 3 TO TWELVEMILE CREEK 12.0
END DESCRIPTION:
XS GIS Cut Line= 3
      2533025.01     13521625.00      2532375.00     13521875.00
      2531575.00     13522675.00
#Sta/Elev= 30
  4303.3  180.33  4403.0  177.31  4457.6  175.44  4517.6  173.05  4542.2  172.36
  4566.9  171.32  4596.9  170.67  4621.5  169.80  4630.0  169.74  4697.2  168.13
  4706.2  167.70  4736.5  167.04  4742.6  166.67  4766.2  165.92  4806.9  164.04
  4850.8  162.54  4924.7  161.06  4935.4  160.57  4978.3  159.86  4993.7  159.81
  4994.2  159.31  5000.0  159.31  5000.5  159.81  5042.2  160.06  5270.5  163.37
  5335.1  164.30  5504.5  167.09  5517.4  167.30  5961.4  172.66  6131.1  174.94
#Mann=10,-1,0
  4303.3    0.12       0  4630.0   0.013       0  4697.2    0.05       0
  4736.5    0.12       0  4993.7    0.05       0  5000.5    0.12       0
  5270.5    0.05       0  5335.1    0.12       0  5504.5    0.05       0
  5517.4    0.04       0
Bank Sta=4993.7,5000.5
Exp/Cntr=0.3,0.1

Type RM Length L Ch R = 1,9705,521,521,521
BEGIN DESCRIPTION:
TRIB 3 TO TWELVEMILE CREEK 11.0
END DESCRIPTION:
XS GIS Cut Line= 3
      2532774.97     13521325.01      2532175.00     13521525.00
      2531575.03     13521924.98
#Sta/Elev= 30
  4407.0  176.01  4409.6  176.01  4417.5  175.66  4491.3  173.32  4628.3  169.68
  4723.2  166.99  4744.3  166.30  4786.4  165.22  4854.5  163.24  4868.6  162.79
  4902.4  161.86  4923.5  161.40  4934.0  160.99  4965.6  160.24  4997.3  159.83
  5014.8  159.80  5015.3  159.30  5021.3  159.30  5021.8  159.80  5042.4  159.84
  5083.0  160.21  5221.8  162.01  5263.0  162.51  5350.4  163.48  5439.1  164.83
  5446.5  164.96  5568.6  167.16  5608.8  167.95  5695.9  169.38  5760.5  170.07
#Mann=10,-1,0
  4407.0    0.12       0  4854.5   0.013       0  4868.6    0.12       0
  5014.8    0.05       0  5021.8    0.12       0  5221.8    0.05       0
  5263.0    0.12       0  5439.1    0.05       0  5446.5    0.12       0
  5568.6    0.05       0
Bank Sta=5014.8,5021.8
Exp/Cntr=0.3,0.1

Type RM Length L Ch R = 1,9184,475,475,475
BEGIN DESCRIPTION:
TRIB 3 TO TWELVEMILE CREEK 10.0
END DESCRIPTION:
XS GIS Cut Line= 3
      2533025.04     13520974.99      2531825.00     13521175.00
      2531274.98     13522575.04
#Sta/Elev= 30
  3787.9  176.94  3815.8  176.23  3820.9  176.63  3838.6  175.69  3881.7  175.07
  3909.6  173.96  3942.5  173.79  3998.3  172.03  4003.4  172.93  4011.0  173.22
  4051.5  171.02  4076.6  171.64  4125.0  171.87  4180.8  170.15  4241.6  169.18
  4741.0  162.06  4915.8  160.22  4968.0  158.49  4968.5  157.99  4974.5  157.99
  4975.0  158.49  4977.9  158.52  5084.3  160.06  5219.4  161.57  5404.2  162.30
  5573.9  166.74  5735.1  169.59  6082.3  171.94  6301.3  173.29  6508.7  175.88
#Mann=8,-1,0
  3787.9    0.05       0  4076.6    0.12       0  4741.0    0.05       0
  4968.0    0.03       0  4975.0    0.05       0  4977.9   0.013       0
  5084.3    0.05       0  6082.3    0.04       0
Bank Sta=4968,4975
Exp/Cntr=0.3,0.1

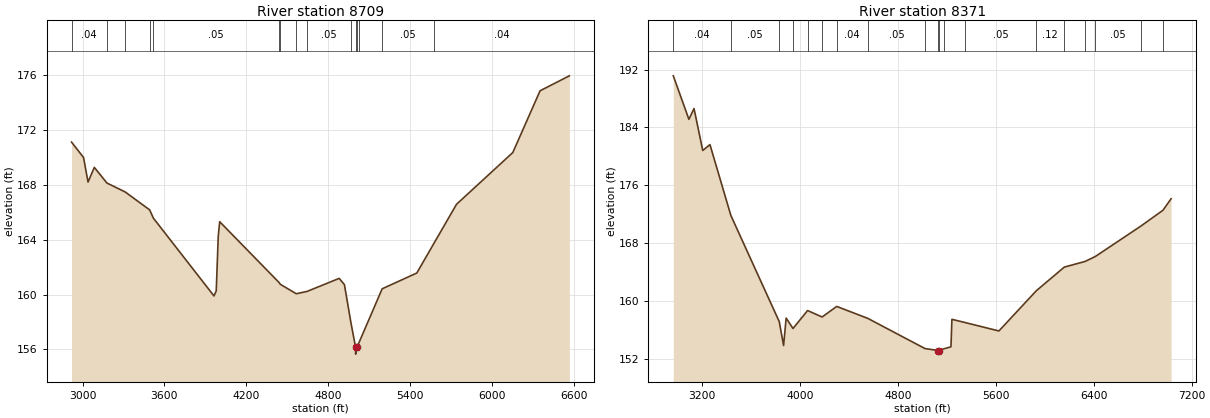
Type RM Length L Ch R = 1,8709,338,338,338
BEGIN DESCRIPTION:
TRIB 3 TO TWELVEMILE CREEK 9.0
END DESCRIPTION:
XS GIS Cut Line= 3
      2533424.97     13520425.01      2531425.00     13521025.00
      2530695.33     13522404.59
#Sta/Elev= 30
  2919.4  171.11  3007.2  169.99  3040.3  168.20  3086.4  169.27  3178.4  168.13
  3312.1  167.48  3492.1  166.17  3519.1  165.57  3963.4  159.90  3979.9  160.27
  3994.7  164.26  4005.2  165.31  4441.2  160.87  4449.3  160.75  4566.8  160.06
  4645.8  160.23  4881.3  161.18  4919.6  160.72  4968.5  157.88  5001.3  156.16
  5001.8  155.66  5008.3  156.16  5026.0  156.49  5196.1  160.42  5450.1  161.57
  5577.2  163.76  5741.2  166.58  6153.7  170.35  6353.6  174.85  6568.1  175.94
#Mann=15,-1,0
  2919.4    0.04       0  3178.4   0.013       0  3312.1    0.05       0
  3492.1   0.013       0  3519.1    0.05       0  4441.2    0.04       0
  4449.3    0.05       0  4566.8    0.04       0  4645.8    0.05       0
  4968.5    0.12       0  5001.3    0.05       0  5008.3    0.12       0
  5026.0   0.013       0  5196.1    0.05       0  5577.2    0.04       0
Bank Sta=5001.3,5008.3
Exp/Cntr=0.3,0.1

Type RM Length L Ch R = 1,8371,0,0,0
BEGIN DESCRIPTION:
Mapping XS 6ad1d7b6
END DESCRIPTION:
XS GIS Cut Line= 4
      2532626.73     13519279.64      2531682.74     13520592.55
      2530836.38     13520918.07      2530424.06     13522404.60
#Sta/Elev= 30
  2965.0  191.13  3092.5  185.12  3134.3  186.61  3205.6  180.82  3264.4  181.63
  3435.5  171.83  3830.5  157.18  3865.9  153.88  3886.8  157.67  3942.8  156.23
  4061.9  158.71  4180.9  157.82  4299.9  159.28  4554.6  157.62  5021.0  153.46
  5128.2  153.19  5128.7  152.69  5135.3  153.19  5174.2  153.42  5233.2  153.70
  5241.0  157.50  5346.9  157.06  5625.0  155.89  5930.8  161.45  6159.3  164.71
  6328.6  165.49  6412.1  166.17  6786.7  170.40  6964.9  172.56  7031.5  174.15
#Mann=19,-1,0
  2965.0    0.04       0  3435.5    0.05       0  3830.5    0.12       0
  3942.8    0.05       0  4061.9    0.04       0  4180.9   0.013       0
  4299.9    0.04       0  4554.6    0.05       0  5021.0    0.12       0
  5128.2    0.05       0  5135.3    0.12       0  5174.2   0.013       0
  5346.9    0.05       0  5930.8    0.12       0  6159.3    0.05       0
  6328.6    0.12       0  6412.1    0.05       0  6786.7    0.04       0
  6964.9   0.013       0
Bank Sta=5128.2,5135.3
Exp/Cntr=0.3,0.1

Chan Stop Cuts=-1