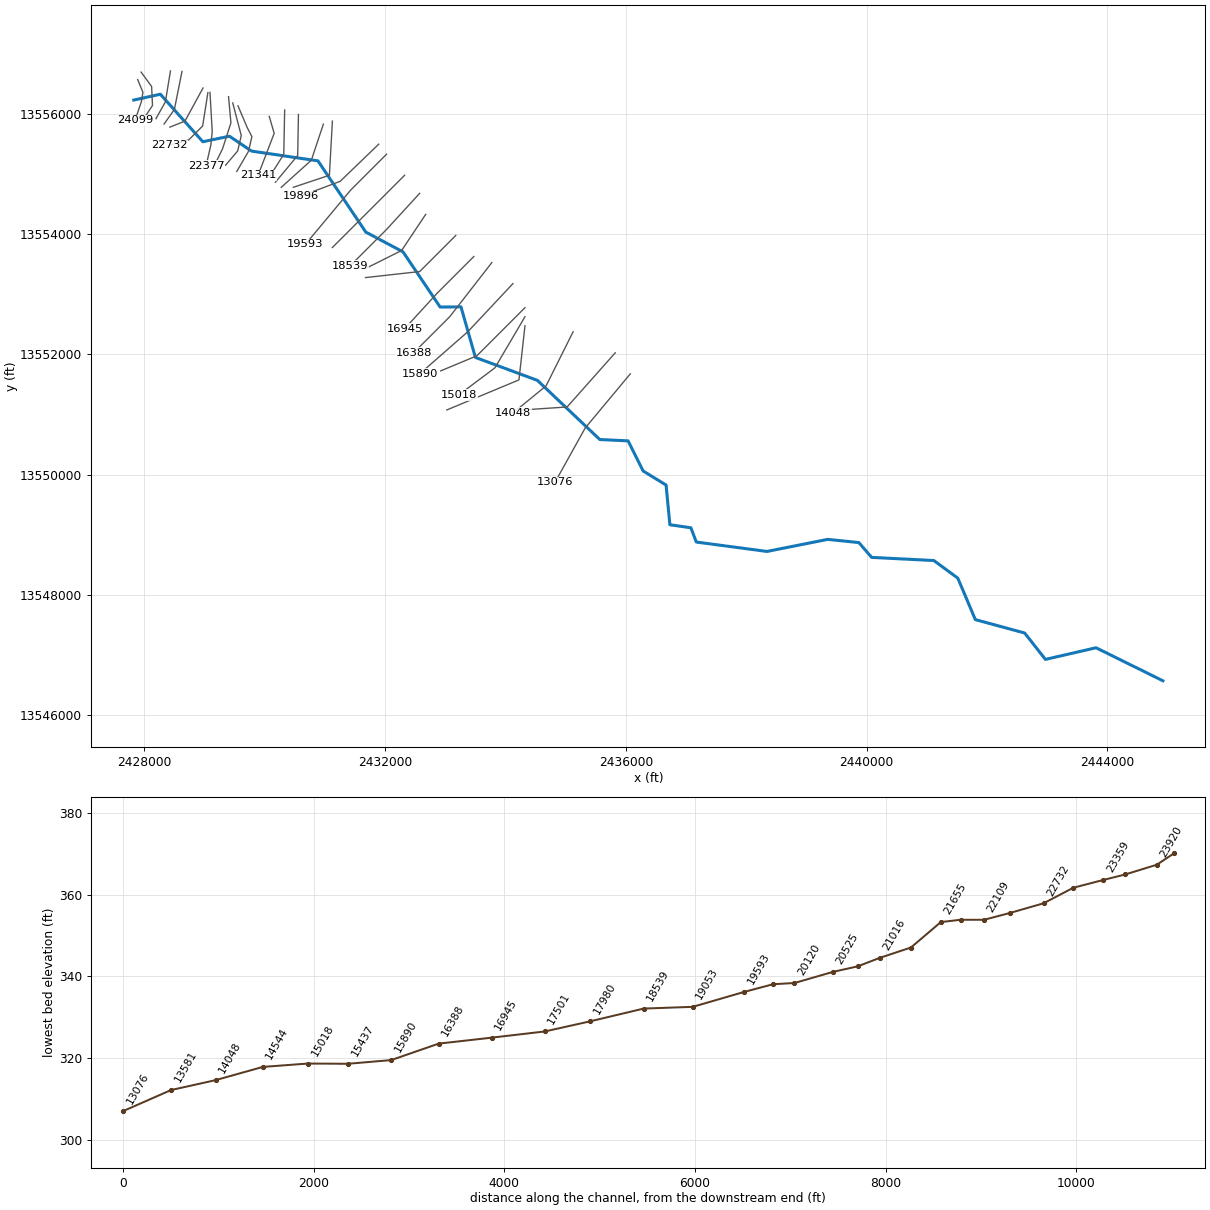
--- TRIB 3 TO YORKTOWN CREEK.prj (project) ---

Proj Title=TRIB 3 TO YORKTOWN CREEK Base Level Engineering
Current Plan=p01
Default Exp/Contr=0.3,0.1
English Units
Geom File=g01
Flow File=f01
Plan File=p01
BEGIN DESCRIPTION:
TRIB 3 TO YORKTOWN CREEK
END DESCRIPTION:

--- TRIB 3 TO YORKTOWN CREEK.p01 (plan) ---

Plan Title=Multiple Run
Short Identifier=Multiple
Geom File=g01
Flow File=f01
Subcritical Flow
K Sum by GR= 0
Std Step Tol= 0.01
Critical Tol= 0.01
Num of Std Step Trials= 20
Max Error Tol= 0.3
Flow Tol Ratio= 0.001
Split Flow NTrial= 30
Split Flow Tol= 0.02
Split Flow Ratio= 0.02
Log Output Level= 0
Friction Slope Method= 1
Unsteady Friction Slope Method= 2
Unsteady Bridges Friction Slope Method= 1
Parabolic Critical Depth
Global Vel Dist=  1 , 1 , 1
Global Log Level= 0
CheckData=True
Encroach Param= -1, 0, 0, 0
BEGIN DESCRIPTION:
Multiple Run
END DESCRIPTION:

--- TRIB 3 TO YORKTOWN CREEK.f01 (steady flow) ---

Flow Title=Multiple
Number of Profiles=7
Profile Names=10-year,25-year,50-year,1pct_min,100-year,1pct_plu,500-year
River Rch & RM= TRIB 3 TO YORKTO,Reach-1,24099
     243     371     480     303     604    1205     944
River Rch & RM= TRIB 3 TO YORKTO,Reach-1,22377
     429     681     904     583    1164    2323    1908
River Rch & RM= TRIB 3 TO YORKTO,Reach-1,20120
     651    1058    1427     933    1862    3715    3138
River Rch & RM= TRIB 3 TO YORKTO,Reach-1,16945
     878    1449    1977    1305    2604    5196    4479
River Rch & RM= TRIB 3 TO YORKTO,Reach-1,15437
    1017    1689    2312    1530    3053    6092    5281
River Rch & RM= TRIB 3 TO YORKTO,Reach-1,10408
    1826    3109    4325    2903    5791   11555   10289
River Rch & RM= TRIB 3 TO YORKTO,Reach-1,5360
    1886    3216    4481    3010    6006   11984   10695
River Rch & RM= TRIB 3 TO YORKTO,Reach-1,3283
    2240    3846    5383    3631    7245   14456   13008
Boundary for River Rch & Prof#=TRIB 3 TO YORKTO,Reach-1,1
Up Type=0
Dn Type=3
Dn Slope=0.005
Boundary for River Rch & Prof#=TRIB 3 TO YORKTO,Reach-1,2
Up Type=0
Dn Type=3
Dn Slope=0.005
Boundary for River Rch & Prof#=TRIB 3 TO YORKTO,Reach-1,3
Up Type=0
Dn Type=3
Dn Slope=0.005
Boundary for River Rch & Prof#=TRIB 3 TO YORKTO,Reach-1,4
Up Type=0
Dn Type=3
Dn Slope=0.005
Boundary for River Rch & Prof#=TRIB 3 TO YORKTO,Reach-1,5
Up Type=0
Dn Type=3
Dn Slope=0.005
Boundary for River Rch & Prof#=TRIB 3 TO YORKTO,Reach-1,6
Up Type=0
Dn Type=3
Dn Slope=0.005
Boundary for River Rch & Prof#=TRIB 3 TO YORKTO,Reach-1,7
Up Type=0
Dn Type=3
Dn Slope=0.005

--- TRIB 3 TO YORKTOWN CREEK.g01 (geometry) ---

Geom Title=Existing Conditions

River Reach=TRIB 3 TO YORKTO,Reach-1
Reach XY= 30
      2427825.00     13556225.00      2428266.54     13556321.50
      2428971.33     13555532.69      2429414.50     13555623.78
      2429780.86     13555377.07      2430884.81     13555214.49
      2431680.25     13554030.44      2432298.83     13553702.01
      2432915.32     13552785.17      2433261.55     13552788.63
      2433501.14     13551948.06      2434531.19     13551567.19
      2435568.29     13550584.16      2436038.34     13550561.59
      2436288.26     13550061.35      2436669.64     13549827.70
      2436732.62     13549168.49      2437081.80     13549117.14
      2437172.30     13548880.36      2438345.17     13548724.54
      2439354.97     13548924.94      2439873.28     13548871.66
      2440085.30     13548625.59      2441118.95     13548573.33
      2441516.86     13548281.06      2441808.33     13547591.65
      2442627.55     13547369.27      2442972.55     13546930.46
      2443814.45     13547123.91      2444925.00     13546575.00

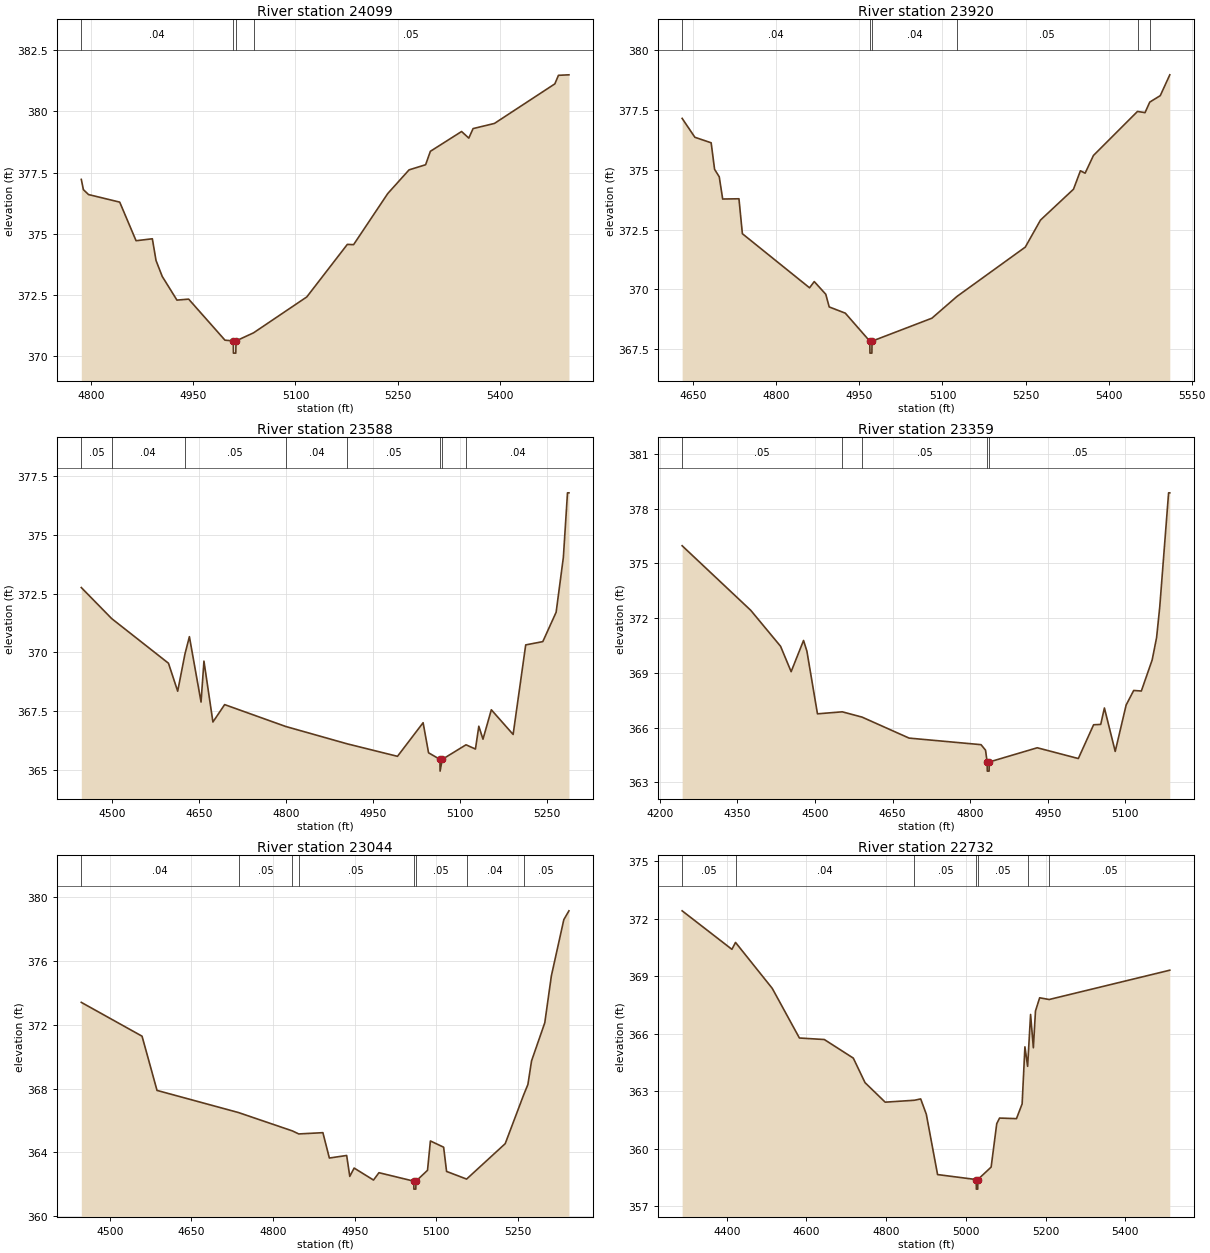
Type RM Length L Ch R = 1,24099,179,179,179
BEGIN DESCRIPTION:
Mapping XS 3013f516
END DESCRIPTION:
XS GIS Cut Line= 4
      2427889.61     13556564.83      2427976.66     13556353.44
      2427949.30     13556191.78      2427844.85     13555885.89
#Sta/Elev= 30
  4785.6  377.22  4788.7  376.80  4796.2  376.60  4842.0  376.29  4866.0  374.71
  4889.9  374.79  4895.3  373.90  4904.4  373.25  4926.0  372.28  4943.2  372.32
  4996.5  370.64  5008.7  370.61  5008.9  370.11  5012.4  370.11  5012.7  370.61
  5038.4  370.94  5116.6  372.41  5176.1  374.56  5185.3  374.55  5235.4  376.64
  5266.7  377.61  5291.0  377.82  5298.0  378.37  5343.8  379.18  5354.4  378.91
  5360.7  379.30  5392.0  379.51  5480.7  381.13  5486.0  381.48  5501.4  381.50
#Mann=4,-1,0
  4785.6    0.04       0  5008.7    0.04       0  5012.7    0.04       0
  5038.4    0.05       0
Bank Sta=5008.7,5012.7
Exp/Cntr=0.3,0.1

Type RM Length L Ch R = 1,23920,332,332,332
BEGIN DESCRIPTION:
Mapping XS e10c8d0b
END DESCRIPTION:
XS GIS Cut Line= 4
      2427946.83     13556689.16      2428120.90     13556450.43
      2428135.82     13556134.58      2427986.58     13555910.72
#Sta/Elev= 30
  4629.8  377.15  4652.8  376.36  4682.2  376.13  4688.4  375.02  4696.8  374.71
  4703.0  373.78  4732.4  373.79  4738.6  372.33  4859.9  370.07  4868.4  370.33
  4889.2  369.80  4895.4  369.27  4924.5  369.01  4968.7  367.84  4969.0  367.34
  4972.5  367.34  4972.7  367.84  5080.9  368.80  5126.2  369.71  5249.5  371.77
  5277.0  372.90  5336.6  374.19  5349.1  374.96  5357.6  374.86  5372.6  375.60
  5452.2  377.44  5465.8  377.39  5474.3  377.83  5493.3  378.10  5510.5  378.97
#Mann=6,-1,0
  4629.8    0.04       0  4968.7    0.04       0  4972.7    0.04       0
  5126.2    0.05       0  5452.2    0.04       0  5474.3    0.05       0
Bank Sta=4968.7,4972.7
Exp/Cntr=0.3,0.1

Type RM Length L Ch R = 1,23588,229,229,229
BEGIN DESCRIPTION:
Mapping XS bebe33ce
END DESCRIPTION:
XS GIS Cut Line= 3
      2428434.26     13556709.08      2428349.70     13556194.27
      2428193.01     13555915.72
#Sta/Elev= 30
  4447.2  372.76  4499.6  371.44  4597.6  369.54  4613.5  368.35  4626.0  369.93
  4633.7  370.67  4653.8  367.89  4658.8  369.63  4674.3  367.04  4694.5  367.78
  4799.8  366.85  4906.1  366.11  4992.7  365.58  5036.9  367.01  5046.3  365.73
  5065.9  365.45  5066.2  364.95  5069.9  365.45  5110.9  366.07  5127.2  365.89
  5133.0  366.86  5140.2  366.31  5154.6  367.56  5192.2  366.51  5213.9  370.32
  5243.4  370.46  5266.4  371.71  5278.9  374.05  5286.0  376.79  5288.5  376.79
#Mann=8,-1,0
  4447.2    0.05       0  4499.6    0.04       0  4626.0    0.05       0
  4799.8    0.04       0  4906.1    0.05       0  5065.9    0.05       0
  5069.9    0.05       0  5110.9    0.04       0
Bank Sta=5065.9,5069.9
Exp/Cntr=0.3,0.1

Type RM Length L Ch R = 1,23359,315,315,315
BEGIN DESCRIPTION:
Mapping XS 6d027c2b
END DESCRIPTION:
XS GIS Cut Line= 3
      2428625.74     13556701.56      2428498.92     13556067.44
      2428327.33     13555826.22
#Sta/Elev= 30
  4243.1  375.96  4375.8  372.42  4433.4  370.45  4453.8  369.06  4477.8  370.77
  4484.3  370.18  4504.7  366.75  4552.7  366.86  4590.9  366.57  4681.8  365.42
  4820.9  365.06  4829.6  364.76  4832.7  364.11  4833.0  363.61  4836.5  363.61
  4836.7  364.11  4929.6  364.89  5009.0  364.30  5038.5  366.15  5052.3  366.17
  5059.4  367.07  5080.3  364.69  5101.4  367.23  5116.0  368.03  5130.8  368.00
  5151.7  369.70  5160.3  370.93  5166.4  372.61  5183.5  378.86  5185.8  378.86
#Mann=5,-1,0
  4243.1    0.05       0  4552.7    0.04       0  4590.9    0.05       0
  4832.7    0.05       0  4836.7    0.05       0
Bank Sta=4832.7,4836.7
Exp/Cntr=0.3,0.1

Type RM Length L Ch R = 1,23044,312,312,312
BEGIN DESCRIPTION:
TRIB 3 TO YORKTOWN CREEK 43.0
END DESCRIPTION:
XS GIS Cut Line= 3
      2428975.02     13556425.04      2428675.00     13555875.00
      2428425.00     13555775.00
#Sta/Elev= 30
  4447.8  373.41  4559.4  371.29  4586.9  367.89  4736.7  366.50  4835.6  365.35
  4847.3  365.16  4891.6  365.24  4903.5  363.65  4935.3  363.81  4941.0  362.50
  4949.0  363.02  4984.6  362.27  4994.6  362.73  5058.6  362.20  5058.8  361.70
  5062.3  361.70  5062.6  362.20  5083.8  362.88  5089.1  364.72  5113.4  364.33
  5118.8  362.81  5155.6  362.33  5226.5  364.55  5260.4  367.61  5268.2  368.26
  5274.9  369.74  5299.2  372.13  5311.3  375.07  5334.2  378.60  5343.6  379.15
#Mann=8,-1,0
  4447.8    0.04       0  4736.7    0.05       0  4835.6    0.04       0
  4847.3    0.05       0  5058.6    0.05       0  5062.6    0.05       0
  5155.6    0.04       0  5260.4    0.05       0
Bank Sta=5058.6,5062.6
Exp/Cntr=0.3,0.1

Type RM Length L Ch R = 1,22732,355,355,355
BEGIN DESCRIPTION:
Mapping XS b80e8a15
END DESCRIPTION:
XS GIS Cut Line= 4
      2429055.99     13556348.43      2428968.95     13555793.87
      2428737.67     13555562.58      2428414.37     13555473.05
#Sta/Elev= 30
  4287.9  372.42  4412.8  370.41  4421.9  370.77  4514.1  368.37  4582.2  365.78
  4644.8  365.70  4717.5  364.73  4746.9  363.45  4797.5  362.43  4870.9  362.53
  4886.6  362.60  4900.7  361.80  4929.0  358.65  5026.0  358.39  5026.3  357.89
  5029.8  357.89  5030.0  358.39  5063.4  359.04  5077.5  361.31  5084.6  361.60
  5127.0  361.57  5141.2  362.34  5148.2  365.32  5155.0  364.30  5162.4  367.01
  5169.4  365.27  5174.7  367.19  5185.2  367.88  5209.0  367.79  5511.8  369.32
#Mann=7,-1,0
  4287.9    0.05       0  4421.9    0.04       0  4870.9    0.05       0
  5026.0    0.05       0  5030.0    0.05       0  5155.0    0.04       0
  5209.0    0.05       0
Bank Sta=5026,5030
Exp/Cntr=0.3,0.1

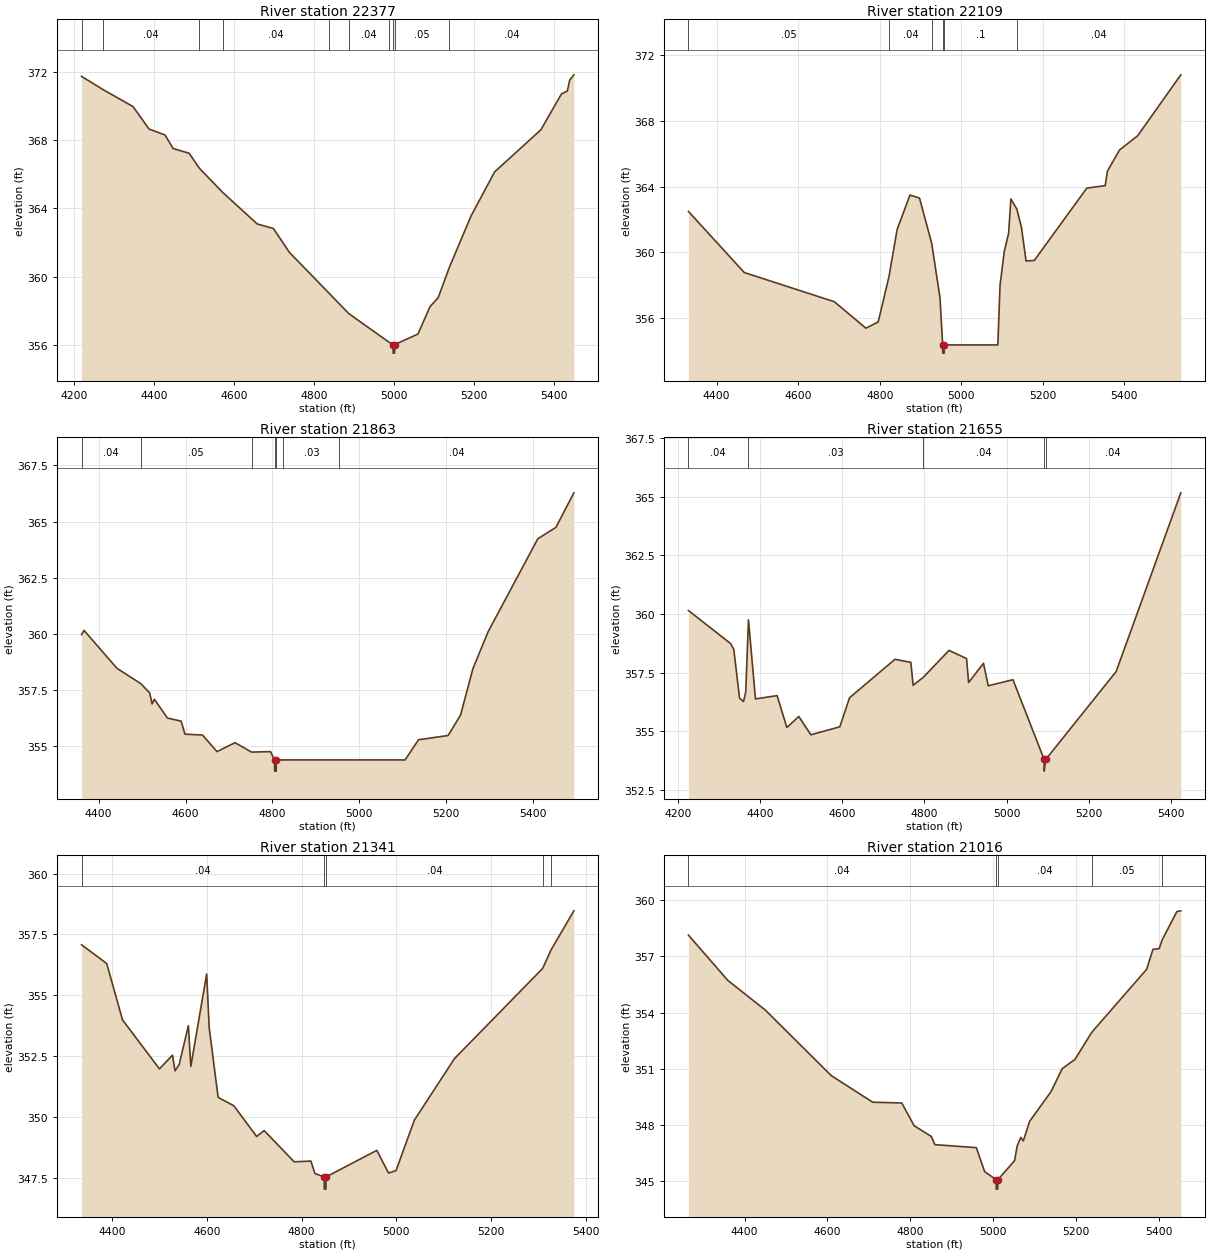
Type RM Length L Ch R = 1,22377,268,268,268
BEGIN DESCRIPTION:
Mapping XS d80e6edb
END DESCRIPTION:
XS GIS Cut Line= 4
      2429090.82     13556353.39      2429128.12     13555701.85
      2429105.74     13555480.51      2429026.16     13555134.83
#Sta/Elev= 30
  4219.7  371.74  4273.0  370.97  4348.3  369.97  4388.4  368.65  4428.4  368.30
  4448.5  367.51  4488.5  367.23  4514.2  366.35  4572.5  364.93  4658.8  363.08
  4698.9  362.82  4738.9  361.42  4838.9  359.00  4887.2  357.83  4986.6  356.17
  4997.8  356.01  4998.1  355.51  5001.6  355.51  5001.8  356.01  5060.1  356.63
  5090.0  358.23  5110.7  358.77  5138.5  360.54  5192.8  363.56  5251.6  366.14
  5367.2  368.61  5418.5  370.71  5433.1  370.88  5439.1  371.52  5449.5  371.83
#Mann=10,-1,0
  4219.7    0.05       0  4273.0    0.04       0  4514.2    0.05       0
  4572.5    0.04       0  4838.9    0.05       0  4887.2    0.04       0
  4986.6    0.05       0  4997.8    0.05       0  5001.8    0.05       0
  5138.5    0.04       0
Bank Sta=4997.8,5001.8
Exp/Cntr=0.3,0.1

Type RM Length L Ch R = 1,22109,246,246,246
BEGIN DESCRIPTION:
Mapping XS ef6670d5
END DESCRIPTION:
XS GIS Cut Line= 4
      2429399.20     13556281.27      2429438.99     13555846.10
      2429299.72     13555415.85      2429160.50     13555129.96
#Sta/Elev= 30
  4331.0  362.49  4467.8  358.77  4688.8  356.99  4766.0  355.38  4796.3  355.76
  4822.7  358.52  4842.7  361.39  4874.2  363.49  4897.6  363.30  4927.3  360.56
  4947.8  357.23  4954.3  354.36  4954.6  353.86  4958.1  353.86  4958.3  354.36
  5089.6  354.36  5095.0  358.00  5105.5  360.07  5116.0  361.15  5121.6  363.25
  5136.4  362.62  5147.5  361.52  5158.8  359.47  5179.1  359.51  5307.8  363.91
  5352.8  364.06  5358.4  364.95  5388.0  366.23  5432.5  367.10  5538.2  370.81
#Mann=6,-1,0
  4331.0    0.05       0  4822.7    0.04       0  4927.3     0.1       0
  4954.3    0.05       0  4958.3     0.1       0  5136.4    0.04       0
Bank Sta=4954.3,4958.3
Exp/Cntr=0.3,0.1

Type RM Length L Ch R = 1,21863,208,208,208
BEGIN DESCRIPTION:
Mapping XS c8e5f42a
END DESCRIPTION:
XS GIS Cut Line= 4
      2429468.85     13556176.82      2429610.59     13555634.70
      2429550.90     13555378.55      2429349.75     13555142.62
#Sta/Elev= 30
  4360.6  359.95  4366.4  360.14  4442.1  358.45  4497.3  357.76  4517.5  357.35
  4523.0  356.86  4528.2  357.07  4558.3  356.23  4589.9  356.09  4598.7  355.51
  4639.1  355.47  4672.6  354.73  4713.9  355.13  4751.9  354.71  4795.7  354.73
  4804.9  354.36  4805.2  353.86  4808.7  353.86  4808.9  354.36  4825.1  354.36
  4954.4  354.36  5105.5  354.36  5136.3  355.26  5204.6  355.45  5233.1  356.36
  5261.7  358.44  5296.8  360.09  5411.0  364.23  5452.7  364.74  5494.0  366.28
#Mann=7,-1,0
  4360.6    0.04       0  4497.3    0.05       0  4751.9    0.04       0
  4804.9    0.04       0  4808.9    0.04       0  4825.1    0.03       0
  4954.4    0.04       0
Bank Sta=4804.9,4808.9
Exp/Cntr=0.3,0.1

Type RM Length L Ch R = 1,21655,314,314,314
BEGIN DESCRIPTION:
Mapping XS 14f7d5eb
END DESCRIPTION:
XS GIS Cut Line= 5
      2429555.89     13556129.58      2429710.07     13555766.51
      2429787.17     13555617.30      2429729.97     13555371.09
      2429536.62     13555038.93
#Sta/Elev= 30
  4225.1  360.15  4327.9  358.74  4335.6  358.49  4349.6  356.41  4359.3  356.27
  4364.7  356.68  4369.5  358.91  4371.3  359.75  4388.4  356.38  4441.1  356.52
  4464.8  355.16  4493.9  355.63  4523.4  354.85  4593.9  355.19  4617.6  356.43
  4728.3  358.07  4766.9  357.94  4772.5  356.96  4797.7  357.31  4860.0  358.45
  4902.6  358.10  4907.7  357.08  4943.9  357.90  4955.5  356.94  5015.7  357.20
  5091.6  353.80  5091.8  353.30  5095.6  353.80  5267.2  357.55  5424.6  365.17
#Mann=5,-1,0
  4225.1    0.04       0  4369.5    0.03       0  4797.7    0.04       0
  5091.6    0.04       0  5095.6    0.04       0
Bank Sta=5091.6,5095.6
Exp/Cntr=0.3,0.1

Type RM Length L Ch R = 1,21341,325,325,325
BEGIN DESCRIPTION:
Mapping XS a3a8cf54
END DESCRIPTION:
XS GIS Cut Line= 3
      2430075.66     13555953.01      2430157.72     13555672.01
      2429889.57     13554974.30
#Sta/Elev= 30
  4335.0  357.08  4388.2  356.31  4421.6  354.00  4499.6  351.99  4527.2  352.55
  4532.5  351.91  4541.3  352.17  4560.7  353.76  4565.9  352.09  4599.4  355.88
  4604.6  353.70  4623.6  350.82  4656.7  350.48  4704.9  349.22  4720.9  349.46
  4784.3  348.18  4819.6  348.21  4828.1  347.70  4847.6  347.56  4847.9  347.06
  4851.4  347.06  4851.6  347.56  4958.9  348.65  4983.6  347.72  4999.5  347.82
  5038.2  349.89  5122.9  352.41  5309.3  356.11  5326.8  356.86  5375.2  358.47
#Mann=5,-1,0
  4335.0    0.04       0  4847.6    0.04       0  4851.6    0.04       0
  5309.3    0.05       0  5326.8    0.12       0
Bank Sta=4847.6,4851.6
Exp/Cntr=0.3,0.1

Type RM Length L Ch R = 1,21016,232,232,232
BEGIN DESCRIPTION:
Mapping XS 28d857e3
END DESCRIPTION:
XS GIS Cut Line= 3
      2430331.81     13556060.02      2430316.89     13555323.83
      2430075.64     13554940.81
#Sta/Elev= 30
  4264.4  358.14  4359.4  355.72  4449.5  354.14  4609.5  350.62  4709.5  349.20
  4779.5  349.16  4809.5  347.94  4850.9  347.37  4859.5  346.93  4959.6  346.77
  4979.6  345.49  5007.5  345.05  5007.7  344.55  5011.2  344.55  5011.5  345.05
  5051.9  346.07  5058.4  346.87  5067.2  347.32  5073.1  347.13  5088.4  348.18
  5140.1  349.77  5167.2  351.00  5197.8  351.49  5238.4  352.94  5370.9  356.31
  5386.2  357.38  5401.2  357.42  5408.5  357.89  5443.9  359.40  5453.4  359.44
#Mann=5,-1,0
  4264.4    0.04       0  5007.5    0.04       0  5011.5    0.04       0
  5238.4    0.05       0  5408.5    0.12       0
Bank Sta=5007.5,5011.5
Exp/Cntr=0.3,0.1

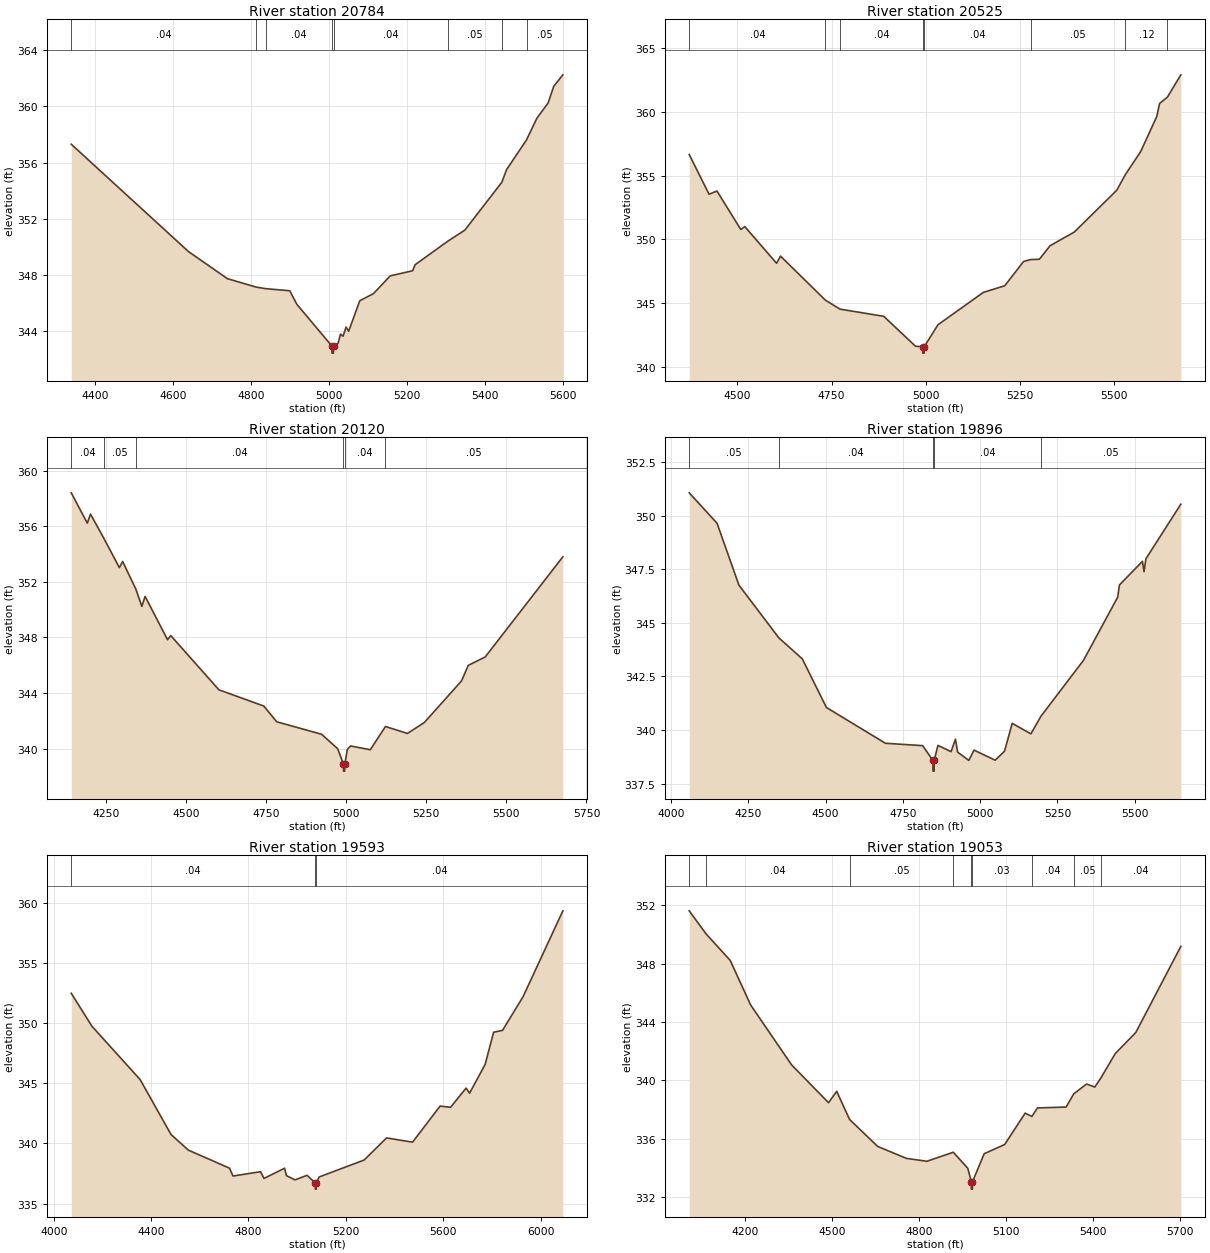
Type RM Length L Ch R = 1,20784,259,259,259
BEGIN DESCRIPTION:
Mapping XS 69c0efc6
END DESCRIPTION:
XS GIS Cut Line= 3
      2430560.61     13555985.34      2430548.18     13555303.94
      2430177.64     13554858.79
#Sta/Elev= 30
  4339.8  357.30  4640.2  349.68  4740.2  347.75  4814.2  347.15  4838.4  347.04
  4900.2  346.89  4918.3  345.93  5008.3  342.96  5008.5  342.46  5012.0  342.46
  5012.3  342.96  5023.9  343.15  5030.3  343.81  5036.8  343.66  5044.6  344.31
  5051.1  344.01  5079.7  346.18  5114.9  346.69  5157.8  347.95  5215.1  348.31
  5221.6  348.74  5305.9  350.42  5349.2  351.20  5444.0  354.60  5456.0  355.49
  5507.3  357.61  5534.1  359.16  5562.7  360.23  5577.0  361.41  5600.5  362.23
#Mann=8,-1,0
  4339.8    0.04       0  4814.2    0.05       0  4838.4    0.04       0
  5008.3    0.04       0  5012.3    0.04       0  5305.9    0.05       0
  5444.0    0.12       0  5507.3    0.05       0
Bank Sta=5008.3,5012.3
Exp/Cntr=0.3,0.1

Type RM Length L Ch R = 1,20525,405,405,405
BEGIN DESCRIPTION:
TRIB 3 TO YORKTOWN CREEK 38.0
END DESCRIPTION:
XS GIS Cut Line= 3
      2430974.98     13555824.95      2430775.00     13555225.00
      2430274.99     13554774.99
#Sta/Elev= 30
  4371.8  356.65  4424.5  353.54  4445.5  353.79  4508.8  350.78  4519.3  351.01
  4603.7  348.14  4614.2  348.70  4733.5  345.25  4772.3  344.55  4888.3  343.99
  4972.6  341.65  4991.7  341.61  4991.9  341.11  4995.4  341.11  4995.7  341.61
  5032.2  343.33  5152.6  345.86  5209.4  346.38  5259.5  348.28  5278.5  348.43
  5301.3  348.45  5329.7  349.51  5394.0  350.58  5506.8  353.85  5529.7  355.08
  5570.4  356.88  5613.0  359.62  5620.5  360.64  5641.4  361.14  5676.9  362.88
#Mann=8,-1,0
  4371.8    0.04       0  4733.5    0.05       0  4772.3    0.04       0
  4991.7    0.04       0  4995.7    0.04       0  5278.5    0.05       0
  5529.7    0.12       0  5641.4    0.05       0
Bank Sta=4991.7,4995.7
Exp/Cntr=0.3,0.1

Type RM Length L Ch R = 1,20120,224,224,224
BEGIN DESCRIPTION:
TRIB 3 TO YORKTOWN CREEK 37.0
END DESCRIPTION:
XS GIS Cut Line= 3
      2431125.00     13555875.00      2431075.00     13554975.00
      2430475.05     13554775.02
#Sta/Elev= 30
  4142.7  358.40  4192.8  356.22  4202.8  356.87  4244.4  355.13  4292.9  353.02
  4303.0  353.46  4344.2  351.48  4363.0  350.23  4373.1  350.95  4443.2  347.83
  4453.2  348.13  4603.4  344.23  4743.6  343.06  4783.7  341.93  4923.9  341.03
  4974.0  339.99  4992.0  338.88  4992.3  338.38  4995.8  338.38  4996.0  338.88
  5004.0  339.93  5014.0  340.19  5075.7  339.92  5123.0  341.59  5191.7  341.09
  5244.4  341.88  5360.3  344.87  5381.4  345.99  5434.1  346.59  5676.5  353.80
#Mann=6,-1,0
  4142.7    0.04       0  4244.4    0.05       0  4344.2    0.04       0
  4992.0    0.04       0  4996.0    0.04       0  5123.0    0.05       0
Bank Sta=4992,4996
Exp/Cntr=0.3,0.1

Type RM Length L Ch R = 1,19896,303,303,303
BEGIN DESCRIPTION:
Mapping XS de70d0ec
END DESCRIPTION:
XS GIS Cut Line= 3
      2431895.27     13555492.09      2431254.67     13554874.93
      2430599.22     13554627.84
#Sta/Elev= 30
  4058.9  351.07  4149.0  349.65  4219.7  346.76  4348.9  344.30  4424.7  343.32
  4502.7  341.05  4693.6  339.38  4813.7  339.27  4847.2  338.58  4847.5  338.08
  4851.0  338.08  4851.2  338.58  4863.4  339.28  4905.8  338.99  4920.0  339.57
  4926.9  338.97  4963.3  338.58  4980.1  339.06  5048.5  338.59  5078.7  339.01
  5103.6  340.31  5164.0  339.82  5196.9  340.65  5334.5  343.26  5444.7  346.20
  5450.4  346.77  5524.6  347.87  5529.9  347.39  5535.9  347.99  5648.9  350.54
#Mann=5,-1,0
  4058.9    0.05       0  4348.9    0.04       0  4847.2    0.04       0
  4851.2    0.04       0  5196.9    0.05       0
Bank Sta=4847.2,4851.2
Exp/Cntr=0.3,0.1

Type RM Length L Ch R = 1,19593,540,540,540
BEGIN DESCRIPTION:
TRIB 3 TO YORKTOWN CREEK 36.0
END DESCRIPTION:
XS GIS Cut Line= 3
      2432025.02     13555325.02      2431425.00     13554725.00
      2430675.00     13553825.00
#Sta/Elev= 30
  4071.8  352.50  4156.7  349.76  4354.7  345.32  4482.0  340.74  4552.7  339.45
  4722.4  337.94  4736.5  337.29  4849.7  337.65  4863.8  337.09  4948.3  337.94
  4956.2  337.32  4991.3  336.97  5040.8  337.35  5074.6  336.70  5074.8  336.20
  5078.3  336.20  5078.6  336.70  5090.2  337.21  5275.1  338.62  5367.5  340.46
  5474.2  340.11  5587.5  343.11  5630.4  343.01  5694.2  344.61  5708.5  344.18
  5772.3  346.57  5807.5  349.26  5843.9  349.41  5928.5  352.22  6091.9  359.36
#Mann=3,-1,0
  4071.8    0.04       0  5074.6    0.04       0  5078.6    0.04       0
Bank Sta=5074.6,5078.6
Exp/Cntr=0.3,0.1

Type RM Length L Ch R = 1,19053,514,514,514
BEGIN DESCRIPTION:
TRIB 3 TO YORKTOWN CREEK 35.0
END DESCRIPTION:
XS GIS Cut Line= 3
      2432325.03     13554975.03      2431725.00     13554375.00
      2431125.00     13553775.00
#Sta/Elev= 30
  4005.8  351.63  4063.6  350.06  4147.3  348.23  4218.0  345.17  4359.4  341.06
  4486.7  338.47  4515.0  339.25  4559.4  337.32  4656.4  335.47  4755.4  334.65
  4826.1  334.45  4917.5  335.07  4967.5  333.97  4979.7  333.04  4979.9  332.54
  4983.4  332.54  4983.7  333.04  5024.1  334.97  5094.8  335.60  5165.5  337.75
  5188.8  337.53  5207.9  338.11  5306.9  338.17  5333.4  339.08  5377.6  339.75
  5405.9  339.54  5427.4  340.18  5476.6  341.84  5547.3  343.28  5702.9  349.19
#Mann=9,-1,0
  4005.8    0.05       0  4063.6    0.04       0  4559.4    0.05       0
  4917.5    0.03       0  4979.7    0.03       0  4983.7    0.03       0
  5188.8    0.04       0  5333.4    0.05       0  5427.4    0.04       0
Bank Sta=4979.7,4983.7
Exp/Cntr=0.3,0.1

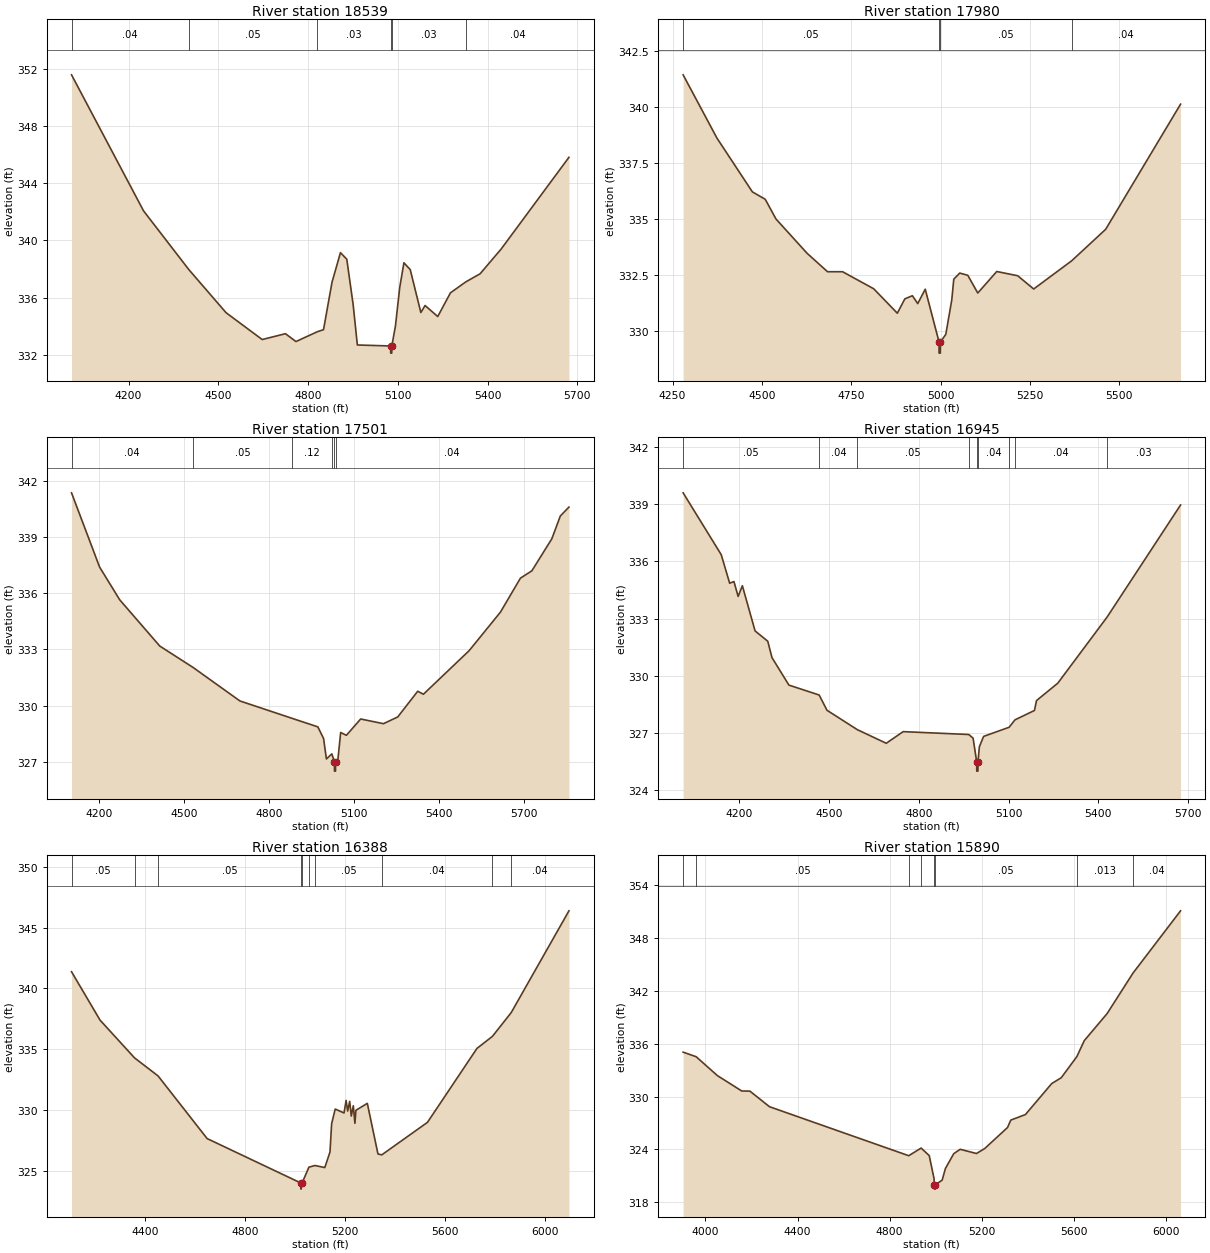
Type RM Length L Ch R = 1,18539,559,559,559
BEGIN DESCRIPTION:
TRIB 3 TO YORKTOWN CREEK 34.0
END DESCRIPTION:
XS GIS Cut Line= 3
      2432574.99     13554674.99      2432025.00     13554075.00
      2431424.97     13553474.97
#Sta/Elev= 30
  4009.3  351.59  4250.1  342.07  4401.5  337.96  4525.7  334.95  4646.6  333.07
  4724.3  333.48  4759.4  332.93  4830.1  333.61  4851.5  333.76  4879.8  337.07
  4908.1  339.15  4929.3  338.69  4950.5  335.52  4964.6  332.69  5075.8  332.62
  5076.0  332.12  5079.5  332.12  5079.8  332.62  5091.9  334.02  5106.1  336.70
  5120.2  338.44  5141.4  337.96  5176.8  334.96  5190.9  335.45  5233.3  334.68
  5275.8  336.34  5327.5  337.11  5374.8  337.67  5445.5  339.41  5671.8  345.82
#Mann=6,-1,0
  4009.3    0.04       0  4401.5    0.05       0  4830.1    0.03       0
  5075.8    0.03       0  5079.8    0.03       0  5327.5    0.04       0
Bank Sta=5075.8,5079.8
Exp/Cntr=0.3,0.1

Type RM Length L Ch R = 1,17980,479,479,479
BEGIN DESCRIPTION:
TRIB 3 TO YORKTOWN CREEK 33.0
END DESCRIPTION:
XS GIS Cut Line= 3
      2432674.99     13554324.99      2432275.00     13553725.00
      2431675.02     13553425.01
#Sta/Elev= 30
  4279.5  341.42  4374.1  338.60  4473.3  336.20  4509.3  335.87  4539.4  334.99
  4626.5  333.46  4683.6  332.64  4725.7  332.64  4812.8  331.88  4878.9  330.79
  4899.9  331.43  4921.0  331.57  4936.0  331.22  4957.0  331.86  4995.6  329.51
  4995.8  329.01  4999.3  329.01  4999.6  329.51  5014.6  329.85  5031.3  331.39
  5036.9  332.31  5053.7  332.58  5076.1  332.48  5104.0  331.69  5157.1  332.65
  5215.8  332.46  5260.5  331.87  5367.0  333.13  5461.8  334.53  5671.4  340.11
#Mann=4,-1,0
  4279.5    0.05       0  4995.6    0.05       0  4999.6    0.05       0
  5367.0    0.04       0
Bank Sta=4995.6,4999.6
Exp/Cntr=0.3,0.1

Type RM Length L Ch R = 1,17501,556,556,556
BEGIN DESCRIPTION:
TRIB 3 TO YORKTOWN CREEK 32.0
END DESCRIPTION:
XS GIS Cut Line= 3
      2433174.99     13553974.99      2432575.00     13553375.00
      2431674.95     13553274.99
#Sta/Elev= 30
  4102.9  341.35  4201.9  337.39  4272.6  335.65  4414.0  333.18  4531.4  332.04
  4696.9  330.25  4881.6  329.32  4971.5  328.87  4991.7  328.25  5001.7  327.16
  5020.8  327.43  5029.9  327.01  5030.2  326.51  5033.7  326.51  5033.9  327.01
  5042.0  327.09  5052.0  328.57  5072.2  328.42  5122.5  329.29  5203.0  329.04
  5253.3  329.40  5323.7  330.77  5343.8  330.61  5504.8  332.93  5615.5  334.99
  5685.9  336.80  5726.2  337.19  5796.6  338.90  5826.8  340.12  5857.0  340.59
#Mann=6,-1,0
  4102.9    0.04       0  4531.4    0.05       0  4881.6    0.12       0
  5020.8    0.04       0  5029.9    0.05       0  5033.9    0.04       0
Bank Sta=5029.9,5033.9
Exp/Cntr=0.3,0.1

Type RM Length L Ch R = 1,16945,557,557,557
BEGIN DESCRIPTION:
TRIB 3 TO YORKTOWN CREEK 31.0
END DESCRIPTION:
XS GIS Cut Line= 3
      2433475.03     13553625.03      2432875.00     13553025.00
      2432325.01     13552425.01
#Sta/Elev= 30
  4012.3  339.59  4139.6  336.35  4167.9  334.85  4182.1  334.94  4196.2  334.16
  4210.3  334.72  4252.8  332.35  4295.2  331.81  4309.3  330.95  4365.9  329.51
  4467.0  328.99  4493.2  328.19  4595.0  327.17  4691.2  326.46  4747.7  327.07
  4967.0  326.92  4981.4  326.73  4993.4  325.50  4993.7  325.00  4997.6  325.00
  4997.9  325.50  5002.4  326.28  5016.6  326.82  5101.9  327.30  5121.6  327.69
  5186.5  328.18  5193.5  328.70  5264.5  329.61  5429.5  333.08  5674.8  338.95
#Mann=9,-1,0
  4012.3    0.05       0  4467.0    0.04       0  4595.0    0.05       0
  4967.0    0.04       0  4993.4    0.04       0  4997.9    0.04       0
  5101.9    0.03       0  5121.6    0.04       0  5429.5    0.03       0
Bank Sta=4993.4,4997.9
Exp/Cntr=0.3,0.1

Type RM Length L Ch R = 1,16388,498,498,498
BEGIN DESCRIPTION:
TRIB 3 TO YORKTOWN CREEK 30.0
END DESCRIPTION:
XS GIS Cut Line= 3
      2433775.01     13553525.02      2433075.00     13552625.00
      2432475.02     13552025.02
#Sta/Elev= 30
  4106.9  341.37  4220.9  337.40  4358.9  334.30  4452.9  332.82  4649.0  327.68
  5024.0  324.03  5024.3  323.53  5028.7  324.03  5055.8  325.33  5080.0  325.47
  5119.5  325.30  5140.3  326.58  5146.7  328.89  5161.1  330.10  5196.4  329.78
  5204.6  330.81  5210.9  329.94  5219.0  330.73  5225.4  329.53  5233.5  330.37
  5239.9  328.93  5243.9  330.00  5289.5  330.57  5332.0  326.42  5347.1  326.34
  5529.9  329.01  5727.9  335.08  5789.8  336.07  5864.8  338.02  6095.6  346.37
#Mann=10,-1,0
  4106.9    0.05       0  4358.9    0.04       0  4452.9    0.05       0
  5024.0    0.05       0  5028.7    0.05       0  5055.8    0.12       0
  5080.0    0.05       0  5347.1    0.04       0  5789.8    0.03       0
  5864.8    0.04       0
Bank Sta=5024,5028.7
Exp/Cntr=0.3,0.1

Type RM Length L Ch R = 1,15890,453,453,453
BEGIN DESCRIPTION:
TRIB 3 TO YORKTOWN CREEK 29.0
END DESCRIPTION:
XS GIS Cut Line= 3
      2434124.99     13553174.99      2433375.00     13552375.00
      2432574.99     13551674.99
#Sta/Elev= 30
  3903.4  335.04  3960.0  334.52  4052.1  332.38  4158.1  330.63  4193.3  330.62
  4278.3  328.85  4883.0  323.29  4936.7  324.16  4971.9  323.30  4992.9  320.69
  4994.1  320.00  4994.4  319.50  4998.6  319.50  4999.0  320.00  5028.0  320.52
  5042.2  321.84  5078.3  323.52  5106.3  324.02  5177.0  323.54  5212.6  324.10
  5311.8  326.49  5326.0  327.33  5389.6  327.96  5503.5  331.47  5545.2  332.14
  5613.0  334.54  5644.9  336.34  5744.1  339.41  5856.7  344.01  6063.0  351.07
#Mann=8,-1,0
  3903.4    0.04       0  3960.0    0.05       0  4883.0   0.013       0
  4936.7    0.05       0  4994.1    0.05       0  4999.0    0.05       0
  5613.0   0.013       0  5856.7    0.04       0
Bank Sta=4994.1,4999
Exp/Cntr=0.3,0.1

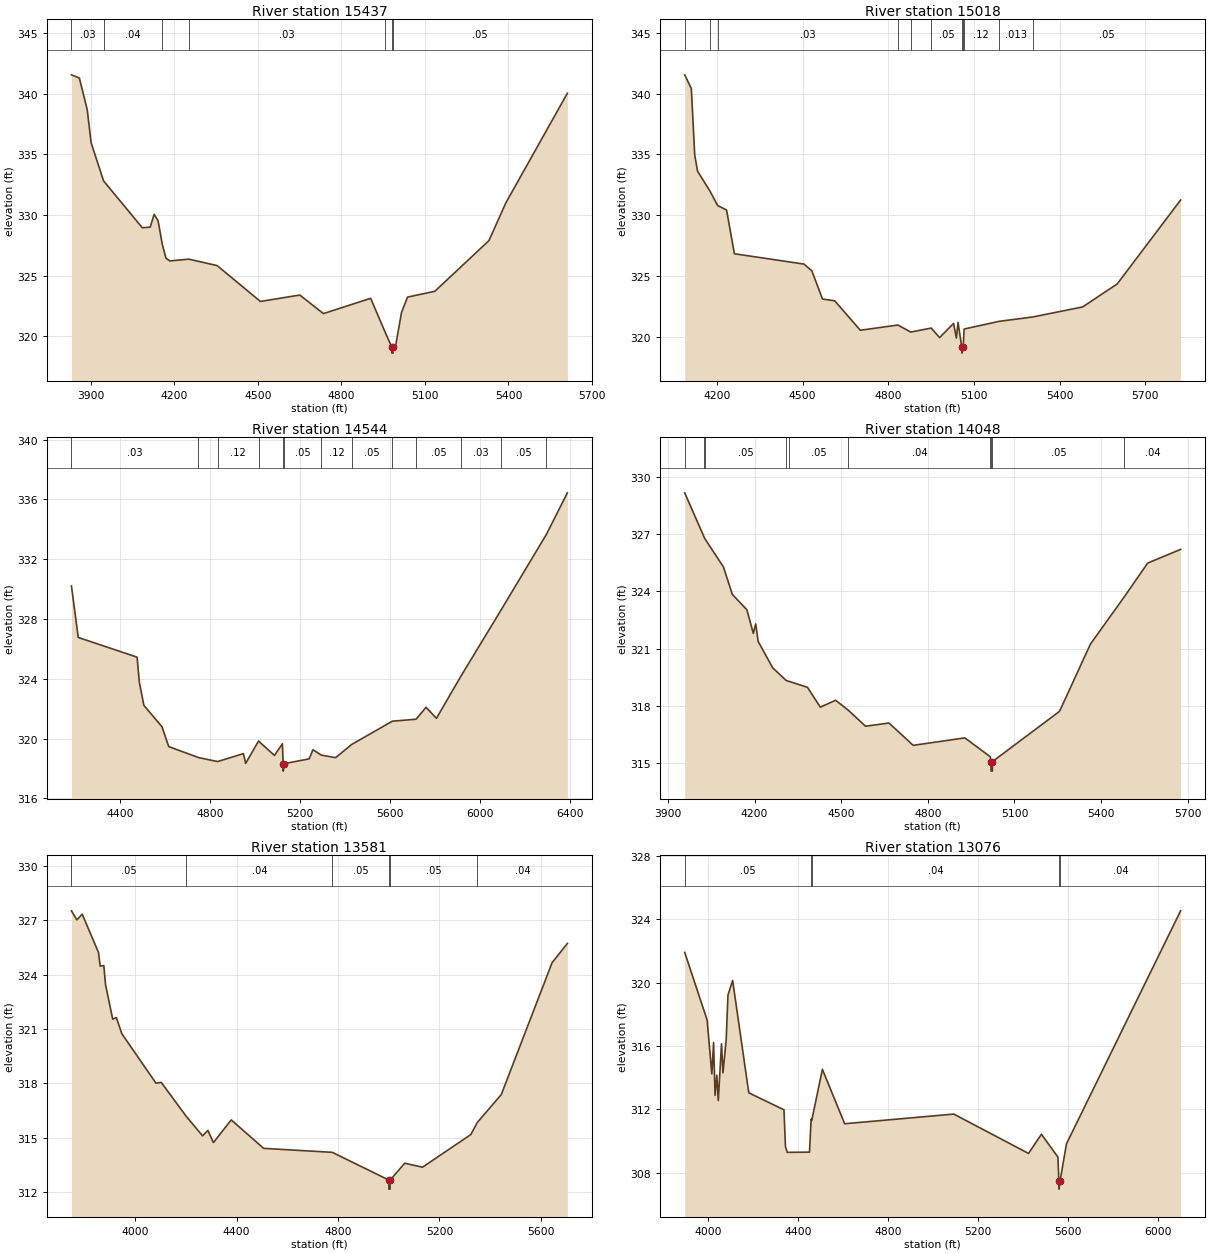
Type RM Length L Ch R = 1,15437,419,419,419
BEGIN DESCRIPTION:
TRIB 3 TO YORKTOWN CREEK 28.0
END DESCRIPTION:
XS GIS Cut Line= 3
      2434324.98     13552774.98      2433525.00     13551975.00
      2432925.05     13551725.02
#Sta/Elev= 30
  3830.3  341.55  3858.6  341.29  3886.8  338.70  3901.0  335.94  3945.7  332.80
  4084.8  328.94  4113.1  328.99  4127.3  330.04  4141.4  329.52  4156.4  327.59
  4169.7  326.43  4183.8  326.20  4252.1  326.35  4353.5  325.82  4509.1  322.86
  4650.5  323.39  4735.4  321.86  4905.1  323.12  4955.6  320.40  4980.8  319.10
  4981.2  318.60  4985.4  318.60  4985.8  319.10  4994.1  319.12  5015.8  321.95
  5037.5  323.22  5135.5  323.70  5330.0  327.88  5390.1  330.97  5611.6  340.03
#Mann=7,-1,0
  3830.3    0.03       0  3945.7    0.04       0  4156.4    0.05       0
  4252.1    0.03       0  4955.6    0.05       0  4980.8    0.05       0
  4985.8    0.05       0
Bank Sta=4980.8,4985.8
Exp/Cntr=0.3,0.1

Type RM Length L Ch R = 1,15018,474,474,474
BEGIN DESCRIPTION:
TRIB 3 TO YORKTOWN CREEK 27.0
END DESCRIPTION:
XS GIS Cut Line= 3
      2434325.01     13552625.01      2433825.00     13551775.00
      2433224.97     13551324.98
#Sta/Elev= 30
  4087.3  341.54  4110.5  340.41  4122.4  334.94  4132.3  333.62  4175.8  331.98
  4202.7  330.79  4233.8  330.43  4261.3  326.83  4505.0  325.98  4532.5  325.42
  4569.7  323.11  4612.6  322.96  4702.2  320.54  4833.7  320.97  4878.8  320.39
  4950.1  320.72  4979.8  319.94  5028.5  321.10  5038.4  319.90  5044.2  321.19
  5057.3  319.16  5057.7  318.66  5062.3  319.16  5063.7  319.79  5065.6  320.64
  5187.5  321.27  5307.8  321.64  5480.8  322.46  5601.6  324.35  5823.5  331.25
#Mann=11,-1,0
  4087.3    0.03       0  4175.8    0.04       0  4202.7    0.03       0
  4833.7    0.05       0  4878.8    0.12       0  4950.1    0.05       0
  5057.3    0.05       0  5062.3    0.05       0  5063.7    0.12       0
  5187.5   0.013       0  5307.8    0.05       0
Bank Sta=5057.3,5062.3
Exp/Cntr=0.3,0.1

Type RM Length L Ch R = 1,14544,496,496,496
BEGIN DESCRIPTION:
TRIB 3 TO YORKTOWN CREEK 26.0
END DESCRIPTION:
XS GIS Cut Line= 3
      2434325.00     13552475.02      2434225.00     13551575.00
      2433024.96     13551074.98
#Sta/Elev= 30
  4184.4  330.21  4214.6  326.77  4476.2  325.45  4486.3  323.78  4506.4  322.23
  4586.9  320.80  4617.1  319.47  4748.9  318.74  4834.2  318.47  4949.1  319.00
  4959.2  318.35  5016.4  319.84  5087.4  318.88  5122.5  319.66  5125.9  318.33
  5126.3  317.83  5130.9  318.33  5241.6  318.65  5258.4  319.26  5295.9  318.90
  5359.2  318.73  5430.4  319.61  5611.8  321.17  5717.1  321.30  5761.6  322.10
  5807.7  321.36  5915.4  324.15  6093.0  328.55  6296.3  333.65  6390.0  336.44
#Mann=13,-1,0
  4184.4    0.03       0  4748.9    0.05       0  4834.2    0.12       0
  5016.4    0.05       0  5125.9    0.05       0  5130.9    0.05       0
  5295.9    0.12       0  5430.4    0.05       0  5611.8   0.013       0
  5717.1    0.05       0  5915.4    0.03       0  6093.0    0.05       0
  6296.3    0.03       0
Bank Sta=5125.9,5130.9
Exp/Cntr=0.3,0.1

Type RM Length L Ch R = 1,14048,467,467,467
BEGIN DESCRIPTION:
TRIB 3 TO YORKTOWN CREEK 25.0
END DESCRIPTION:
XS GIS Cut Line= 3
      2435124.98     13552374.97      2434675.00     13551475.00
      2434125.02     13551025.02
#Sta/Elev= 30
  3958.3  329.16  4026.4  326.81  4030.2  326.71  4092.4  325.28  4123.2  323.84
  4173.5  323.04  4195.8  321.80  4204.2  322.30  4212.6  321.38  4262.9  320.00
  4310.0  319.33  4319.4  319.29  4383.1  318.98  4427.8  317.94  4480.9  318.30
  4525.3  317.77  4584.4  316.94  4665.4  317.11  4749.3  315.94  4928.2  316.33
  5016.4  315.34  5018.7  315.09  5019.1  314.59  5023.3  314.59  5023.7  315.09
  5255.9  317.72  5362.9  321.24  5480.3  323.72  5561.0  325.48  5675.1  326.20
#Mann=10,-1,0
  3958.3    0.05       0  4026.4    0.04       0  4030.2    0.05       0
  4310.0    0.04       0  4319.4    0.05       0  4525.3    0.04       0
  5016.4    0.05       0  5018.7    0.04       0  5023.7    0.05       0
  5480.3    0.04       0
Bank Sta=5018.7,5023.7
Exp/Cntr=0.3,0.1

Type RM Length L Ch R = 1,13581,505,505,505
BEGIN DESCRIPTION:
TRIB 3 TO YORKTOWN CREEK 24.0
END DESCRIPTION:
XS GIS Cut Line= 3
      2435825.03     13552025.03      2435025.00     13551125.00
      2434274.96     13551075.00
#Sta/Elev= 30
  3748.5  327.52  3769.9  327.02  3790.8  327.34  3855.2  325.22  3861.8  324.47
  3876.1  324.50  3882.8  323.45  3911.2  321.54  3925.4  321.63  3947.1  320.74
  4081.8  318.01  4102.7  318.05  4201.6  316.17  4265.7  315.10  4286.6  315.40
  4308.4  314.73  4378.6  315.98  4506.6  314.41  4777.4  314.19  5000.3  312.66
  5000.6  312.16  5005.0  312.16  5005.4  312.66  5062.9  313.59  5133.1  313.37
  5323.5  315.17  5349.3  315.84  5443.8  317.38  5644.2  324.66  5704.4  325.72
#Mann=6,-1,0
  3748.5    0.05       0  4201.6    0.04       0  4777.4    0.05       0
  5000.3    0.05       0  5005.4    0.05       0  5349.3    0.04       0
Bank Sta=5000.3,5005.4
Exp/Cntr=0.3,0.1

Type RM Length L Ch R = 1,13076,440,440,440
BEGIN DESCRIPTION:
TRIB 3 TO YORKTOWN CREEK 23.0
END DESCRIPTION:
XS GIS Cut Line= 3
      2436074.97     13551674.96      2435325.00     13550775.00
      2434824.98     13549874.96
#Sta/Elev= 30
  3897.1  321.90  3996.6  317.64  4017.5  314.24  4025.3  316.22  4031.8  312.89
  4039.6  314.16  4046.1  312.56  4060.4  316.14  4066.9  314.31  4081.2  316.39
  4089.1  319.21  4109.9  320.13  4181.5  313.05  4337.7  311.98  4344.2  309.67
  4352.0  309.30  4450.9  309.31  4458.2  311.38  4461.0  311.31  4508.2  314.53
  4607.1  311.10  5091.5  311.71  5423.2  309.23  5480.4  310.44  5553.6  309.00
  5557.9  307.48  5558.3  306.98  5563.0  307.48  5591.4  309.83  6098.2  324.52
#Mann=5,-1,0
  3897.1    0.05       0  4458.2   0.013       0  4461.0    0.04       0
  5557.9    0.04       0  5563.0    0.04       0
Bank Sta=5557.9,5563
Exp/Cntr=0.3,0.1