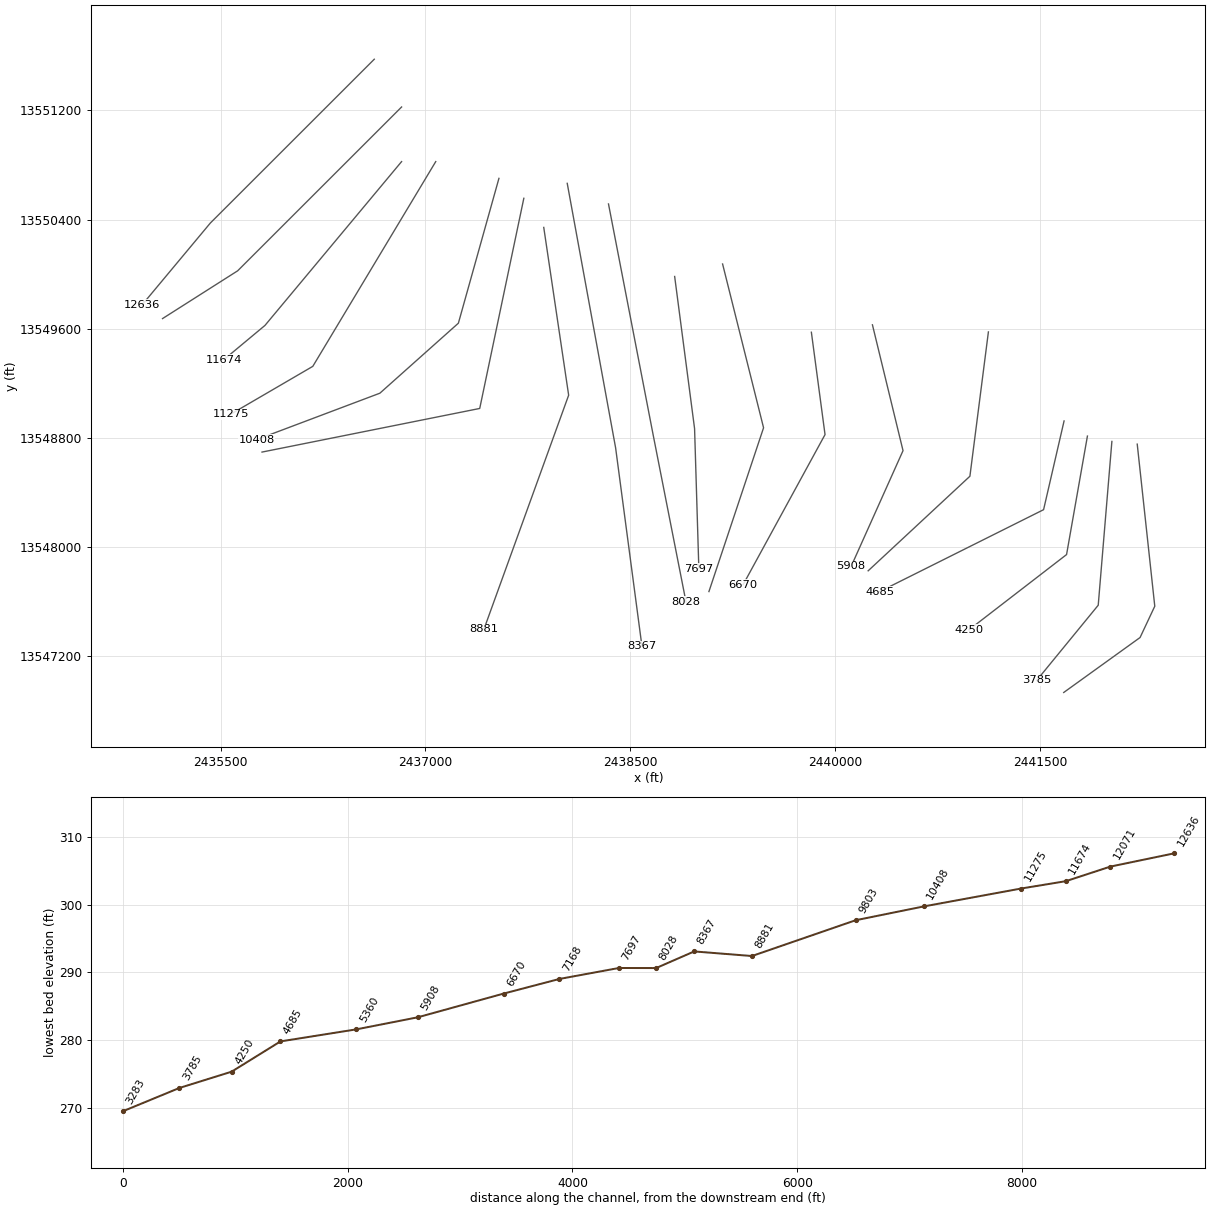
HEC-RAS study TRIB 3 TO YORKTOWN CREEK.prj: TRIB 3 TO YORKTOWN CREEK Base Level Engineering

--- TRIB 3 TO YORKTOWN CREEK.g01 (geometry) --- (continued)

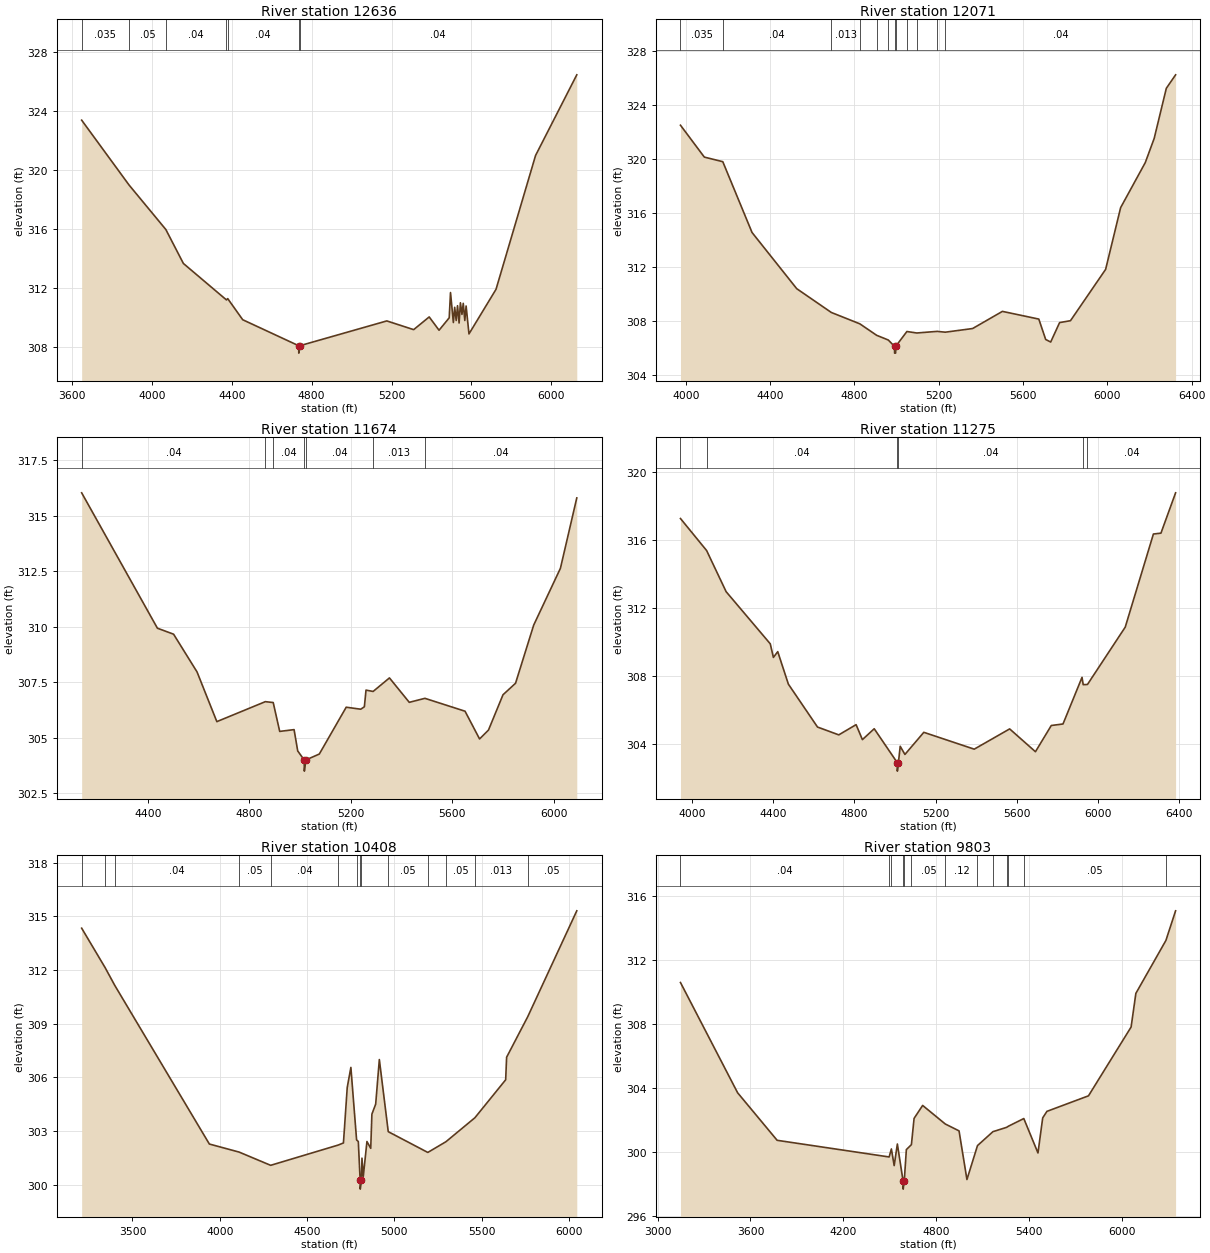
Type RM Length L Ch R = 1,12636,565,565,565
BEGIN DESCRIPTION:
TRIB 3 TO YORKTOWN CREEK 22.0
END DESCRIPTION:
XS GIS Cut Line= 3
      2436625.00     13551575.00      2435425.00     13550375.00
      2434924.98     13549774.98
#Sta/Elev= 30
  3649.0  323.37  3886.2  318.98  4070.2  315.97  4158.1  313.67  4373.8  311.20
  4380.0  311.29  4455.1  309.86  4735.3  308.10  4735.7  307.60  4740.5  308.10
  5176.3  309.78  5310.7  309.19  5388.4  310.05  5437.8  309.15  5488.6  309.99
  5495.1  311.70  5509.4  309.67  5515.9  310.70  5523.7  309.81  5530.2  310.81
  5538.1  309.64  5544.6  311.01  5552.4  310.22  5558.9  310.97  5566.7  309.81
  5573.2  310.79  5587.5  308.90  5722.9  311.92  5920.8  320.98  6127.1  326.44
#Mann=7,-1,0
  3649.0   0.035       0  3886.2    0.05       0  4070.2    0.04       0
  4373.8   0.013       0  4380.0    0.04       0  4735.3    0.04       0
  4740.5    0.04       0
Bank Sta=4735.3,4740.5
Exp/Cntr=0.3,0.1

Type RM Length L Ch R = 1,12071,397,397,397
BEGIN DESCRIPTION:
TRIB 3 TO YORKTOWN CREEK 21.0
END DESCRIPTION:
XS GIS Cut Line= 3
      2436825.03     13551225.03      2435625.00     13550025.00
      2435075.02     13549675.01
#Sta/Elev= 30
  3974.8  322.52  4088.0  320.16  4175.6  319.82  4314.3  314.58  4526.4  310.42
  4690.4  308.66  4825.6  307.82  4905.5  306.97  4960.8  306.62  4990.2  306.15
  4990.7  305.65  4995.5  305.65  4996.0  306.15  5049.0  307.25  5096.0  307.14
  5192.5  307.26  5231.2  307.20  5360.8  307.47  5502.2  308.74  5674.9  308.17
  5707.5  306.66  5731.2  306.47  5773.5  307.91  5825.1  308.05  5991.9  311.85
  6063.1  316.42  6179.9  319.75  6222.2  321.54  6279.8  325.25  6323.8  326.25
#Mann=12,-1,0
  3974.8   0.035       0  4175.6    0.04       0  4690.4   0.013       0
  4825.6    0.04       0  4905.5   0.013       0  4960.8    0.04       0
  4990.2    0.04       0  4996.0    0.04       0  5049.0    0.05       0
  5096.0    0.04       0  5192.5    0.05       0  5231.2    0.04       0
Bank Sta=4990.2,4996
Exp/Cntr=0.3,0.1

Type RM Length L Ch R = 1,11674,399,399,399
BEGIN DESCRIPTION:
TRIB 3 TO YORKTOWN CREEK 20.0
END DESCRIPTION:
XS GIS Cut Line= 3
      2436825.00     13550825.00      2435825.00     13549625.00
      2435524.97     13549374.98
#Sta/Elev= 30
  4139.0  316.03  4437.7  309.93  4501.5  309.66  4594.0  307.96  4672.1  305.72
  4863.3  306.62  4894.4  306.58  4920.0  305.28  4976.7  305.36  4991.0  304.40
  5016.7  303.99  5017.2  303.49  5022.5  303.99  5076.2  304.26  5182.3  306.37
  5239.6  306.28  5253.9  306.39  5260.4  307.14  5288.4  307.08  5352.8  307.69
  5431.0  306.59  5492.7  306.77  5650.9  306.19  5708.2  304.94  5743.4  305.34
  5800.6  306.93  5850.1  307.45  5921.7  310.07  6027.1  312.63  6091.6  315.80
#Mann=7,-1,0
  4139.0    0.04       0  4863.3    0.05       0  4894.4    0.04       0
  5016.7    0.04       0  5022.5    0.04       0  5288.4   0.013       0
  5492.7    0.04       0
Bank Sta=5016.7,5022.5
Exp/Cntr=0.3,0.1

Type RM Length L Ch R = 1,11275,867,867,867
BEGIN DESCRIPTION:
TRIB 3 TO YORKTOWN CREEK 19.0
END DESCRIPTION:
XS GIS Cut Line= 3
      2437075.01     13550825.01      2436175.00     13549325.00
      2435575.02     13548975.01
#Sta/Elev= 30
  3941.1  317.24  4070.1  315.36  4166.6  312.94  4384.3  309.88  4399.8  309.08
  4421.2  309.42  4473.7  307.51  4617.5  304.99  4722.5  304.53  4808.0  305.13
  4839.1  304.25  4897.4  304.89  5011.1  302.90  5011.6  302.40  5016.9  302.90
  5025.7  303.86  5049.0  303.38  5142.3  304.68  5391.1  303.69  5566.0  304.88
  5693.3  303.54  5771.4  305.08  5829.3  305.17  5923.2  307.91  5928.9  307.48
  5950.0  307.49  6136.5  310.86  6275.5  316.33  6312.7  316.38  6385.0  318.75
#Mann=6,-1,0
  3941.1   0.035       0  4070.1    0.04       0  5011.1    0.04       0
  5016.9    0.04       0  5928.9   0.013       0  5950.0    0.04       0
Bank Sta=5011.1,5016.9
Exp/Cntr=0.3,0.1

Type RM Length L Ch R = 1,10408,605,605,605
BEGIN DESCRIPTION:
Mapping XS ad4f4a38
END DESCRIPTION:
XS GIS Cut Line= 4
      2437537.66     13550702.19      2437240.82     13549641.24
      2436666.07     13549128.34      2435764.01     13548788.14
#Sta/Elev= 30
  3209.0  314.33  3343.7  312.12  3398.2  311.14  3940.4  302.27  4110.8  301.82
  4291.6  301.08  4677.8  302.21  4708.5  302.33  4730.2  305.43  4751.1  306.55
  4783.8  302.50  4793.7  302.41  4804.2  300.25  4804.7  299.75  4811.6  300.25
  4814.6  301.48  4822.2  300.46  4843.1  302.41  4864.8  302.03  4871.5  303.94
  4893.2  304.50  4914.1  306.99  4965.2  302.96  5191.8  301.80  5295.8  302.40
  5461.7  303.74  5637.8  305.86  5643.2  307.12  5764.0  309.38  6045.1  315.30
#Mann=14,-1,0
  3209.0    0.04       0  3343.7    0.05       0  3398.2    0.04       0
  4110.8    0.05       0  4291.6    0.04       0  4677.8    0.05       0
  4783.8    0.04       0  4804.2    0.05       0  4811.6    0.04       0
  4965.2    0.05       0  5191.8    0.04       0  5295.8    0.05       0
  5461.7   0.013       0  5764.0    0.05       0
Bank Sta=4804.2,4811.6
Exp/Cntr=0.3,0.1

Type RM Length L Ch R = 1,9803,922,922,922
BEGIN DESCRIPTION:
Mapping XS d52185ca
END DESCRIPTION:
XS GIS Cut Line= 3
      2437719.94     13550556.31      2437397.00     13549016.55
      2435803.28     13548696.98
#Sta/Elev= 30
  3147.8  310.62  3517.0  303.73  3772.4  300.76  4495.8  299.72  4510.4  300.22
  4528.5  299.18  4549.0  300.53  4586.1  298.21  4586.6  297.71  4593.5  298.21
  4607.1  300.18  4639.8  300.49  4657.0  302.13  4712.4  302.94  4858.5  301.78
  4947.5  301.35  4998.5  298.31  5066.7  300.43  5166.4  301.30  5254.7  301.57
  5266.1  301.64  5365.9  302.12  5457.4  299.97  5488.0  302.16  5515.4  302.57
  5783.8  303.54  6059.2  307.84  6089.8  309.94  6284.0  313.25  6346.5  315.10
#Mann=13,-1,0
  3147.8    0.04       0  4495.8    0.05       0  4510.4   0.013       0
  4586.1    0.05       0  4593.5   0.013       0  4639.8    0.05       0
  4858.5    0.12       0  5066.7    0.05       0  5166.4   0.013       0
  5254.7    0.05       0  5266.1    0.12       0  5365.9    0.05       0
  6284.0    0.04       0
Bank Sta=4586.1,4593.5
Exp/Cntr=0.3,0.1

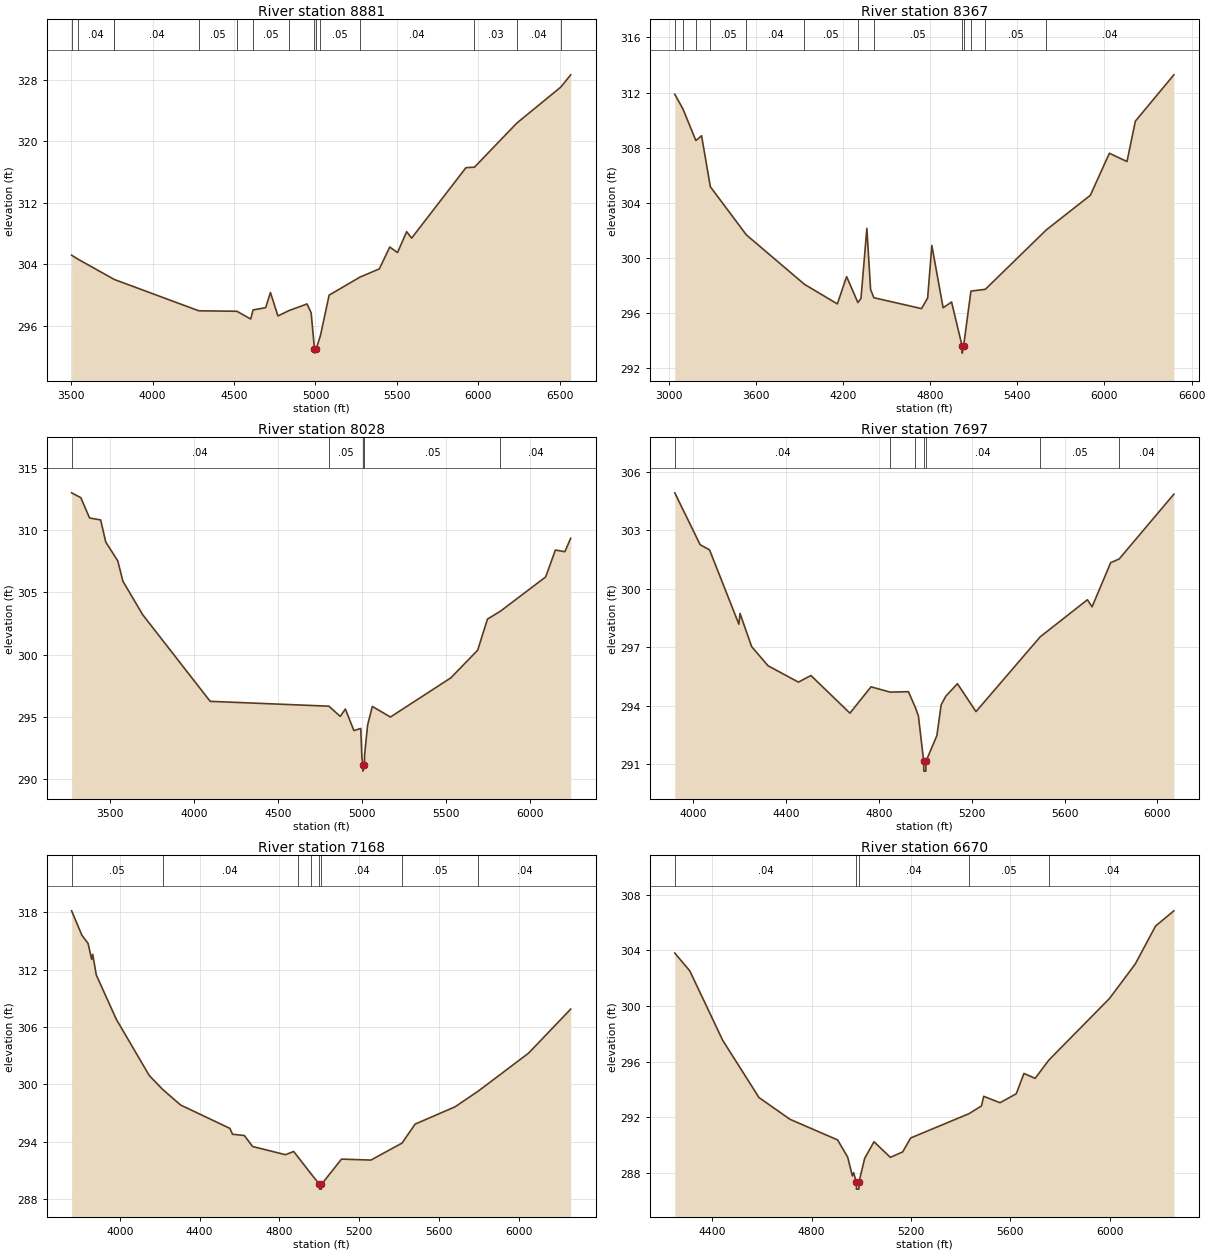
Type RM Length L Ch R = 1,8881,514,514,514
BEGIN DESCRIPTION:
Mapping XS dbbf72f6
END DESCRIPTION:
XS GIS Cut Line= 3
      2437865.78     13550342.80      2438048.07     13549113.65
      2437428.27     13547400.09
#Sta/Elev= 30
  3502.5  305.17  3542.4  304.64  3759.7  302.07  3765.8  302.00  4283.5  297.93
  4517.6  297.87  4602.2  296.86  4616.8  298.04  4694.2  298.34  4723.5  300.31
  4769.5  297.26  4836.3  297.95  4948.1  298.82  4973.5  297.67  4994.0  292.92
  4994.5  292.42  5003.5  292.92  5030.4  294.70  5083.9  299.97  5272.7  302.31
  5392.3  303.39  5456.1  306.23  5503.9  305.51  5559.9  308.23  5590.5  307.39
  5924.0  316.56  5976.5  316.63  6236.2  322.36  6506.3  327.05  6567.3  328.65
#Mann=15,-1,0
  3502.5    0.05       0  3542.4    0.04       0  3759.7    0.05       0
  3765.8    0.04       0  4283.5    0.05       0  4517.6   0.013       0
  4616.8    0.05       0  4836.3    0.12       0  4994.0    0.05       0
  5003.5    0.12       0  5030.4    0.05       0  5272.7    0.04       0
  5976.5    0.03       0  6236.2    0.04       0  6506.3    0.03       0
Bank Sta=4994,5003.5
Exp/Cntr=0.3,0.1

Type RM Length L Ch R = 1,8367,339,339,339
BEGIN DESCRIPTION:
Mapping XS 5121e03d
END DESCRIPTION:
XS GIS Cut Line= 3
      2438037.65     13550665.77      2438391.82     13548728.23
      2438584.53     13547275.10
#Sta/Elev= 30
  3042.0  311.88  3098.0  310.82  3187.3  308.52  3226.4  308.87  3286.9  305.17
  3534.6  301.68  3933.7  298.10  4161.0  296.67  4225.0  298.65  4302.4  296.77
  4323.7  297.07  4364.3  302.15  4389.8  297.72  4412.3  297.12  4740.5  296.33
  4782.6  297.10  4811.6  300.91  4889.1  296.39  4947.4  296.81  5020.2  293.60
  5020.7  293.10  5029.8  293.60  5080.7  297.60  5179.7  297.73  5599.4  302.04
  5902.6  304.55  6033.7  307.60  6154.8  307.00  6212.6  309.93  6477.5  313.29
#Mann=13,-1,0
  3042.0    0.04       0  3098.0   0.013       0  3187.3    0.04       0
  3286.9    0.05       0  3534.6    0.04       0  3933.7    0.05       0
  4302.4   0.013       0  4412.3    0.05       0  5020.2    0.05       0
  5029.8    0.05       0  5080.7   0.013       0  5179.7    0.05       0
  5599.4    0.04       0
Bank Sta=5020.2,5029.8
Exp/Cntr=0.3,0.1

Type RM Length L Ch R = 1,8028,331,331,331
BEGIN DESCRIPTION:
Mapping XS 30945a94
END DESCRIPTION:
XS GIS Cut Line= 3
      2438339.74     13550514.68      2438667.86     13548816.77
      2438907.25     13547599.00
#Sta/Elev= 30
  3271.4  313.01  3326.3  312.62  3378.1  310.99  3444.2  310.83  3474.8  309.05
  3546.1  307.54  3576.6  305.91  3694.1  303.22  4096.1  296.25  4802.8  295.86
  4870.1  295.04  4900.7  295.63  4951.6  293.90  4992.3  294.07  4999.1  291.77
  5004.9  291.14  5005.4  290.64  5014.5  291.14  5014.8  291.91  5033.1  294.34
  5061.1  295.84  5169.0  294.99  5528.8  298.14  5688.1  300.36  5746.5  302.86
  5824.0  303.50  6093.0  306.25  6150.7  308.41  6207.2  308.28  6241.8  309.36
#Mann=5,-1,0
  3271.4    0.04       0  4802.8    0.05       0  5004.9    0.05       0
  5014.5    0.05       0  5824.0    0.04       0
Bank Sta=5004.9,5014.5
Exp/Cntr=0.3,0.1

Type RM Length L Ch R = 1,7697,529,529,529
BEGIN DESCRIPTION:
Mapping XS 53c4e671
END DESCRIPTION:
XS GIS Cut Line= 3
      2438824.12     13549983.41      2438969.95     13548868.85
      2439001.20     13547842.79
#Sta/Elev= 30
  3920.6  304.91  4029.9  302.25  4070.3  301.99  4196.8  298.18  4201.8  298.73
  4251.8  297.03  4322.4  296.05  4453.5  295.21  4507.2  295.55  4675.4  293.62
  4766.2  294.97  4848.1  294.70  4927.5  294.72  4957.8  293.90  4970.5  293.47
  4993.3  291.15  4993.8  290.65  5002.4  290.65  5002.9  291.15  5050.0  292.47
  5068.5  294.05  5088.5  294.49  5138.6  295.13  5218.6  293.70  5495.1  297.53
  5698.6  299.43  5718.8  299.07  5798.9  301.33  5835.5  301.52  6071.2  304.84
#Mann=7,-1,0
  3920.6    0.04       0  4848.1    0.05       0  4957.8    0.04       0
  4993.3    0.04       0  5002.9    0.04       0  5495.1    0.05       0
  5835.5    0.04       0
Bank Sta=4993.3,5002.9
Exp/Cntr=0.3,0.1

Type RM Length L Ch R = 1,7168,498,498,498
BEGIN DESCRIPTION:
TRIB 3 TO YORKTOWN CREEK 11.0
END DESCRIPTION:
XS GIS Cut Line= 3
      2439175.00     13550075.00      2439475.00     13548875.00
      2439075.01     13547675.04
#Sta/Elev= 30
  3758.5  318.14  3810.0  315.59  3841.0  314.73  3859.0  313.06  3864.2  313.59
  3882.2  311.43  3982.7  306.79  4147.6  300.92  4214.3  299.47  4304.8  297.83
  4552.2  295.38  4565.1  294.77  4624.4  294.64  4665.6  293.49  4830.5  292.63
  4871.7  292.97  4892.1  292.42  4956.2  290.70  5000.9  289.53  5001.4  289.03
  5010.6  289.03  5011.1  289.53  5111.4  292.17  5259.0  292.07  5415.1  293.85
  5480.3  295.83  5680.6  297.64  5798.1  299.30  6049.5  303.26  6260.3  307.86
#Mann=8,-1,0
  3758.5    0.05       0  4214.3    0.04       0  4892.1    0.05       0
  4956.2    0.04       0  5000.9    0.04       0  5011.1    0.04       0
  5415.1    0.05       0  5798.1    0.04       0
Bank Sta=5000.9,5011.1
Exp/Cntr=0.3,0.1

Type RM Length L Ch R = 1,6670,762,762,762
BEGIN DESCRIPTION:
TRIB 3 TO YORKTOWN CREEK 10.0
END DESCRIPTION:
XS GIS Cut Line= 3
      2439825.00     13549574.98      2439925.00     13548825.00
      2439325.00     13547725.01
#Sta/Elev= 30
  4248.9  303.80  4309.4  302.52  4441.8  297.54  4588.1  293.43  4712.9  291.87
  4904.6  290.39  4945.0  289.16  4963.9  287.81  4968.9  288.04  4980.1  287.36
  4980.6  286.86  4990.0  286.86  4990.5  287.36  5013.6  289.07  5051.1  290.26
  5117.0  289.14  5166.4  289.53  5198.7  290.53  5433.1  292.27  5483.9  292.83
  5492.9  293.52  5558.4  293.06  5623.9  293.70  5654.8  295.16  5699.9  294.81
  5755.2  296.12  5999.8  300.55  6103.3  303.02  6184.9  305.74  6258.5  306.83
#Mann=5,-1,0
  4248.9    0.04       0  4980.1    0.04       0  4990.5    0.04       0
  5433.1    0.05       0  5755.2    0.04       0
Bank Sta=4980.1,4990.5
Exp/Cntr=0.3,0.1

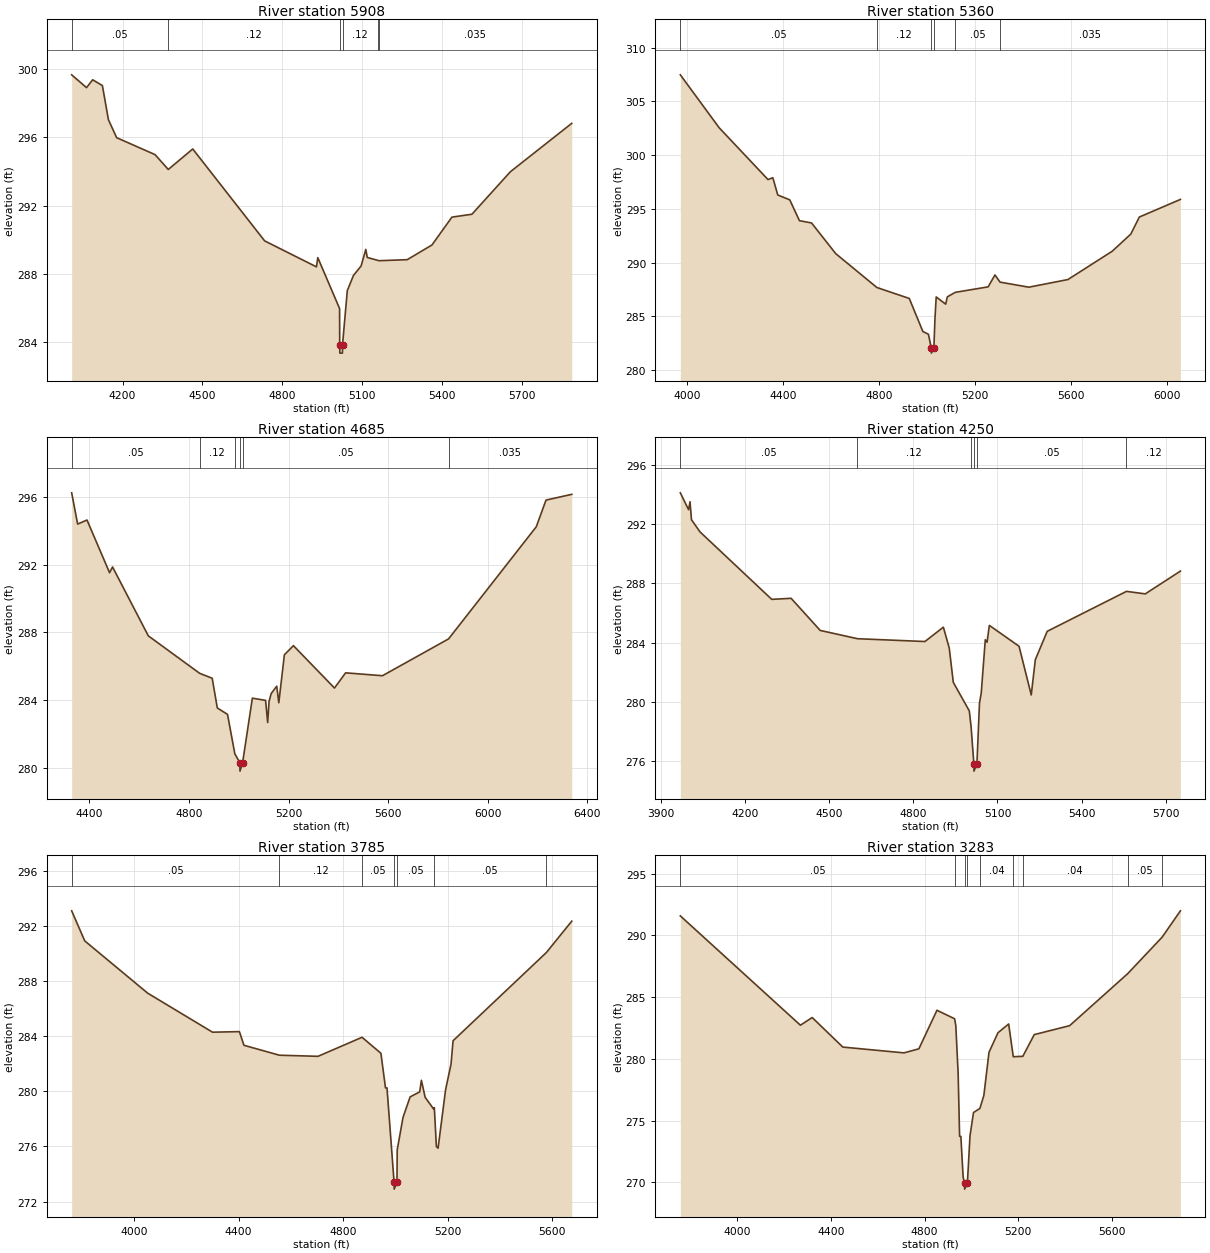
Type RM Length L Ch R = 1,5908,548,548,548
BEGIN DESCRIPTION:
Mapping XS feca892f
END DESCRIPTION:
XS GIS Cut Line= 3
      2440272.04     13549629.22      2440495.99     13548707.40
      2440116.13     13547859.21
#Sta/Elev= 30
  4008.7  299.65  4064.5  298.90  4087.5  299.36  4124.1  299.02  4146.8  297.02
  4177.7  295.97  4321.8  294.98  4371.5  294.11  4463.4  295.31  4733.4  289.93
  4927.9  288.41  4933.0  288.95  5014.8  285.97  5015.3  283.86  5015.8  283.36
  5025.4  283.36  5025.9  283.86  5043.8  287.02  5067.0  287.91  5095.6  288.46
  5113.3  289.43  5118.8  288.96  5158.2  288.79  5162.2  288.77  5268.9  288.83
  5361.7  289.69  5436.7  291.32  5511.8  291.49  5656.4  293.98  5886.7  296.81
#Mann=6,-1,0
  4008.7    0.05       0  4371.5    0.12       0  5015.3    0.05       0
  5025.9    0.12       0  5158.2    0.05       0  5162.2   0.035       0
Bank Sta=5015.3,5025.9
Exp/Cntr=0.3,0.1

Type RM Length L Ch R = 1,5360,675,675,675
BEGIN DESCRIPTION:
Mapping XS c81e085a
END DESCRIPTION:
XS GIS Cut Line= 3
      2441120.99     13549577.22      2440985.57     13548519.90
      2440240.77     13547827.18
#Sta/Elev= 30
  3973.2  307.48  4135.1  302.55  4338.4  297.73  4358.5  297.90  4379.2  296.29
  4429.1  295.84  4469.4  293.90  4519.8  293.69  4620.7  290.83  4791.9  287.68
  4926.9  286.66  4983.6  283.58  5006.6  283.33  5018.5  282.07  5019.0  281.57
  5029.4  282.07  5034.0  284.84  5039.1  286.80  5078.6  286.13  5085.4  286.81
  5118.6  287.23  5255.4  287.74  5283.8  288.85  5305.1  288.18  5425.0  287.71
  5587.7  288.42  5771.9  291.05  5849.6  292.65  5885.2  294.24  6056.3  295.88
#Mann=6,-1,0
  3973.2    0.05       0  4791.9    0.12       0  5018.5    0.05       0
  5029.4    0.12       0  5118.6    0.05       0  5305.1   0.035       0
Bank Sta=5018.5,5029.4
Exp/Cntr=0.3,0.1

Type RM Length L Ch R = 1,4685,435,435,435
BEGIN DESCRIPTION:
TRIB 3 TO YORKTOWN CREEK 6.0
END DESCRIPTION:
XS GIS Cut Line= 3
      2441675.00     13548925.02      2441525.00     13548275.00
      2440325.04     13547675.02
#Sta/Elev= 30
  4328.6  296.27  4352.6  294.42  4390.2  294.66  4480.8  291.54  4492.8  291.88
  4636.5  287.80  4842.9  285.58  4893.1  285.29  4913.6  283.53  4954.6  283.15
  4984.1  280.81  5004.2  280.29  5004.7  279.79  5015.2  280.29  5054.4  284.11
  5107.5  283.98  5115.9  282.67  5121.5  283.92  5129.9  284.38  5152.2  284.82
  5160.6  283.84  5183.0  286.68  5219.3  287.22  5384.2  284.71  5428.9  285.61
  5577.1  285.44  5842.5  287.62  6194.8  294.26  6233.9  295.84  6337.3  296.18
#Mann=6,-1,0
  4328.6    0.05       0  4842.9    0.12       0  4984.1    0.05       0
  5004.2    0.05       0  5015.2    0.05       0  5842.5   0.035       0
Bank Sta=5004.2,5015.2
Exp/Cntr=0.3,0.1

Type RM Length L Ch R = 1,4250,465,465,465
BEGIN DESCRIPTION:
Mapping XS 68f7227e
END DESCRIPTION:
XS GIS Cut Line= 3
      2441845.98     13548814.17      2441693.21     13547946.15
      2440978.98     13547394.87
#Sta/Elev= 30
  3968.8  294.12  3998.3  292.98  4003.4  293.52  4008.6  292.30  4039.0  291.48
  4294.9  286.92  4364.0  286.99  4467.7  284.82  4600.7  284.26  4841.2  284.07
  4907.0  285.04  4927.9  283.63  4942.4  281.31  4999.5  279.38  5005.9  278.30
  5015.7  275.81  5016.2  275.31  5026.7  275.81  5035.7  279.89  5042.0  280.58
  5056.5  284.19  5062.8  284.02  5071.0  285.16  5176.9  283.75  5220.4  280.46
  5234.9  282.84  5277.4  284.76  5560.1  287.46  5627.1  287.29  5752.4  288.83
#Mann=6,-1,0
  3968.8    0.05       0  4600.7    0.12       0  5005.9    0.05       0
  5015.7    0.05       0  5026.7    0.05       0  5560.1    0.12       0
Bank Sta=5015.7,5026.7
Exp/Cntr=0.3,0.1

Type RM Length L Ch R = 1,3785,502,502,502
BEGIN DESCRIPTION:
TRIB 3 TO YORKTOWN CREEK 5.0
END DESCRIPTION:
XS GIS Cut Line= 3
      2442025.00     13548774.97      2441925.00     13547575.00
      2441474.98     13547024.97
#Sta/Elev= 30
  3760.7  293.08  3810.8  290.90  4051.7  287.11  4300.0  284.28  4402.9  284.32
  4420.4  283.33  4556.1  282.61  4703.9  282.53  4872.5  283.91  4944.8  282.75
  4962.3  280.24  4968.1  280.24  4995.2  273.40  4995.7  272.90  5006.2  273.40
  5007.2  275.74  5029.4  278.10  5056.7  279.59  5093.3  279.95  5099.8  280.79
  5114.1  279.56  5147.2  278.69  5149.3  278.81  5157.2  275.99  5163.7  275.87
  5192.4  280.11  5213.2  281.96  5221.1  283.66  5578.5  290.06  5675.5  292.33
#Mann=7,-1,0
  3760.7    0.05       0  4556.1    0.12       0  4872.5    0.05       0
  4995.2    0.05       0  5006.2    0.05       0  5147.2    0.05       0
  5578.5   0.013       0
Bank Sta=4995.2,5006.2
Exp/Cntr=0.3,0.1

Type RM Length L Ch R = 1,3283,215,215,215
BEGIN DESCRIPTION:
Mapping XS 5f9ed00f
END DESCRIPTION:
XS GIS Cut Line= 4
      2442210.57     13548755.15      2442339.04     13547567.67
      2442231.40     13547338.51      2441672.39     13546935.74
#Sta/Elev= 30
  3756.5  291.58  4269.6  282.73  4319.9  283.35  4450.7  280.96  4712.2  280.49
  4775.7  280.82  4853.0  283.94  4928.5  283.25  4933.5  282.70  4943.5  278.83
  4949.7  273.73  4955.1  273.73  4964.9  270.42  4970.7  269.96  4971.2  269.46
  4983.0  269.96  4994.1  273.77  5009.1  275.66  5036.3  275.99  5053.3  277.04
  5075.4  280.54  5113.7  282.12  5159.3  282.83  5179.0  280.18  5219.8  280.21
  5268.7  281.97  5419.6  282.69  5668.3  286.91  5815.1  289.86  5893.1  291.99
#Mann=9,-1,0
  3756.5    0.05       0  4928.5     0.1       0  4970.7    0.05       0
  4983.0     0.1       0  5036.3    0.04       0  5179.0    0.05       0
  5219.8    0.04       0  5668.3    0.05       0  5815.1   0.013       0
Bank Sta=4970.7,4983
Exp/Cntr=0.3,0.1