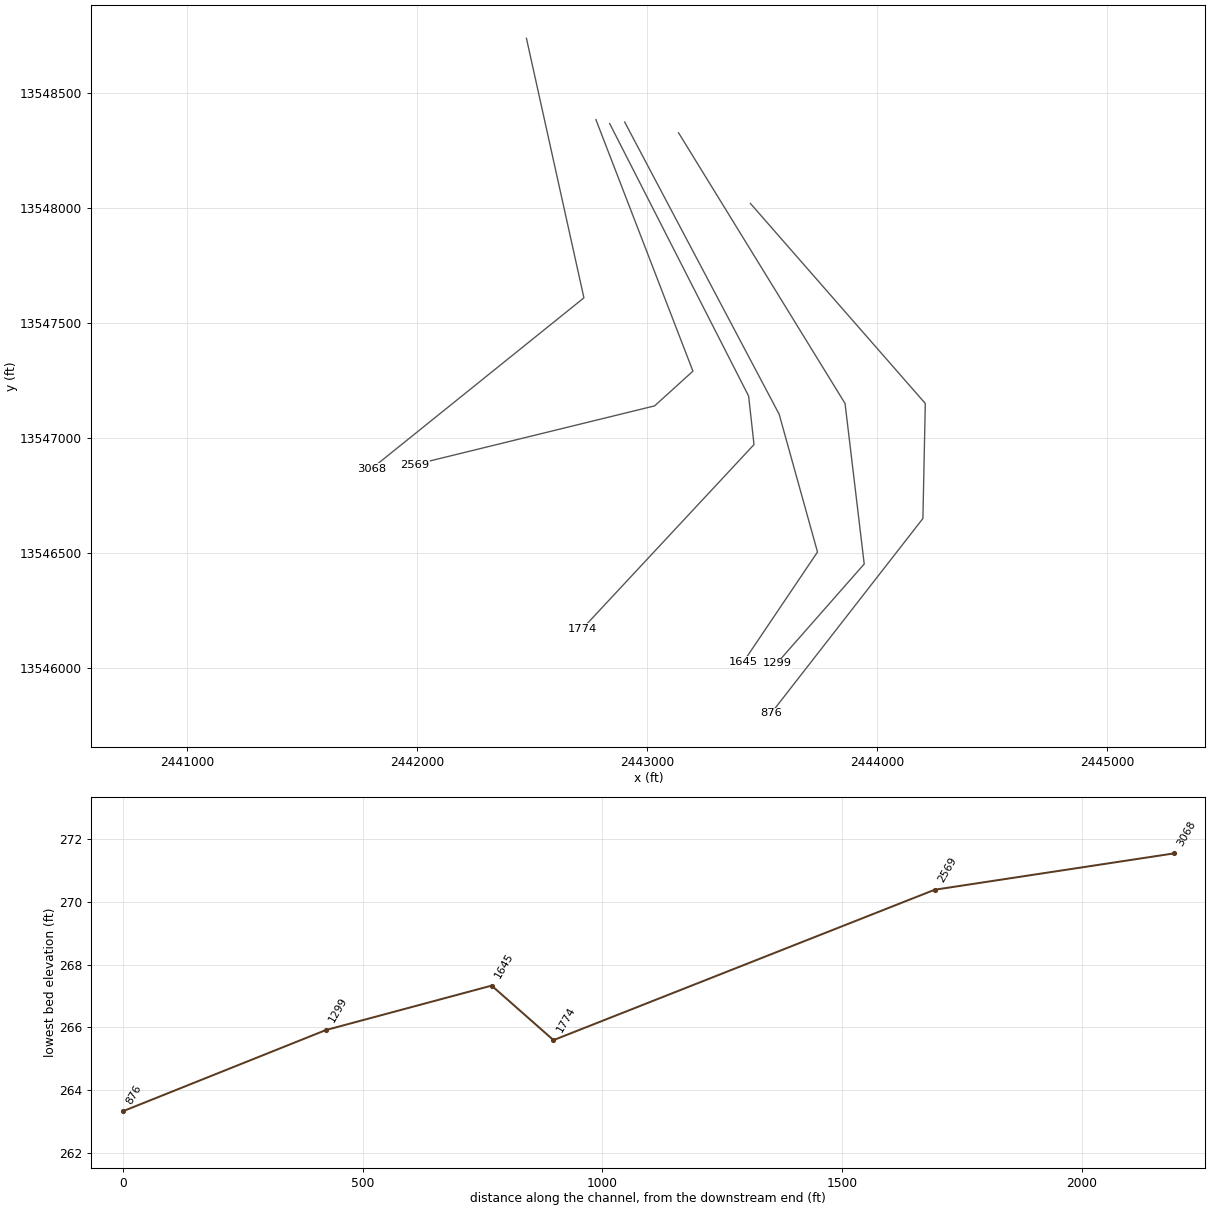
HEC-RAS study TRIB 3 TO YORKTOWN CREEK.prj: TRIB 3 TO YORKTOWN CREEK Base Level Engineering

--- TRIB 3 TO YORKTOWN CREEK.g01 (geometry) --- (continued)

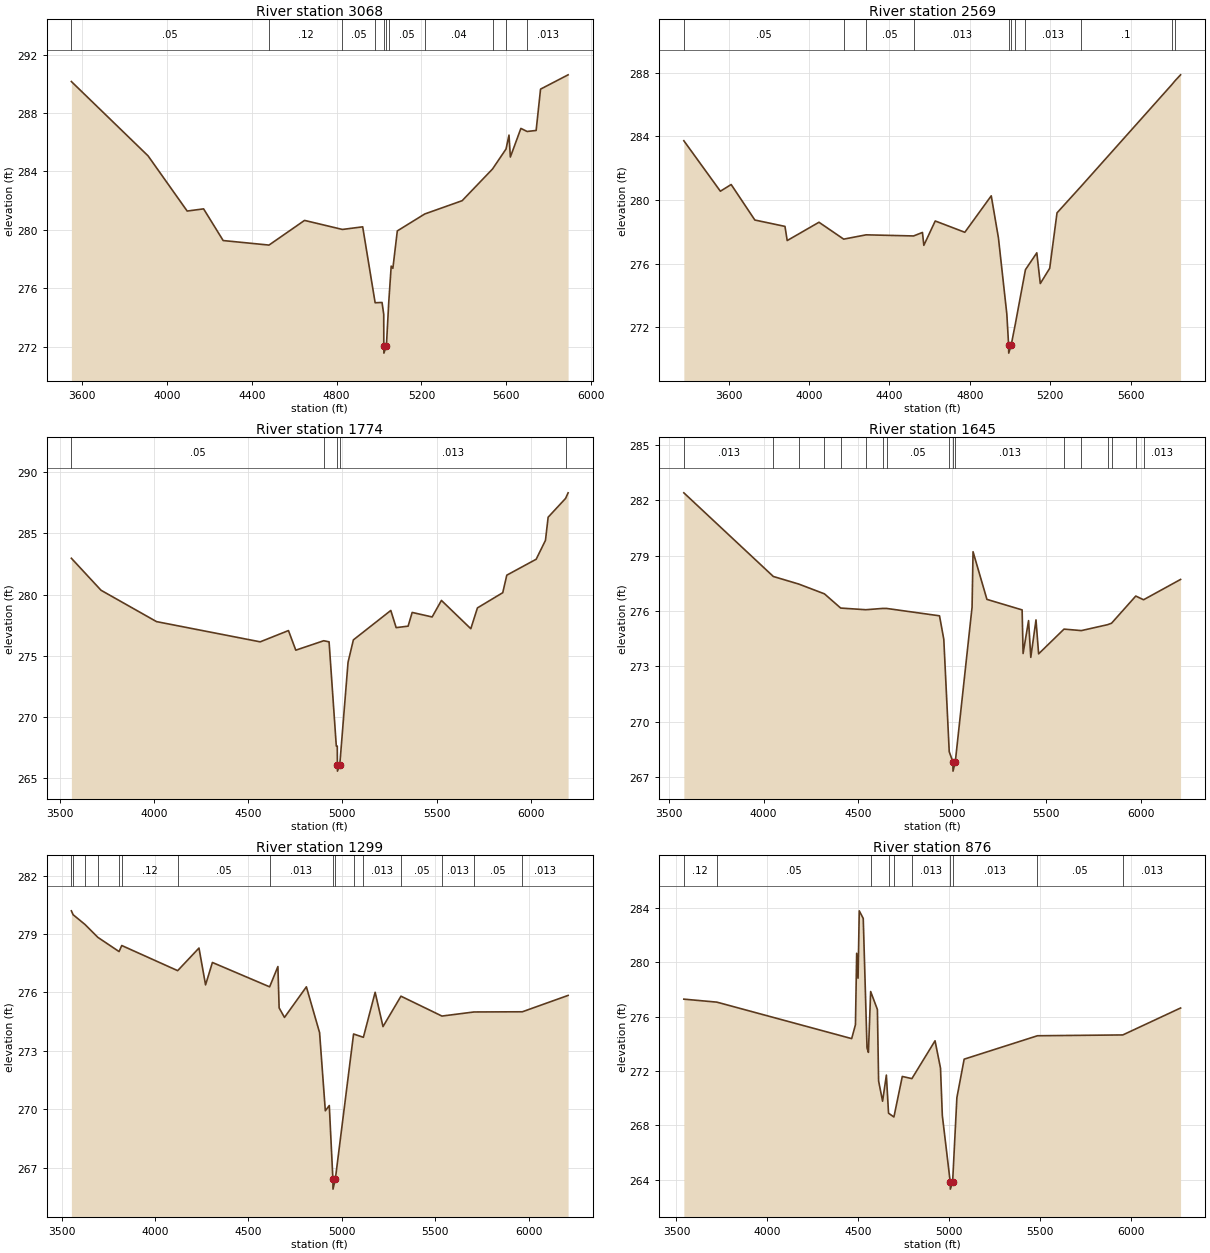
Type RM Length L Ch R = 1,3068,499,499,499
BEGIN DESCRIPTION:
Mapping XS ce234cba
END DESCRIPTION:
XS GIS Cut Line= 3
      2442475.11     13548737.93      2442725.11     13547609.45
      2441801.54     13546866.42
#Sta/Elev= 30
  3550.0  290.15  3911.5  285.06  4095.8  281.28  4173.2  281.43  4265.5  279.26
  4481.5  278.95  4648.9  280.64  4827.5  280.02  4923.0  280.20  4981.7  275.00
  5014.2  275.02  5022.2  274.21  5022.5  272.05  5023.0  271.55  5034.8  272.05
  5045.8  275.03  5057.4  277.51  5065.3  277.36  5086.2  279.92  5215.5  281.08
  5391.8  281.99  5534.9  284.16  5598.6  285.53  5612.6  286.48  5619.0  284.98
  5668.6  286.94  5698.0  286.73  5740.5  286.80  5761.3  289.63  5891.2  290.61
#Mann=11,-1,0
  3550.0    0.05       0  4481.5    0.12       0  4827.5    0.05       0
  4981.7     0.1       0  5022.5    0.05       0  5034.8     0.1       0
  5045.8    0.05       0  5215.5    0.04       0  5534.9   0.013       0
  5598.6    0.04       0  5698.0   0.013       0
Bank Sta=5022.5,5034.8
Exp/Cntr=0.3,0.1

Type RM Length L Ch R = 1,2569,795,795,795
BEGIN DESCRIPTION:
Mapping XS 743989a9
END DESCRIPTION:
XS GIS Cut Line= 4
      2442777.24     13548384.47      2443199.11     13547290.73
      2443032.45     13547139.69      2441990.76     13546884.47
#Sta/Elev= 30
  3377.7  283.73  3559.3  280.56  3613.0  280.98  3730.8  278.75  3880.5  278.35
  3891.6  277.46  4049.6  278.61  4172.4  277.55  4284.1  277.82  4520.0  277.75
  4564.1  277.97  4570.9  277.16  4627.6  278.69  4774.7  277.98  4906.1  280.27
  4941.9  277.62  4983.5  272.85  4992.5  270.89  4993.0  270.39  5005.1  270.89
  5025.8  272.22  5076.1  275.63  5132.6  276.69  5149.9  274.76  5196.7  275.72
  5233.1  279.20  5351.6  280.85  5802.9  287.24  5820.8  287.51  5847.4  287.87
#Mann=11,-1,0
  3377.7    0.05       0  4172.4    0.12       0  4284.1    0.05       0
  4520.0   0.013       0  4992.5    0.03       0  5005.1   0.013       0
  5025.8     0.1       0  5076.1   0.013       0  5351.6     0.1       0
  5802.9   0.013       0  5820.8    0.04       0
Bank Sta=4992.5,5005.1
Exp/Cntr=0.3,0.1

Type RM Length L Ch R = 1,1774,129,129,129
BEGIN DESCRIPTION:
Mapping XS c362588d
END DESCRIPTION:
XS GIS Cut Line= 4
      2442837.08     13548367.28      2443441.26     13547182.36
      2443464.69     13546971.43      2442718.95     13546171.11
#Sta/Elev= 30
  3561.5  282.96  3718.8  280.35  4013.4  277.79  4563.6  276.14  4713.6  277.06
  4752.5  275.46  4900.8  276.23  4929.1  276.14  4967.5  267.63  4972.6  267.63
  4973.2  266.09  4973.7  265.59  4985.8  266.09  5029.8  274.47  5058.1  276.30
  5256.7  278.70  5285.1  277.30  5348.6  277.42  5370.1  278.54  5476.1  278.17
  5525.4  279.52  5681.3  277.21  5716.5  278.91  5850.8  280.15  5872.3  281.58
  6028.2  282.88  6077.5  284.42  6091.7  286.31  6184.0  287.84  6197.7  288.30
#Mann=5,-1,0
  3561.5    0.05       0  4900.8   0.013       0  4973.2    0.03       0
  4985.8   0.013       0  6184.0    0.05       0
Bank Sta=4973.2,4985.8
Exp/Cntr=0.3,0.1

Type RM Length L Ch R = 1,1645,346,346,346
BEGIN DESCRIPTION:
Mapping XS 1304494b
END DESCRIPTION:
XS GIS Cut Line= 4
      2442902.23     13548374.07      2443574.11     13547103.23
      2443740.78     13546504.27      2443418.96     13546026.73
#Sta/Elev= 30
  3576.8  282.40  4051.5  277.87  4186.4  277.46  4322.6  276.93  4408.8  276.16
  4542.3  276.07  4631.3  276.14  4652.1  276.14  4933.1  275.74  4955.8  274.47
  4984.7  268.38  5004.2  267.83  5004.7  267.33  5016.8  267.83  5105.8  276.21
  5111.0  279.21  5184.6  276.63  5371.3  276.06  5376.5  273.70  5405.5  275.48
  5417.3  273.49  5444.9  275.52  5458.8  273.68  5593.6  275.02  5685.7  274.94
  5824.6  275.26  5845.8  275.34  5974.2  276.81  6015.6  276.61  6211.9  277.71
#Mann=17,-1,0
  3576.8   0.013       0  4051.5    0.05       0  4186.4   0.013       0
  4322.6    0.05       0  4408.8   0.013       0  4542.3    0.05       0
  4631.3   0.013       0  4652.1    0.05       0  4984.7   0.013       0
  5004.2    0.03       0  5016.8   0.013       0  5593.6    0.05       0
  5685.7   0.013       0  5824.6    0.05       0  5845.8   0.013       0
  5974.2    0.05       0  6015.6   0.013       0
Bank Sta=5004.2,5016.8
Exp/Cntr=0.3,0.1

Type RM Length L Ch R = 1,1299,423,423,423
BEGIN DESCRIPTION:
Mapping XS e95aedae
END DESCRIPTION:
XS GIS Cut Line= 4
      2443136.64     13548327.15      2443860.57     13547150.10
      2443943.90     13546452.19      2443563.72     13546019.92
#Sta/Elev= 30
  3551.5  280.19  3560.9  279.99  3624.4  279.49  3693.2  278.83  3806.9  278.10
  3821.3  278.41  4120.8  277.12  4234.9  278.28  4270.2  276.39  4306.8  277.54
  4613.3  276.29  4657.6  277.33  4664.2  275.21  4692.8  274.72  4810.2  276.29
  4880.8  273.94  4911.6  269.93  4932.8  270.20  4952.2  266.41  4952.7  265.91
  4965.0  266.41  5062.9  273.87  5115.4  273.70  5178.4  276.01  5220.5  274.25
  5316.7  275.81  5536.2  274.79  5707.5  275.00  5966.9  275.01  6211.9  275.85
#Mann=16,-1,0
  3551.5    0.05       0  3560.9   0.013       0  3624.4    0.05       0
  3693.2    0.12       0  3806.9    0.05       0  3821.3    0.12       0
  4120.8    0.05       0  4613.3   0.013       0  4952.2    0.03       0
  4965.0   0.013       0  5062.9    0.05       0  5115.4   0.013       0
  5316.7    0.05       0  5536.2   0.013       0  5707.5    0.05       0
  5966.9   0.013       0
Bank Sta=4952.2,4965
Exp/Cntr=0.3,0.1

Type RM Length L Ch R = 1,876,0,0,0
BEGIN DESCRIPTION:
Mapping XS 8f2e6b6b
END DESCRIPTION:
XS GIS Cut Line= 4
      2443449.10     13548019.91      2444209.53     13547150.10
      2444199.11     13546650.10      2443538.80     13545802.62
#Sta/Elev= 30
  3540.7  277.28  3722.3  277.06  4463.0  274.38  4483.8  275.40  4490.5  280.65
  4498.1  278.82  4504.7  283.77  4526.6  283.21  4547.4  273.70  4555.0  273.37
  4567.3  277.84  4604.4  276.52  4611.0  271.27  4632.9  269.78  4653.7  271.70
  4665.6  268.90  4695.1  268.62  4741.2  271.60  4793.9  271.44  4921.2  274.22
  4951.2  272.21  4961.2  268.73  5004.8  263.82  5005.3  263.32  5017.7  263.82
  5041.2  270.04  5081.2  272.87  5484.0  274.59  5953.1  274.65  6270.5  276.63
#Mann=10,-1,0
  3540.7    0.12       0  3722.3    0.05       0  4567.3   0.013       0
  4665.6    0.05       0  4695.1     0.1       0  4793.9   0.013       0
  5004.8    0.03       0  5017.7   0.013       0  5484.0    0.05       0
  5953.1   0.013       0
Bank Sta=5004.8,5017.7
Exp/Cntr=0.3,0.1

Chan Stop Cuts=-1