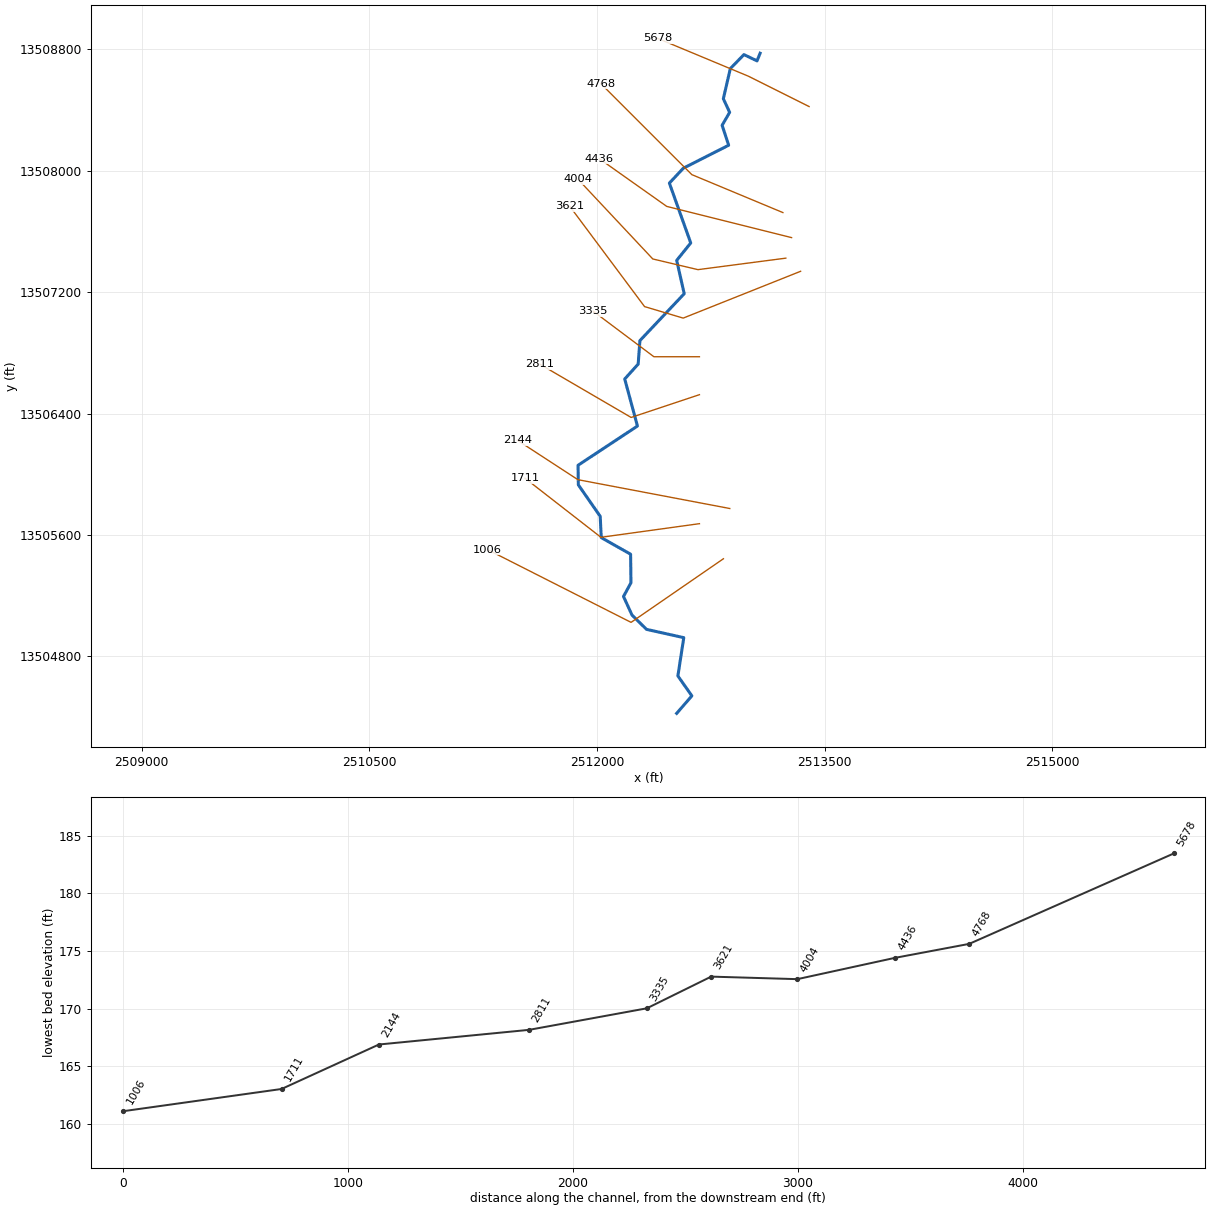
--- TRIB 3_1 TO FIFTEENMILE CREEK.prj (project) ---

Proj Title=TRIB 3_1 TO FIFTEENMILE CREEK Base Level Engineering
Current Plan=p01
Default Exp/Contr=0.3,0.1
English Units
Geom File=g01
Flow File=f01
Plan File=p01
BEGIN DESCRIPTION:
TRIB 3_1 TO FIFTEENMILE CREEK
END DESCRIPTION:

--- TRIB 3_1 TO FIFTEENMILE CREEK.p01 (plan) ---

Plan Title=Multiple Run
Short Identifier=Multiple
Geom File=g01
Flow File=f01
Subcritical Flow
K Sum by GR= 0
Std Step Tol= 0.01
Critical Tol= 0.01
Num of Std Step Trials= 20
Max Error Tol= 0.3
Flow Tol Ratio= 0.001
Split Flow NTrial= 30
Split Flow Tol= 0.02
Split Flow Ratio= 0.02
Log Output Level= 0
Friction Slope Method= 1
Unsteady Friction Slope Method= 2
Unsteady Bridges Friction Slope Method= 1
Parabolic Critical Depth
Global Vel Dist=  1 , 1 , 1
Global Log Level= 0
CheckData=True
Encroach Param= -1, 0, 0, 0
BEGIN DESCRIPTION:
Multiple Run
END DESCRIPTION:

--- TRIB 3_1 TO FIFTEENMILE CREEK.f01 (steady flow) ---

Flow Title=Multiple
Number of Profiles=7
Profile Names=10-year,25-year,50-year,1pct_min,100-year,1pct_plu,500-year
River Rch & RM= TRIB 3_1 TO FIFT,Reach-1,5678
     449     701     920     585    1168    2330    1860
River Rch & RM= TRIB 3_1 TO FIFT,Reach-1,4004
     481     752     990     631    1259    2511    2011
River Rch & RM= TRIB 3_1 TO FIFT,Reach-1,2144
     719    1152    1540     996    1987    3964    3270
Boundary for River Rch & Prof#=TRIB 3_1 TO FIFT,Reach-1,1
Up Type=0
Dn Type=3
Dn Slope=0.005
Boundary for River Rch & Prof#=TRIB 3_1 TO FIFT,Reach-1,2
Up Type=0
Dn Type=3
Dn Slope=0.005
Boundary for River Rch & Prof#=TRIB 3_1 TO FIFT,Reach-1,3
Up Type=0
Dn Type=3
Dn Slope=0.005
Boundary for River Rch & Prof#=TRIB 3_1 TO FIFT,Reach-1,4
Up Type=0
Dn Type=3
Dn Slope=0.005
Boundary for River Rch & Prof#=TRIB 3_1 TO FIFT,Reach-1,5
Up Type=0
Dn Type=3
Dn Slope=0.005
Boundary for River Rch & Prof#=TRIB 3_1 TO FIFT,Reach-1,6
Up Type=0
Dn Type=3
Dn Slope=0.005
Boundary for River Rch & Prof#=TRIB 3_1 TO FIFT,Reach-1,7
Up Type=0
Dn Type=3
Dn Slope=0.005

--- TRIB 3_1 TO FIFTEENMILE CREEK.g01 (geometry) ---

Geom Title=Existing Conditions

River Reach=TRIB 3_1 TO FIFT,Reach-1
Reach XY= 30
      2513075.00     13508775.00      2513054.59     13508724.57
      2512968.27     13508765.89      2512878.54     13508673.56
      2512832.59     13508474.99      2512874.16     13508385.70
      2512824.62     13508300.00      2512867.63     13508168.66
      2512568.81     13508017.14      2512476.96     13507919.12
      2512617.70     13507524.92      2512525.25     13507409.78
      2512574.76     13507190.22      2512282.82     13506881.19
      2512271.43     13506726.47      2512182.81     13506628.41
      2512266.56     13506318.23      2511875.31     13506059.98
      2511877.05     13505930.86      2512021.24     13505723.44
      2512028.07     13505583.28      2512221.55     13505473.75
      2512223.76     13505285.50      2512174.70     13505195.17
      2512230.82     13505072.69      2512326.49     13504978.60
      2512571.87     13504923.83      2512533.01     13504671.67
      2512625.14     13504540.36      2512525.00     13504425.00

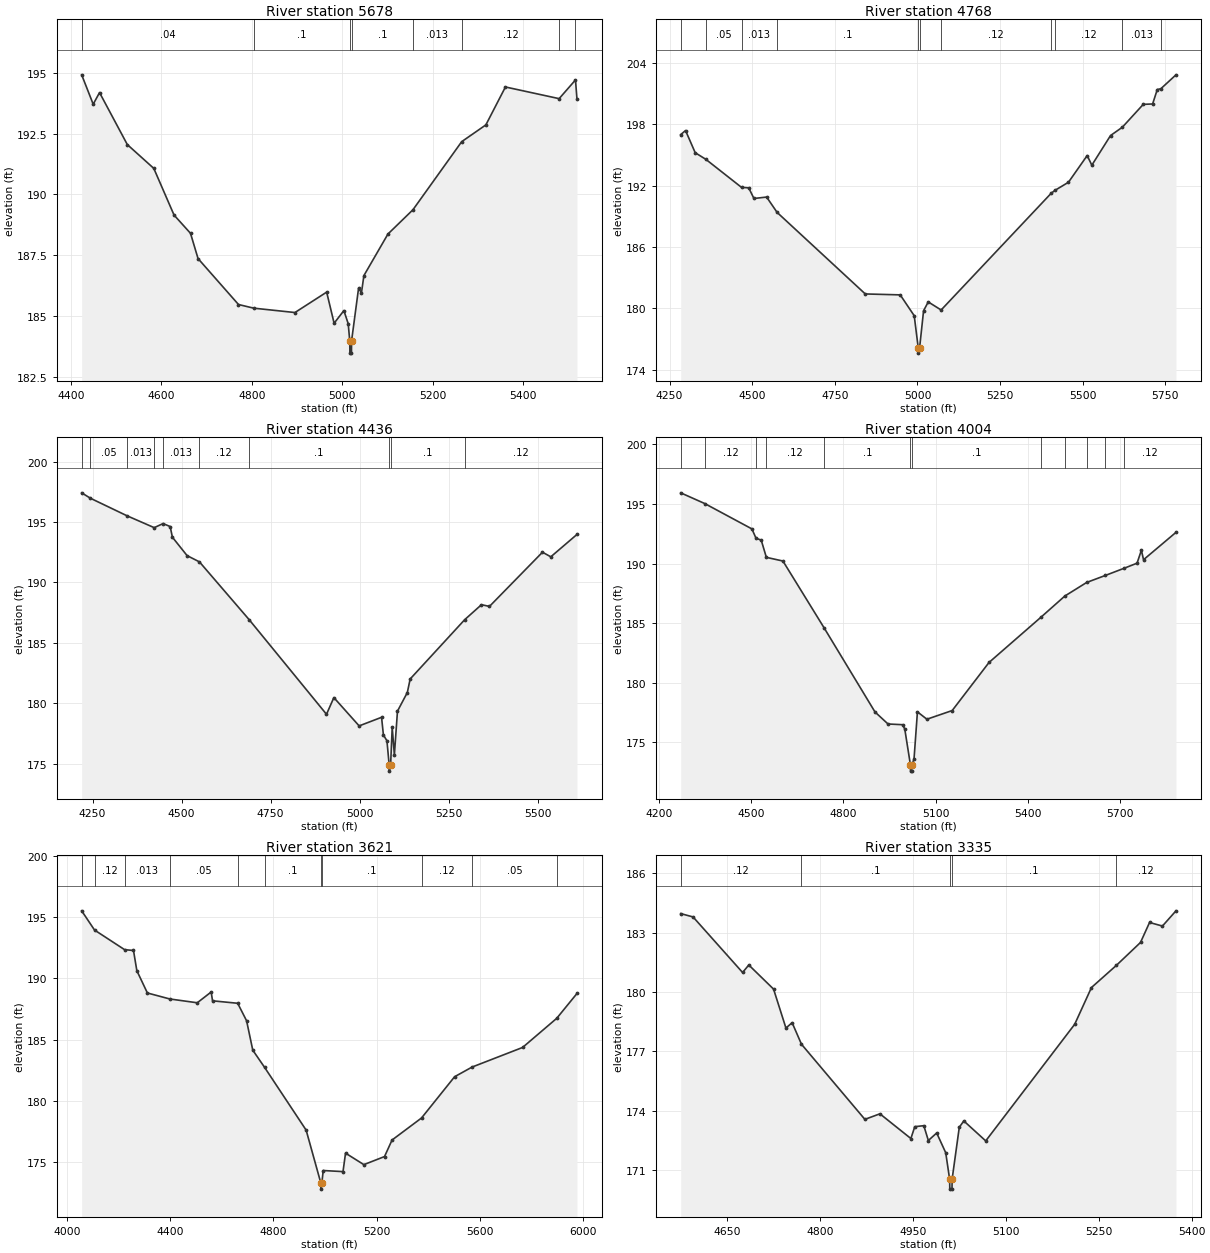
Type RM Length L Ch R = 1,5678,910,910,910
BEGIN DESCRIPTION:
TRIB 3_1 TO FIFTEENMILE CREEK 9.0
END DESCRIPTION:
XS GIS Cut Line= 3
      2513397.79     13508423.55      2512997.75     13508623.58
      2512398.91     13508873.09
#Sta/Elev= 30
  4423.5  194.92  4449.0  193.71  4463.0  194.19  4524.5  192.05  4583.1  191.07
  4627.9  189.15  4664.3  188.40  4681.0  187.36  4770.5  185.47  4804.2  185.32
  4895.4  185.14  4965.6  185.98  4982.1  184.70  5003.7  185.22  5013.3  184.68
  5016.7  183.97  5017.0  183.47  5020.5  183.47  5020.7  183.97  5036.2  186.14
  5042.6  185.95  5048.0  186.66  5101.2  188.37  5156.6  189.37  5264.4  192.17
  5317.9  192.86  5361.2  194.42  5480.0  193.94  5516.2  194.71  5519.5  193.92
#Mann=8,-1,0
  4423.5    0.04       0  4804.2     0.1       0  5016.7    0.05       0
  5020.7     0.1       0  5156.6   0.013       0  5264.4    0.12       0
  5480.0   0.013       0  5516.2    0.12       0
Bank Sta=5016.7,5020.7
Exp/Cntr=0.3,0.1

Type RM Length L Ch R = 1,4768,332,332,332
BEGIN DESCRIPTION:
TRIB 3_1 TO FIFTEENMILE CREEK 8.0
END DESCRIPTION:
XS GIS Cut Line= 3
      2513225.04     13507724.98      2512625.00     13507975.00
      2512024.98     13508575.02
#Sta/Elev= 30
  4283.6  197.00  4298.3  197.40  4327.5  195.23  4359.8  194.58  4467.6  191.84
  4489.5  191.79  4505.2  190.75  4543.6  190.89  4575.3  189.39  4842.1  181.41
  4947.8  181.32  4990.2  179.28  5002.4  176.12  5002.6  175.62  5006.4  176.12
  5018.5  179.77  5032.6  180.63  5071.6  179.84  5404.3  191.25  5415.7  191.54
  5456.9  192.34  5513.5  194.95  5527.6  194.01  5584.2  196.91  5619.8  197.72
  5683.2  199.96  5711.5  200.00  5725.6  201.41  5736.4  201.49  5782.2  202.85
#Mann=11,-1,0
  4283.6    0.04       0  4359.8    0.05       0  4467.6   0.013       0
  4575.3     0.1       0  5002.4    0.05       0  5006.4     0.1       0
  5071.6    0.12       0  5404.3    0.05       0  5415.7    0.12       0
  5619.8   0.013       0  5736.4    0.04       0
Bank Sta=5002.4,5006.4
Exp/Cntr=0.3,0.1

Type RM Length L Ch R = 1,4436,432,432,432
BEGIN DESCRIPTION:
Mapping XS 6ace60d5
END DESCRIPTION:
XS GIS Cut Line= 3
      2513282.30     13507559.98      2512459.73     13507765.62
      2512015.92     13508079.54
#Sta/Elev= 30
  4219.4  197.41  4244.1  196.96  4346.2  195.52  4423.2  194.53  4448.2  194.87
  4468.0  194.62  4474.3  193.74  4515.5  192.22  4550.3  191.70  4689.7  186.93
  4907.2  179.10  4927.9  180.48  4998.9  178.14  5061.9  178.85  5067.1  177.39
  5077.0  176.91  5083.3  174.90  5083.6  174.40  5087.3  174.90  5091.8  178.01
  5097.9  175.74  5106.6  179.36  5134.3  180.90  5142.3  182.02  5295.4  186.92
  5342.6  188.16  5365.1  188.02  5514.0  192.50  5537.4  192.12  5610.9  193.97
#Mann=10,-1,0
  4219.4    0.04       0  4244.1    0.05       0  4346.2   0.013       0
  4423.2    0.05       0  4448.2   0.013       0  4550.3    0.12       0
  4689.7     0.1       0  5083.3    0.05       0  5087.3     0.1       0
  5295.4    0.12       0
Bank Sta=5083.3,5087.3
Exp/Cntr=0.3,0.1

Type RM Length L Ch R = 1,4004,383,383,383
BEGIN DESCRIPTION:
Mapping XS 916696eb
END DESCRIPTION:
XS GIS Cut Line= 4
      2513244.48     13507424.67      2512665.38     13507348.90
      2512367.73     13507419.26      2511875.24     13507944.21
#Sta/Elev= 30
  4270.9  195.94  4349.0  195.04  4502.3  192.91  4515.8  192.12  4532.6  191.97
  4549.3  190.52  4603.2  190.21  4736.9  184.60  4902.4  177.53  4944.7  176.52
  4992.1  176.46  4999.2  176.09  5017.7  173.06  5018.0  172.56  5021.5  172.56
  5021.7  173.06  5029.2  173.56  5040.3  177.54  5071.1  176.92  5153.3  177.65
  5273.0  181.69  5442.2  185.50  5519.4  187.27  5590.3  188.41  5651.1  189.00
  5711.8  189.60  5754.1  190.03  5768.2  191.12  5775.1  190.32  5880.6  192.62
#Mann=12,-1,0
  4270.9   0.013       0  4349.0    0.12       0  4515.8   0.013       0
  4549.3    0.12       0  4736.9     0.1       0  5017.7    0.05       0
  5021.7     0.1       0  5442.2    0.12       0  5519.4    0.05       0
  5590.3    0.12       0  5651.1    0.05       0  5711.8    0.12       0
Bank Sta=5017.7,5021.7
Exp/Cntr=0.3,0.1

Type RM Length L Ch R = 1,3621,286,286,286
BEGIN DESCRIPTION:
Mapping XS 3e2474c2
END DESCRIPTION:
XS GIS Cut Line= 4
      2513341.83     13507338.06      2512567.97     13507029.60
      2512313.61     13507105.37      2511821.11     13507765.64
#Sta/Elev= 30
  4055.7  195.51  4105.6  193.94  4222.1  192.34  4256.8  192.27  4269.8  190.62
  4310.7  188.80  4397.8  188.31  4504.3  188.00  4558.2  188.88  4563.6  188.16
  4661.1  187.96  4695.7  186.53  4719.7  184.13  4765.7  182.72  4926.8  177.60
  4983.8  173.28  4984.0  172.78  4987.8  173.28  4993.1  174.30  5069.9  174.21
  5079.7  175.72  5150.8  174.78  5231.0  175.44  5260.2  176.79  5374.6  178.59
  5503.0  181.96  5570.8  182.75  5766.8  184.35  5899.3  186.73  5977.9  188.76
#Mann=11,-1,0
  4055.7   0.013       0  4105.6    0.12       0  4222.1   0.013       0
  4397.8    0.05       0  4661.1    0.12       0  4765.7     0.1       0
  4983.8    0.05       0  4987.8     0.1       0  5374.6    0.12       0
  5570.8    0.05       0  5899.3    0.12       0
Bank Sta=4983.8,4987.8
Exp/Cntr=0.3,0.1

Type RM Length L Ch R = 1,3335,524,524,524
BEGIN DESCRIPTION:
TRIB 3_1 TO FIFTEENMILE CREEK 5.0
END DESCRIPTION:
XS GIS Cut Line= 3
      2512674.97     13506775.00      2512375.00     13506775.00
      2511974.97     13507075.02
#Sta/Elev= 30
  4574.7  183.97  4594.7  183.80  4674.7  180.99  4684.7  181.37  4724.7  180.15
  4744.7  178.18  4754.7  178.45  4769.8  177.36  4872.2  173.56  4896.5  173.84
  4946.5  172.59  4952.8  173.19  4967.4  173.24  4974.7  172.49  4988.2  172.87
  5002.8  171.87  5009.1  170.53  5009.4  170.03  5012.9  170.03  5013.1  170.53
  5024.7  173.16  5032.0  173.48  5067.4  172.47  5211.1  178.37  5238.2  180.23
  5278.4  181.35  5317.4  182.51  5332.0  183.52  5352.8  183.34  5374.7  184.11
#Mann=5,-1,0
  4574.7    0.12       0  4769.8     0.1       0  5009.1    0.05       0
  5013.1     0.1       0  5278.4    0.12       0
Bank Sta=5009.1,5013.1
Exp/Cntr=0.3,0.1

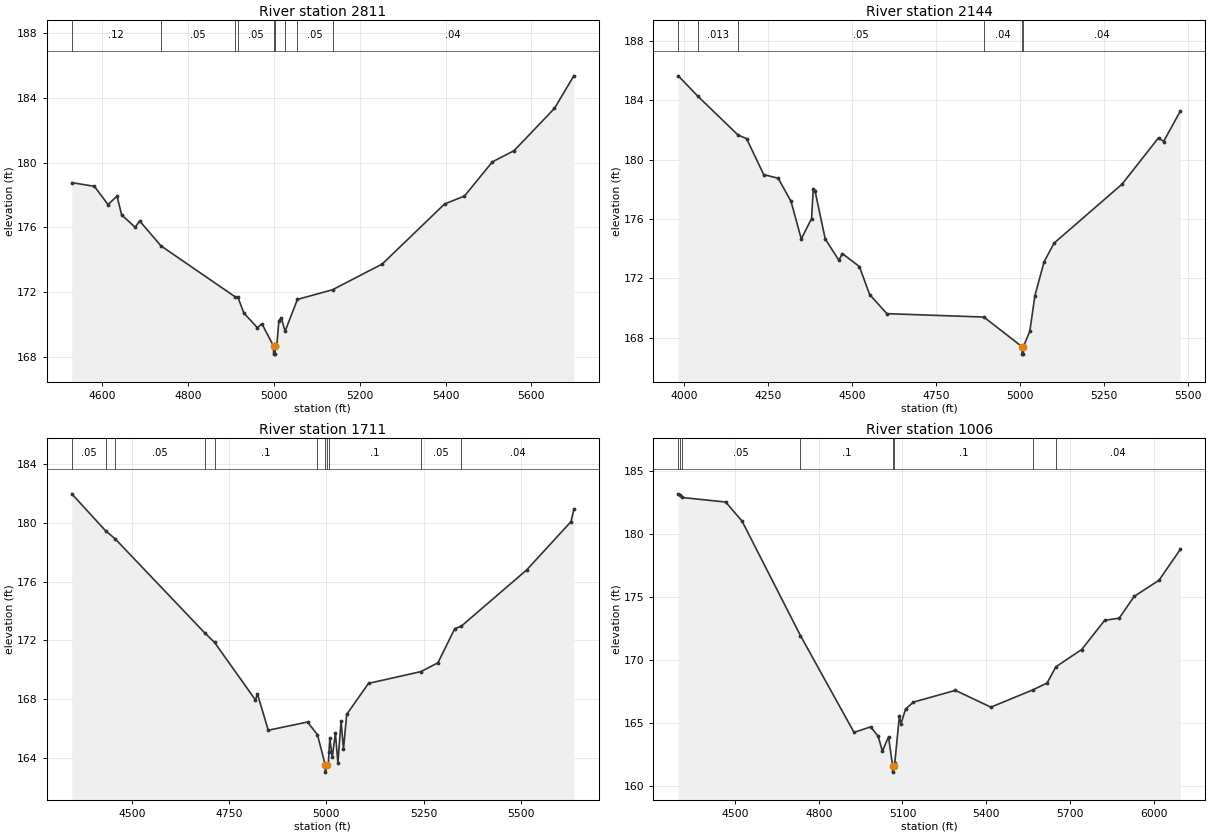
Type RM Length L Ch R = 1,2811,667,667,667
BEGIN DESCRIPTION:
TRIB 3_1 TO FIFTEENMILE CREEK 4.0
END DESCRIPTION:
XS GIS Cut Line= 3
      2512675.03     13506525.01      2512225.00     13506375.00
      2511625.00     13506725.00
#Sta/Elev= 30
  4529.8  178.76  4582.5  178.53  4614.2  177.40  4635.2  177.93  4645.8  176.77
  4677.4  176.00  4687.9  176.39  4737.5  174.85  4910.9  171.69  4916.7  171.67
  4930.4  170.70  4962.0  169.79  4972.5  170.04  4999.5  168.66  4999.8  168.16
  5003.3  168.16  5003.5  168.66  5007.1  168.66  5012.0  170.23  5017.8  170.40
  5026.4  169.57  5055.2  171.54  5137.0  172.14  5252.7  173.73  5397.8  177.44
  5444.1  177.93  5509.0  180.04  5559.9  180.74  5653.7  183.35  5698.8  185.36
#Mann=9,-1,0
  4529.8    0.12       0  4737.5    0.05       0  4910.9   0.013       0
  4916.7    0.05       0  4999.5    0.05       0  5003.5    0.05       0
  5026.4    0.04       0  5055.2    0.05       0  5137.0    0.04       0
Bank Sta=4999.5,5003.5
Exp/Cntr=0.3,0.1

Type RM Length L Ch R = 1,2144,433,433,433
BEGIN DESCRIPTION:
TRIB 3_1 TO FIFTEENMILE CREEK 3.0
END DESCRIPTION:
XS GIS Cut Line= 3
      2512874.99     13505775.00      2511874.15     13505964.96
      2511474.99     13506225.00
#Sta/Elev= 30
  3981.6  185.66  4040.7  184.27  4159.5  181.67  4185.2  181.42  4236.1  179.00
  4279.2  178.75  4317.5  177.19  4348.0  174.66  4378.6  176.03  4383.7  178.04
  4388.8  177.92  4419.3  174.66  4460.0  173.22  4470.2  173.67  4521.0  172.80
  4551.6  170.91  4602.9  169.62  4891.8  169.39  5005.4  167.39  5005.7  166.89
  5009.2  166.89  5009.4  167.39  5028.5  168.43  5043.6  170.82  5070.9  173.11
  5100.9  174.38  5303.1  178.35  5411.8  181.48  5426.9  181.23  5476.7  183.28
#Mann=6,-1,0
  3981.6    0.05       0  4040.7   0.013       0  4159.5    0.05       0
  4891.8    0.04       0  5005.4    0.04       0  5009.4    0.04       0
Bank Sta=5005.4,5009.4
Exp/Cntr=0.3,0.1

Type RM Length L Ch R = 1,1711,705,705,705
BEGIN DESCRIPTION:
TRIB 3_1 TO FIFTEENMILE CREEK 2.0
END DESCRIPTION:
XS GIS Cut Line= 3
      2512675.03     13505675.00      2512025.99     13505585.27
      2511525.03     13505974.97
#Sta/Elev= 30
  4346.0  181.97  4434.1  179.42  4457.0  178.92  4687.1  172.52  4712.7  171.86
  4818.0  167.94  4823.1  168.35  4850.8  165.88  4951.7  166.44  4977.2  165.58
  4997.1  163.53  4997.4  163.03  5001.2  163.53  5005.0  163.53  5006.9  164.41
  5008.9  165.34  5015.2  164.04  5023.3  165.69  5029.7  163.66  5037.8  166.49
  5044.1  164.61  5052.3  166.96  5108.4  169.07  5242.9  169.87  5286.7  170.47
  5330.1  172.80  5346.2  172.95  5514.7  176.79  5628.7  180.08  5635.9  180.91
#Mann=11,-1,0
  4346.0    0.05       0  4434.1    0.12       0  4457.0    0.05       0
  4687.1    0.12       0  4712.7     0.1       0  4977.2    0.05       0
  4997.1    0.05       0  5001.2    0.05       0  5006.9     0.1       0
  5242.9    0.05       0  5346.2    0.04       0
Bank Sta=4997.1,5001.2
Exp/Cntr=0.3,0.1

Type RM Length L Ch R = 1,1006,0,0,0
BEGIN DESCRIPTION:
TRIB 3_1 TO FIFTEENMILE CREEK 1.0
END DESCRIPTION:
XS GIS Cut Line= 3
      2512833.17     13505443.92      2512224.62     13505024.67
      2511280.00     13505503.41
#Sta/Elev= 30
  4297.0  183.16  4304.9  183.06  4310.2  182.87  4466.7  182.51  4525.5  181.00
  4734.5  171.93  4926.6  164.25  4986.1  164.69  5013.1  163.94  5028.0  162.76
  5050.1  163.90  5064.7  161.60  5064.9  161.10  5068.8  161.60  5072.4  161.81
  5089.0  165.55  5094.6  164.93  5111.3  166.11  5139.2  166.65  5289.5  167.58
  5416.7  166.25  5567.9  167.63  5617.9  168.16  5649.4  169.45  5741.9  170.82
  5824.0  173.13  5876.4  173.31  5929.7  175.03  6018.8  176.31  6095.0  178.76
#Mann=8,-1,0
  4297.0    0.05       0  4304.9   0.013       0  4310.2    0.05       0
  4734.5     0.1       0  5064.7    0.05       0  5068.8     0.1       0
  5567.9    0.05       0  5649.4    0.04       0
Bank Sta=5064.7,5068.8
Exp/Cntr=0.3,0.1

Chan Stop Cuts=-1