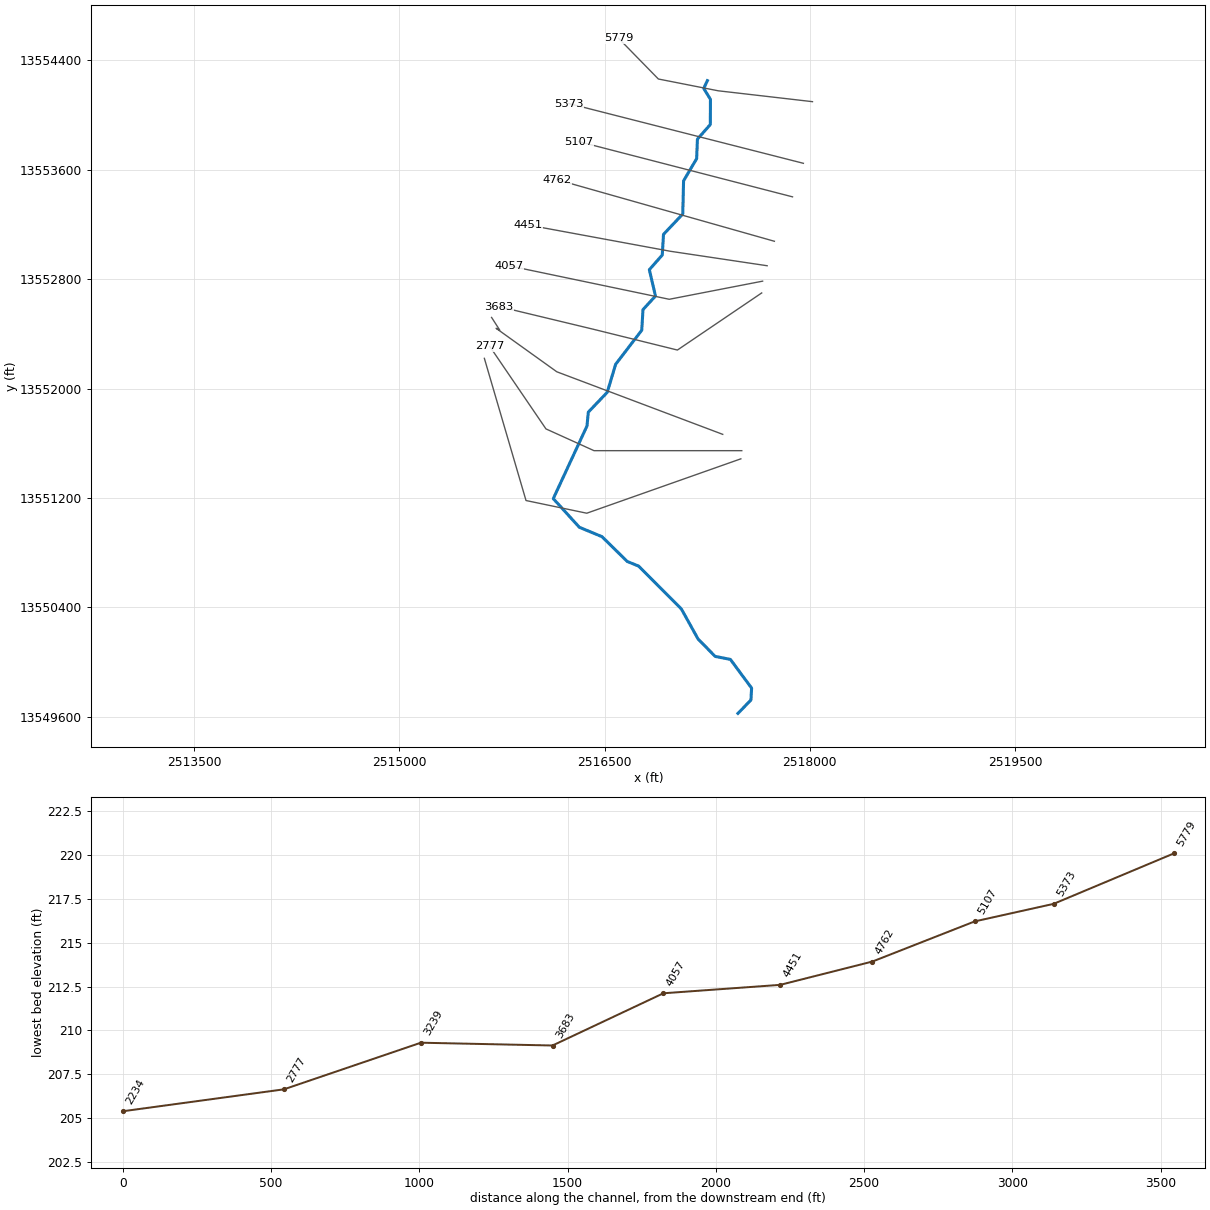
--- TRIB 3_1 TO FIVEMILE CREEK.prj (project) ---

Proj Title=TRIB 3_1 TO FIVEMILE CREEK Base Level Engineering
Current Plan=p01
Default Exp/Contr=0.3,0.1
English Units
Geom File=g01
Flow File=f01
Plan File=p01
BEGIN DESCRIPTION:
TRIB 3_1 TO FIVEMILE CREEK
END DESCRIPTION:

--- TRIB 3_1 TO FIVEMILE CREEK.p01 (plan) ---

Plan Title=Multiple Run
Short Identifier=Multiple
Geom File=g01
Flow File=f01
Subcritical Flow
K Sum by GR= 0
Std Step Tol= 0.01
Critical Tol= 0.01
Num of Std Step Trials= 20
Max Error Tol= 0.3
Flow Tol Ratio= 0.001
Split Flow NTrial= 30
Split Flow Tol= 0.02
Split Flow Ratio= 0.02
Log Output Level= 0
Friction Slope Method= 1
Unsteady Friction Slope Method= 2
Unsteady Bridges Friction Slope Method= 1
Parabolic Critical Depth
Global Vel Dist=  1 , 1 , 1
Global Log Level= 0
CheckData=True
Encroach Param= -1, 0, 0, 0
BEGIN DESCRIPTION:
Multiple Run
END DESCRIPTION:

--- TRIB 3_1 TO FIVEMILE CREEK.f01 (steady flow) ---

Flow Title=Multiple
Number of Profiles=7
Profile Names=10-year,25-year,50-year,1pct_min,100-year,1pct_plu,500-year
River Rch & RM= TRIB 3_1 TO FIVE,Reach-1,5779
     576     916    1218     784    1563    3119    2553
River Rch & RM= TRIB 3_1 TO FIVE,Reach-1,5373
     752    1212    1626    1055    2105    4201    3496
Boundary for River Rch & Prof#=TRIB 3_1 TO FIVE,Reach-1,1
Up Type=0
Dn Type=3
Dn Slope=0.005
Boundary for River Rch & Prof#=TRIB 3_1 TO FIVE,Reach-1,2
Up Type=0
Dn Type=3
Dn Slope=0.005
Boundary for River Rch & Prof#=TRIB 3_1 TO FIVE,Reach-1,3
Up Type=0
Dn Type=3
Dn Slope=0.005
Boundary for River Rch & Prof#=TRIB 3_1 TO FIVE,Reach-1,4
Up Type=0
Dn Type=3
Dn Slope=0.005
Boundary for River Rch & Prof#=TRIB 3_1 TO FIVE,Reach-1,5
Up Type=0
Dn Type=3
Dn Slope=0.005
Boundary for River Rch & Prof#=TRIB 3_1 TO FIVE,Reach-1,6
Up Type=0
Dn Type=3
Dn Slope=0.005
Boundary for River Rch & Prof#=TRIB 3_1 TO FIVE,Reach-1,7
Up Type=0
Dn Type=3
Dn Slope=0.005

--- TRIB 3_1 TO FIVEMILE CREEK.g01 (geometry) ---

Geom Title=Existing Conditions

River Reach=TRIB 3_1 TO FIVE,Reach-1
Reach XY= 30
      2517251.40     13554251.40      2517224.60     13554194.96
      2517273.80     13554114.51      2517272.94     13553930.86
      2517178.56     13553823.53      2517172.75     13553680.93
      2517077.24     13553519.07      2517071.46     13553276.46
      2516930.47     13553127.45      2516921.44     13552976.47
      2516826.97     13552869.11      2516871.86     13552676.64
      2516780.48     13552577.44      2516771.45     13552426.47
      2516580.54     13552177.42      2516519.17     13551972.70
      2516380.52     13551827.43      2516371.17     13551726.59
      2516124.59     13551195.13      2516315.32     13550985.76
      2516481.06     13550916.86      2516665.32     13550735.78
      2516748.47     13550701.98      2517061.37     13550388.21
      2517183.16     13550168.95      2517308.27     13550041.47
      2517419.53     13550019.74      2517574.77     13549809.78
      2517569.67     13549722.55      2517475.00     13549625.00

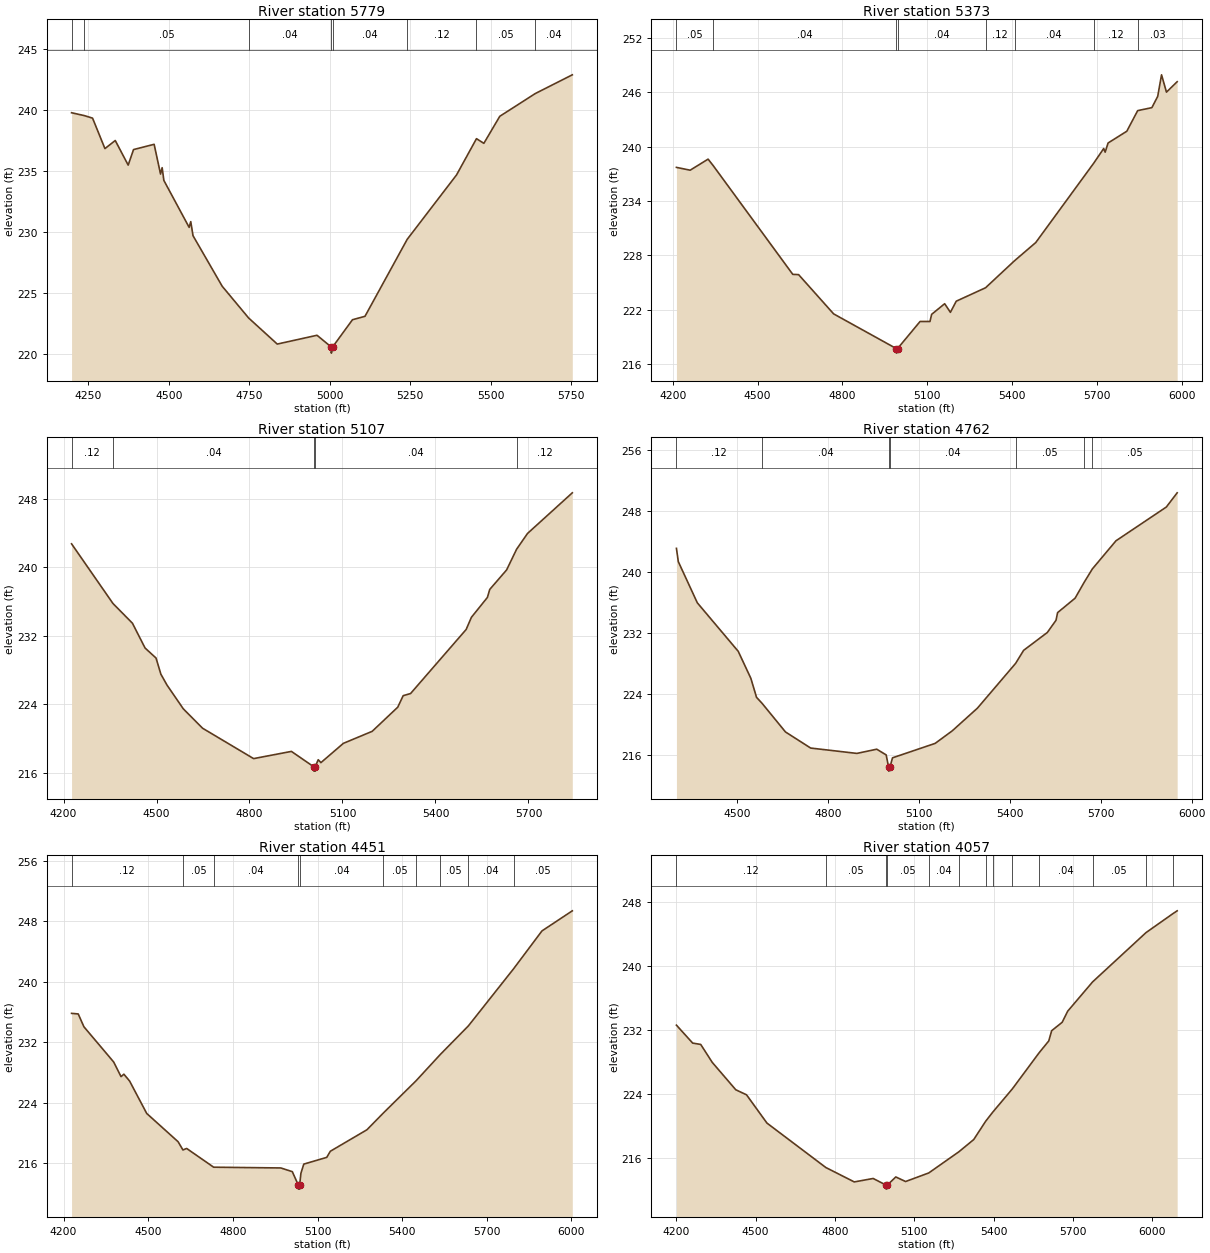
Type RM Length L Ch R = 1,5779,406,406,406
BEGIN DESCRIPTION:
LGII4555
END DESCRIPTION:
XS GIS Cut Line= 4
      2518019.77     13554097.77      2517330.42     13554177.31
      2516892.96     13554263.48      2516602.19     13554560.85
#Sta/Elev= 30
  4198.1  239.75  4237.1  239.52  4263.3  239.31  4301.7  236.82  4333.8  237.48
  4374.0  235.47  4390.6  236.74  4454.6  237.17  4474.5  234.74  4479.5  235.26
  4484.8  234.22  4563.4  230.38  4568.4  230.85  4575.4  229.70  4666.0  225.57
  4748.3  222.97  4837.1  220.84  4960.7  221.56  5004.9  220.60  5005.2  220.10
  5009.0  220.60  5070.8  222.83  5109.7  223.11  5240.8  229.40  5394.2  234.67
  5456.1  237.63  5479.0  237.25  5528.5  239.46  5638.8  241.32  5753.8  242.85
#Mann=8,-1,0
  4198.1    0.04       0  4237.1    0.05       0  4748.3    0.04       0
  5004.9    0.04       0  5009.0    0.04       0  5240.8    0.12       0
  5456.1    0.05       0  5638.8    0.04       0
Bank Sta=5004.9,5009
Exp/Cntr=0.3,0.1

Type RM Length L Ch R = 1,5373,266,266,266
BEGIN DESCRIPTION:
LGII4554
END DESCRIPTION:
XS GIS Cut Line= 2
      2517953.43     13553647.06      2516238.34     13554084.11
#Sta/Elev= 30
  4213.3  237.71  4261.9  237.40  4325.2  238.62  4343.8  237.88  4624.5  225.91
  4645.1  225.88  4768.9  221.55  4990.6  217.72  4990.9  217.22  4994.8  217.72
  5074.5  220.71  5109.5  220.71  5115.4  221.50  5161.4  222.67  5181.7  221.72
  5202.4  222.95  5305.9  224.43  5408.3  227.41  5483.4  229.42  5688.2  238.17
  5723.5  239.79  5728.7  239.39  5739.0  240.40  5805.3  241.70  5843.6  243.97
  5893.8  244.30  5914.4  245.54  5928.0  247.92  5945.4  246.01  5983.2  247.16
#Mann=8,-1,0
  4213.3    0.05       0  4343.8    0.04       0  4990.6    0.04       0
  4994.8    0.04       0  5305.9    0.12       0  5408.3    0.04       0
  5688.2    0.12       0  5843.6    0.03       0
Bank Sta=4990.6,4994.8
Exp/Cntr=0.3,0.1

Type RM Length L Ch R = 1,5107,345,345,345
BEGIN DESCRIPTION:
LGII4553
END DESCRIPTION:
XS GIS Cut Line= 2
      2517873.93     13553401.81      2516309.83     13553806.09
#Sta/Elev= 30
  4226.0  242.73  4359.6  235.77  4422.4  233.47  4463.1  230.58  4498.5  229.41
  4514.1  227.53  4534.0  226.25  4586.4  223.49  4648.4  221.23  4813.3  217.68
  4935.2  218.52  5007.8  216.72  5008.0  216.22  5011.7  216.22  5012.0  216.72
  5021.7  217.55  5030.5  217.21  5102.9  219.46  5195.8  220.86  5278.4  223.68
  5295.8  225.02  5319.7  225.27  5499.0  232.74  5516.0  234.16  5567.6  236.48
  5575.1  237.41  5629.6  239.69  5661.8  242.10  5697.0  243.94  5841.5  248.68
#Mann=5,-1,0
  4226.0    0.12       0  4359.6    0.04       0  5007.8    0.04       0
  5012.0    0.04       0  5661.8    0.12       0
Bank Sta=5007.8,5012
Exp/Cntr=0.3,0.1

Type RM Length L Ch R = 1,4762,311,311,311
BEGIN DESCRIPTION:
LGII4552
END DESCRIPTION:
XS GIS Cut Line= 2
      2517741.37     13553077.03      2516150.59     13553527.75
#Sta/Elev= 30
  4298.8  243.09  4305.0  241.35  4367.8  235.96  4502.9  229.61  4544.5  226.08
  4563.3  223.59  4582.1  222.78  4658.8  219.06  4742.0  216.95  4894.6  216.25
  4960.2  216.80  4991.4  216.05  4999.5  214.43  4999.8  213.93  5003.7  214.43
  5012.2  215.67  5153.0  217.56  5209.7  219.21  5292.8  222.18  5418.7  228.03
  5445.2  229.74  5523.5  232.08  5552.2  233.68  5557.4  234.68  5615.0  236.56
  5644.9  238.63  5672.0  240.39  5750.1  244.08  5916.4  248.50  5952.2  250.36
#Mann=7,-1,0
  4298.8    0.12       0  4582.1    0.04       0  4999.5    0.04       0
  5003.7    0.04       0  5418.7    0.05       0  5644.9    0.04       0
  5672.0    0.05       0
Bank Sta=4999.5,5003.7
Exp/Cntr=0.3,0.1

Type RM Length L Ch R = 1,4451,394,394,394
BEGIN DESCRIPTION:
LGII4551
END DESCRIPTION:
XS GIS Cut Line= 3
      2517688.34     13552898.07      2516979.13     13553004.12
      2515939.22     13553196.20
#Sta/Elev= 30
  4228.3  235.85  4251.9  235.77  4272.1  234.07  4377.4  229.42  4403.6  227.48
  4413.7  227.80  4433.9  226.90  4494.6  222.61  4605.8  218.87  4623.0  217.78
  4636.1  217.98  4731.9  215.50  4969.9  215.40  5010.6  214.91  5032.3  213.10
  5032.6  212.60  5036.3  212.60  5036.5  213.10  5041.1  214.70  5051.3  215.91
  5132.6  216.80  5145.4  217.61  5275.0  220.45  5333.3  222.67  5449.7  226.95
  5534.3  230.38  5634.8  234.20  5794.7  241.74  5895.3  246.75  6002.9  249.41
#Mann=10,-1,0
  4228.3    0.12       0  4623.0    0.05       0  4731.9    0.04       0
  5032.3    0.04       0  5036.5    0.04       0  5333.3    0.05       0
  5449.7    0.04       0  5534.3    0.05       0  5634.8    0.04       0
  5794.7    0.05       0
Bank Sta=5032.3,5036.5
Exp/Cntr=0.3,0.1

Type RM Length L Ch R = 1,4057,374,374,374
BEGIN DESCRIPTION:
LGII4550
END DESCRIPTION:
XS GIS Cut Line= 3
      2517655.25     13552785.39      2516972.50     13552652.82
      2515799.65     13552897.99
#Sta/Elev= 30
  4200.4  232.60  4261.8  230.36  4292.3  230.19  4335.9  227.95  4424.8  224.53
  4465.5  223.90  4542.7  220.37  4765.4  214.82  4873.0  213.02  4944.4  213.45
  4993.4  212.62  4993.7  212.12  4997.7  212.62  5030.0  213.64  5067.0  213.07
  5154.6  214.14  5268.8  216.79  5324.7  218.31  5369.9  220.60  5397.3  221.76
  5471.0  224.65  5572.0  229.15  5608.5  230.63  5619.5  231.91  5659.3  232.96
  5680.0  234.34  5774.2  238.00  5976.3  244.16  6077.3  246.51  6094.1  246.88
#Mann=13,-1,0
  4200.4    0.12       0  4765.4    0.05       0  4993.4    0.05       0
  4997.7    0.05       0  5154.6    0.04       0  5268.8    0.12       0
  5369.9    0.05       0  5397.3    0.04       0  5471.0    0.05       0
  5572.0    0.04       0  5774.2    0.05       0  5976.3    0.04       0
  6077.3    0.05       0
Bank Sta=4993.4,4997.7
Exp/Cntr=0.3,0.1

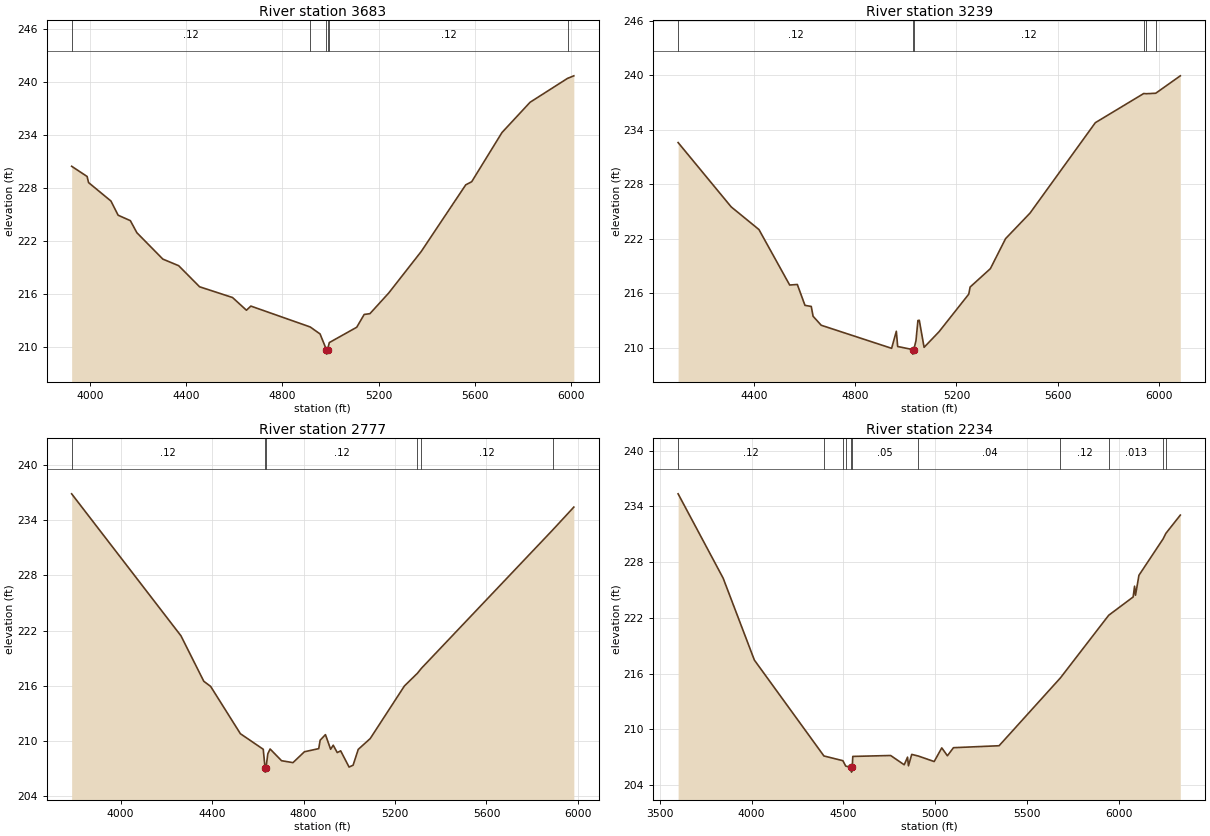
Type RM Length L Ch R = 1,3683,444,444,444
BEGIN DESCRIPTION:
LGII4549
END DESCRIPTION:
XS GIS Cut Line= 4
      2517648.58     13552699.22      2517032.15     13552281.64
      2516415.73     13552434.09      2515728.16     13552599.37
#Sta/Elev= 30
  3924.4  230.45  3988.7  229.29  3994.7  228.60  4087.6  226.51  4117.5  224.90
  4168.4  224.28  4195.5  222.91  4303.3  219.92  4369.2  219.17  4456.0  216.78
  4593.0  215.56  4650.7  214.12  4669.0  214.59  4915.7  212.22  4956.6  211.43
  4983.2  209.64  4983.5  209.14  4987.6  209.64  4995.0  210.45  5109.0  212.19
  5139.9  213.64  5163.8  213.73  5241.5  216.06  5376.9  220.78  5561.8  228.34
  5586.7  228.70  5712.6  234.28  5829.2  237.71  5984.8  240.42  6011.1  240.71
#Mann=6,-1,0
  3924.4    0.12       0  4915.7    0.05       0  4983.2    0.05       0
  4987.6    0.05       0  4995.0    0.12       0  5984.8    0.04       0
Bank Sta=4983.2,4987.6
Exp/Cntr=0.3,0.1

Type RM Length L Ch R = 1,3239,462,462,462
BEGIN DESCRIPTION:
LGII4548
END DESCRIPTION:
XS GIS Cut Line= 5
      2517363.58     13551665.21      2516150.60     13552122.56
      2515706.51     13552440.72      2515733.02     13552427.46
      2515673.47     13552520.09
#Sta/Elev= 30
  4101.4  232.60  4310.8  225.52  4420.5  223.02  4541.8  216.91  4572.0  216.97
  4602.2  214.67  4627.0  214.55  4634.2  213.47  4666.3  212.48  4944.2  209.94
  4962.8  211.82  4968.1  210.14  5027.4  209.80  5027.7  209.30  5031.9  209.80
  5040.4  210.79  5048.0  213.00  5053.4  213.03  5072.4  210.05  5131.2  211.76
  5248.8  215.91  5254.1  216.69  5334.0  218.71  5394.1  222.02  5490.5  224.83
  5748.4  234.79  5939.3  238.00  5950.1  237.98  5986.7  238.03  6083.8  239.95
#Mann=6,-1,0
  4101.4    0.12       0  5027.4    0.05       0  5031.9    0.12       0
  5939.3    0.05       0  5950.1    0.12       0  5986.7    0.05       0
Bank Sta=5027.4,5031.9
Exp/Cntr=0.3,0.1

Type RM Length L Ch R = 1,2777,543,543,543
BEGIN DESCRIPTION:
LGII4547
END DESCRIPTION:
XS GIS Cut Line= 4
      2517502.77     13551545.91      2516422.36     13551545.91
      2516071.06     13551704.99      2515660.11     13552308.15
#Sta/Elev= 30
  3786.2  236.84  4264.0  221.44  4364.0  216.50  4394.0  215.94  4524.0  210.81
  4624.0  209.12  4631.7  207.14  4632.0  206.64  4636.2  207.14  4644.0  208.63
  4654.0  209.15  4704.0  207.88  4754.0  207.67  4804.0  208.85  4866.6  209.19
  4872.9  210.11  4896.0  210.71  4918.6  209.12  4930.0  209.56  4947.6  208.76
  4962.5  208.95  4999.3  207.19  5016.9  207.39  5039.4  209.11  5091.7  210.28
  5241.3  215.99  5298.2  217.37  5315.4  217.90  5889.3  232.91  5982.1  235.40
#Mann=6,-1,0
  3786.2    0.12       0  4631.7    0.05       0  4636.2    0.12       0
  5298.2   0.013       0  5315.4    0.12       0  5889.3    0.05       0
Bank Sta=4631.7,4636.2
Exp/Cntr=0.3,0.1

Type RM Length L Ch R = 1,2234,0,0,0
BEGIN DESCRIPTION:
LGII4546
END DESCRIPTION:
XS GIS Cut Line= 4
      2517496.16     13551486.27      2516369.33     13551088.56
      2515925.24     13551181.36      2515620.63     13552221.02
#Sta/Elev= 30
  3600.5  235.34  3845.6  226.26  4015.3  217.45  4393.7  207.13  4496.9  206.62
  4512.4  206.04  4543.3  205.89  4543.6  205.39  4547.8  205.89  4550.8  207.08
  4756.7  207.18  4830.5  206.18  4848.6  207.00  4853.7  206.07  4871.4  207.30
  4907.5  207.12  4993.5  206.53  5034.8  208.00  5065.5  207.15  5098.5  208.02
  5346.7  208.23  5680.7  215.54  5942.9  222.27  6076.1  224.24  6083.6  225.40
  6088.8  224.43  6107.4  226.57  6239.2  230.50  6254.2  231.09  6332.5  233.05
#Mann=11,-1,0
  3600.5    0.12       0  4393.7    0.05       0  4496.9   0.013       0
  4512.4    0.05       0  4543.3    0.04       0  4547.8    0.05       0
  4907.5    0.04       0  5680.7    0.12       0  5942.9   0.013       0
  6239.2    0.12       0  6254.2    0.05       0
Bank Sta=4543.3,4547.8
Exp/Cntr=0.3,0.1

Chan Stop Cuts=-1