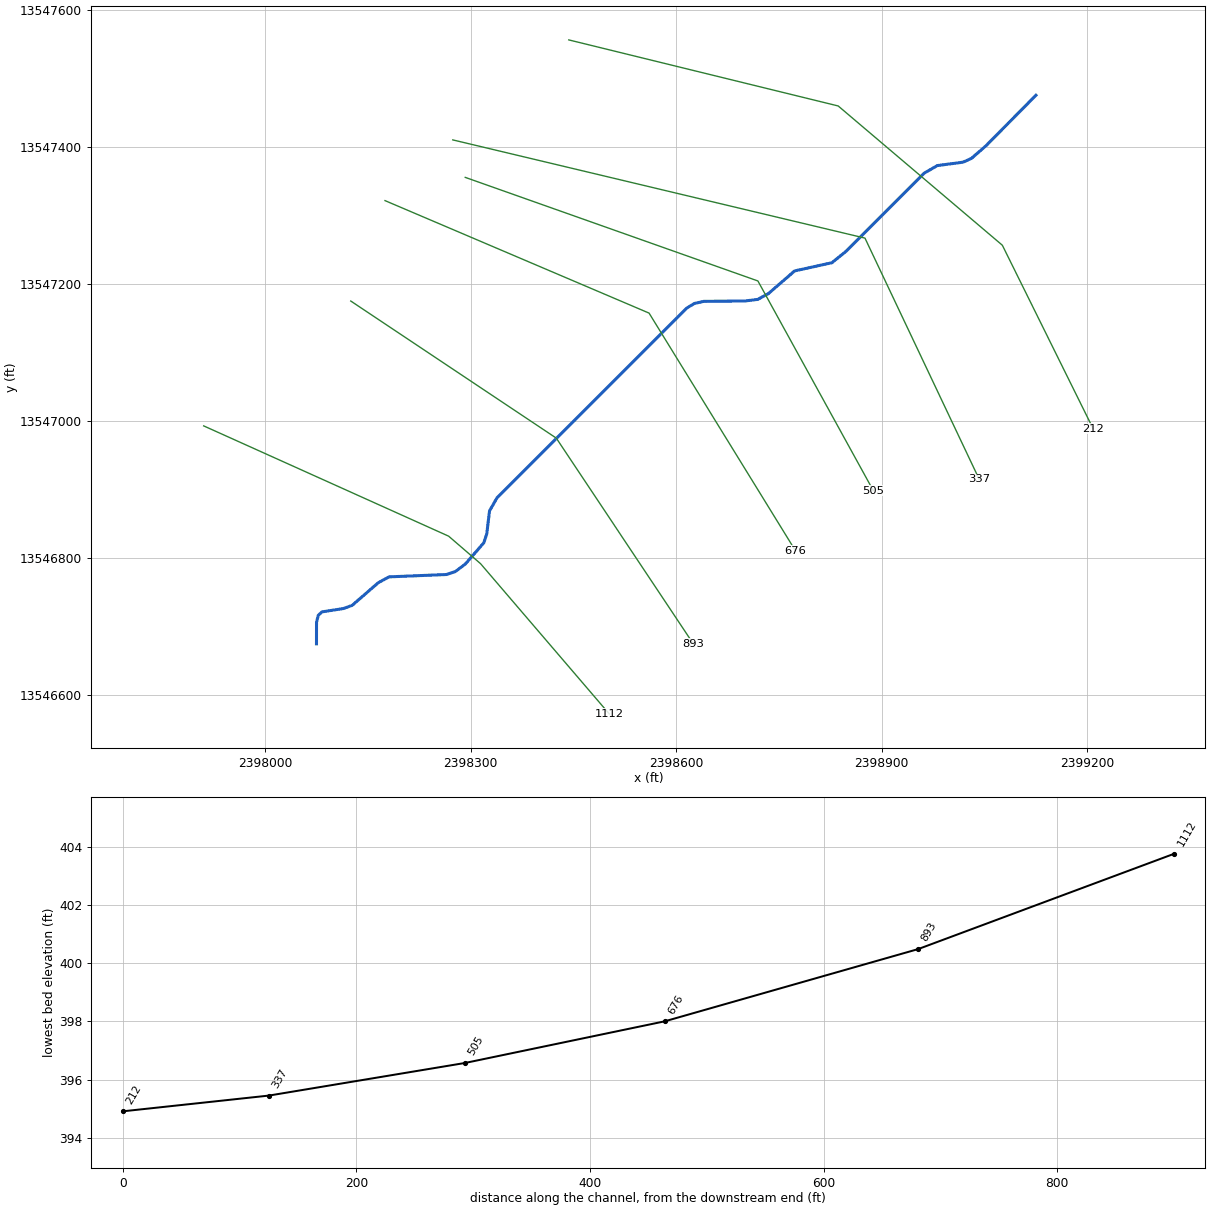
--- TRIB 3_1 TO THOMAS CREEK.prj (project) ---

Proj Title=TRIB 3_1 TO THOMAS CREEK Base Level Engineering
Current Plan=p01
Default Exp/Contr=0.3,0.1
English Units
Geom File=g01
Flow File=f01
Plan File=p01
BEGIN DESCRIPTION:
TRIB 3_1 TO THOMAS CREEK
END DESCRIPTION:

--- TRIB 3_1 TO THOMAS CREEK.p01 (plan) ---

Plan Title=Multiple Run
Short Identifier=Multiple
Geom File=g01
Flow File=f01
Subcritical Flow
K Sum by GR= 0
Std Step Tol= 0.01
Critical Tol= 0.01
Num of Std Step Trials= 20
Max Error Tol= 0.3
Flow Tol Ratio= 0.001
Split Flow NTrial= 30
Split Flow Tol= 0.02
Split Flow Ratio= 0.02
Log Output Level= 0
Friction Slope Method= 1
Unsteady Friction Slope Method= 2
Unsteady Bridges Friction Slope Method= 1
Parabolic Critical Depth
Global Vel Dist=  1 , 1 , 1
Global Log Level= 0
CheckData=True
Encroach Param= -1, 0, 0, 0
BEGIN DESCRIPTION:
Multiple Run
END DESCRIPTION:

--- TRIB 3_1 TO THOMAS CREEK.f01 (steady flow) ---

Flow Title=Multiple
Number of Profiles=7
Profile Names=10-year,25-year,50-year,1pct_min,100-year,1pct_plu,500-year
River Rch & RM= TRIB 3_1 TO THOM,Reach-1,1112
     432     689     918     593    1184    2362    1948
River Rch & RM= TRIB 3_1 TO THOM,Reach-1,676
     456     729     973     630    1258    2510    2078
Boundary for River Rch & Prof#=TRIB 3_1 TO THOM,Reach-1,1
Up Type=0
Dn Type=3
Dn Slope=0.005
Boundary for River Rch & Prof#=TRIB 3_1 TO THOM,Reach-1,2
Up Type=0
Dn Type=3
Dn Slope=0.005
Boundary for River Rch & Prof#=TRIB 3_1 TO THOM,Reach-1,3
Up Type=0
Dn Type=3
Dn Slope=0.005
Boundary for River Rch & Prof#=TRIB 3_1 TO THOM,Reach-1,4
Up Type=0
Dn Type=3
Dn Slope=0.005
Boundary for River Rch & Prof#=TRIB 3_1 TO THOM,Reach-1,5
Up Type=0
Dn Type=3
Dn Slope=0.005
Boundary for River Rch & Prof#=TRIB 3_1 TO THOM,Reach-1,6
Up Type=0
Dn Type=3
Dn Slope=0.005
Boundary for River Rch & Prof#=TRIB 3_1 TO THOM,Reach-1,7
Up Type=0
Dn Type=3
Dn Slope=0.005

--- TRIB 3_1 TO THOMAS CREEK.g01 (geometry) ---

Geom Title=Existing Conditions

River Reach=TRIB 3_1 TO THOM,Reach-1
Reach XY= 30
      2398075.00     13546675.00      2398075.06     13546706.56
      2398077.61     13546716.60      2398082.99     13546721.60
      2398114.13     13546726.47      2398127.00     13546731.04
      2398165.29     13546764.21      2398180.95     13546772.69
      2398264.67     13546776.10      2398277.67     13546780.42
      2398292.13     13546791.30      2398319.26     13546822.43
      2398323.52     13546835.47      2398327.55     13546868.91
      2398338.64     13546888.20      2398615.21     13547164.48
      2398626.50     13547171.39      2398640.22     13547174.48
      2398700.00     13547175.00      2398719.03     13547177.33
      2398734.65     13547185.84      2398772.83     13547218.86
      2398827.30     13547230.83      2398848.47     13547248.01
      2398961.79     13547361.37      2398981.04     13547372.48
      2399018.96     13547377.52      2399031.07     13547383.11
      2399051.86     13547401.20      2399125.00     13547475.00

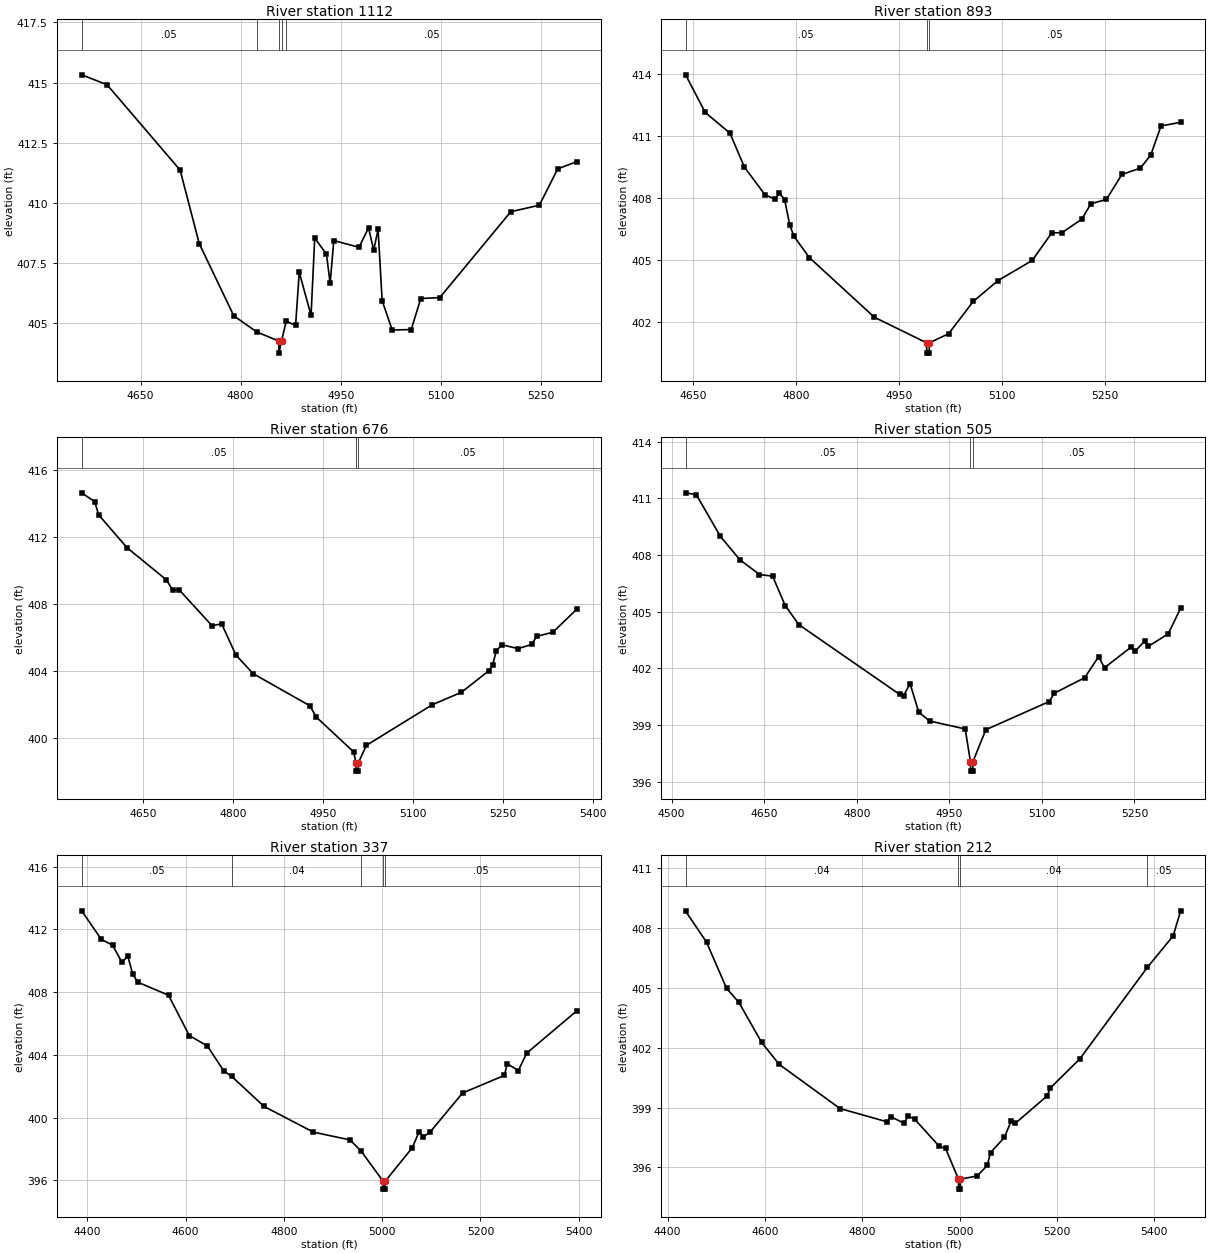
Type RM Length L Ch R = 1,1112,219,219,219
BEGIN DESCRIPTION:
TRIB 3_1 TO THOMAS CREEK 3.0
END DESCRIPTION:
XS GIS Cut Line= 4
      2397910.36     13546992.88      2398267.92     13546832.00
      2398314.40     13546791.97      2398502.36     13546572.74
#Sta/Elev= 30
  4561.7  415.32  4599.7  414.91  4709.3  411.36  4738.0  408.30  4789.8  405.30
  4824.2  404.63  4857.3  404.25  4857.5  403.75  4861.3  404.25  4868.4  405.08
  4882.4  404.90  4887.9  407.11  4905.6  405.32  4911.1  408.53  4928.7  407.87
  4934.2  406.65  4939.7  408.43  4977.5  408.15  4991.8  408.96  4999.5  408.03
  5006.1  408.89  5012.2  405.93  5027.3  404.71  5055.8  404.73  5070.1  406.02
  5098.6  406.06  5205.1  409.63  5247.9  409.90  5275.4  411.41  5303.9  411.71
#Mann=5,-1,0
  4561.7    0.05       0  4824.2    0.03       0  4857.3    0.05       0
  4861.3    0.03       0  4868.4    0.05       0
Bank Sta=4857.3,4861.3
Exp/Cntr=0.3,0.1

Type RM Length L Ch R = 1,893,217,217,217
BEGIN DESCRIPTION:
TRIB 3_1 TO THOMAS CREEK 2.0
END DESCRIPTION:
XS GIS Cut Line= 3
      2398125.02     13547174.99      2398425.00     13546975.00
      2398625.01     13546674.99
#Sta/Elev= 30
  4639.5  413.97  4668.0  412.15  4704.1  411.14  4725.1  409.50  4755.2  408.15
  4770.2  407.94  4776.2  408.24  4783.7  407.92  4791.2  406.69  4797.2  406.15
  4819.8  405.11  4914.4  402.22  4990.5  400.98  4990.8  400.48  4994.3  400.48
  4994.5  400.98  5022.6  401.42  5058.6  402.99  5094.7  404.00  5144.3  404.97
  5172.8  406.31  5187.8  406.32  5216.4  406.97  5229.9  407.72  5252.4  407.93
  5275.0  409.14  5302.0  409.45  5317.0  410.08  5332.0  411.49  5360.6  411.67
#Mann=3,-1,0
  4639.5    0.05       0  4990.5    0.05       0  4994.5    0.05       0
Bank Sta=4990.5,4994.5
Exp/Cntr=0.3,0.1

Type RM Length L Ch R = 1,676,171,171,171
BEGIN DESCRIPTION:
Mapping XS fa6be04b
END DESCRIPTION:
XS GIS Cut Line= 3
      2398174.98     13547321.41      2398560.37     13547157.36
      2398773.89     13546811.04
#Sta/Elev= 30
  4547.3  414.63  4569.1  414.10  4575.5  413.32  4622.7  411.36  4688.6  409.43
  4699.1  408.82  4710.3  408.82  4764.7  406.69  4780.8  406.80  4804.5  404.94
  4833.5  403.82  4927.7  401.91  4938.9  401.22  5000.9  399.15  5004.8  398.50
  5005.0  398.00  5008.5  398.00  5008.8  398.50  5022.2  399.54  5132.2  401.97
  5180.7  402.71  5226.9  404.01  5232.7  404.34  5239.1  405.20  5248.1  405.55
  5275.3  405.32  5297.9  405.57  5306.1  406.05  5333.2  406.30  5373.0  407.67
#Mann=3,-1,0
  4547.3    0.05       0  5004.8    0.05       0  5008.8    0.05       0
Bank Sta=5004.8,5008.8
Exp/Cntr=0.3,0.1

Type RM Length L Ch R = 1,505,168,168,168
BEGIN DESCRIPTION:
Mapping XS e3f21035
END DESCRIPTION:
XS GIS Cut Line= 3
      2398292.13     13547355.28      2398719.22     13547204.23
      2398887.65     13546898.46
#Sta/Elev= 30
  4522.8  411.29  4540.2  411.19  4578.9  409.00  4610.7  407.75  4642.5  406.97
  4663.8  406.88  4684.1  405.33  4706.2  404.32  4869.5  400.63  4875.9  400.55
  4886.5  401.20  4900.5  399.69  4918.3  399.22  4975.8  398.80  4984.3  397.07
  4984.6  396.57  4988.1  396.57  4988.3  397.07  5009.2  398.76  5111.9  400.25
  5120.1  400.69  5169.3  401.51  5191.9  402.62  5201.5  402.04  5245.0  403.14
  5250.8  402.90  5266.8  403.46  5272.5  403.17  5304.7  403.83  5324.9  405.19
#Mann=3,-1,0
  4522.8    0.05       0  4984.3    0.05       0  4988.3    0.05       0
Bank Sta=4984.3,4988.3
Exp/Cntr=0.3,0.1

Type RM Length L Ch R = 1,337,125,125,125
BEGIN DESCRIPTION:
Mapping XS 86004728
END DESCRIPTION:
XS GIS Cut Line= 3
      2398273.87     13547409.97      2398875.47     13547266.73
      2399042.14     13546915.16
#Sta/Elev= 30
  4388.5  413.19  4428.6  411.37  4451.3  411.00  4470.7  409.90  4482.2  410.32
  4492.5  409.15  4502.7  408.64  4565.3  407.81  4607.5  405.24  4644.5  404.57
  4677.5  402.99  4693.7  402.64  4759.7  400.72  4860.3  399.08  4934.5  398.59
  4957.5  397.86  5002.1  395.95  5002.4  395.45  5005.9  395.45  5006.1  395.95
  5061.4  398.09  5075.2  399.11  5084.1  398.79  5097.4  399.08  5163.8  401.58
  5248.9  402.70  5254.4  403.44  5277.1  403.01  5294.3  404.12  5396.0  406.81
#Mann=5,-1,0
  4388.5    0.05       0  4693.7    0.04       0  4957.5    0.05       0
  5002.1    0.05       0  5006.1    0.05       0
Bank Sta=5002.1,5006.1
Exp/Cntr=0.3,0.1

Type RM Length L Ch R = 1,212,0,0,0
BEGIN DESCRIPTION:
Mapping XS 01f6aa68
END DESCRIPTION:
XS GIS Cut Line= 4
      2398443.19     13547555.79      2398836.41     13547459.44
      2399075.99     13547256.32      2399208.33     13546989.04
#Sta/Elev= 30
  4437.0  408.84  4480.0  407.29  4521.2  404.97  4546.2  404.28  4593.3  402.26
  4629.4  401.16  4754.2  398.95  4851.5  398.28  4858.1  398.55  4886.6  398.20
  4893.2  398.58  4907.5  398.42  4958.0  397.06  4971.2  396.95  4997.7  395.41
  4998.0  394.91  5001.5  394.91  5001.7  395.41  5036.1  395.57  5056.9  396.10
  5063.5  396.74  5092.0  397.50  5106.3  398.35  5114.0  398.20  5179.7  399.58
  5186.4  399.98  5246.7  401.43  5385.9  406.03  5438.7  407.60  5454.2  408.86
#Mann=4,-1,0
  4437.0    0.04       0  4997.7    0.04       0  5001.7    0.04       0
  5385.9    0.05       0
Bank Sta=4997.7,5001.7
Exp/Cntr=0.3,0.1

Chan Stop Cuts=-1