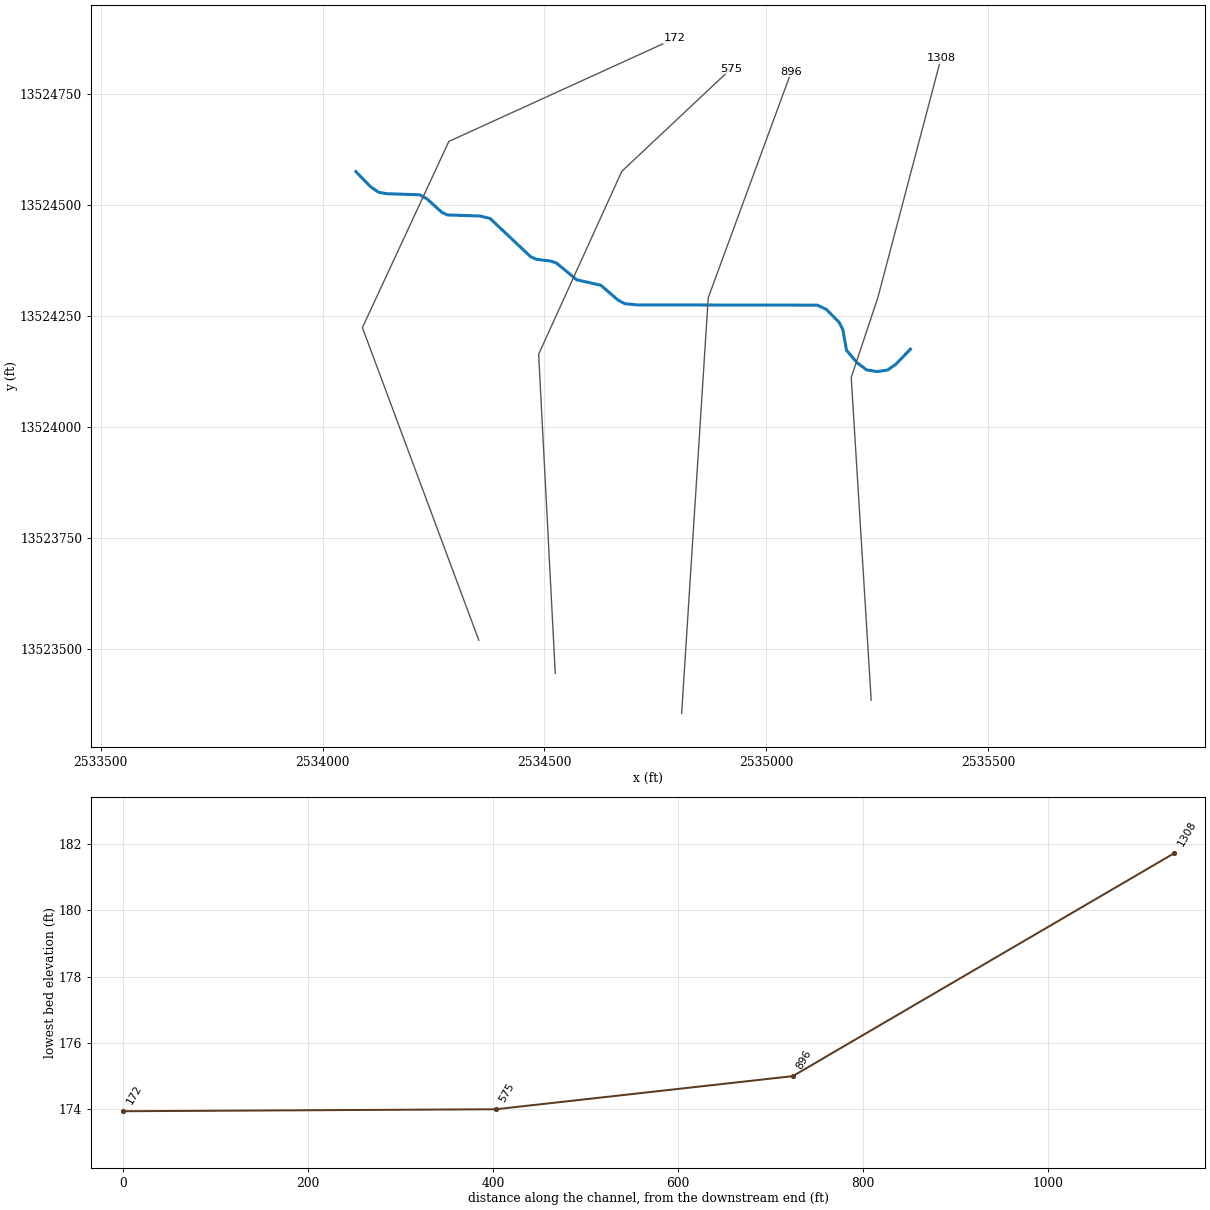
--- TRIB 3_1 TO TWELVEMILE CREEK.prj (project) ---

Proj Title=TRIB 3_1 TO TWELVEMILE CREEK Base Level Engineering
Current Plan=p01
Default Exp/Contr=0.3,0.1
English Units
Geom File=g01
Flow File=f01
Plan File=p01
BEGIN DESCRIPTION:
TRIB 3_1 TO TWELVEMILE CREEK
END DESCRIPTION:

--- TRIB 3_1 TO TWELVEMILE CREEK.p01 (plan) ---

Plan Title=Multiple Run
Short Identifier=Multiple
Geom File=g01
Flow File=f01
Subcritical Flow
K Sum by GR= 0
Std Step Tol= 0.01
Critical Tol= 0.01
Num of Std Step Trials= 20
Max Error Tol= 0.3
Flow Tol Ratio= 0.001
Split Flow NTrial= 30
Split Flow Tol= 0.02
Split Flow Ratio= 0.02
Log Output Level= 0
Friction Slope Method= 1
Unsteady Friction Slope Method= 2
Unsteady Bridges Friction Slope Method= 1
Parabolic Critical Depth
Global Vel Dist=  1 , 1 , 1
Global Log Level= 0
CheckData=True
Encroach Param= -1, 0, 0, 0
BEGIN DESCRIPTION:
Multiple Run
END DESCRIPTION:

--- TRIB 3_1 TO TWELVEMILE CREEK.f01 (steady flow) ---

Flow Title=Multiple
Number of Profiles=7
Profile Names=10-year,25-year,50-year,1pct_min,100-year,1pct_plu,500-year
River Rch & RM= TRIB 3_1 TO TWEL,Reach-1,1308
     375     579     756     479     956    1908    1509
Boundary for River Rch & Prof#=TRIB 3_1 TO TWEL,Reach-1,1
Up Type=0
Dn Type=3
Dn Slope=0.005
Boundary for River Rch & Prof#=TRIB 3_1 TO TWEL,Reach-1,2
Up Type=0
Dn Type=3
Dn Slope=0.005
Boundary for River Rch & Prof#=TRIB 3_1 TO TWEL,Reach-1,3
Up Type=0
Dn Type=3
Dn Slope=0.005
Boundary for River Rch & Prof#=TRIB 3_1 TO TWEL,Reach-1,4
Up Type=0
Dn Type=3
Dn Slope=0.005
Boundary for River Rch & Prof#=TRIB 3_1 TO TWEL,Reach-1,5
Up Type=0
Dn Type=3
Dn Slope=0.005
Boundary for River Rch & Prof#=TRIB 3_1 TO TWEL,Reach-1,6
Up Type=0
Dn Type=3
Dn Slope=0.005
Boundary for River Rch & Prof#=TRIB 3_1 TO TWEL,Reach-1,7
Up Type=0
Dn Type=3
Dn Slope=0.005

--- TRIB 3_1 TO TWELVEMILE CREEK.g01 (geometry) ---

Geom Title=Existing Conditions

River Reach=TRIB 3_1 TO TWEL,Reach-1
Reach XY= 30
      2535325.00     13524175.00      2535291.91     13524140.74
      2535273.34     13524127.65      2535249.80     13524124.24
      2535226.35     13524127.98      2535204.50     13524144.29
      2535180.76     13524172.42      2535172.54     13524219.11
      2535164.37     13524235.04      2535135.12     13524264.65
      2535114.72     13524274.01      2534709.82     13524274.56
      2534680.93     13524277.24      2534665.33     13524285.80
      2534627.18     13524318.88      2534572.80     13524331.08
      2534527.19     13524368.90      2534514.30     13524373.30
      2534481.04     13524377.51      2534468.95     13524383.16
      2534377.42     13524469.46      2534354.95     13524474.87
      2534280.98     13524477.36      2534268.96     13524483.19
      2534234.64     13524514.12      2534219.04     13524522.68
      2534145.08     13524525.19      2534126.40     13524528.39
      2534107.95     13524541.12      2534075.00     13524575.00

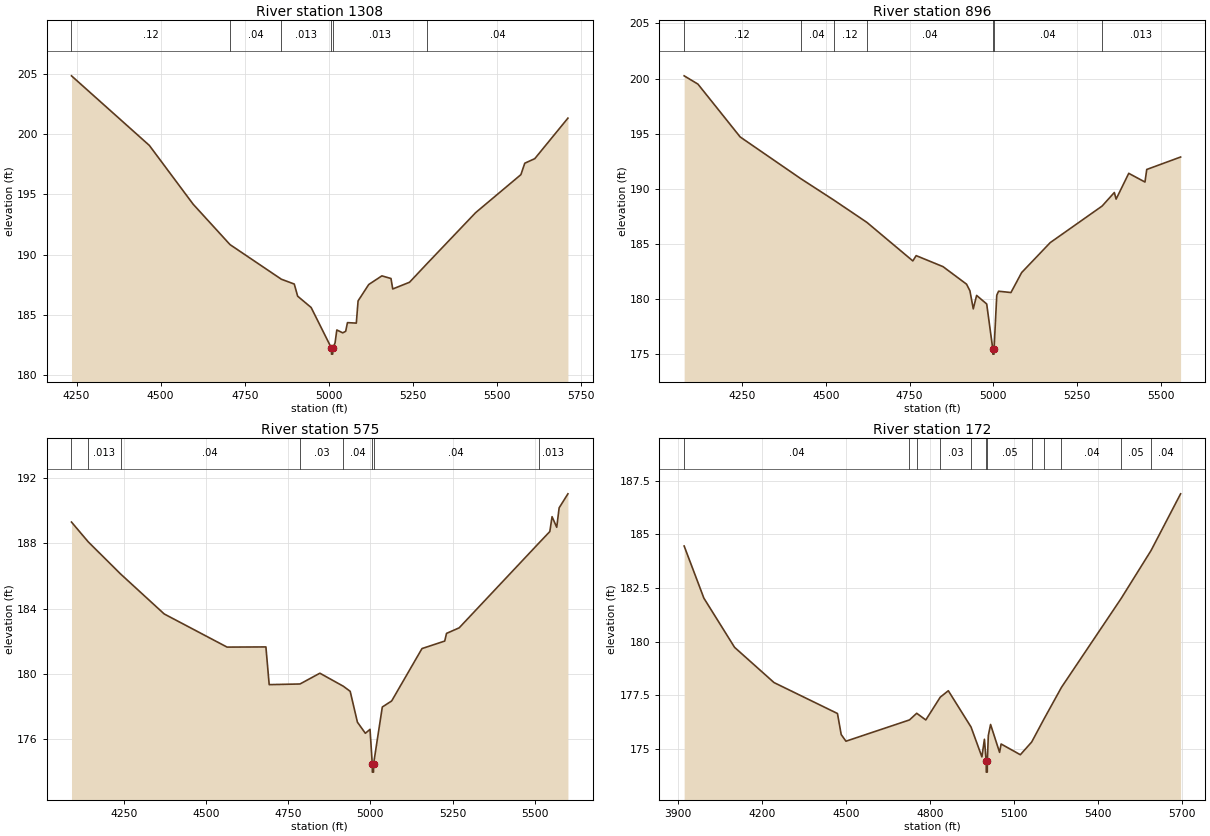
Type RM Length L Ch R = 1,1308,412,412,412
BEGIN DESCRIPTION:
LGII4699
END DESCRIPTION:
XS GIS Cut Line= 4
      2535236.43     13523383.99      2535191.46     13524110.92
      2535251.42     13524290.79      2535393.77     13524830.21
#Sta/Elev= 30
  4235.0  204.87  4466.5  199.08  4596.7  194.19  4706.3  190.83  4858.9  187.95
  4897.3  187.55  4907.3  186.54  4947.4  185.60  5007.8  182.22  5008.0  181.72
  5011.5  181.72  5011.8  182.22  5018.5  182.65  5023.8  183.73  5041.4  183.49
  5050.1  183.62  5055.4  184.34  5081.7  184.30  5087.0  186.15  5118.6  187.51
  5157.7  188.23  5184.8  188.01  5190.0  187.14  5240.0  187.70  5292.4  189.26
  5436.5  193.49  5571.0  196.65  5582.5  197.60  5612.3  197.98  5710.8  201.35
#Mann=6,-1,0
  4235.0    0.12       0  4706.3    0.04       0  4858.9   0.013       0
  5007.8    0.03       0  5011.8   0.013       0  5292.4    0.04       0
Bank Sta=5007.8,5011.8
Exp/Cntr=0.3,0.1

Type RM Length L Ch R = 1,896,321,321,321
BEGIN DESCRIPTION:
LGII4698
END DESCRIPTION:
XS GIS Cut Line= 3
      2534809.25     13523353.98      2534869.21     13524290.79
      2535056.50     13524800.22
#Sta/Elev= 30
  4077.1  200.25  4118.2  199.50  4244.4  194.70  4424.5  190.93  4523.4  188.98
  4622.4  186.95  4759.5  183.45  4769.5  183.93  4849.7  182.93  4919.8  181.34
  4929.9  180.74  4939.9  179.10  4949.9  180.32  4980.0  179.54  4998.0  175.49
  4998.3  174.99  5001.8  174.99  5002.0  175.49  5010.0  180.33  5015.4  180.70
  5052.4  180.58  5084.2  182.39  5169.5  185.11  5324.4  188.43  5360.9  189.66
  5366.2  189.06  5403.9  191.40  5452.3  190.61  5457.6  191.75  5558.6  192.88
#Mann=7,-1,0
  4077.1    0.12       0  4424.5    0.04       0  4523.4    0.12       0
  4622.4    0.04       0  4998.0    0.04       0  5002.0    0.04       0
  5324.4   0.013       0
Bank Sta=4998,5002
Exp/Cntr=0.3,0.1

Type RM Length L Ch R = 1,575,403,403,403
BEGIN DESCRIPTION:
LGII4697
END DESCRIPTION:
XS GIS Cut Line= 4
      2534524.47     13523443.93      2534487.00     13524163.38
      2534674.36     13524575.57      2534920.85     13524807.13
#Sta/Elev= 30
  4089.9  189.31  4140.8  188.10  4239.4  186.13  4372.2  183.68  4563.5  181.65
  4681.8  181.66  4691.8  179.35  4785.6  179.39  4846.1  180.05  4917.7  179.25
  4938.4  178.94  4960.4  177.05  4984.6  176.37  4998.8  176.61  5005.6  174.49
  5005.9  173.99  5009.4  173.99  5009.6  174.49  5036.2  177.98  5064.7  178.35
  5157.0  181.56  5226.2  182.02  5231.7  182.49  5270.2  182.83  5512.3  188.01
  5546.2  188.73  5553.0  189.64  5567.2  188.99  5574.5  190.18  5601.3  191.04
#Mann=8,-1,0
  4089.9    0.04       0  4140.8   0.013       0  4239.4    0.04       0
  4785.6    0.03       0  4917.7    0.04       0  5005.6    0.04       0
  5009.6    0.04       0  5512.3   0.013       0
Bank Sta=5005.6,5009.6
Exp/Cntr=0.3,0.1

Type RM Length L Ch R = 1,172,0,0,0
BEGIN DESCRIPTION:
LGII4696
END DESCRIPTION:
XS GIS Cut Line= 4
      2534352.10     13523518.86      2534089.80     13524223.34
      2534284.65     13524643.02      2534794.26     13524875.34
#Sta/Elev= 30
  3922.0  184.46  3992.6  182.03  4102.3  179.74  4243.3  178.10  4470.0  176.66
  4483.4  175.68  4500.3  175.37  4727.3  176.36  4753.3  176.67  4785.8  176.36
  4837.4  177.42  4866.3  177.72  4947.5  176.03  4986.3  174.64  4995.3  175.46
  5001.7  174.43  5002.0  173.93  5005.5  173.93  5005.7  174.43  5009.2  175.63
  5017.3  176.15  5049.5  174.85  5055.0  175.24  5123.7  174.74  5164.1  175.33
  5208.5  176.41  5270.8  177.88  5484.2  182.02  5590.9  184.25  5696.5  186.89
#Mann=12,-1,0
  3922.0    0.04       0  4727.3    0.03       0  4753.3    0.04       0
  4837.4    0.03       0  4947.5    0.05       0  5001.7    0.05       0
  5005.7    0.05       0  5164.1    0.04       0  5208.5    0.05       0
  5270.8    0.04       0  5484.2    0.05       0  5590.9    0.04       0
Bank Sta=5001.7,5005.7
Exp/Cntr=0.3,0.1

Chan Stop Cuts=-1