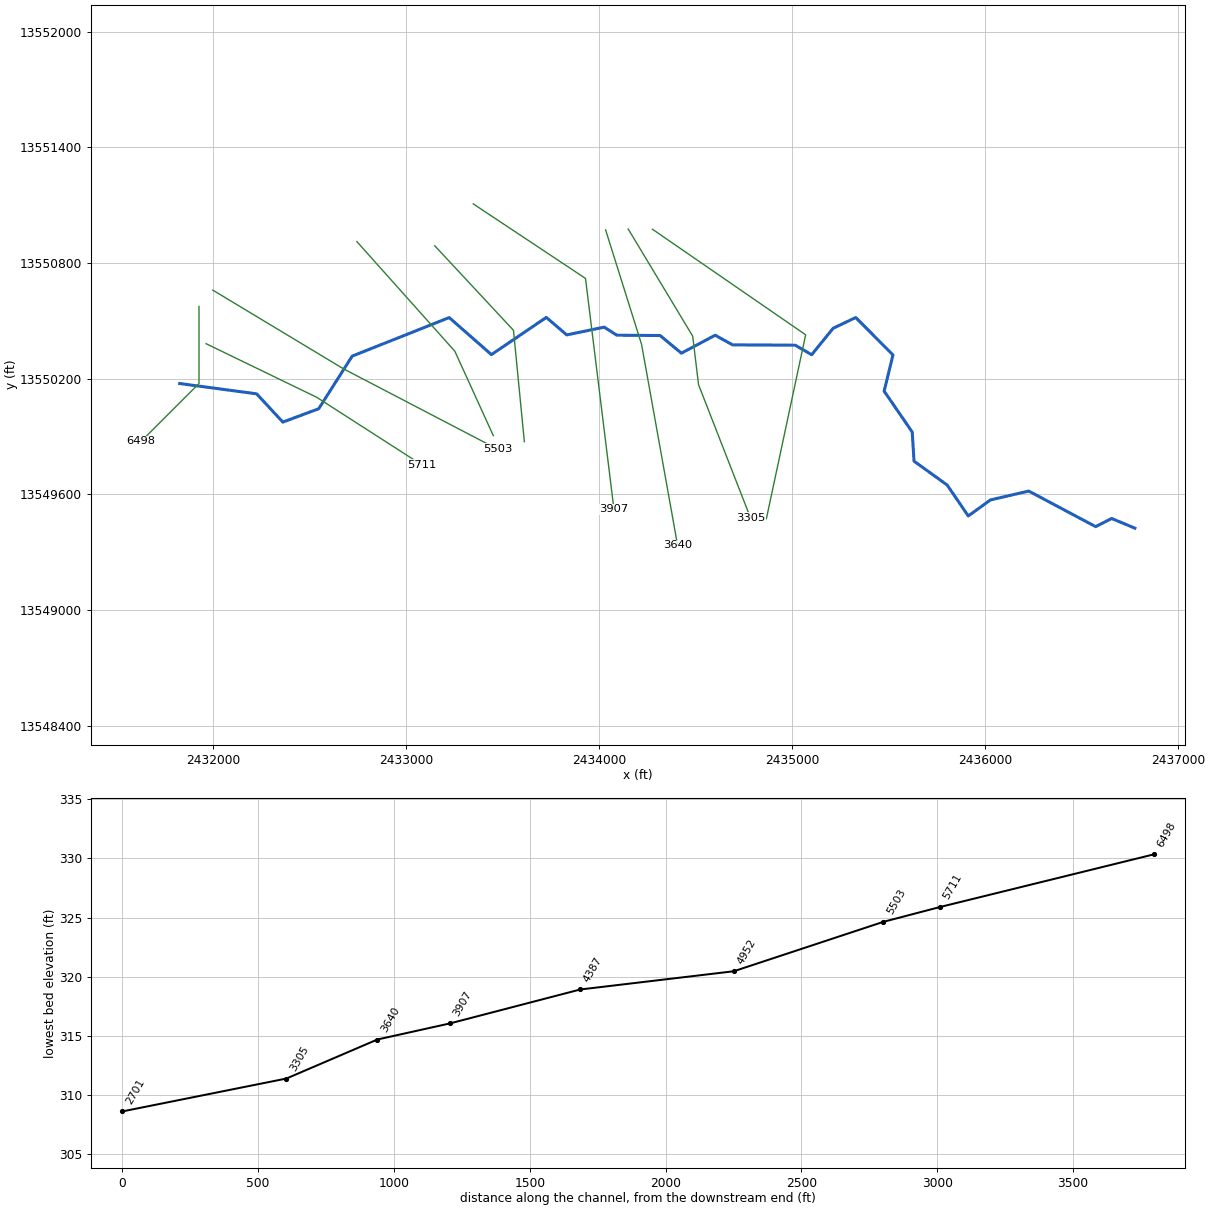
--- TRIB 3_1 TO YORKTOWN CREEK.prj (project) ---

Proj Title=TRIB 3_1 TO YORKTOWN CREEK Base Level Engineering
Current Plan=p01
Default Exp/Contr=0.3,0.1
English Units
Geom File=g01
Flow File=f01
Plan File=p01
BEGIN DESCRIPTION:
TRIB 3_1 TO YORKTOWN CREEK
END DESCRIPTION:

--- TRIB 3_1 TO YORKTOWN CREEK.p01 (plan) ---

Plan Title=Multiple Run
Short Identifier=Multiple
Geom File=g01
Flow File=f01
Subcritical Flow
K Sum by GR= 0
Std Step Tol= 0.01
Critical Tol= 0.01
Num of Std Step Trials= 20
Max Error Tol= 0.3
Flow Tol Ratio= 0.001
Split Flow NTrial= 30
Split Flow Tol= 0.02
Split Flow Ratio= 0.02
Log Output Level= 0
Friction Slope Method= 1
Unsteady Friction Slope Method= 2
Unsteady Bridges Friction Slope Method= 1
Parabolic Critical Depth
Global Vel Dist=  1 , 1 , 1
Global Log Level= 0
CheckData=True
Encroach Param= -1, 0, 0, 0
BEGIN DESCRIPTION:
Multiple Run
END DESCRIPTION:

--- TRIB 3_1 TO YORKTOWN CREEK.f01 (steady flow) ---

Flow Title=Multiple
Number of Profiles=7
Profile Names=10-year,25-year,50-year,1pct_min,100-year,1pct_plu,500-year
River Rch & RM= TRIB 3_1 TO YORK,Reach-1,6498
     458     727     966     623    1243    2479    2031
River Rch & RM= TRIB 3_1 TO YORK,Reach-1,3305
     525     838    1117     722    1440    2873    2367
Boundary for River Rch & Prof#=TRIB 3_1 TO YORK,Reach-1,1
Up Type=0
Dn Type=3
Dn Slope=0.005
Boundary for River Rch & Prof#=TRIB 3_1 TO YORK,Reach-1,2
Up Type=0
Dn Type=3
Dn Slope=0.005
Boundary for River Rch & Prof#=TRIB 3_1 TO YORK,Reach-1,3
Up Type=0
Dn Type=3
Dn Slope=0.005
Boundary for River Rch & Prof#=TRIB 3_1 TO YORK,Reach-1,4
Up Type=0
Dn Type=3
Dn Slope=0.005
Boundary for River Rch & Prof#=TRIB 3_1 TO YORK,Reach-1,5
Up Type=0
Dn Type=3
Dn Slope=0.005
Boundary for River Rch & Prof#=TRIB 3_1 TO YORK,Reach-1,6
Up Type=0
Dn Type=3
Dn Slope=0.005
Boundary for River Rch & Prof#=TRIB 3_1 TO YORK,Reach-1,7
Up Type=0
Dn Type=3
Dn Slope=0.005

--- TRIB 3_1 TO YORKTOWN CREEK.g01 (geometry) ---

Geom Title=Existing Conditions

River Reach=TRIB 3_1 TO YORK,Reach-1
Reach XY= 30
      2431825.00     13550175.00      2432223.75     13550121.54
      2432359.53     13549975.01      2432545.54     13550044.46
      2432718.81     13550317.14      2433221.73     13550516.96
      2433440.36     13550324.89      2433725.00     13550517.91
      2433830.86     13550427.07      2434025.00     13550467.44
      2434090.16     13550425.66      2434314.57     13550423.94
      2434424.92     13550332.30      2434600.00     13550425.41
      2434690.21     13550375.54      2435014.50     13550373.76
      2435100.12     13550324.47      2435211.44     13550461.54
      2435328.41     13550517.23      2435521.54     13550323.50
      2435475.60     13550135.62      2435621.24     13549923.44
      2435630.46     13549772.54      2435802.14     13549648.84
      2435911.64     13549488.40      2436026.47     13549571.43
      2436225.01     13549617.47      2436571.69     13549433.07
      2436654.79     13549475.30      2436775.00     13549425.00

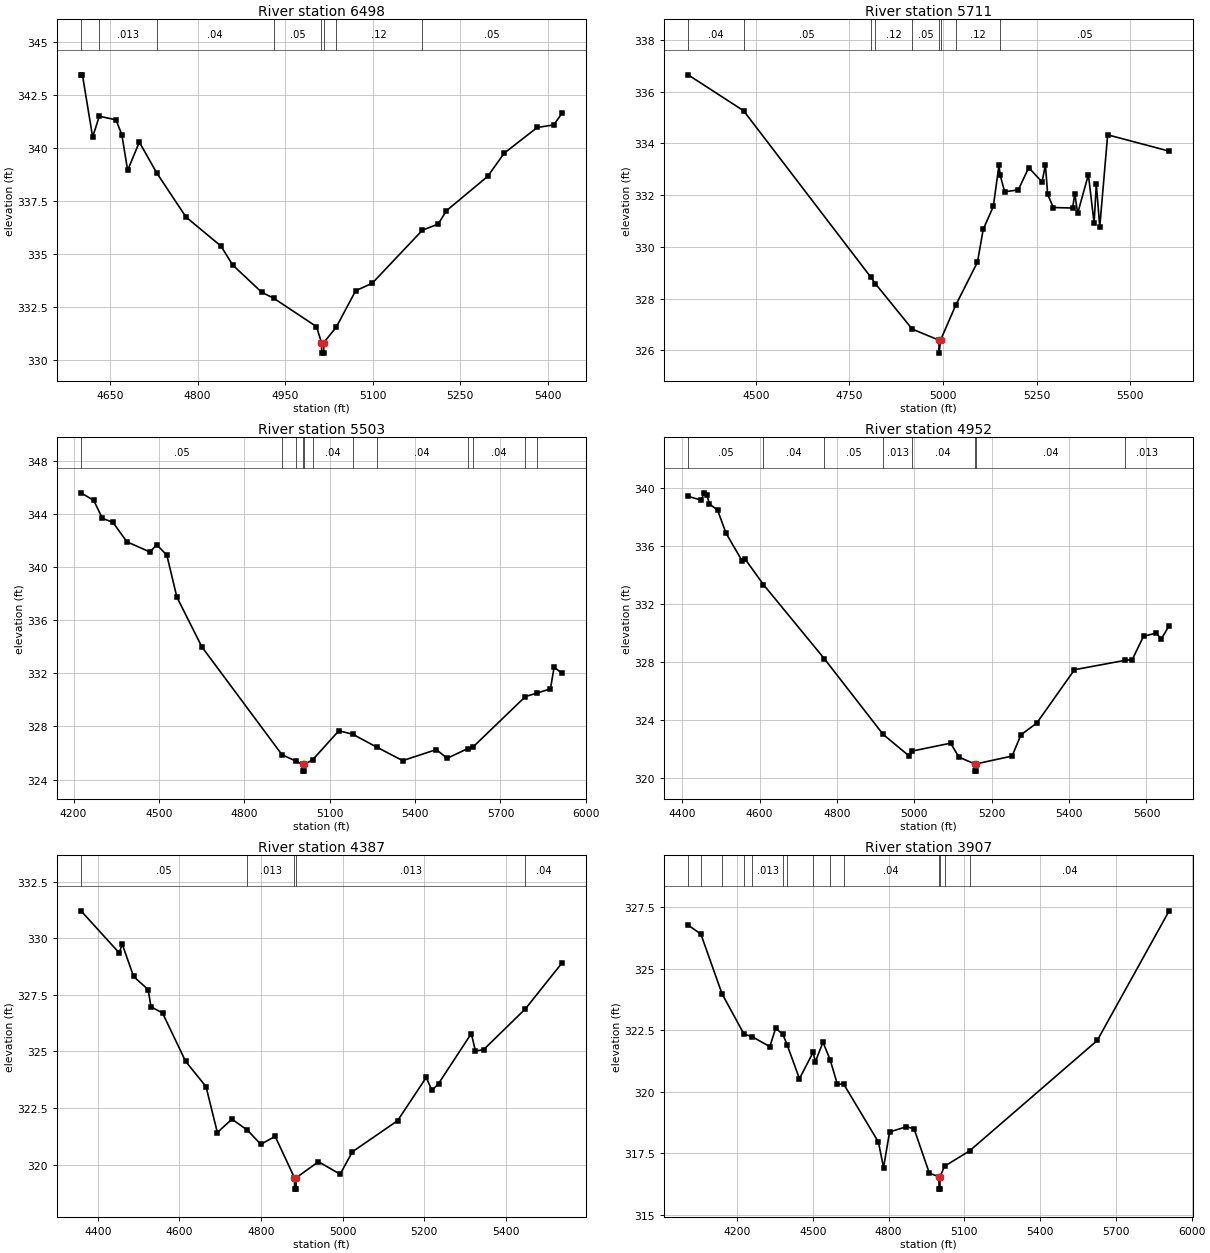
Type RM Length L Ch R = 1,6498,787,787,787
BEGIN DESCRIPTION:
TRIB 3_1 TO YORKTOWN CREEK 8.0
END DESCRIPTION:
XS GIS Cut Line= 3
      2431925.00     13550575.00      2431925.00     13550175.00
      2431624.98     13549874.98
#Sta/Elev= 30
  4600.1  343.45  4602.6  343.45  4620.1  340.52  4631.5  341.50  4660.1  341.33
  4670.1  340.63  4680.1  338.95  4700.1  340.28  4730.1  338.82  4780.1  336.75
  4840.1  335.38  4860.1  334.49  4910.1  333.20  4930.2  332.93  5003.6  331.59
  5012.2  330.84  5012.5  330.34  5016.0  330.34  5016.2  330.84  5037.5  331.56
  5070.8  333.28  5099.1  333.63  5185.1  336.13  5212.2  336.42  5226.4  337.05
  5297.1  338.67  5325.4  339.76  5381.9  340.97  5410.2  341.09  5424.4  341.64
#Mann=8,-1,0
  4600.1    0.05       0  4631.5   0.013       0  4730.1    0.04       0
  4930.2    0.05       0  5012.2    0.05       0  5016.2    0.05       0
  5037.5    0.12       0  5185.1    0.05       0
Bank Sta=5012.2,5016.2
Exp/Cntr=0.3,0.1

Type RM Length L Ch R = 1,5711,208,208,208
BEGIN DESCRIPTION:
Mapping XS 8a823cf0
END DESCRIPTION:
XS GIS Cut Line= 3
      2431961.79     13550381.59      2432534.74     13550103.80
      2433080.80     13549752.76
#Sta/Elev= 30
  4318.7  336.65  4467.1  335.26  4806.9  328.83  4819.0  328.58  4917.7  326.82
  4989.4  326.39  4989.7  325.89  4993.4  326.39  5034.0  327.74  5092.2  329.41
  5107.4  330.67  5134.5  331.56  5149.6  333.15  5153.1  332.76  5164.8  332.13
  5201.2  332.20  5229.2  333.06  5264.8  332.51  5273.8  333.17  5279.8  332.03
  5294.9  331.52  5346.5  331.50  5352.4  332.06  5359.9  331.29  5388.7  332.79
  5403.9  330.92  5409.9  332.42  5419.1  330.78  5440.2  334.33  5604.6  333.70
#Mann=9,-1,0
  4318.7    0.04       0  4467.1    0.05       0  4806.9   0.013       0
  4819.0    0.12       0  4917.7    0.05       0  4989.4    0.05       0
  4993.4    0.05       0  5034.0    0.12       0  5153.1    0.05       0
Bank Sta=4989.4,4993.4
Exp/Cntr=0.3,0.1

Type RM Length L Ch R = 1,5503,551,551,551
BEGIN DESCRIPTION:
Mapping XS 2d387bc0
END DESCRIPTION:
XS GIS Cut Line= 3
      2431996.55     13550659.35      2432673.62     13550251.37
      2433471.11     13549835.29
#Sta/Elev= 30
  4226.2  345.58  4271.1  345.01  4301.4  343.66  4338.3  343.36  4387.8  341.89
  4469.6  341.12  4491.6  341.69  4527.9  340.89  4563.0  337.74  4650.9  333.99
  4932.2  325.88  4983.3  325.37  5004.6  325.14  5004.9  324.64  5008.4  324.64
  5008.6  325.14  5039.7  325.48  5132.2  327.68  5181.6  327.41  5264.9  326.45
  5356.6  325.43  5474.4  326.26  5512.9  325.61  5585.6  326.34  5602.8  326.44
  5787.5  330.25  5828.0  330.51  5875.5  330.83  5888.4  332.46  5916.2  332.00
#Mann=12,-1,0
  4226.2    0.05       0  4932.2    0.04       0  4983.3    0.05       0
  5004.6    0.05       0  5008.6    0.05       0  5039.7    0.04       0
  5181.6    0.05       0  5264.9    0.04       0  5585.6    0.05       0
  5602.8    0.04       0  5787.5    0.05       0  5828.0   0.013       0
Bank Sta=5004.6,5008.6
Exp/Cntr=0.3,0.1

Type RM Length L Ch R = 1,4952,565,565,565
BEGIN DESCRIPTION:
Mapping XS 3f2b31a0
END DESCRIPTION:
XS GIS Cut Line= 3
      2432743.10     13550911.06      2433250.88     13550342.52
      2433450.25     13549904.77
#Sta/Elev= 30
  4415.3  339.43  4449.6  339.16  4456.3  339.67  4463.7  339.52  4470.5  338.90
  4491.4  338.48  4513.2  336.89  4555.8  334.93  4562.5  335.10  4609.9  333.34
  4767.0  328.23  4919.5  322.99  4987.2  321.49  4993.7  321.84  5093.8  322.39
  5115.1  321.43  5155.7  320.96  5156.0  320.46  5159.5  320.46  5159.7  320.96
  5252.6  321.50  5275.6  322.97  5316.2  323.77  5413.9  327.46  5545.1  328.11
  5563.2  328.16  5592.4  329.77  5625.4  329.99  5637.9  329.57  5658.6  330.50
#Mann=8,-1,0
  4415.3    0.05       0  4609.9    0.04       0  4767.0    0.05       0
  4919.5   0.013       0  4993.7    0.04       0  5155.7    0.04       0
  5159.7    0.04       0  5545.1   0.013       0
Bank Sta=5155.7,5159.7
Exp/Cntr=0.3,0.1

Type RM Length L Ch R = 1,4387,480,480,480
BEGIN DESCRIPTION:
Mapping XS eba28a30
END DESCRIPTION:
XS GIS Cut Line= 3
      2433146.74     13550889.37      2433554.70     13550451.03
      2433611.12     13549873.79
#Sta/Elev= 30
  4358.7  331.21  4452.5  329.35  4459.8  329.74  4487.7  328.31  4523.4  327.73
  4530.2  326.97  4558.5  326.70  4615.2  324.56  4665.1  323.45  4692.9  321.42
  4728.6  322.01  4766.2  321.53  4799.4  320.90  4834.6  321.25  4881.9  319.42
  4882.2  318.92  4885.7  318.92  4885.9  319.42  4940.6  320.13  4993.7  319.58
  5023.9  320.57  5134.4  321.94  5204.7  323.85  5218.7  323.28  5234.9  323.58
  5315.2  325.79  5325.3  325.02  5345.4  325.08  5447.7  326.88  5537.5  328.91
#Mann=5,-1,0
  4358.7    0.05       0  4766.2   0.013       0  4881.9    0.03       0
  4885.9   0.013       0  5447.7    0.04       0
Bank Sta=4881.9,4885.9
Exp/Cntr=0.3,0.1

Type RM Length L Ch R = 1,3907,267,267,267
BEGIN DESCRIPTION:
Mapping XS a21ccf9b
END DESCRIPTION:
XS GIS Cut Line= 3
      2433346.39     13551106.39      2433927.96     13550720.12
      2434075.53     13549522.24
#Sta/Elev= 30
  4005.8  326.76  4056.2  326.40  4139.9  323.98  4227.0  322.34  4260.2  322.23
  4329.4  321.83  4352.3  322.57  4380.6  322.34  4397.7  321.91  4446.7  320.53
  4500.9  321.60  4509.8  321.22  4539.9  322.01  4568.5  321.29  4597.1  320.30
  4621.3  320.32  4759.5  317.96  4779.7  316.92  4803.6  318.37  4870.3  318.58
  4900.6  318.50  4961.0  316.70  4999.3  316.55  4999.6  316.05  5003.1  316.05
  5003.3  316.55  5021.3  316.98  5120.3  317.60  5626.0  322.08  5910.9  327.34
#Mann=14,-1,0
  4005.8    0.03       0  4056.2    0.05       0  4139.9    0.03       0
  4227.0    0.05       0  4260.2   0.013       0  4380.6    0.04       0
  4397.7    0.05       0  4500.9    0.04       0  4568.5    0.05       0
  4621.3    0.04       0  4999.3    0.04       0  5003.3    0.04       0
  5021.3   0.013       0  5120.3    0.04       0
Bank Sta=4999.3,5003.3
Exp/Cntr=0.3,0.1

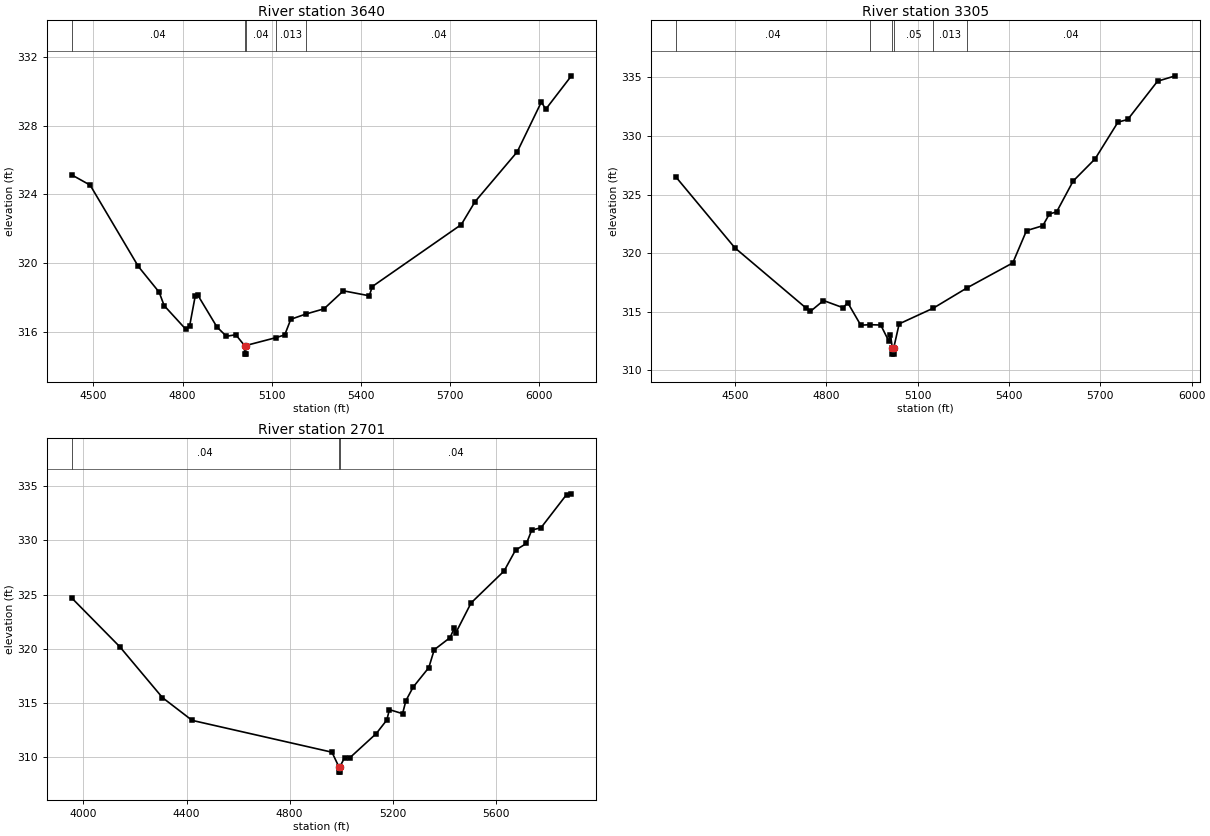
Type RM Length L Ch R = 1,3640,335,335,335
BEGIN DESCRIPTION:
Mapping XS 4e79d9b4
END DESCRIPTION:
XS GIS Cut Line= 3
      2434032.15     13550971.82      2434218.76     13550377.24
      2434405.39     13549335.60
#Sta/Elev= 30
  4426.9  325.14  4489.1  324.54  4651.2  319.80  4721.3  318.30  4738.0  317.52
  4811.4  316.13  4823.8  316.33  4842.8  318.09  4850.9  318.14  4915.8  316.27
  4947.6  315.73  4979.1  315.82  5008.5  315.19  5008.7  314.69  5012.2  314.69
  5012.5  315.19  5114.1  315.65  5143.8  315.81  5164.1  316.72  5213.8  317.02
  5275.9  317.33  5341.2  318.38  5428.2  318.09  5438.4  318.63  5737.8  322.24
  5783.8  323.57  5926.0  326.48  6007.3  329.39  6021.8  328.96  6108.3  330.91
#Mann=5,-1,0
  4426.9    0.04       0  5008.5    0.04       0  5012.5    0.04       0
  5114.1   0.013       0  5213.8    0.04       0
Bank Sta=5008.5,5012.5
Exp/Cntr=0.3,0.1

Type RM Length L Ch R = 1,3305,604,604,604
BEGIN DESCRIPTION:
Mapping XS 57c53635
END DESCRIPTION:
XS GIS Cut Line= 4
      2434149.31     13550976.21      2434483.52     13550420.64
      2434513.90     13550168.91      2434782.77     13549479.38
#Sta/Elev= 30
  4304.4  326.53  4499.0  320.46  4732.1  315.34  4747.7  315.04  4790.4  315.96
  4854.5  315.35  4870.1  315.77  4912.8  313.86  4944.7  313.90  4978.6  313.87
  5005.3  312.48  5010.3  313.03  5016.9  311.89  5017.1  311.39  5020.6  311.39
  5020.9  311.89  5039.0  313.97  5151.2  315.31  5262.7  317.05  5412.4  319.17
  5457.4  321.92  5511.0  322.34  5532.5  323.34  5556.4  323.52  5610.7  326.15
  5682.8  328.04  5757.9  331.17  5790.1  331.40  5887.9  334.66  5946.4  335.12
#Mann=6,-1,0
  4304.4    0.04       0  4944.7    0.05       0  5016.9    0.05       0
  5020.9    0.05       0  5151.2   0.013       0  5262.7    0.04       0
Bank Sta=5016.9,5020.9
Exp/Cntr=0.3,0.1

Type RM Length L Ch R = 1,2701,0,0,0
BEGIN DESCRIPTION:
TRIB 3_1 TO YORKTOWN CREEK 1.0
END DESCRIPTION:
XS GIS Cut Line= 3
      2434274.98     13550975.01      2435068.88     13550427.70
      2434865.46     13549474.44
#Sta/Elev= 30
  3954.3  324.70  4141.0  320.19  4306.6  315.49  4421.6  313.39  4964.2  310.45
  4990.9  309.11  4991.2  308.61  4994.7  308.61  4994.9  309.11  5013.8  309.96
  5033.8  309.94  5136.1  312.17  5177.0  313.42  5187.2  314.38  5238.3  314.01
  5251.1  315.21  5279.2  316.46  5340.0  318.26  5361.0  319.91  5422.4  321.03
  5439.0  321.92  5444.1  321.44  5504.2  324.24  5632.0  327.18  5676.4  329.11
  5718.9  329.73  5739.3  330.96  5775.4  331.18  5874.5  334.24  5893.3  334.31
#Mann=3,-1,0
  3954.3    0.04       0  4990.9    0.04       0  4994.9    0.04       0
Bank Sta=4990.9,4994.9
Exp/Cntr=0.3,0.1

Chan Stop Cuts=-1