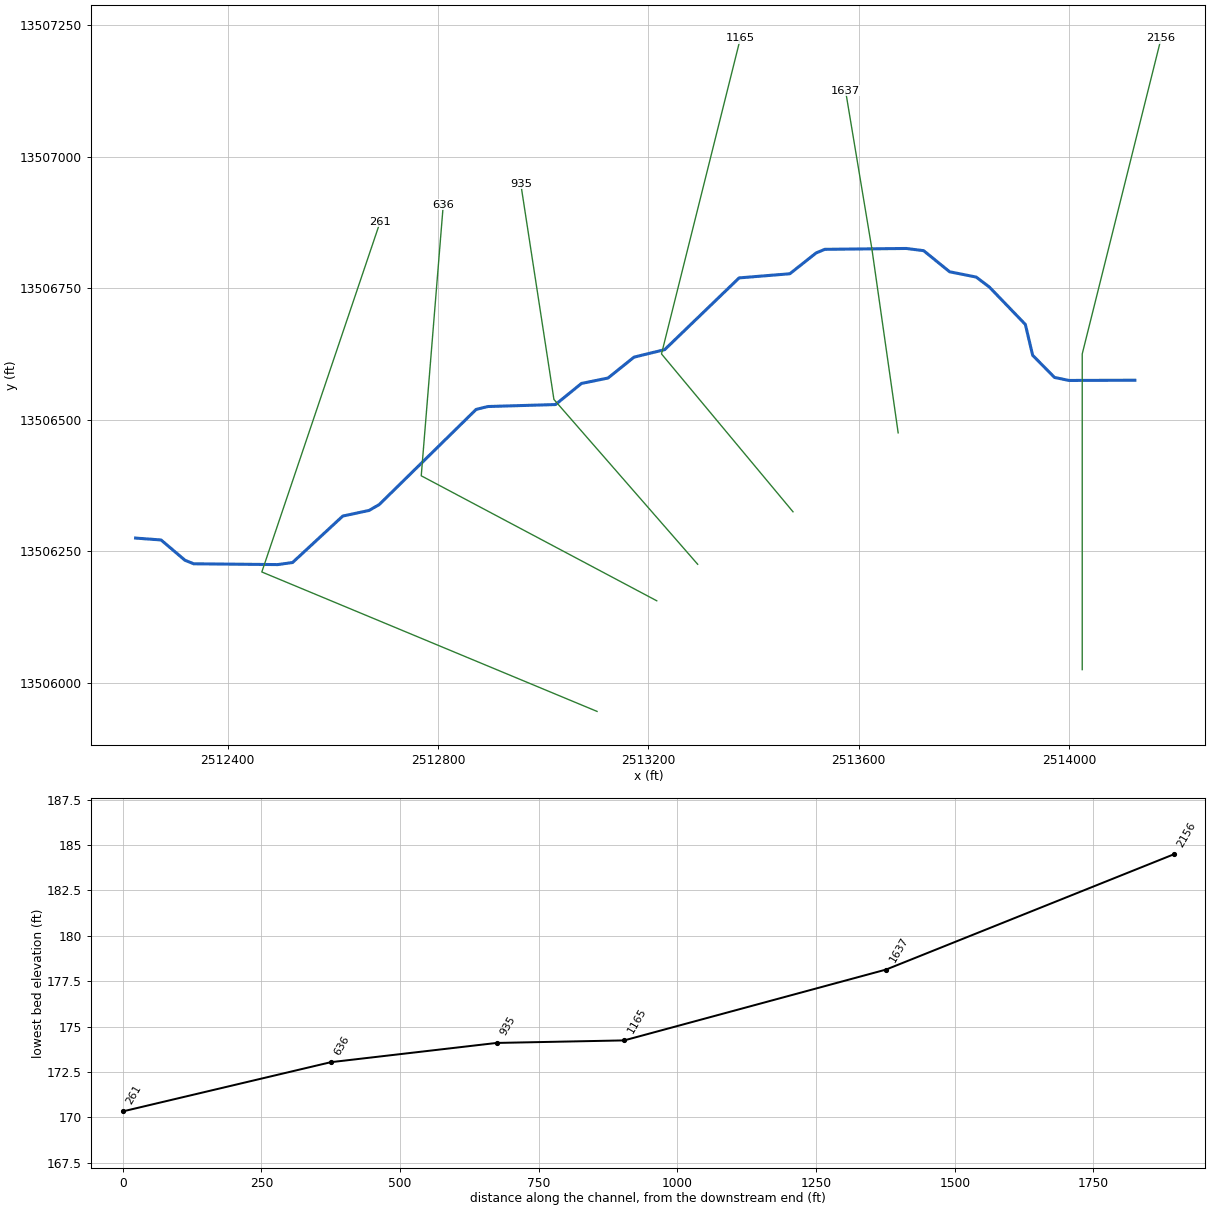
--- TRIB 3_1_1 TO FIFTEENMILE CREEK.prj (project) ---

Proj Title=TRIB 3_1_1 TO FIFTEENMILE CREEK Base Level Engineering
Current Plan=p01
Default Exp/Contr=0.3,0.1
English Units
Geom File=g01
Flow File=f01
Plan File=p01
BEGIN DESCRIPTION:
TRIB 3_1_1 TO FIFTEENMILE CREEK
END DESCRIPTION:

--- TRIB 3_1_1 TO FIFTEENMILE CREEK.p01 (plan) ---

Plan Title=Multiple Run
Short Identifier=Multiple
Geom File=g01
Flow File=f01
Subcritical Flow
K Sum by GR= 0
Std Step Tol= 0.01
Critical Tol= 0.01
Num of Std Step Trials= 20
Max Error Tol= 0.3
Flow Tol Ratio= 0.001
Split Flow NTrial= 30
Split Flow Tol= 0.02
Split Flow Ratio= 0.02
Log Output Level= 0
Friction Slope Method= 1
Unsteady Friction Slope Method= 2
Unsteady Bridges Friction Slope Method= 1
Parabolic Critical Depth
Global Vel Dist=  1 , 1 , 1
Global Log Level= 0
CheckData=True
Encroach Param= -1, 0, 0, 0
BEGIN DESCRIPTION:
Multiple Run
END DESCRIPTION:

--- TRIB 3_1_1 TO FIFTEENMILE CREEK.f01 (steady flow) ---

Flow Title=Multiple
Number of Profiles=7
Profile Names=10-year,25-year,50-year,1pct_min,100-year,1pct_plu,500-year
River Rch & RM= TRIB 3_1_1 TO FI,Reach-1,2156
     303     460     595     373     745    1486    1151
River Rch & RM= TRIB 3_1_1 TO FI,Reach-1,935
     325     496     643     404     806    1609    1253
Boundary for River Rch & Prof#=TRIB 3_1_1 TO FI,Reach-1,1
Up Type=0
Dn Type=3
Dn Slope=0.005
Boundary for River Rch & Prof#=TRIB 3_1_1 TO FI,Reach-1,2
Up Type=0
Dn Type=3
Dn Slope=0.005
Boundary for River Rch & Prof#=TRIB 3_1_1 TO FI,Reach-1,3
Up Type=0
Dn Type=3
Dn Slope=0.005
Boundary for River Rch & Prof#=TRIB 3_1_1 TO FI,Reach-1,4
Up Type=0
Dn Type=3
Dn Slope=0.005
Boundary for River Rch & Prof#=TRIB 3_1_1 TO FI,Reach-1,5
Up Type=0
Dn Type=3
Dn Slope=0.005
Boundary for River Rch & Prof#=TRIB 3_1_1 TO FI,Reach-1,6
Up Type=0
Dn Type=3
Dn Slope=0.005
Boundary for River Rch & Prof#=TRIB 3_1_1 TO FI,Reach-1,7
Up Type=0
Dn Type=3
Dn Slope=0.005

--- TRIB 3_1_1 TO FIFTEENMILE CREEK.g01 (geometry) ---

Geom Title=Existing Conditions

River Reach=TRIB 3_1_1 TO FI,Reach-1
Reach XY= 30
      2514125.00     13506575.00      2513999.75     13506574.59
      2513972.28     13506580.33      2513930.74     13506622.43
      2513916.84     13506681.05      2513848.52     13506752.01
      2513823.38     13506771.06      2513772.83     13506781.14
      2513723.45     13506821.25      2513690.18     13506825.44
      2513535.50     13506823.78      2513518.94     13506816.86
      2513469.02     13506777.36      2513372.57     13506769.48
      2513231.06     13506633.14      2513172.81     13506618.90
      2513123.28     13506579.16      2513072.82     13506568.88
      2513023.44     13506528.76      2512894.99     13506525.02
      2512872.55     13506519.53      2512688.21     13506338.63
      2512668.95     13506327.53      2512618.96     13506316.82
      2512523.53     13506228.55      2512495.18     13506224.57
      2512335.46     13506226.12      2512318.84     13506232.89
      2512273.49     13506271.35      2512225.00     13506275.00

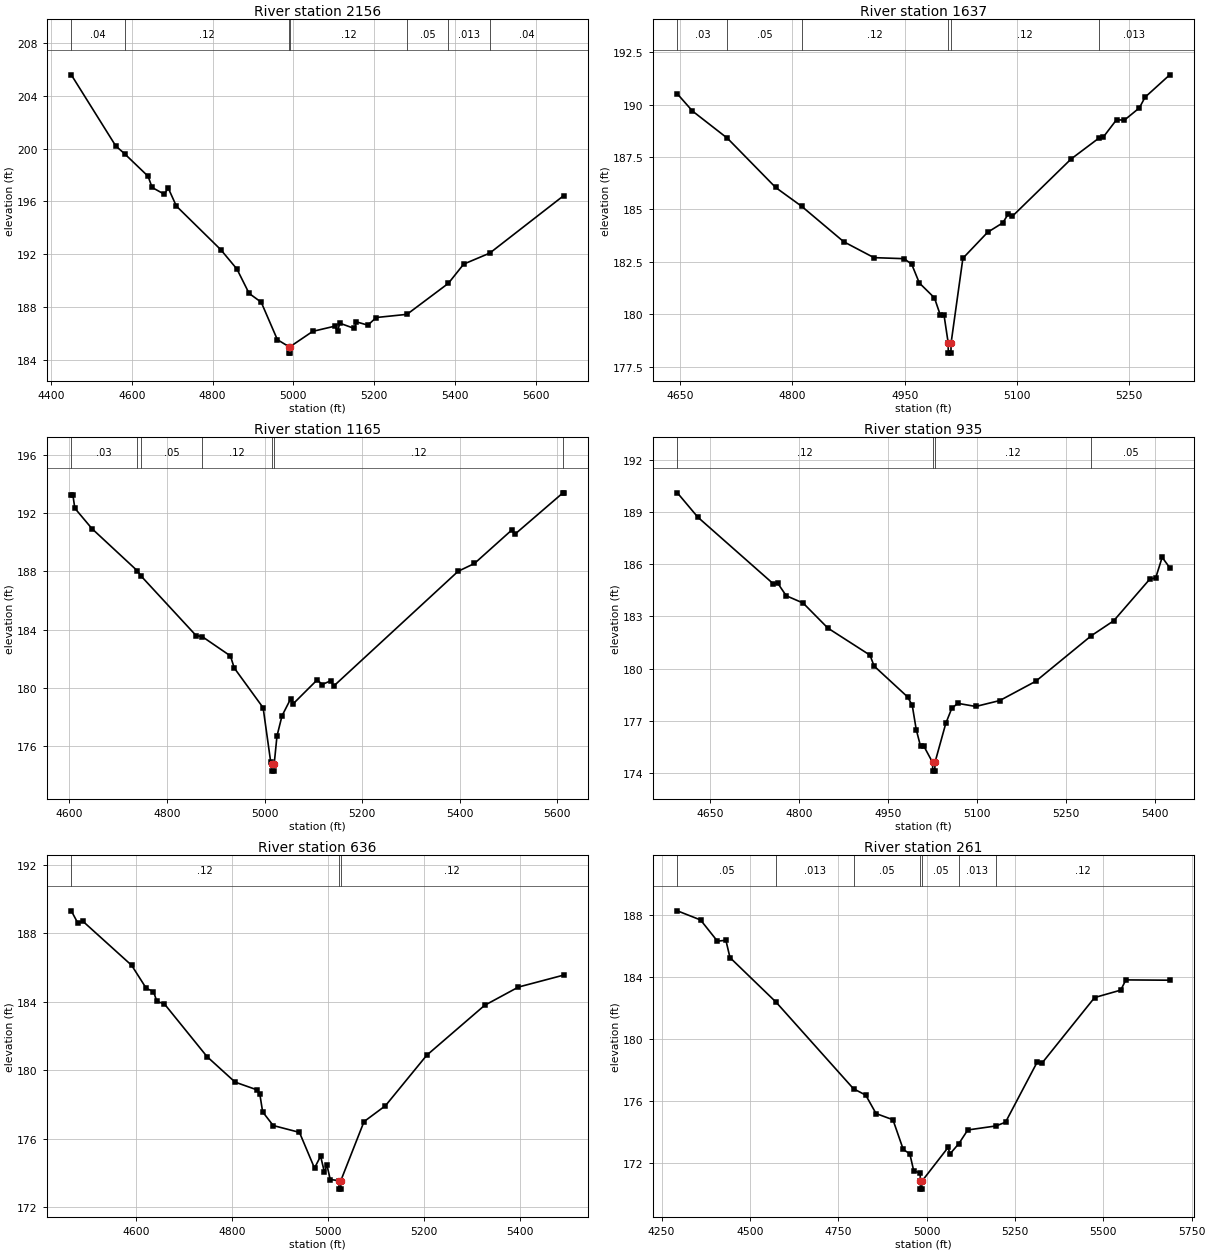
Type RM Length L Ch R = 1,2156,519,519,519
BEGIN DESCRIPTION:
TRIB 3_1-1 TO FIFTEENMILE CREEK 4.0
END DESCRIPTION:
XS GIS Cut Line= 3
      2514025.00     13506024.98      2514025.00     13506625.00
      2514175.00     13507225.01
#Sta/Elev= 30
  4450.5  205.59  4560.5  200.20  4582.6  199.60  4640.5  197.90  4650.5  197.05
  4680.5  196.54  4690.5  197.00  4710.5  195.64  4820.5  192.33  4860.5  190.86
  4890.5  189.02  4920.5  188.35  4960.5  185.51  4988.5  184.99  4988.8  184.49
  4992.3  184.49  4992.5  184.99  5048.0  186.14  5102.1  186.53  5109.8  186.17
  5114.9  186.76  5151.0  186.36  5156.2  186.86  5184.5  186.61  5205.1  187.19
  5281.2  187.43  5383.6  189.78  5421.6  191.24  5485.9  192.07  5669.0  196.43
#Mann=7,-1,0
  4450.5    0.04       0  4582.6    0.12       0  4988.5    0.05       0
  4992.5    0.12       0  5281.2    0.05       0  5383.6   0.013       0
  5485.9    0.04       0
Bank Sta=4988.5,4992.5
Exp/Cntr=0.3,0.1

Type RM Length L Ch R = 1,1637,472,472,472
BEGIN DESCRIPTION:
TRIB 3_1-1 TO FIFTEENMILE CREEK 3.0
END DESCRIPTION:
XS GIS Cut Line= 3
      2513675.00     13506475.01      2513625.00     13506825.00
      2513575.00     13507125.02
#Sta/Elev= 30
  4646.3  190.52  4666.5  189.70  4713.2  188.40  4777.6  186.05  4812.4  185.15
  4868.5  183.46  4908.9  182.70  4949.3  182.65  4959.4  182.38  4969.5  181.49
  4989.7  180.78  4997.3  179.98  5002.4  179.98  5008.0  178.64  5008.2  178.14
  5011.7  178.14  5012.0  178.64  5027.7  182.67  5060.7  183.91  5080.9  184.36
  5088.6  184.80  5093.6  184.67  5172.2  187.41  5209.8  188.42  5215.3  188.46
  5233.0  189.29  5243.2  189.26  5263.4  189.85  5271.0  190.36  5304.0  191.43
#Mann=6,-1,0
  4646.3    0.03       0  4713.2    0.05       0  4812.4    0.12       0
  5008.0    0.05       0  5012.0    0.12       0  5209.8   0.013       0
Bank Sta=5008,5012
Exp/Cntr=0.3,0.1

Type RM Length L Ch R = 1,1165,230,230,230
BEGIN DESCRIPTION:
TRIB 3_1-1 TO FIFTEENMILE CREEK 2.0
END DESCRIPTION:
XS GIS Cut Line= 3
      2513475.03     13506324.96      2513225.00     13506625.00
      2513374.99     13507224.98
#Sta/Elev= 30
  4603.9  193.28  4607.2  193.28  4611.1  192.36  4646.3  190.95  4738.8  188.06
  4746.8  187.69  4859.7  183.58  4872.2  183.51  4930.0  182.18  4937.8  181.35
  4997.0  178.61  5012.5  174.88  5015.7  174.74  5015.9  174.24  5019.4  174.24
  5019.7  174.74  5025.4  176.66  5035.7  178.05  5053.7  179.24  5058.9  178.89
  5107.8  180.53  5118.2  180.21  5136.2  180.48  5141.3  180.09  5396.5  188.01
  5430.0  188.55  5507.3  190.88  5512.4  190.55  5611.1  193.41  5612.9  193.42
#Mann=7,-1,0
  4603.9    0.03       0  4738.8    0.12       0  4746.8    0.05       0
  4872.2    0.12       0  5015.7    0.05       0  5019.7    0.12       0
  5611.1   0.013       0
Bank Sta=5015.7,5019.7
Exp/Cntr=0.3,0.1

Type RM Length L Ch R = 1,935,299,299,299
BEGIN DESCRIPTION:
Mapping XS c8083081
END DESCRIPTION:
XS GIS Cut Line= 3
      2513293.77     13506225.19      2513020.46     13506538.44
      2512957.39     13506948.40
#Sta/Elev= 30
  4594.6  190.11  4629.1  188.71  4756.3  184.88  4763.9  184.91  4778.2  184.19
  4806.7  183.77  4848.4  182.33  4919.6  180.77  4926.3  180.15  4983.2  178.36
  4990.8  177.88  4997.5  176.49  5004.7  175.54  5010.3  175.54  5025.1  174.60
  5025.3  174.10  5028.8  174.10  5029.1  174.60  5047.3  176.84  5057.4  177.71
  5067.5  178.00  5097.9  177.82  5138.4  178.16  5199.1  179.27  5292.8  181.89
  5330.6  182.75  5391.3  185.14  5401.4  185.22  5412.3  186.40  5425.1  185.80
#Mann=4,-1,0
  4594.6    0.12       0  5025.1    0.05       0  5029.1    0.12       0
  5292.8    0.05       0
Bank Sta=5025.1,5029.1
Exp/Cntr=0.3,0.1

Type RM Length L Ch R = 1,636,375,375,375
BEGIN DESCRIPTION:
Mapping XS 8fe720dc
END DESCRIPTION:
XS GIS Cut Line= 3
      2513215.97     13506155.80      2512768.16     13506393.37
      2512810.08     13506908.94
#Sta/Elev= 30
  4466.0  189.32  4479.5  188.61  4489.7  188.72  4591.6  186.13  4622.1  184.78
  4636.9  184.60  4644.1  184.02  4659.5  183.88  4748.4  180.79  4806.7  179.30
  4852.0  178.85  4858.3  178.58  4864.0  177.56  4886.0  176.76  4940.6  176.36
  4971.9  174.27  4984.6  174.97  4992.6  174.02  4997.6  174.46  5004.7  173.60
  5022.7  173.54  5023.0  173.04  5026.5  173.04  5026.7  173.54  5074.9  176.99
  5119.5  177.92  5205.3  180.87  5325.7  183.79  5396.0  184.86  5490.2  185.56
#Mann=3,-1,0
  4466.0    0.12       0  5022.7    0.05       0  5026.7    0.12       0
Bank Sta=5022.7,5026.7
Exp/Cntr=0.3,0.1

Type RM Length L Ch R = 1,261,0,0,0
BEGIN DESCRIPTION:
TRIB 3_1-1 TO FIFTEENMILE CREEK 1.0
END DESCRIPTION:
XS GIS Cut Line= 3
      2513102.46     13505945.53      2512465.01     13506210.54
      2512690.17     13506876.36
#Sta/Elev= 30
  4294.8  188.30  4360.5  187.71  4408.2  186.34  4432.1  186.40  4443.7  185.28
  4573.8  182.41  4793.2  176.81  4827.8  176.40  4857.0  175.21  4904.8  174.81
  4934.0  172.89  4952.5  172.61  4963.5  171.52  4981.7  171.36  4982.4  170.83
  4982.7  170.33  4986.2  170.33  4986.4  170.83  5060.8  173.02  5066.1  172.60
  5091.3  173.27  5116.5  174.15  5196.4  174.41  5223.3  174.65  5312.4  178.51
  5327.7  178.50  5475.4  182.70  5549.3  183.18  5563.9  183.84  5688.0  183.82
#Mann=7,-1,0
  4294.8    0.05       0  4573.8   0.013       0  4793.2    0.05       0
  4982.4    0.05       0  4986.4    0.05       0  5091.3   0.013       0
  5196.4    0.12       0
Bank Sta=4982.4,4986.4
Exp/Cntr=0.3,0.1

Chan Stop Cuts=-1