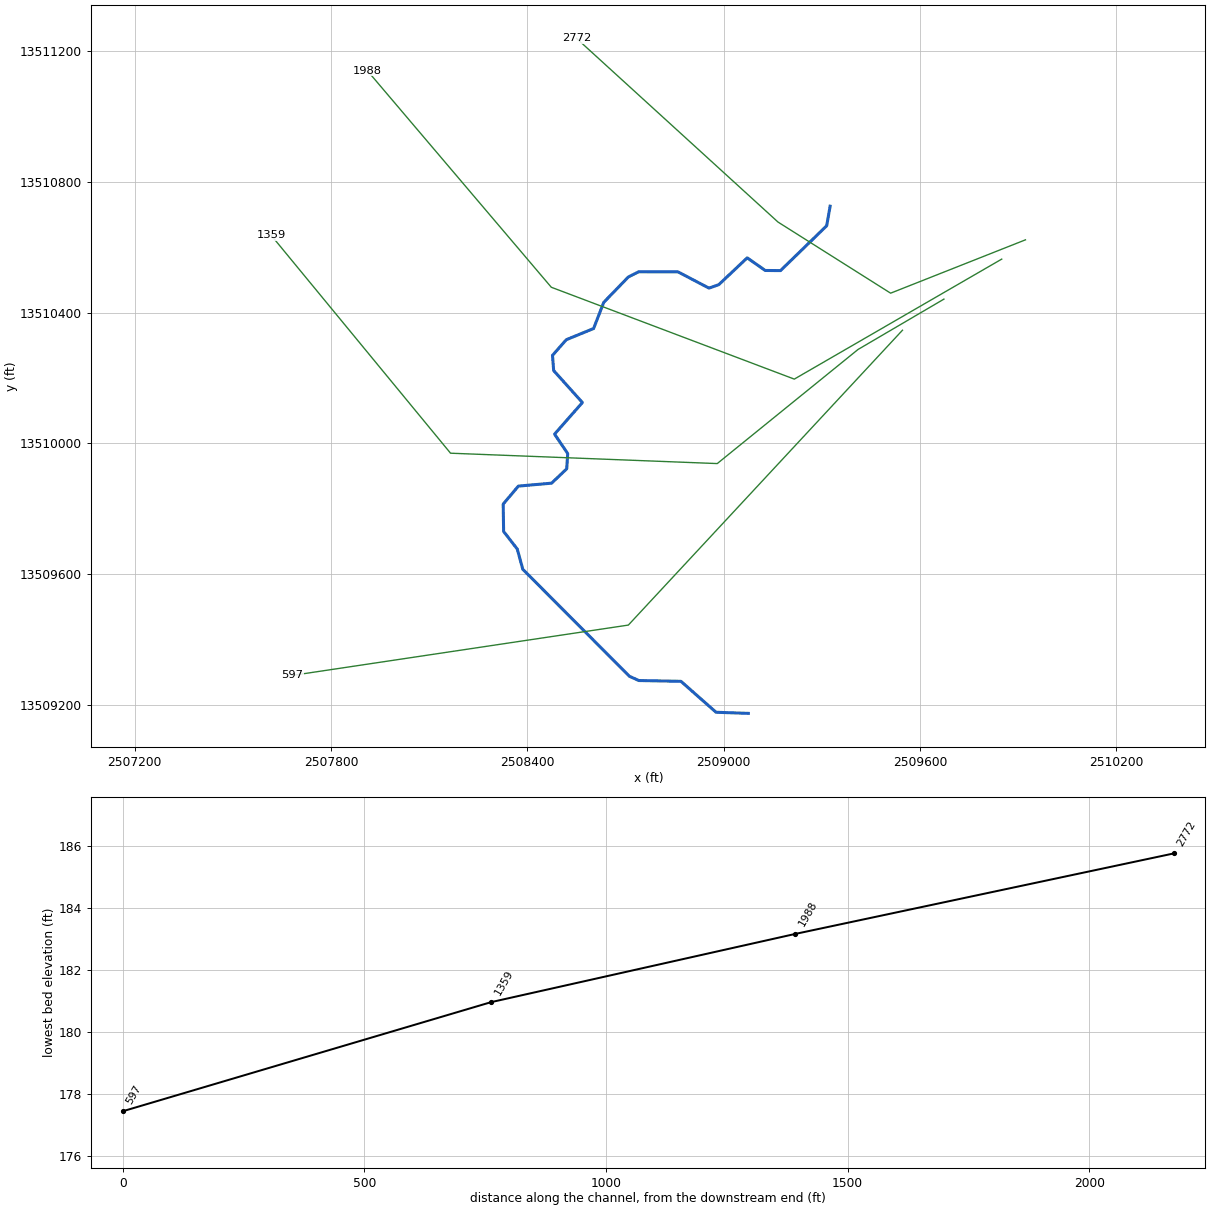
--- TRIB 3_2 TO FIFTEENMILE CREEK.prj (project) ---

Proj Title=TRIB 3_2 TO FIFTEENMILE CREEK Base Level Engineering
Current Plan=p01
Default Exp/Contr=0.3,0.1
English Units
Geom File=g01
Flow File=f01
Plan File=p01
BEGIN DESCRIPTION:
TRIB 3_2 TO FIFTEENMILE CREEK
END DESCRIPTION:

--- TRIB 3_2 TO FIFTEENMILE CREEK.p01 (plan) ---

Plan Title=Multiple Run
Short Identifier=Multiple
Geom File=g01
Flow File=f01
Subcritical Flow
K Sum by GR= 0
Std Step Tol= 0.01
Critical Tol= 0.01
Num of Std Step Trials= 20
Max Error Tol= 0.3
Flow Tol Ratio= 0.001
Split Flow NTrial= 30
Split Flow Tol= 0.02
Split Flow Ratio= 0.02
Log Output Level= 0
Friction Slope Method= 1
Unsteady Friction Slope Method= 2
Unsteady Bridges Friction Slope Method= 1
Parabolic Critical Depth
Global Vel Dist=  1 , 1 , 1
Global Log Level= 0
CheckData=True
Encroach Param= -1, 0, 0, 0
BEGIN DESCRIPTION:
Multiple Run
END DESCRIPTION:

--- TRIB 3_2 TO FIFTEENMILE CREEK.f01 (steady flow) ---

Flow Title=Multiple
Number of Profiles=7
Profile Names=10-year,25-year,50-year,1pct_min,100-year,1pct_plu,500-year
River Rch & RM= TRIB 3_2 TO FIFT,Reach-1,2772
     699    1118    1493     964    1924    3839    3162
Boundary for River Rch & Prof#=TRIB 3_2 TO FIFT,Reach-1,1
Up Type=0
Dn Type=3
Dn Slope=0.005
Boundary for River Rch & Prof#=TRIB 3_2 TO FIFT,Reach-1,2
Up Type=0
Dn Type=3
Dn Slope=0.005
Boundary for River Rch & Prof#=TRIB 3_2 TO FIFT,Reach-1,3
Up Type=0
Dn Type=3
Dn Slope=0.005
Boundary for River Rch & Prof#=TRIB 3_2 TO FIFT,Reach-1,4
Up Type=0
Dn Type=3
Dn Slope=0.005
Boundary for River Rch & Prof#=TRIB 3_2 TO FIFT,Reach-1,5
Up Type=0
Dn Type=3
Dn Slope=0.005
Boundary for River Rch & Prof#=TRIB 3_2 TO FIFT,Reach-1,6
Up Type=0
Dn Type=3
Dn Slope=0.005
Boundary for River Rch & Prof#=TRIB 3_2 TO FIFT,Reach-1,7
Up Type=0
Dn Type=3
Dn Slope=0.005

--- TRIB 3_2 TO FIFTEENMILE CREEK.g01 (geometry) ---

Geom Title=Existing Conditions

River Reach=TRIB 3_2 TO FIFT,Reach-1
Reach XY= 30
      2509325.00     13510725.00      2509314.49     13510665.21
      2509173.35     13510528.16      2509126.65     13510528.59
      2509071.60     13510567.16      2508984.68     13510485.23
      2508954.87     13510474.61      2508859.78     13510524.48
      2508740.16     13510524.64      2508708.20     13510508.59
      2508633.16     13510431.05      2508602.13     13510351.17
      2508518.59     13510316.95      2508476.51     13510269.13
      2508480.08     13510222.73      2508567.89     13510125.00
      2508482.85     13510028.41      2508523.03     13509968.91
      2508520.00     13509922.43      2508473.77     13509878.53
      2508372.29     13509869.59      2508325.86     13509814.69
      2508327.14     13509730.97      2508368.85     13509677.17
      2508385.76     13509615.32      2508711.68     13509288.37
      2508740.16     13509275.40      2508869.14     13509272.93
      2508976.41     13509178.39      2509075.00     13509175.00

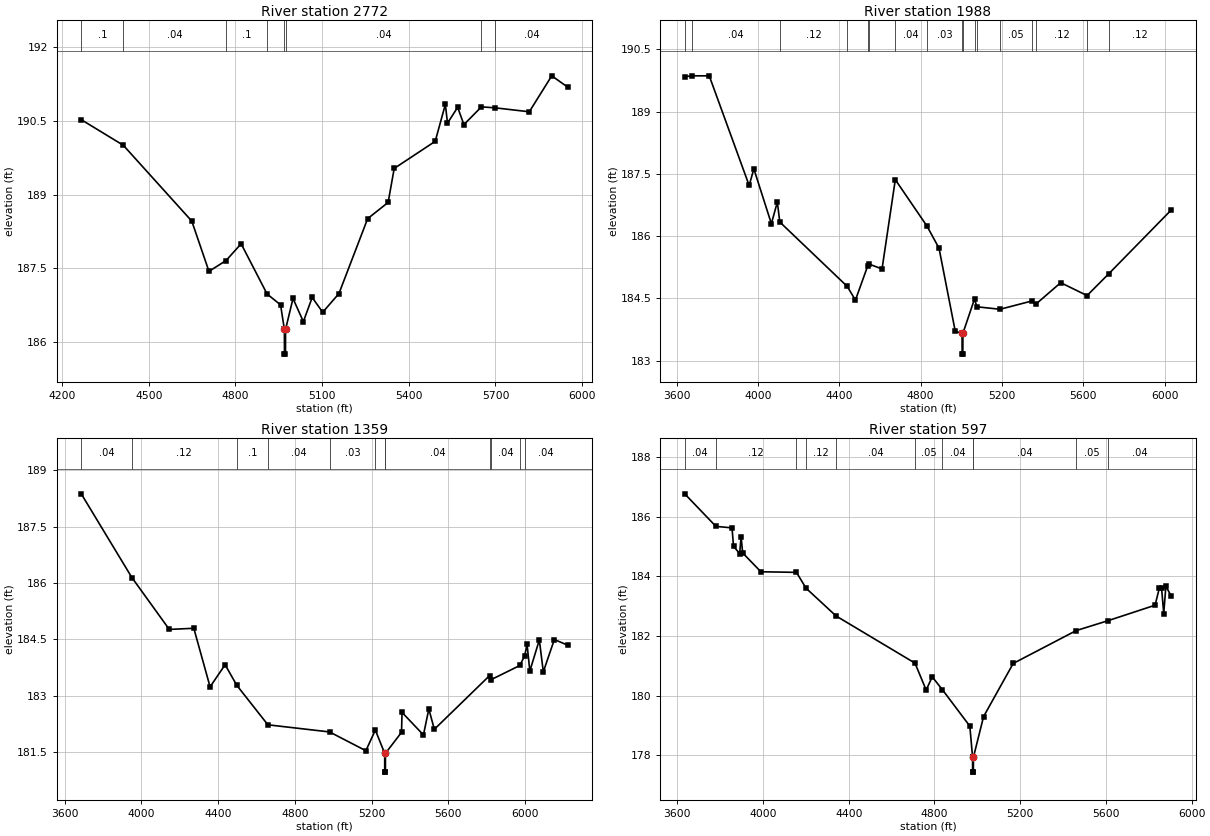
Type RM Length L Ch R = 1,2772,784,784,784
BEGIN DESCRIPTION:
LGII4683
END DESCRIPTION:
XS GIS Cut Line= 4
      2509921.98     13510622.24      2509509.86     13510459.20
      2509165.70     13510676.57      2508549.89     13511238.04
#Sta/Elev= 30
  4266.5  190.52  4412.1  190.00  4649.1  188.46  4708.5  187.44  4767.6  187.66
  4819.8  188.00  4909.7  186.98  4956.3  186.76  4969.5  186.26  4969.8  185.76
  4973.3  185.76  4973.5  186.26  4999.3  186.89  5035.1  186.42  5065.7  186.91
  5102.1  186.61  5158.3  186.99  5257.6  188.51  5328.5  188.84  5349.5  189.53
  5491.4  190.08  5526.5  190.83  5533.9  190.45  5569.1  190.77  5590.7  190.42
  5651.3  190.78  5699.1  190.76  5817.0  190.68  5894.7  191.41  5950.1  191.18
#Mann=8,-1,0
  4266.5     0.1       0  4412.1    0.04       0  4767.6     0.1       0
  4909.7    0.04       0  4969.5    0.04       0  4973.5    0.04       0
  5651.3    0.05       0  5699.1    0.04       0
Bank Sta=4969.5,4973.5
Exp/Cntr=0.3,0.1

Type RM Length L Ch R = 1,1988,629,629,629
BEGIN DESCRIPTION:
LGII4682
END DESCRIPTION:
XS GIS Cut Line= 4
      2509849.45     13510563.34      2509215.51     13510196.56
      2508472.85     13510477.32      2507911.32     13511138.48
#Sta/Elev= 30
  3639.0  189.84  3675.8  189.86  3759.7  189.86  3956.1  187.22  3979.2  187.62
  4065.4  186.30  4094.7  186.82  4106.9  186.34  4438.7  184.79  4478.9  184.46
  4539.9  185.29  4544.9  185.33  4609.9  185.21  4675.2  187.36  4831.3  186.24
  4890.3  185.71  4970.1  183.71  5003.7  183.66  5003.9  183.16  5007.4  183.16
  5007.7  183.66  5065.1  184.49  5076.1  184.30  5190.5  184.24  5347.6  184.44
  5366.0  184.36  5489.0  184.88  5618.7  184.57  5724.5  185.09  6032.8  186.63
#Mann=17,-1,0
  3639.0     0.1       0  3675.8    0.04       0  4106.9    0.12       0
  4438.7     0.1       0  4539.9    0.12       0  4544.9     0.1       0
  4675.2    0.04       0  4831.3    0.03       0  5003.7    0.03       0
  5007.7    0.03       0  5065.1    0.04       0  5076.1    0.03       0
  5190.5    0.05       0  5347.6    0.04       0  5366.0    0.12       0
  5618.7    0.05       0  5724.5    0.12       0
Bank Sta=5003.7,5007.7
Exp/Cntr=0.3,0.1

Type RM Length L Ch R = 1,1359,762,762,762
BEGIN DESCRIPTION:
LGII4681
END DESCRIPTION:
XS GIS Cut Line= 5
      2509672.85     13510441.07      2509410.23     13510287.12
      2508980.03     13509938.44      2508164.92     13509970.13
      2507616.98     13510635.82
#Sta/Elev= 30
  3686.6  188.37  3950.7  186.14  4145.5  184.76  4273.4  184.79  4358.2  183.23
  4436.5  183.82  4497.7  183.27  4659.5  182.22  4981.1  182.03  5170.3  181.53
  5219.7  182.08  5268.4  181.46  5268.6  180.96  5272.1  180.96  5272.4  181.46
  5356.2  182.02  5358.8  182.55  5470.4  181.95  5498.5  182.64  5527.2  182.10
  5815.3  183.53  5822.3  183.42  5973.1  183.80  5998.1  184.06  6010.7  184.36
  6025.0  183.65  6074.5  184.48  6095.3  183.63  6152.7  184.49  6222.7  184.34
#Mann=12,-1,0
  3686.6    0.04       0  3950.7    0.12       0  4497.7     0.1       0
  4659.5    0.04       0  4981.1    0.03       0  5219.7    0.04       0
  5268.4    0.03       0  5272.4    0.04       0  5815.3    0.05       0
  5822.3    0.04       0  5973.1    0.05       0  5998.1    0.04       0
Bank Sta=5268.4,5272.4
Exp/Cntr=0.3,0.1

Type RM Length L Ch R = 1,597,0,0,0
BEGIN DESCRIPTION:
LGII4680
END DESCRIPTION:
XS GIS Cut Line= 3
      2509546.07     13510345.97      2508708.33     13509444.84
      2507680.38     13509290.87
#Sta/Elev= 30
  3634.9  186.76  3780.4  185.67  3855.5  185.62  3862.8  185.00  3891.2  184.76
  3898.0  185.32  3905.3  184.78  3990.3  184.15  4156.3  184.13  4200.9  183.60
  4341.0  182.67  4709.3  181.09  4761.3  180.19  4789.7  180.63  4837.2  180.20
  4965.1  178.98  4977.9  177.94  4978.1  177.44  4981.6  177.44  4981.9  177.94
  5029.2  179.30  5167.5  181.08  5461.3  182.18  5609.1  182.51  5829.3  183.03
  5849.5  183.61  5859.6  183.61  5869.7  182.75  5879.8  183.67  5904.7  183.33
#Mann=11,-1,0
  3634.9    0.04       0  3780.4    0.12       0  4156.3     0.1       0
  4200.9    0.12       0  4341.0    0.04       0  4709.3    0.05       0
  4837.2    0.04       0  4977.9    0.04       0  4981.9    0.04       0
  5461.3    0.05       0  5609.1    0.04       0
Bank Sta=4977.9,4981.9
Exp/Cntr=0.3,0.1

Chan Stop Cuts=-1