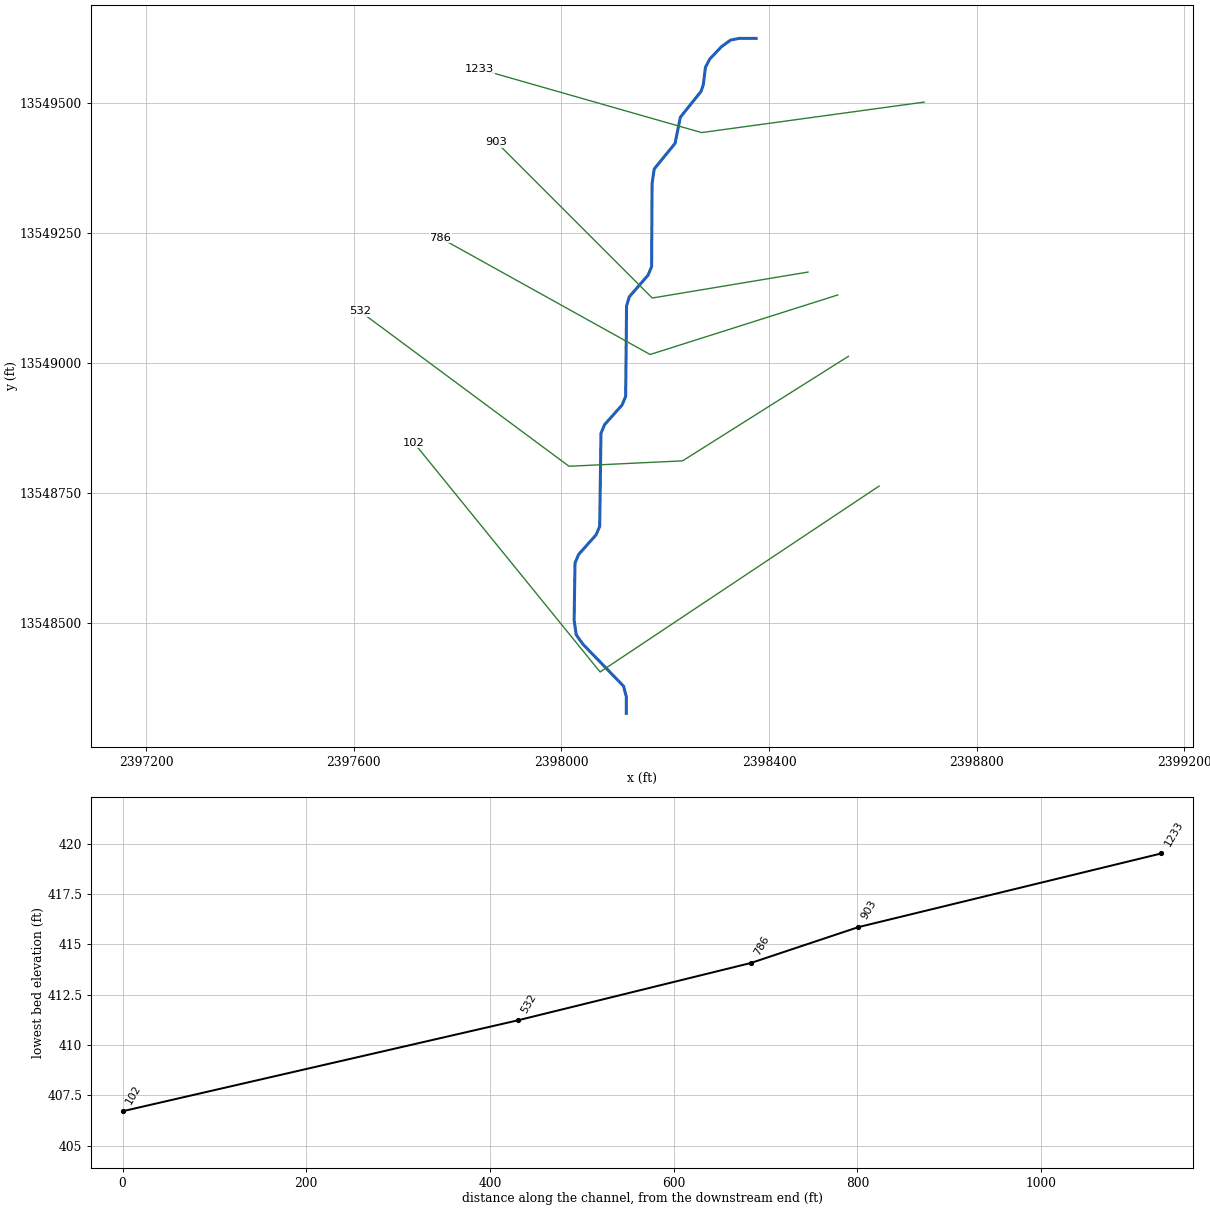
--- TRIB 3_2 TO THOMAS CREEK.prj (project) ---

Proj Title=TRIB 3_2 TO THOMAS CREEK Base Level Engineering
Current Plan=p01
Default Exp/Contr=0.3,0.1
English Units
Geom File=g01
Flow File=f01
Plan File=p01
BEGIN DESCRIPTION:
TRIB 3_2 TO THOMAS CREEK
END DESCRIPTION:

--- TRIB 3_2 TO THOMAS CREEK.p01 (plan) ---

Plan Title=Multiple Run
Short Identifier=Multiple
Geom File=g01
Flow File=f01
Subcritical Flow
K Sum by GR= 0
Std Step Tol= 0.01
Critical Tol= 0.01
Num of Std Step Trials= 20
Max Error Tol= 0.3
Flow Tol Ratio= 0.001
Split Flow NTrial= 30
Split Flow Tol= 0.02
Split Flow Ratio= 0.02
Log Output Level= 0
Friction Slope Method= 1
Unsteady Friction Slope Method= 2
Unsteady Bridges Friction Slope Method= 1
Parabolic Critical Depth
Global Vel Dist=  1 , 1 , 1
Global Log Level= 0
CheckData=True
Encroach Param= -1, 0, 0, 0
BEGIN DESCRIPTION:
Multiple Run
END DESCRIPTION:

--- TRIB 3_2 TO THOMAS CREEK.f01 (steady flow) ---

Flow Title=Multiple
Number of Profiles=7
Profile Names=10-year,25-year,50-year,1pct_min,100-year,1pct_plu,500-year
River Rch & RM= TRIB 3_2 TO THOM,Reach-1,1233
     280     435     569     362     721    1440    1149
Boundary for River Rch & Prof#=TRIB 3_2 TO THOM,Reach-1,1
Up Type=0
Dn Type=3
Dn Slope=0.005
Boundary for River Rch & Prof#=TRIB 3_2 TO THOM,Reach-1,2
Up Type=0
Dn Type=3
Dn Slope=0.005
Boundary for River Rch & Prof#=TRIB 3_2 TO THOM,Reach-1,3
Up Type=0
Dn Type=3
Dn Slope=0.005
Boundary for River Rch & Prof#=TRIB 3_2 TO THOM,Reach-1,4
Up Type=0
Dn Type=3
Dn Slope=0.005
Boundary for River Rch & Prof#=TRIB 3_2 TO THOM,Reach-1,5
Up Type=0
Dn Type=3
Dn Slope=0.005
Boundary for River Rch & Prof#=TRIB 3_2 TO THOM,Reach-1,6
Up Type=0
Dn Type=3
Dn Slope=0.005
Boundary for River Rch & Prof#=TRIB 3_2 TO THOM,Reach-1,7
Up Type=0
Dn Type=3
Dn Slope=0.005

--- TRIB 3_2 TO THOMAS CREEK.g01 (geometry) ---

Geom Title=Existing Conditions

River Reach=TRIB 3_2 TO THOM,Reach-1
Reach XY= 30
      2398375.00     13549625.00      2398342.95     13549625.15
      2398326.03     13549621.86      2398307.76     13549608.64
      2398285.55     13549584.98      2398277.42     13549569.11
      2398273.32     13549535.72      2398268.91     13549522.82
      2398229.16     13549473.28      2398218.88     13549422.82
      2398178.75     13549373.45      2398174.64     13549345.15
      2398173.78     13549185.51      2398166.86     13549168.94
      2398130.75     13549127.33      2398125.52     13549109.78
      2398123.78     13548935.51      2398116.86     13548918.94
      2398083.14     13548881.06      2398076.22     13548864.49
      2398073.78     13548685.51      2398066.86     13548668.94
      2398033.14     13548631.05      2398026.21     13548614.49
      2398024.54     13548504.83      2398028.53     13548476.47
      2398041.43     13548458.24      2398119.67     13548377.51
      2398125.07     13548356.88      2398125.00     13548325.00

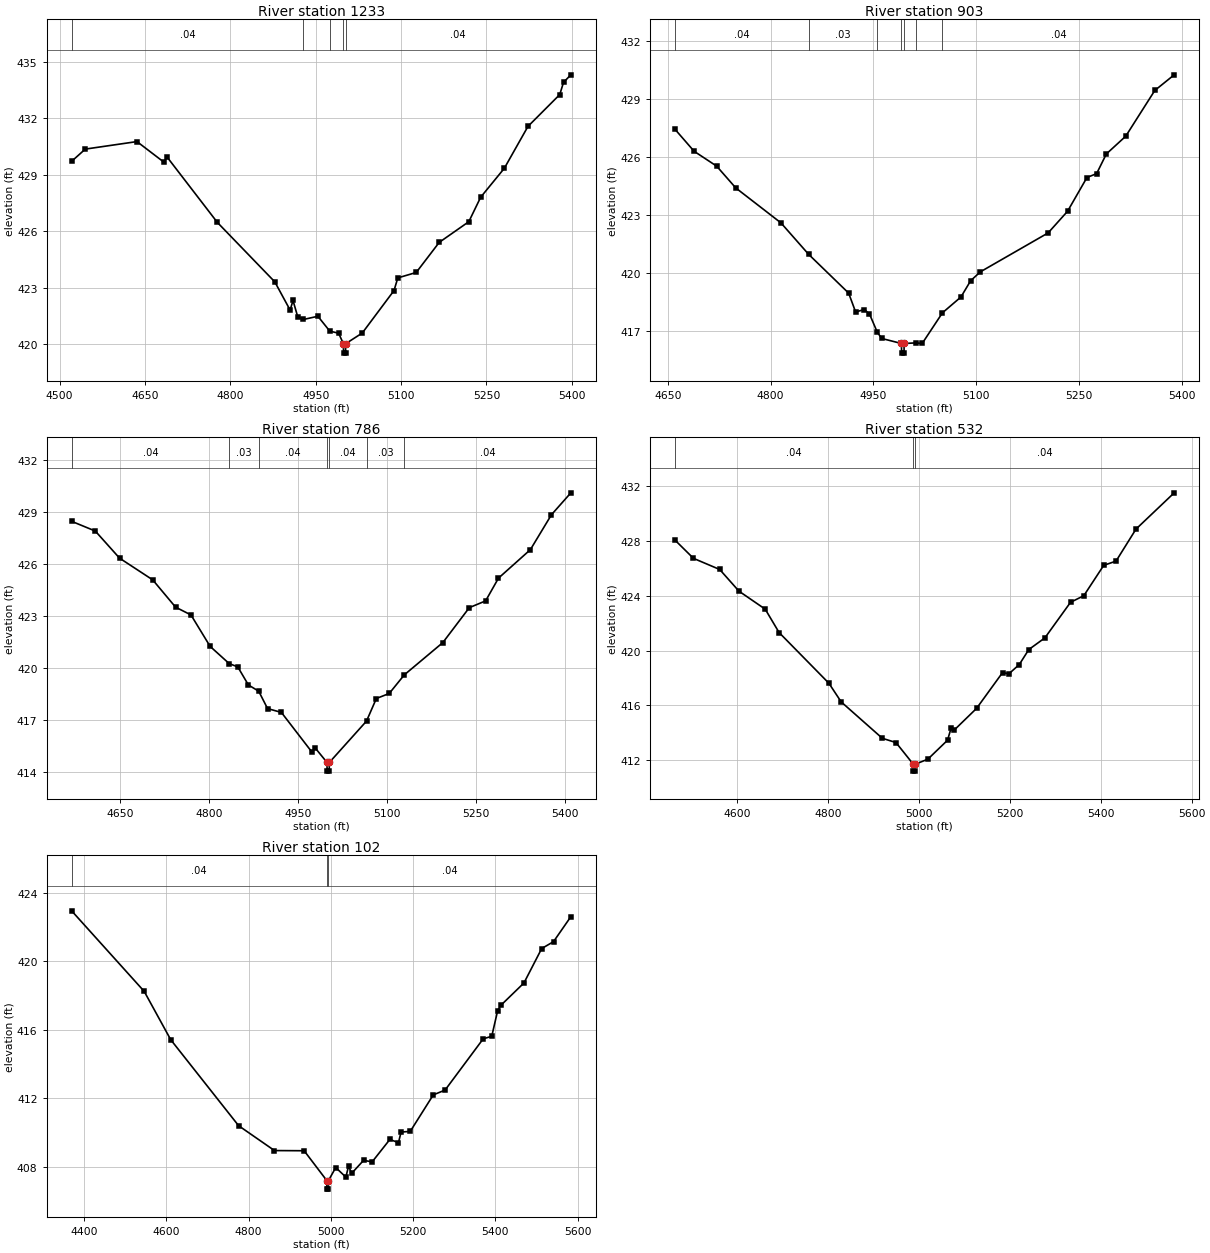
Type RM Length L Ch R = 1,1233,330,330,330
BEGIN DESCRIPTION:
TRIB 3_2 TO THOMAS CREEK 3.0
END DESCRIPTION:
XS GIS Cut Line= 3
      2398698.73     13549502.33      2398270.06     13549443.62
      2397842.64     13549565.74
#Sta/Elev= 30
  4521.1  429.71  4545.1  430.36  4635.9  430.76  4683.5  429.66  4688.5  429.95
  4777.2  426.46  4878.1  423.30  4905.0  421.80  4910.1  422.31  4918.5  421.43
  4928.5  421.30  4953.8  421.47  4974.7  420.68  4990.2  420.57  4998.6  420.01
  4998.9  419.51  5002.4  419.51  5002.6  420.01  5031.8  420.58  5087.6  422.84
  5094.2  423.51  5126.6  423.80  5167.0  425.40  5219.0  426.50  5239.8  427.80
  5281.4  429.34  5323.0  431.57  5378.8  433.26  5385.4  433.91  5398.3  434.31
#Mann=5,-1,0
  4521.1    0.04       0  4928.5    0.03       0  4974.7    0.04       0
  4998.6    0.04       0  5002.6    0.04       0
Bank Sta=4998.6,5002.6
Exp/Cntr=0.3,0.1

Type RM Length L Ch R = 1,903,117,117,117
BEGIN DESCRIPTION:
TRIB 3_2 TO THOMAS CREEK 2.0
END DESCRIPTION:
XS GIS Cut Line= 3
      2398474.98     13549175.00      2398175.00     13549125.00
      2397874.99     13549425.01
#Sta/Elev= 30
  4660.5  427.45  4688.4  426.31  4721.3  425.54  4749.2  424.41  4815.1  422.60
  4855.5  420.97  4913.9  418.96  4924.1  417.98  4936.7  418.11  4944.3  417.88
  4955.6  416.94  4962.1  416.61  4990.9  416.35  4991.2  415.85  4994.7  415.85
  4994.9  416.35  5011.7  416.38  5021.2  416.35  5050.8  417.94  5077.8  418.76
  5091.9  419.60  5106.0  420.06  5205.0  422.08  5233.3  423.20  5261.6  424.95
  5275.7  425.15  5289.9  426.17  5318.2  427.09  5360.6  429.46  5388.9  430.27
#Mann=7,-1,0
  4660.5    0.04       0  4855.5    0.03       0  4955.6    0.04       0
  4990.9    0.04       0  4994.9    0.04       0  5011.7    0.03       0
  5050.8    0.04       0
Bank Sta=4990.9,4994.9
Exp/Cntr=0.3,0.1

Type RM Length L Ch R = 1,786,254,254,254
BEGIN DESCRIPTION:
Mapping XS b158986d
END DESCRIPTION:
XS GIS Cut Line= 3
      2398532.02     13549130.80      2398170.91     13549016.22
      2397766.40     13549240.95
#Sta/Elev= 30
  4568.5  428.45  4608.4  427.89  4649.3  426.33  4705.2  425.08  4743.7  423.51
  4769.7  423.06  4802.0  421.25  4834.1  420.26  4848.6  420.07  4866.5  419.03
  4883.9  418.67  4898.8  417.67  4922.1  417.45  4973.5  415.17  4979.2  415.40
  4999.0  414.57  4999.2  414.07  5002.7  414.07  5003.0  414.57  5065.6  416.95
  5082.2  418.25  5103.9  418.54  5129.3  419.61  5194.3  421.47  5238.9  423.48
  5266.4  423.87  5288.1  425.18  5341.9  426.82  5377.4  428.83  5410.1  430.09
#Mann=7,-1,0
  4568.5    0.04       0  4834.1    0.03       0  4883.9    0.04       0
  4999.0    0.04       0  5003.0    0.04       0  5065.6    0.03       0
  5129.3    0.04       0
Bank Sta=4999,5003
Exp/Cntr=0.3,0.1

Type RM Length L Ch R = 1,532,430,430,430
BEGIN DESCRIPTION:
Mapping XS e3897f7f
END DESCRIPTION:
XS GIS Cut Line= 4
      2398552.82     13549012.72      2398233.41     13548811.36
      2398014.66     13548800.94      2397611.86     13549099.57
#Sta/Elev= 30
  4463.6  428.04  4504.3  426.71  4562.0  425.90  4604.4  424.32  4662.1  423.01
  4692.6  421.31  4802.1  417.62  4829.2  416.26  4919.7  413.61  4949.7  413.30
  4987.8  411.72  4988.0  411.22  4991.5  411.22  4991.8  411.72  5019.8  412.09
  5063.1  413.47  5070.7  414.33  5076.9  414.18  5127.0  415.79  5184.2  418.40
  5197.9  418.30  5220.9  418.98  5241.8  420.07  5277.2  420.92  5333.6  423.51
  5362.8  423.99  5406.6  426.20  5433.7  426.51  5477.6  428.84  5561.6  431.48
#Mann=3,-1,0
  4463.6    0.04       0  4987.8    0.04       0  4991.8    0.04       0
Bank Sta=4987.8,4991.8
Exp/Cntr=0.3,0.1

Type RM Length L Ch R = 1,102,0,0,0
BEGIN DESCRIPTION:
TRIB 3_2 TO THOMAS CREEK 1.0
END DESCRIPTION:
XS GIS Cut Line= 3
      2398611.85     13548762.72      2398074.54     13548404.75
      2397716.07     13548846.06
#Sta/Elev= 30
  4369.4  422.95  4545.9  418.25  4610.4  415.43  4775.6  410.41  4862.8  408.96
  4934.9  408.95  4990.0  407.21  4990.2  406.71  4993.7  406.71  4994.0  407.21
  5011.8  407.97  5036.4  407.41  5042.8  408.04  5050.8  407.64  5079.5  408.39
  5100.3  408.30  5143.4  409.61  5164.3  409.42  5170.7  410.04  5193.0  410.08
  5249.0  412.21  5277.7  412.49  5370.4  415.48  5391.2  415.63  5405.6  417.13
  5413.5  417.44  5469.5  418.74  5512.7  420.75  5541.4  421.15  5583.6  422.61
#Mann=3,-1,0
  4369.4    0.04       0  4990.0    0.04       0  4994.0    0.04       0
Bank Sta=4990,4994
Exp/Cntr=0.3,0.1

Chan Stop Cuts=-1