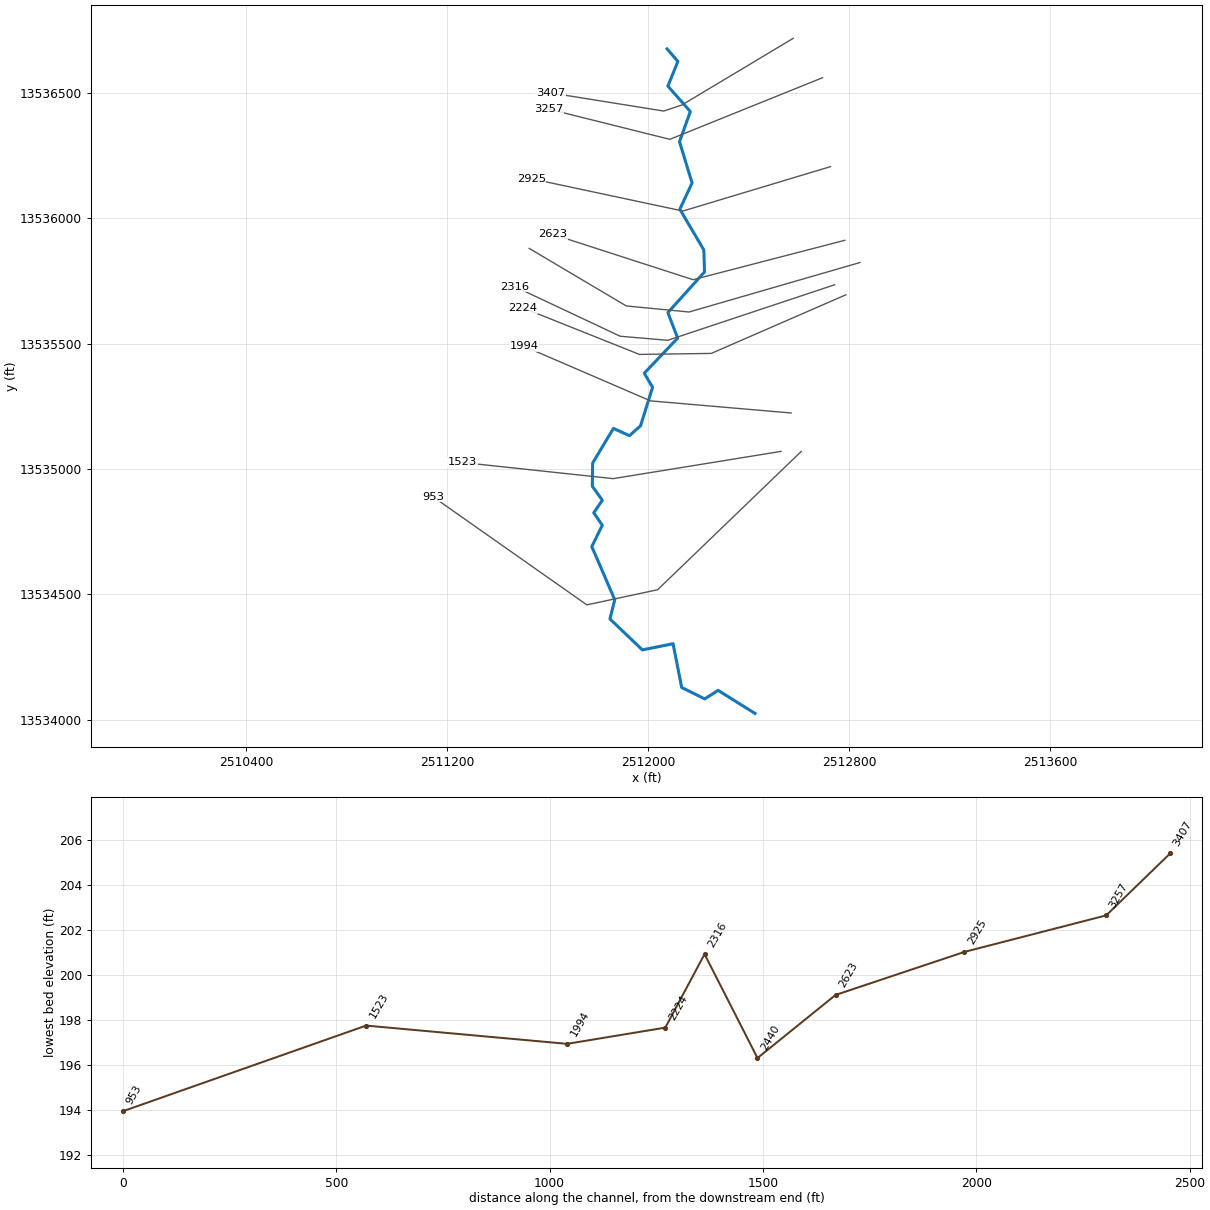
--- TRIB 4 TO BOGGY BRANCH.prj (project) ---

Proj Title=TRIB 4 TO BOGGY BRANCH Base Level Engineering
Current Plan=p01
Default Exp/Contr=0.3,0.1
English Units
Geom File=g01
Flow File=f01
Plan File=p01
BEGIN DESCRIPTION:
TRIB 4 TO BOGGY BRANCH
END DESCRIPTION:

--- TRIB 4 TO BOGGY BRANCH.p01 (plan) ---

Plan Title=Multiple Run
Short Identifier=Multiple
Geom File=g01
Flow File=f01
Subcritical Flow
K Sum by GR= 0
Std Step Tol= 0.01
Critical Tol= 0.01
Num of Std Step Trials= 20
Max Error Tol= 0.3
Flow Tol Ratio= 0.001
Split Flow NTrial= 30
Split Flow Tol= 0.02
Split Flow Ratio= 0.02
Log Output Level= 0
Friction Slope Method= 1
Unsteady Friction Slope Method= 2
Unsteady Bridges Friction Slope Method= 1
Parabolic Critical Depth
Global Vel Dist=  1 , 1 , 1
Global Log Level= 0
CheckData=True
Encroach Param= -1, 0, 0, 0
BEGIN DESCRIPTION:
Multiple Run
END DESCRIPTION:

--- TRIB 4 TO BOGGY BRANCH.f01 (steady flow) ---

Flow Title=Multiple
Number of Profiles=7
Profile Names=10-year,25-year,50-year,1pct_min,100-year,1pct_plu,500-year
River Rch & RM= TRIB 4 TO BOGGY ,Reach-1,3407
     384     593     773     489     975    1945    1530
River Rch & RM= TRIB 4 TO BOGGY ,Reach-1,953
     460     716     937     595    1186    2367    1878
Boundary for River Rch & Prof#=TRIB 4 TO BOGGY ,Reach-1,1
Up Type=0
Dn Type=3
Dn Slope=0.005
Boundary for River Rch & Prof#=TRIB 4 TO BOGGY ,Reach-1,2
Up Type=0
Dn Type=3
Dn Slope=0.005
Boundary for River Rch & Prof#=TRIB 4 TO BOGGY ,Reach-1,3
Up Type=0
Dn Type=3
Dn Slope=0.005
Boundary for River Rch & Prof#=TRIB 4 TO BOGGY ,Reach-1,4
Up Type=0
Dn Type=3
Dn Slope=0.005
Boundary for River Rch & Prof#=TRIB 4 TO BOGGY ,Reach-1,5
Up Type=0
Dn Type=3
Dn Slope=0.005
Boundary for River Rch & Prof#=TRIB 4 TO BOGGY ,Reach-1,6
Up Type=0
Dn Type=3
Dn Slope=0.005
Boundary for River Rch & Prof#=TRIB 4 TO BOGGY ,Reach-1,7
Up Type=0
Dn Type=3
Dn Slope=0.005

--- TRIB 4 TO BOGGY BRANCH.g01 (geometry) ---

Geom Title=Existing Conditions

River Reach=TRIB 4 TO BOGGY ,Reach-1
Reach XY= 30
      2512075.00     13536675.00      2512118.05     13536625.12
      2512078.17     13536526.64      2512167.67     13536425.10
      2512124.42     13536304.96      2512174.60     13536140.27
      2512125.75     13536035.68      2512221.33     13535873.41
      2512224.07     13535785.48      2512078.16     13535623.35
      2512117.18     13535521.59      2511984.30     13535381.67
      2512017.20     13535325.10      2511969.48     13535172.03
      2511925.23     13535132.47      2511861.32     13535161.49
      2511778.68     13535023.42      2511777.36     13534930.89
      2511817.21     13534874.90      2511783.03     13534825.00
      2511817.19     13534775.09      2511775.15     13534690.42
      2511866.71     13534478.22      2511847.51     13534401.66
      2511976.65     13534278.16      2512098.86     13534302.75
      2512133.11     13534128.31      2512225.05     13534082.75
      2512278.23     13534116.78      2512425.00     13534025.00

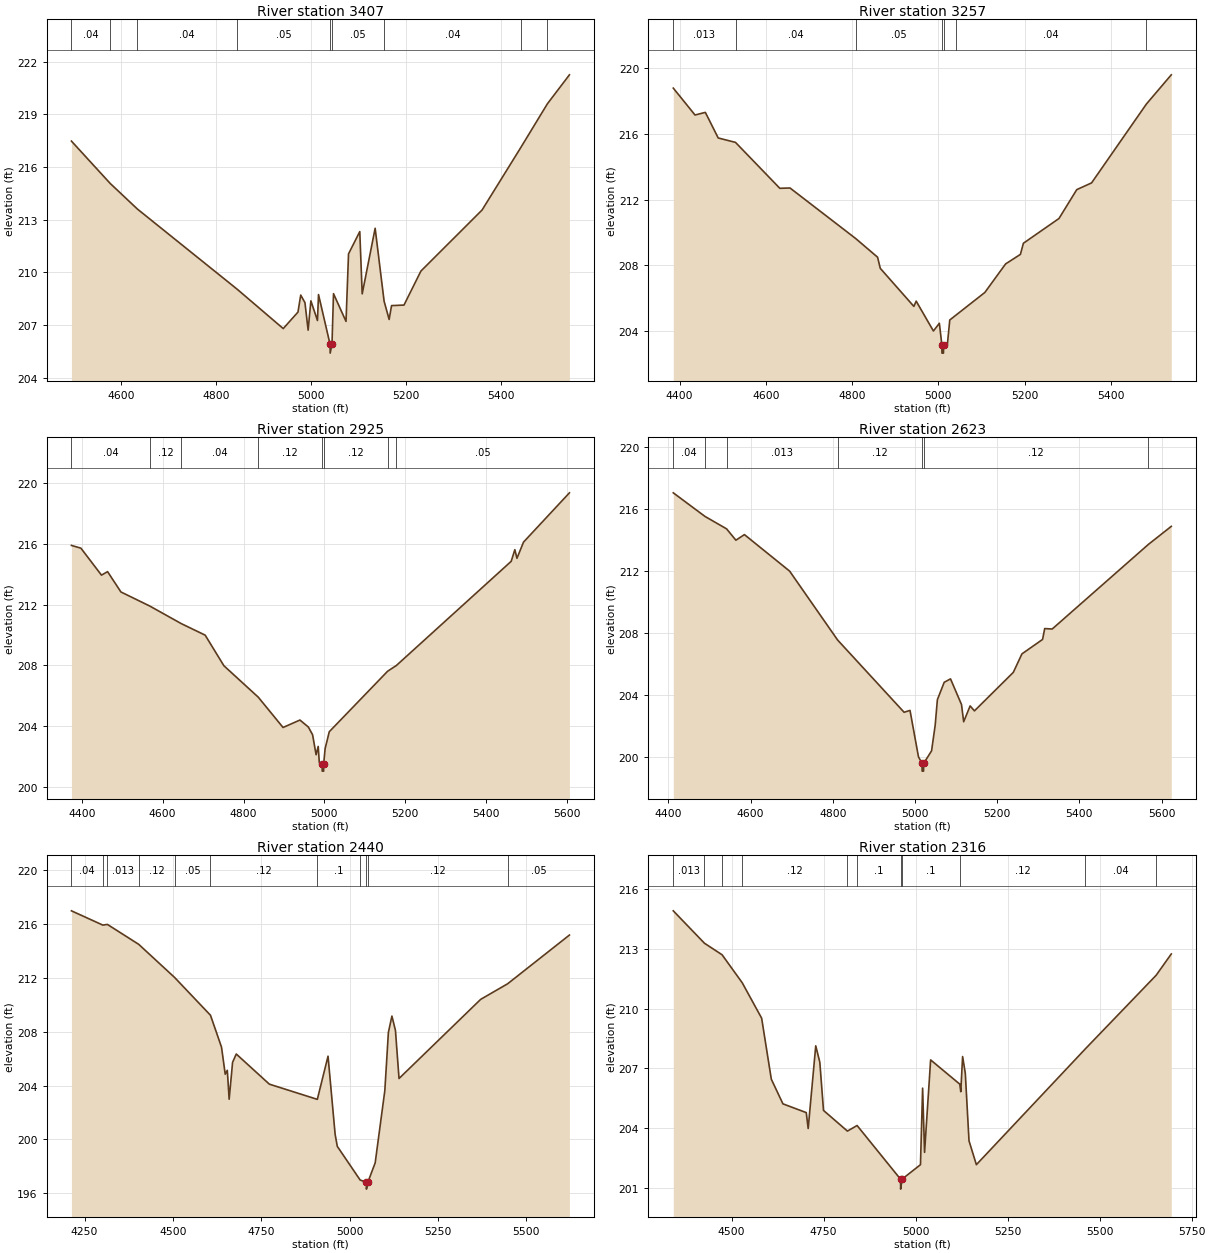
Type RM Length L Ch R = 1,3407,150,150,150
BEGIN DESCRIPTION:
Mapping XS c8d2c46e
END DESCRIPTION:
XS GIS Cut Line= 4
      2512577.16     13536717.14      2512134.13     13536451.32
      2512061.63     13536427.15      2511610.60     13536499.64
#Sta/Elev= 30
  4494.5  217.48  4576.1  215.07  4633.4  213.61  4844.1  209.03  4941.0  206.79
  4972.1  207.73  4977.9  208.70  4986.8  208.27  4993.5  206.70  4999.3  208.37
  5013.2  207.25  5015.4  208.73  5039.8  205.89  5040.0  205.39  5043.8  205.89
  5047.0  208.78  5073.4  207.20  5078.7  211.05  5102.4  212.32  5107.5  208.77
  5134.8  212.51  5153.7  208.35  5164.3  207.31  5169.4  208.10  5195.6  208.13
  5231.3  210.07  5360.2  213.55  5442.0  217.12  5498.0  219.61  5544.4  221.26
#Mann=9,-1,0
  4494.5    0.04       0  4576.1   0.013       0  4633.4    0.04       0
  4844.1    0.05       0  5039.8    0.05       0  5043.8    0.05       0
  5153.7    0.04       0  5442.0    0.05       0  5498.0    0.04       0
Bank Sta=5039.8,5043.8
Exp/Cntr=0.3,0.1

Type RM Length L Ch R = 1,3257,332,332,332
BEGIN DESCRIPTION:
Mapping XS 0fd3c891
END DESCRIPTION:
XS GIS Cut Line= 3
      2512693.91     13536560.04      2512085.80     13536314.38
      2511602.52     13536435.20
#Sta/Elev= 30
  4385.6  218.80  4436.0  217.16  4459.9  217.32  4489.7  215.76  4529.8  215.49
  4632.5  212.69  4656.1  212.71  4808.2  209.63  4859.0  208.49  4865.3  207.81
  4943.1  205.49  4948.5  205.81  4988.4  203.99  5002.2  204.46  5008.0  203.14
  5008.2  202.64  5011.7  202.64  5012.0  203.14  5020.7  203.16  5026.3  204.66
  5040.3  204.95  5107.6  206.34  5155.7  208.08  5190.0  208.66  5196.9  209.34
  5279.4  210.85  5320.6  212.61  5354.9  213.02  5482.0  217.83  5539.6  219.61
#Mann=7,-1,0
  4385.6   0.013       0  4529.8    0.04       0  4808.2    0.05       0
  5008.0    0.05       0  5012.0    0.05       0  5040.3    0.04       0
  5482.0    0.05       0
Bank Sta=5008,5012
Exp/Cntr=0.3,0.1

Type RM Length L Ch R = 1,2925,302,302,302
BEGIN DESCRIPTION:
Mapping XS d3c423d0
END DESCRIPTION:
XS GIS Cut Line= 3
      2512726.12     13536205.63      2512138.15     13536028.43
      2511534.04     13536157.31
#Sta/Elev= 30
  4374.4  215.91  4397.8  215.73  4448.7  213.95  4463.8  214.18  4496.8  212.84
  4567.5  211.92  4646.2  210.75  4705.2  209.99  4751.6  207.97  4836.5  205.90
  4897.8  203.90  4939.6  204.39  4960.4  203.93  4970.9  203.42  4979.6  202.10
  4984.8  202.65  4987.5  201.59  4994.4  201.52  4994.7  201.02  4998.2  201.02
  4998.4  201.52  5001.9  202.51  5012.2  203.62  5156.5  207.61  5178.2  207.99
  5462.1  214.86  5471.2  215.63  5476.4  215.06  5492.7  216.13  5606.2  219.38
#Mann=8,-1,0
  4374.4    0.04       0  4567.5    0.12       0  4646.2    0.04       0
  4836.5    0.12       0  4994.4    0.04       0  4998.4    0.12       0
  5156.5    0.12       0  5178.2    0.05       0
Bank Sta=4994.4,4998.4
Exp/Cntr=0.3,0.1

Type RM Length L Ch R = 1,2623,183,183,183
BEGIN DESCRIPTION:
Mapping XS 642d6eff
END DESCRIPTION:
XS GIS Cut Line= 3
      2512782.52     13535911.63      2512178.43     13535754.57
      2511619.28     13535935.59
#Sta/Elev= 30
  4411.8  217.03  4489.0  215.51  4541.5  214.71  4564.2  213.98  4584.9  214.34
  4694.9  211.99  4811.8  207.55  4973.5  202.90  4987.9  203.02  5008.5  200.03
  5017.2  199.61  5017.4  199.11  5020.9  199.11  5021.2  199.61  5040.4  200.42
  5049.2  202.08  5054.5  203.71  5071.1  204.83  5086.5  205.05  5113.2  203.40
  5118.5  202.29  5134.2  203.31  5144.7  202.99  5239.3  205.47  5260.3  206.66
  5310.5  207.59  5315.7  208.29  5333.9  208.26  5567.6  213.70  5623.7  214.87
#Mann=7,-1,0
  4411.8    0.04       0  4489.0    0.12       0  4541.5   0.013       0
  4811.8    0.12       0  5017.2    0.05       0  5021.2    0.12       0
  5567.6    0.05       0
Bank Sta=5017.2,5021.2
Exp/Cntr=0.3,0.1

Type RM Length L Ch R = 1,2440,124,124,124
BEGIN DESCRIPTION:
Mapping XS c543cff1
END DESCRIPTION:
XS GIS Cut Line= 4
      2512842.95     13535823.03      2512162.32     13535625.69
      2511912.62     13535649.85      2511525.96     13535879.43
#Sta/Elev= 30
  4212.8  216.99  4301.6  215.93  4314.6  215.98  4403.2  214.50  4504.7  212.04
  4606.3  209.23  4637.5  206.86  4648.0  204.85  4653.9  205.14  4659.1  202.99
  4668.8  205.73  4679.2  206.35  4772.9  204.11  4908.6  202.98  4938.9  206.19
  4959.0  200.38  4965.1  199.49  5029.7  196.99  5047.4  196.81  5047.6  196.31
  5051.4  196.81  5072.3  198.26  5099.6  203.63  5109.7  207.95  5119.7  209.17
  5129.7  208.10  5139.8  204.53  5370.8  210.41  5447.2  211.57  5622.0  215.19
#Mann=11,-1,0
  4212.8    0.04       0  4301.6    0.12       0  4314.6   0.013       0
  4403.2    0.12       0  4504.7    0.05       0  4606.3    0.12       0
  4908.6     0.1       0  5029.7    0.12       0  5047.4    0.05       0
  5051.4    0.12       0  5447.2    0.05       0
Bank Sta=5047.4,5051.4
Exp/Cntr=0.3,0.1

Type RM Length L Ch R = 1,2316,92,92,92
BEGIN DESCRIPTION:
Mapping XS 405daae8
END DESCRIPTION:
XS GIS Cut Line= 4
      2512742.24     13535734.42      2512077.74     13535512.92
      2511888.45     13535529.03      2511469.81     13535726.27
#Sta/Elev= 30
  4341.4  214.92  4426.1  213.29  4474.0  212.71  4528.8  211.30  4581.5  209.52
  4607.8  206.45  4639.4  205.21  4702.7  204.77  4708.0  203.97  4728.5  208.13
  4739.6  207.30  4749.6  204.88  4814.6  203.84  4840.9  204.12  4958.9  201.42
  4959.2  200.92  4962.9  201.42  5013.1  202.15  5018.9  206.00  5024.2  202.77
  5040.7  207.42  5120.0  206.20  5122.6  205.82  5127.6  207.59  5134.9  206.75
  5145.0  203.35  5165.0  202.15  5461.3  207.98  5653.6  211.68  5694.6  212.75
#Mann=11,-1,0
  4341.4   0.013       0  4426.1    0.12       0  4474.0    0.05       0
  4528.8    0.12       0  4814.6    0.05       0  4840.9     0.1       0
  4958.9    0.05       0  4962.9     0.1       0  5120.0    0.12       0
  5461.3    0.04       0  5653.6    0.05       0
Bank Sta=4958.9,4962.9
Exp/Cntr=0.3,0.1

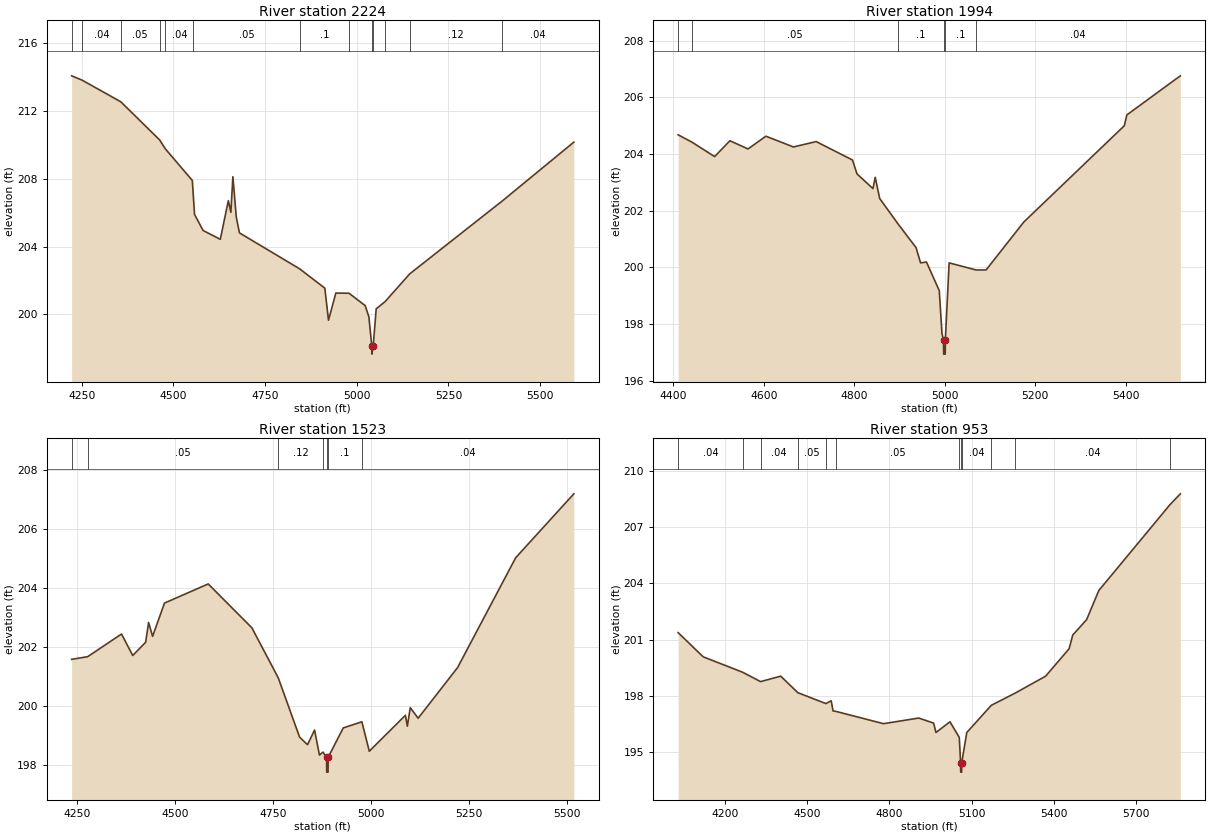
Type RM Length L Ch R = 1,2224,230,230,230
BEGIN DESCRIPTION:
Mapping XS 0a8d6412
END DESCRIPTION:
XS GIS Cut Line= 4
      2512786.54     13535694.14      2512250.92     13535460.56
      2511964.97     13535456.53      2511501.77     13535641.81
#Sta/Elev= 30
  4222.7  214.07  4250.7  213.82  4356.7  212.54  4462.6  210.29  4478.0  209.77
  4551.7  207.90  4554.8  206.87  4557.7  205.90  4581.1  204.95  4628.0  204.43
  4649.9  206.71  4656.8  206.02  4662.3  208.12  4671.7  205.72  4680.2  204.81
  4844.3  202.69  4913.0  201.55  4923.0  199.66  4943.0  201.26  4979.1  201.25
  5023.0  200.52  5033.0  199.87  5041.0  198.16  5041.2  197.66  5045.0  198.16
  5053.0  200.33  5077.4  200.76  5144.3  202.39  5397.3  206.70  5591.9  210.16
#Mann=13,-1,0
  4222.7   0.013       0  4250.7    0.04       0  4356.7    0.05       0
  4462.6    0.12       0  4478.0    0.04       0  4554.8    0.05       0
  4844.3     0.1       0  4979.1    0.12       0  5041.0    0.05       0
  5045.0    0.12       0  5077.4    0.04       0  5144.3    0.12       0
  5397.3    0.04       0
Bank Sta=5041,5045
Exp/Cntr=0.3,0.1

Type RM Length L Ch R = 1,1994,471,471,471
BEGIN DESCRIPTION:
Mapping XS 73fc3b39
END DESCRIPTION:
XS GIS Cut Line= 3
      2512569.07     13535222.94      2512009.27     13535271.27
      2511505.83     13535488.76
#Sta/Elev= 30
  4410.8  204.68  4441.4  204.42  4491.5  203.91  4525.3  204.47  4565.4  204.18
  4604.8  204.63  4665.8  204.25  4716.0  204.44  4796.3  203.79  4806.3  203.30
  4841.6  202.78  4846.6  203.18  4856.5  202.43  4897.3  201.53  4936.8  200.70
  4946.9  200.16  4959.9  200.19  4988.2  199.18  4994.2  197.66  4997.6  197.44
  4997.9  196.94  5001.4  196.94  5001.6  197.44  5010.0  200.16  5069.4  199.91
  5091.7  199.91  5175.0  201.60  5397.4  205.00  5402.9  205.38  5521.1  206.76
#Mann=6,-1,0
  4410.8    0.04       0  4441.4    0.05       0  4897.3     0.1       0
  4997.6    0.05       0  5001.6     0.1       0  5069.4    0.04       0
Bank Sta=4997.6,5001.6
Exp/Cntr=0.3,0.1

Type RM Length L Ch R = 1,1523,570,570,570
BEGIN DESCRIPTION:
Mapping XS 689aaf5b
END DESCRIPTION:
XS GIS Cut Line= 3
      2512528.77     13535069.89      2511860.26     13534961.16
      2511260.20     13535025.59
#Sta/Elev= 30
  4236.2  201.58  4277.0  201.67  4363.4  202.44  4392.0  201.71  4424.9  202.16
  4432.5  202.83  4442.6  202.36  4473.0  203.49  4584.5  204.14  4695.9  202.65
  4763.2  200.95  4817.5  198.94  4837.8  198.68  4855.7  199.18  4868.2  198.33
  4877.2  198.43  4886.4  198.25  4886.7  197.75  4890.2  197.75  4890.4  198.25
  4928.8  199.25  4976.4  199.46  4995.3  198.46  5087.4  199.68  5092.4  199.31
  5099.8  199.94  5119.9  199.58  5220.5  201.30  5368.7  205.03  5517.0  207.20
#Mann=7,-1,0
  4236.2    0.04       0  4277.0    0.05       0  4763.2    0.12       0
  4877.2     0.1       0  4886.4    0.04       0  4890.4     0.1       0
  4976.4    0.04       0
Bank Sta=4886.4,4890.4
Exp/Cntr=0.3,0.1

Type RM Length L Ch R = 1,953,0,0,0
BEGIN DESCRIPTION:
Mapping XS 987a35c6
END DESCRIPTION:
XS GIS Cut Line= 4
      2512609.38     13535069.91      2512037.47     13534518.14
      2511755.54     13534457.72      2511143.34     13534888.68
#Sta/Elev= 30
  4029.4  201.38  4120.8  200.09  4264.6  199.27  4330.1  198.77  4403.7  199.06
  4466.2  198.18  4568.5  197.60  4587.7  197.75  4594.6  197.21  4606.1  197.18
  4778.6  196.53  4907.0  196.83  4961.5  196.56  4969.8  196.06  5020.9  196.63
  5054.9  195.80  5059.8  194.45  5060.1  193.95  5063.6  193.95  5063.8  194.45
  5082.3  196.06  5171.9  197.51  5259.1  198.16  5369.9  199.06  5455.5  200.52
  5468.8  201.25  5519.4  202.07  5563.8  203.62  5823.2  208.19  5861.1  208.77
#Mann=12,-1,0
  4029.4    0.04       0  4264.6    0.05       0  4330.1    0.04       0
  4466.2    0.05       0  4568.5    0.04       0  4606.1    0.05       0
  5054.9    0.04       0  5059.8    0.05       0  5063.8    0.04       0
  5171.9    0.12       0  5259.1    0.04       0  5823.2    0.03       0
Bank Sta=5059.8,5063.8
Exp/Cntr=0.3,0.1

Chan Stop Cuts=-1