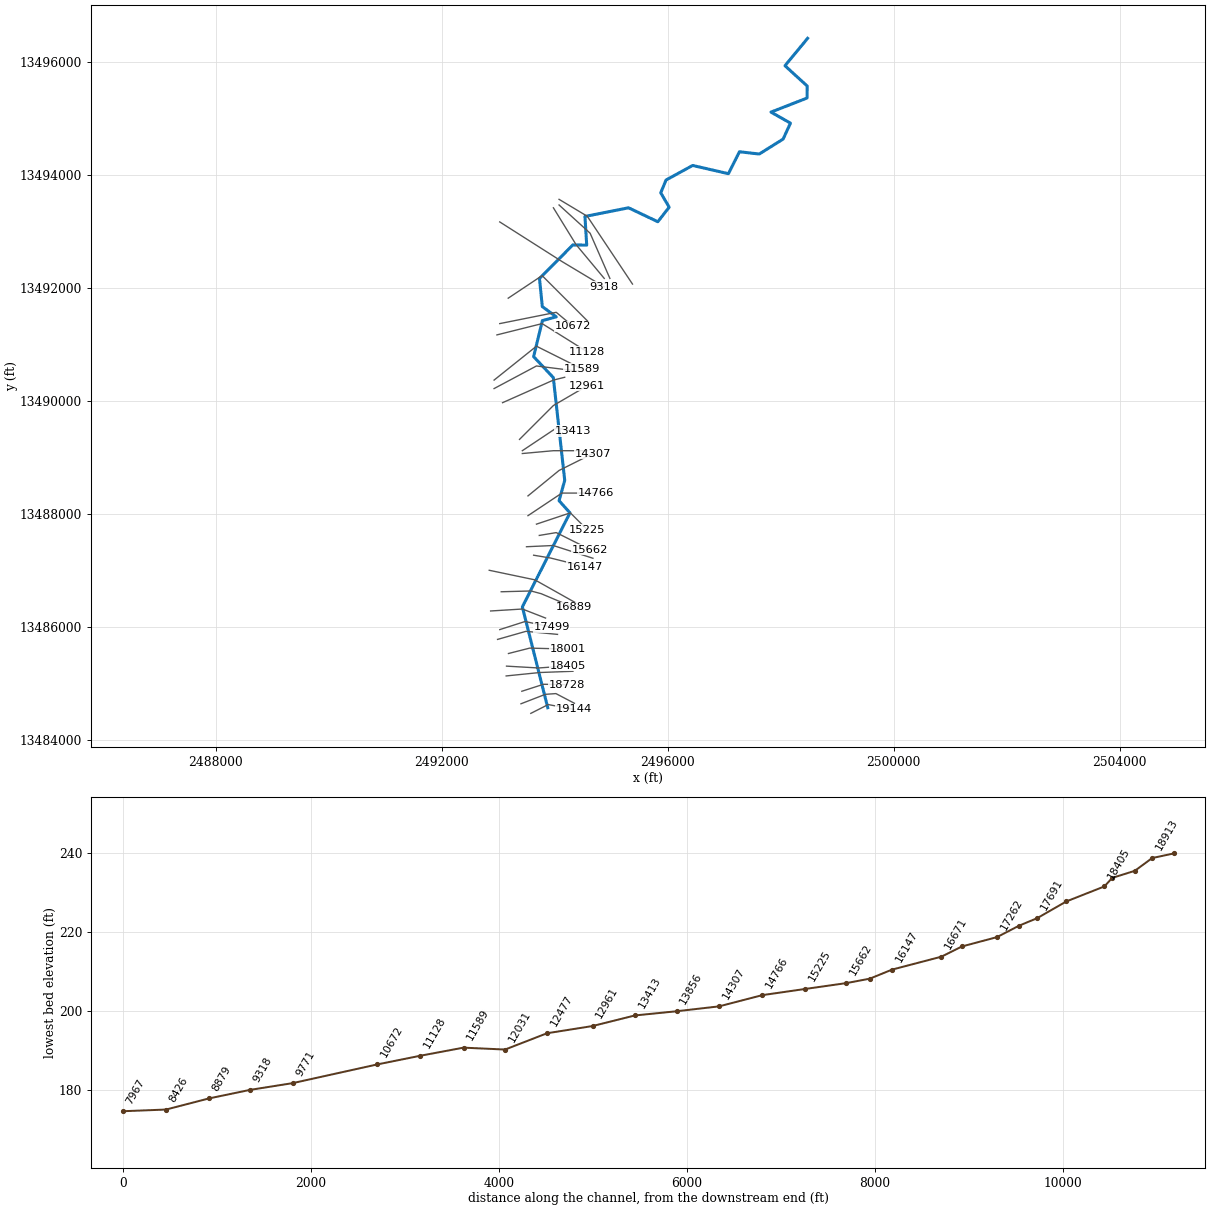
--- TRIB 4 TO EIGHTEENMILE CREEK.prj (project) ---

Proj Title=TRIB 4 TO EIGHTEENMILE CREEK Base Level Engineering
Current Plan=p01
Default Exp/Contr=0.3,0.1
English Units
Geom File=g01
Flow File=f01
Plan File=p01
Y Axis Title=Elevation
X Axis Title(PF)=Main Channel Distance
X Axis Title(XS)=Station
BEGIN DESCRIPTION:
TRIB 4 TO EIGHTEENMILE CREEK
END DESCRIPTION:
DSS Export Rating Curves= 0
DSS Export Rating Curve Sorted= 0
DSS Export Volume Flow Curves= 0
DXF OffsetX= 0
DXF OffsetY= 0
DXF ScaleX= 1
DXF ScaleY= 10

--- TRIB 4 TO EIGHTEENMILE CREEK.p01 (plan) ---

Plan Title=Multiple Run
Short Identifier=Multiple
Geom File=g01
Flow File=f01
Subcritical Flow
K Sum by GR= 0
Std Step Tol= 0.01
Critical Tol= 0.01
Num of Std Step Trials= 20
Max Error Tol= 0.3
Flow Tol Ratio= 0.001
Split Flow NTrial= 30
Split Flow Tol= 0.02
Split Flow Ratio= 0.02
Log Output Level= 0
Friction Slope Method= 1
Unsteady Friction Slope Method= 2
Unsteady Bridges Friction Slope Method= 1
Parabolic Critical Depth
Global Vel Dist=  1 , 1 , 1
Global Log Level= 0
CheckData=True
Encroach Param= -1, 0, 0, 0
BEGIN DESCRIPTION:
Multiple Run
END DESCRIPTION:

--- TRIB 4 TO EIGHTEENMILE CREEK.f01 (steady flow) ---

Flow Title=Multiple
Number of Profiles=7
Profile Names=10-year,25-year,50-year,1pct_min,100-year,1pct_plu,500-year
River Rch & RM= TRIB 4 TO EIGHTE,Reach-1,19144
     256     388     499     313     624    1245     960
River Rch & RM= TRIB 4 TO EIGHTE,Reach-1,16147
     730    1178    1582    1028    2050    4091    3408
River Rch & RM= TRIB 4 TO EIGHTE,Reach-1,9318
    2140    3632    5043    3375    6733   13435   11889
River Rch & RM= TRIB 4 TO EIGHTE,Reach-1,4713
    2393    4079    5681    3811    7604   15172   13497
Boundary for River Rch & Prof#=TRIB 4 TO EIGHTE,Reach-1,1
Up Type=0
Dn Type=3
Dn Slope=0.005
Boundary for River Rch & Prof#=TRIB 4 TO EIGHTE,Reach-1,2
Up Type=0
Dn Type=3
Dn Slope=0.005
Boundary for River Rch & Prof#=TRIB 4 TO EIGHTE,Reach-1,3
Up Type=0
Dn Type=3
Dn Slope=0.005
Boundary for River Rch & Prof#=TRIB 4 TO EIGHTE,Reach-1,4
Up Type=0
Dn Type=3
Dn Slope=0.005
Boundary for River Rch & Prof#=TRIB 4 TO EIGHTE,Reach-1,5
Up Type=0
Dn Type=3
Dn Slope=0.005
Boundary for River Rch & Prof#=TRIB 4 TO EIGHTE,Reach-1,6
Up Type=0
Dn Type=3
Dn Slope=0.005
Boundary for River Rch & Prof#=TRIB 4 TO EIGHTE,Reach-1,7
Up Type=0
Dn Type=3
Dn Slope=0.005

--- TRIB 4 TO EIGHTEENMILE CREEK.g01 (geometry) ---

Geom Title=Existing Conditions
Program Version=4.10

River Reach=TRIB 4 TO EIGHTE,Reach-1
Reach XY= 30
        2493875.       13484575.      2493425.37     13486359.73
      2494268.01     13488025.22      2494075.37     13488240.27
      2494175.32     13488600.11      2493973.04     13490419.35
      2493624.91     13490790.36      2493779.99     13491427.62
      2494025.26     13491494.94      2493778.36     13491676.25
      2493728.54     13492173.54      2494318.81     13492767.25
      2494564.65     13492764.76      2494533.25     13493271.93
      2495305.02     13493425.04      2495823.54     13493178.53
      2496024.26     13493435.69      2495875.37     13493690.17
      2495968.93     13493916.87      2496440.16     13494174.62
      2497073.55     13494028.53      2497268.81     13494417.19
      2497619.11     13494376.97      2498041.67     13494641.65
      2498171.57     13494923.78      2497826.56     13495118.92
      2498465.71     13495368.31      2498467.25     13495581.19
      2498074.52     13495940.16        2498475.       13496425.

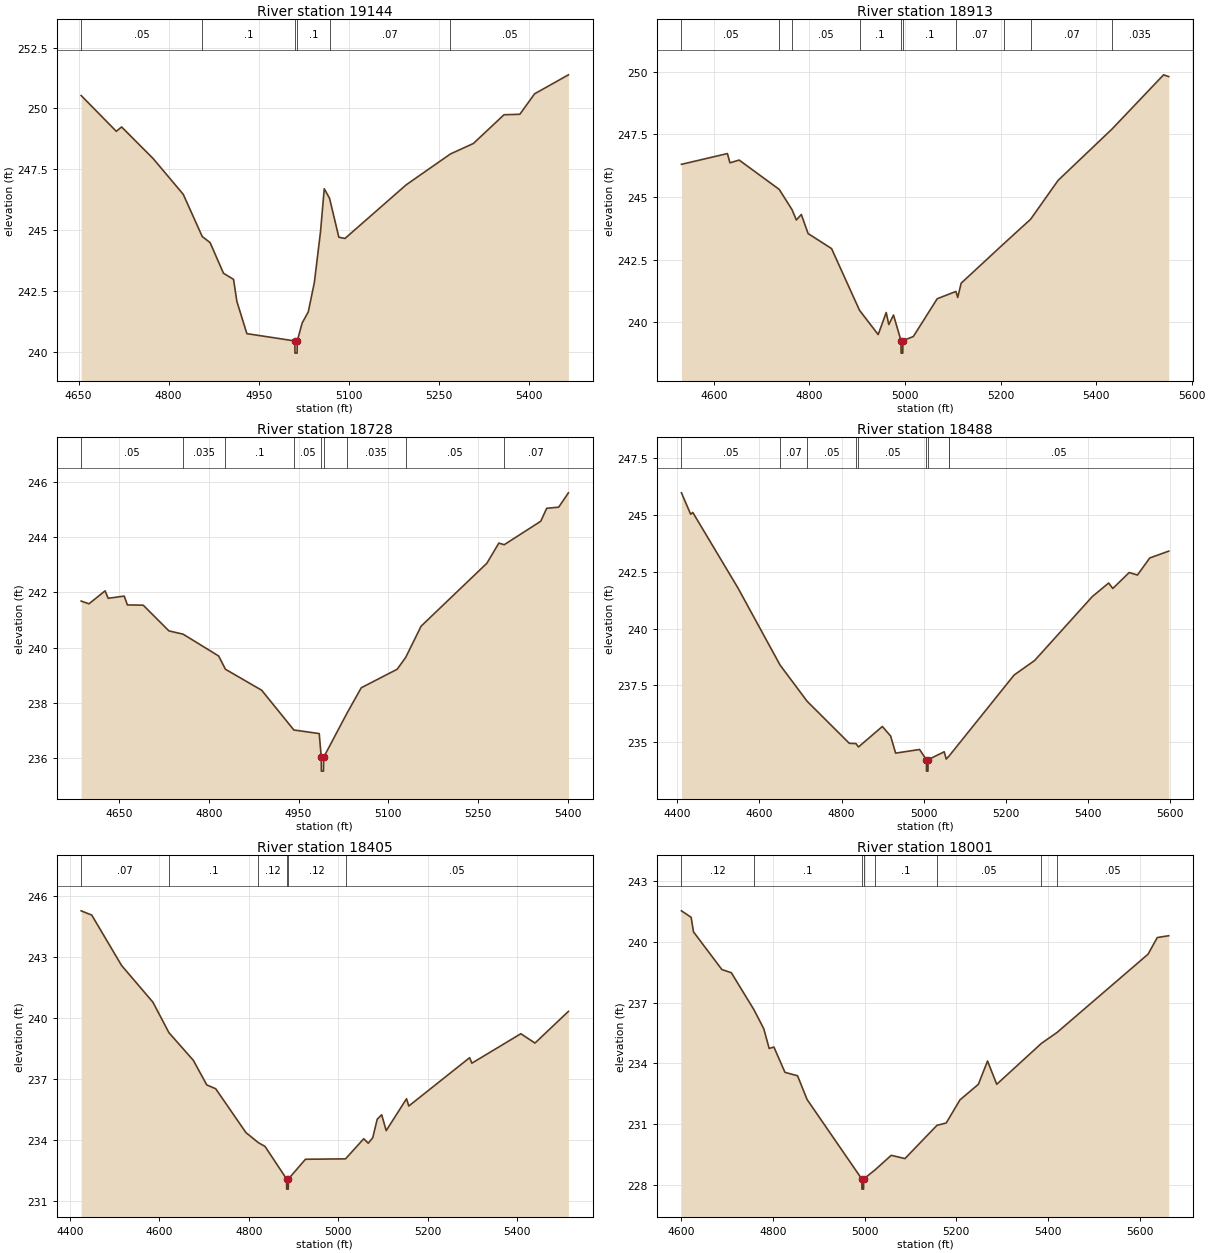
Type RM Length L Ch R = 1 ,19144   ,231,231,231
BEGIN DESCRIPTION:
TRIB 4 TO EIGHTEENMILE CREEK 37.0
END DESCRIPTION:
XS GIS Cut Line= 3
      2493574.96     13484474.98      2493883.32     13484631.04
      2494340.34     13484545.27
#Sta/Elev= 30
  4654.4  250.53  4712.9  249.06  4721.7  249.24  4774.2  247.94  4824.3  246.47
  4855.8  244.74  4868.9  244.49  4891.2  243.23  4907.9  242.98  4913.5  242.07
  4930.1  240.75  5009.9  240.45  5010.1  239.95  5013.6  239.95  5013.9  240.45
  5022.1  241.19  5032.2  241.64  5042.4  242.86  5052.6  244.94  5058.8   246.7
  5067.6  246.31  5083.1  244.71  5093.3  244.66    5195  246.86  5268.7  248.13
  5306.9  248.56  5357.8  249.74  5384.2  249.76  5408.7   250.6    5465  251.38
#Mann= 6 ,-1 , 0
  4654.4     .05       0  4855.8      .1       0  5009.9     .05       0
  5013.9      .1       0  5067.6     .07       0  5268.7     .05       0
Bank Sta=5009.9,5013.9
XS Rating Curve= 0 ,0
Exp/Cntr=0.3,0.1

Type RM Length L Ch R = 1 ,18913   ,185,185,185
BEGIN DESCRIPTION:
Mapping XS c51b62ad
END DESCRIPTION:
XS GIS Cut Line= 4
      2493400.97     13484645.03      2493832.84     13484812.14
      2494019.47     13484825.16      2494347.17     13484653.71
#Sta/Elev= 30
    4532   246.3  4628.2  246.73  4633.5  246.36  4652.8  246.47  4736.7   245.3
  4763.5  244.49  4772.5  244.08  4782.9   244.3  4797.1  243.54  4846.2  242.94
  4904.7  240.48  4943.8  239.51  4960.6  240.39    4966  239.91  4975.9  240.29
  4991.5  239.27  4991.8  238.77  4995.3  238.77  4995.5  239.27  5017.3  239.43
  5067.4  240.94  5106.5  241.23  5110.3  240.99  5117.5  241.56  5208.2  243.16
  5262.9  244.11  5320.4  245.66  5433.4  247.71  5541.2  249.87    5552   249.8
#Mann= 10 ,-1 , 0
    4532     .05       0  4736.7    .035       0  4763.5     .05       0
  4904.7      .1       0  4991.5     .05       0  4995.5      .1       0
  5106.5     .07       0  5208.2    .035       0  5262.9     .07       0
  5433.4    .035       0
Bank Sta=4991.5,4995.5
XS Rating Curve= 0 ,0
Exp/Cntr=0.3,0.1

Type RM Length L Ch R = 1 ,18728   ,240,240,240
BEGIN DESCRIPTION:
Mapping XS b99a22ce
END DESCRIPTION:
XS GIS Cut Line= 3
      2493416.17     13484866.39      2493800.28     13484990.09
       2494211.3      13484983.6
#Sta/Elev= 30
  4586.6  241.69  4599.7  241.59  4626.6  242.06  4631.8  241.79  4658.6  241.87
  4663.9  241.55  4690.4  241.54  4733.3  240.61  4757.1  240.49  4816.5   239.7
  4827.8  239.22  4888.4  238.46  4942.2  237.02  4984.6  236.89    4988  236.03
  4988.2  235.53  4991.7  235.53    4992  236.03  5030.8  237.62  5054.9  238.55
  5114.9  239.22  5129.2  239.65  5154.9  240.78  5264.9  243.06  5284.9  243.79
  5293.8  243.73  5354.9  244.58  5364.9  245.05  5384.9  245.09  5401.2  245.61
#Mann= 9 ,-1 , 0
  4586.6     .05       0  4757.1    .035       0  4827.8      .1       0
  4942.2     .05       0    4988     .05       0    4992     .05       0
  5030.8    .035       0  5129.2     .05       0  5293.8     .07       0
Bank Sta=4988,4992
XS Rating Curve= 0 ,0
Exp/Cntr=0.3,0.1

Type RM Length L Ch R = 1 ,18488   ,83,83,83
BEGIN DESCRIPTION:
Mapping XS 8616b350
END DESCRIPTION:
XS GIS Cut Line= 3
       2493138.4     13485137.66      2493737.35     13485198.42
      2494321.12     13485220.12
#Sta/Elev= 30
  4410.2  245.96  4432.6  245.02  4437.7   245.1  4547.5  241.79  4650.2   238.4
    4716  236.81  4818.9  234.96    4835  234.95  4841.1   234.8  4899.3   235.7
  4919.4  235.28  4931.6  234.53  4989.8  234.69  5006.5  234.24  5006.8  233.74
  5010.3  233.74  5010.5  234.24  5049.8  234.59  5054.8  234.27  5060.4  234.38
  5061.1  234.39    5220  237.96  5270.1   238.6  5410.1   241.4  5450.2     242
  5460.2  241.76  5500.2  242.46  5520.2  242.35  5550.2   243.1  5596.4   243.4
#Mann= 9 ,-1 , 0
  4410.2     .05       0  4650.2     .07       0    4716     .05       0
    4835    .035       0  4841.1     .05       0  5006.5     .05       0
  5010.5     .05       0  5060.4    .035       0  5061.1     .05       0
Bank Sta=5006.5,5010.5
XS Rating Curve= 0 ,0
Exp/Cntr=0.3,0.1

Type RM Length L Ch R = 1 ,18405   ,404,404,404
BEGIN DESCRIPTION:
Mapping XS 888f33d0
END DESCRIPTION:
XS GIS Cut Line= 3
      2493144.86     13485311.27      2493711.31     13485278.72
      2494231.02     13485315.53
#Sta/Elev= 30
  4425.5  245.28  4449.2  245.07  4515.8  242.59  4585.9  240.78  4621.6  239.28
  4676.1  237.92  4706.1  236.71  4726.1  236.52  4793.7  234.36  4821.2  233.87
  4836.3  233.68  4884.4  232.08  4884.6  231.58  4888.1  231.58  4888.4  232.08
  4926.5  233.05    5016  233.07  5056.7  234.06  5066.8  233.84  5076.8  234.11
  5086.8  235.02  5096.8  235.24  5106.9  234.46  5152.3  236.03  5157.3  235.67
  5293.2  238.05  5298.2  237.78  5407.6  239.23  5439.2  238.77  5513.9  240.33
#Mann= 6 ,-1 , 0
  4425.5     .07       0  4621.6      .1       0  4821.2     .12       0
  4884.4     .05       0  4888.4     .12       0    5016     .05       0
Bank Sta=4884.4,4888.4
XS Rating Curve= 0 ,0
Exp/Cntr=0.3,0.1

Type RM Length L Ch R = 1 ,18001   ,310,310,310
BEGIN DESCRIPTION:
Mapping XS 9ffaa928
END DESCRIPTION:
XS GIS Cut Line= 3
      2493179.58     13485534.78      2493555.06     13485630.28
      2494230.01     13485612.92
#Sta/Elev= 30
  4600.5  241.53  4621.6  241.21  4626.8  240.49  4688.6  238.63  4709.3  238.47
  4758.7  236.64  4780.1   235.7  4791.8  234.73  4802.1   234.8  4826.2  233.55
  4853.7  233.38  4874.4  232.21  4993.8  228.28  4994.1  227.78  4997.6  227.78
  4997.8  228.28  5022.1  228.72  5057.9  229.45  5087.9  229.29  5157.6  230.93
  5177.9  231.05  5207.9  232.19    5248  232.96    5268  234.11    5288  232.96
  5385.4  234.98  5419.5  235.52  5618.1  239.39  5638.1  240.21  5663.1   240.3
#Mann= 8 ,-1 , 0
  4600.5     .12       0  4758.7      .1       0  4993.8     .05       0
  4997.8      .1       0  5022.1      .1       0  5157.6     .05       0
  5385.4    .035       0  5419.5     .05       0
Bank Sta=4993.8,4997.8
XS Rating Curve= 0 ,0
Exp/Cntr=0.3,0.1

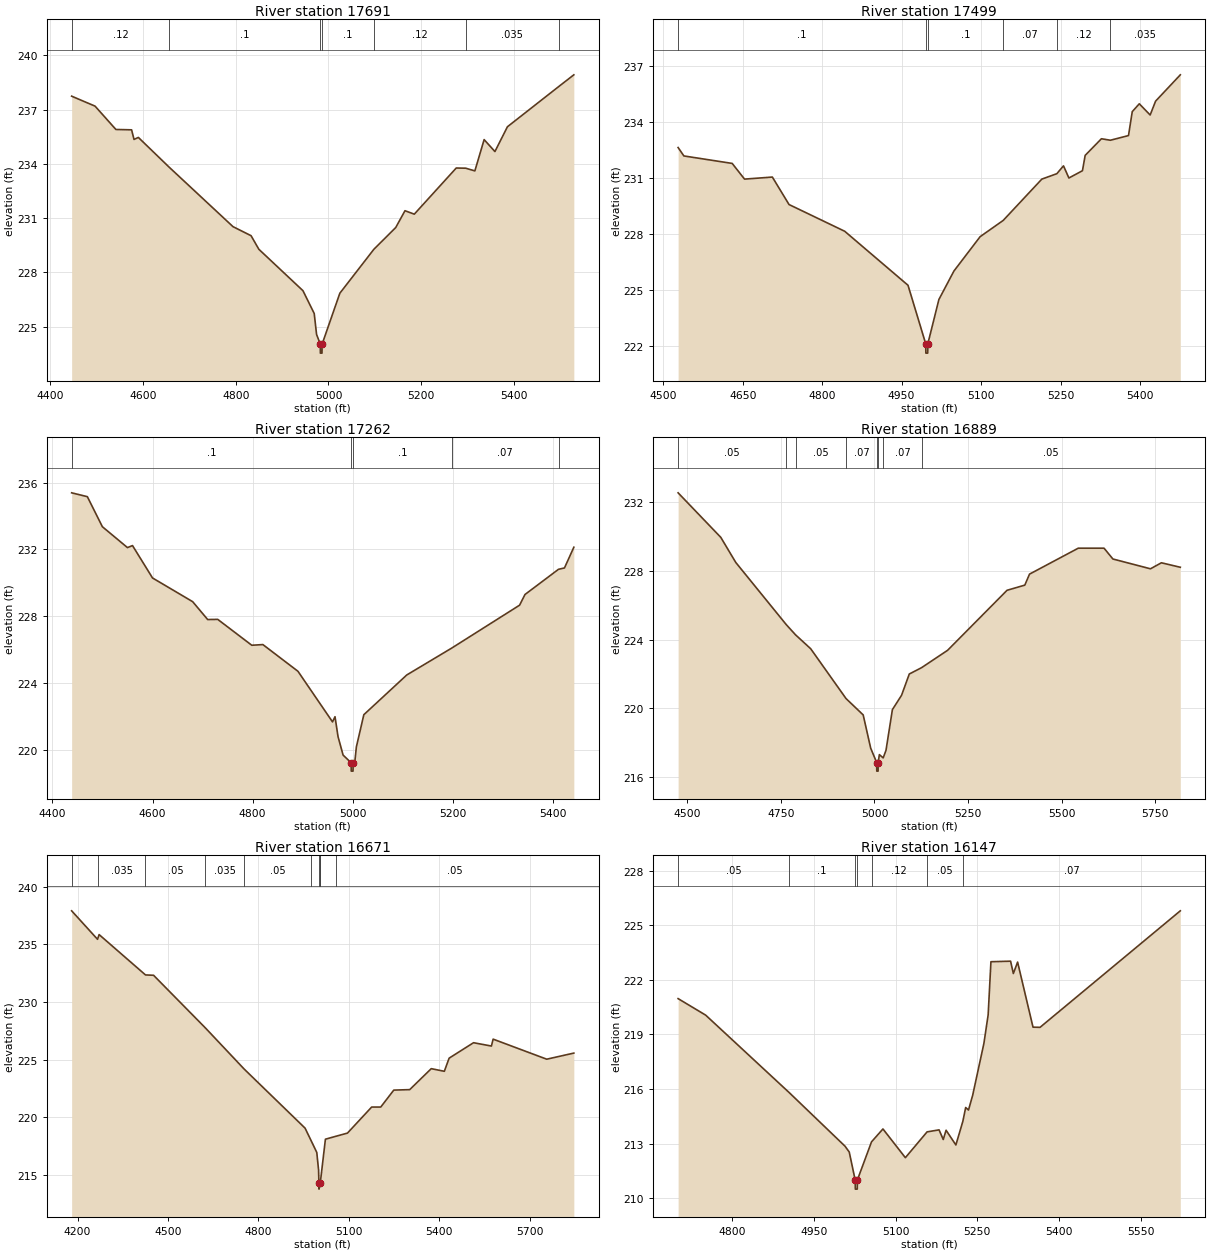
Type RM Length L Ch R = 1 ,17691   ,192,192,192
BEGIN DESCRIPTION:
Mapping XS 73347ad8
END DESCRIPTION:
XS GIS Cut Line= 3
      2492986.45     13485784.35      2493489.95     13485927.59
      2494047.64     13485873.34
#Sta/Elev= 30
  4445.7  237.74  4496.2  237.19  4541.2   235.9  4575.1  235.88  4580.3  235.35
  4589.7  235.46  4656.4  233.81  4793.9  230.53  4832.9  230.03  4849.7  229.28
  4944.9  226.99  4969.2  225.73  4974.3  224.57  4982.3  224.04  4982.5  223.54
    4986  223.54  4986.3  224.04  5024.5  226.85    5098  229.28  5145.1  230.48
  5165.1  231.41  5185.2  231.22  5275.7  233.77  5296.1  233.76  5315.9  233.61
  5335.9  235.34  5359.2  234.68  5386.2  236.05  5497.8  238.29  5529.5  238.92
#Mann= 7 ,-1 , 0
  4445.7     .12       0  4656.4      .1       0  4982.3     .05       0
  4986.3      .1       0    5098     .12       0  5296.1    .035       0
  5497.8     .05       0
Bank Sta=4982.3,4986.3
XS Rating Curve= 0 ,0
Exp/Cntr=0.3,0.1

Type RM Length L Ch R = 1 ,17499   ,237,237,237
BEGIN DESCRIPTION:
Mapping XS 9c91d4ec
END DESCRIPTION:
XS GIS Cut Line= 3
      2493025.54     13485957.97      2493472.59      13486101.2
      2493940.66     13486001.52
#Sta/Elev= 30
  4528.1  232.64    4539  232.19  4630.2  231.79  4653.5  230.95    4706  231.06
  4737.5  229.59  4842.6  228.16  4962.1  225.27  4995.5  222.14  4995.8  221.64
  4999.3  221.64  4999.5  222.14  5020.4  224.51  5048.7  226.03  5098.2  227.87
  5141.8  228.74  5214.7  230.95    5243  231.24  5255.6  231.66  5265.8  231.01
  5291.4   231.4  5296.5  232.22  5327.2  233.11  5344.1  233.03  5378.3  233.28
  5385.4  234.56  5398.7  234.98  5419.2  234.38  5429.4  235.12  5476.1  236.53
#Mann= 6 ,-1 , 0
  4528.1      .1       0  4995.5     .05       0  4999.5      .1       0
  5141.8     .07       0    5243     .12       0  5344.1    .035       0
Bank Sta=4995.5,4999.5
XS Rating Curve= 0 ,0
Exp/Cntr=0.3,0.1

Type RM Length L Ch R = 1 ,17262   ,373,373,373
BEGIN DESCRIPTION:
Mapping XS 50c15284
END DESCRIPTION:
XS GIS Cut Line= 3
      2492863.67     13486287.65       2493426.2     13486322.38
      2493835.96     13486162.64
#Sta/Elev= 30
  4438.4  235.39  4469.8  235.16  4499.8  233.36  4549.9  232.11    4560  232.23
    4600  230.29  4680.2  228.87  4710.2   227.8  4730.3  227.81  4798.3  226.26
  4820.5   226.3  4890.6   224.7  4959.6  221.67  4964.6  221.98  4970.7  220.78
  4980.8  219.68  4996.9  219.22  4997.1  218.72  5000.6  218.72  5000.9  219.22
    5004  219.22  5007.3  220.17  5022.2   222.1    5108  224.48  5197.8  226.09
  5333.4  228.66  5344.2   229.3  5411.2  230.81  5423.1  230.89  5441.8  232.13
#Mann= 5 ,-1 , 0
  4438.4      .1       0  4996.9     .05       0  5000.9      .1       0
  5197.8     .07       0  5411.2     .05       0
Bank Sta=4996.9,5000.9
XS Rating Curve= 0 ,0
Exp/Cntr=0.3,0.1

Type RM Length L Ch R = 1 ,16889   ,218,218,218
BEGIN DESCRIPTION:
Mapping XS 7d8ace20
END DESCRIPTION:
XS GIS Cut Line= 4
      2493051.18     13486627.93      2493578.98     13486641.82
      2493759.54     13486593.21      2494335.92     13486350.16
#Sta/Elev= 30
  4475.9  232.54  4589.8  229.95  4629.8  228.49  4764.3  224.88  4789.3  224.28
  4829.8  223.47  4924.2  220.57  4969.9  219.62  4989.9  217.69  5005.9  216.85
  5006.2  216.35  5009.7  216.35  5009.9  216.85  5013.1  217.31  5023.3  217.12
  5030.8  217.56  5047.9  219.93  5072.3  220.76    5093     222  5125.9  222.37
  5195.3  223.38  5353.9  226.87  5401.3  227.17  5413.9  227.81  5544.1  229.32
  5612.8  229.32  5636.5  228.69  5736.8  228.12  5765.9  228.47  5816.4  228.21
#Mann= 8 ,-1 , 0
  4475.9     .05       0  4764.3     .07       0  4789.3     .05       0
  4924.2     .07       0  5005.9     .05       0  5009.9     .07       0
  5023.3     .07       0  5125.9     .05       0
Bank Sta=5005.9,5009.9
XS Rating Curve= 0 ,0
Exp/Cntr=0.3,0.1

Type RM Length L Ch R = 1 ,16671   ,524,524,524
BEGIN DESCRIPTION:
Mapping XS 2afcf76b
END DESCRIPTION:
XS GIS Cut Line= 3
      2492838.95     13487008.31       2493646.2     13486839.05
      2494379.74      13486426.7
#Sta/Elev= 30
  4180.4   237.9  4266.3  235.43  4271.5  235.84  4425.4  232.34  4452.2  232.31
  4623.9  227.75    4753  224.17  4954.9  219.05    4976  217.91  4993.8  216.94
  4999.7  215.42  5000.9  214.26  5001.1  213.76  5004.9  214.26  5005.2  214.26
  5022.4  218.09  5056.6  218.34  5095.6  218.62  5175.9  220.88    5206  220.88
  5249.3  222.35  5302.1  222.39  5373.6  224.21    5417  223.98  5432.9  225.12
  5513.9  226.46  5573.2  226.17  5578.9  226.77  5756.8  225.03  5846.7  225.56
#Mann= 10 ,-1 , 0
  4180.4     .05       0  4266.3    .035       0  4425.4     .05       0
  4623.9    .035       0    4753     .05       0    4976     .07       0
  5000.9     .05       0  5004.9     .07       0  5005.2     .07       0
  5056.6     .05       0
Bank Sta=5000.9,5004.9
XS Rating Curve= 0 ,0
Exp/Cntr=0.3,0.1

Type RM Length L Ch R = 1 ,16147   ,237,237,237
BEGIN DESCRIPTION:
TRIB 4 TO EIGHTEENMILE CREEK 31.0
END DESCRIPTION:
XS GIS Cut Line= 3
        2493625.       13487275.        2493925.       13487225.
        2494525.       13487075.
#Sta/Elev= 30
  4700.3  220.97    4751  220.06  4904.4   215.8    5007  212.85  5014.7  212.53
  5025.6  210.99  5025.9  210.49  5029.4  210.49  5029.6  210.99  5055.6  213.09
  5076.6   213.8  5117.8  212.22  5157.7  213.64  5179.7  213.75  5187.4  213.22
  5192.6  213.73  5210.6  212.92  5223.4  214.22  5228.6  214.98  5233.8  214.84
  5241.5  215.66  5262.1  218.51  5269.9  220.08    5275     223  5311.1  223.03
  5316.2  222.35    5324  222.98  5352.3   219.4  5365.2  219.39  5622.9   225.8
#Mann= 7 ,-1 , 0
  4700.3     .05       0  4904.4      .1       0  5025.6     .05       0
  5029.6      .1       0  5055.6     .12       0  5157.7     .05       0
  5223.4     .07       0
Bank Sta=5025.6,5029.6
XS Rating Curve= 0 ,0
Exp/Cntr=0.3,0.1

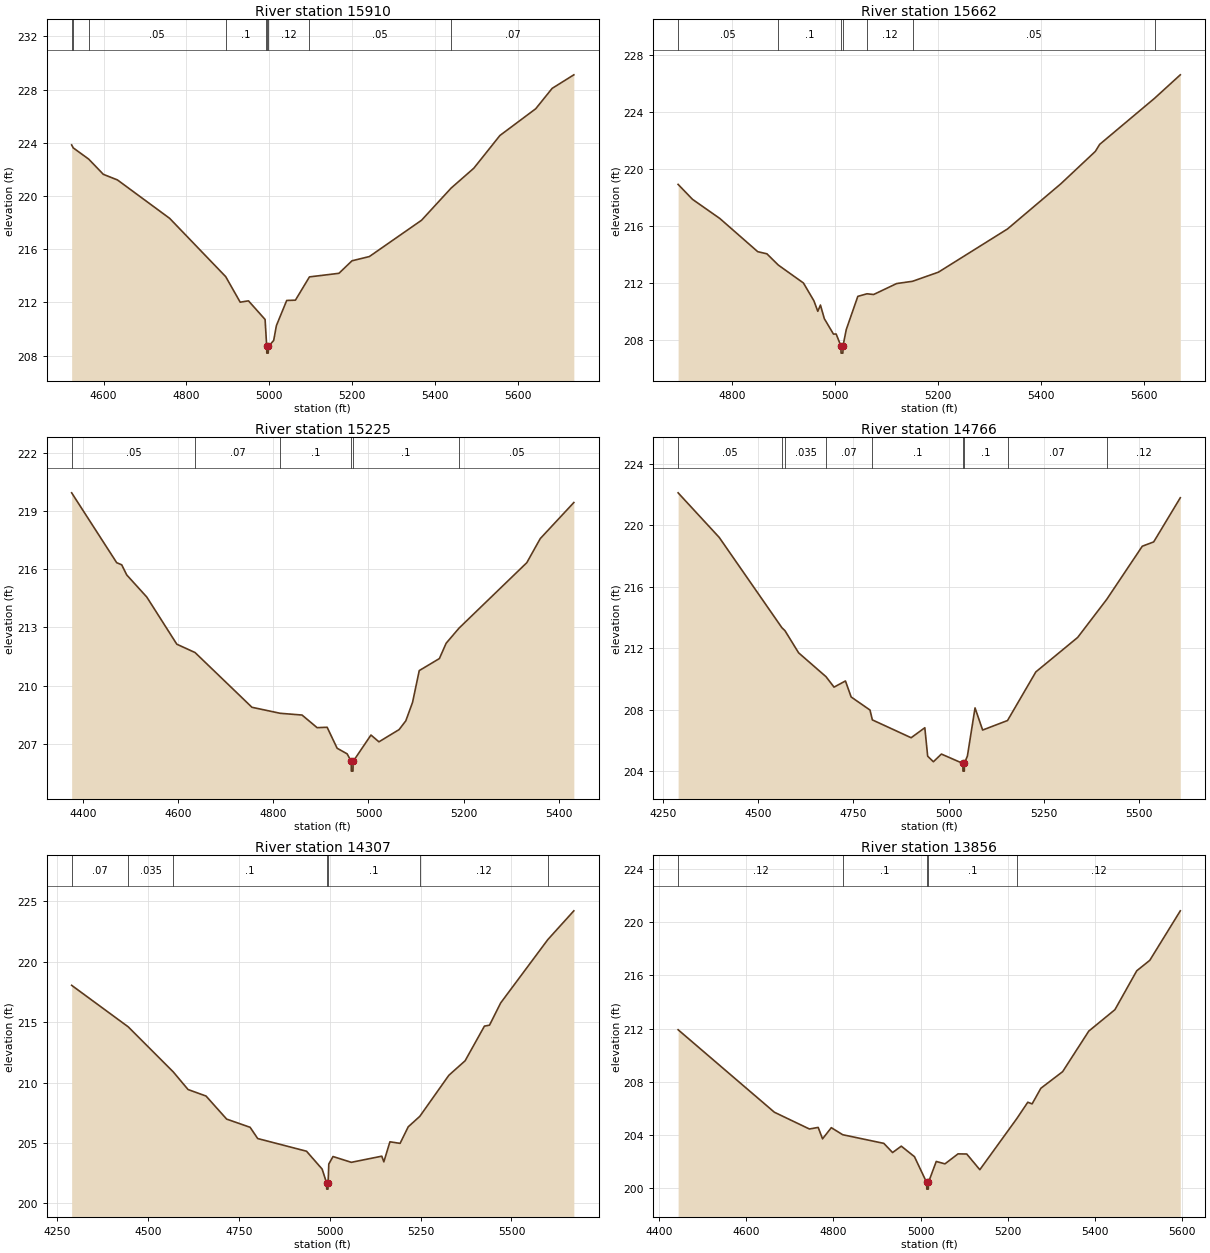
Type RM Length L Ch R = 1 ,15910   ,248,248,248
BEGIN DESCRIPTION:
Mapping XS 0b8a91b4
END DESCRIPTION:
XS GIS Cut Line= 3
      2493498.61     13487424.98      2493971.72     13487446.69
      2494674.87     13487220.98
#Sta/Elev= 30
  4522.9  223.84  4526.7  223.62  4564.2  222.77  4599.4  221.63  4633.4  221.21
  4759.5  218.32  4894.7  213.94  4929.7  212.02  4949.7  212.12  4989.8  210.72
  4992.8  209.16  4993.7  208.69  4993.9  208.19  4997.4  208.19  4997.7  208.69
  5010.5  209.14  5017.1  210.26    5042  212.15    5063  212.17  5096.8  213.92
    5168  214.19  5199.5  215.13  5241.5  215.45  5367.5  218.18  5438.6  220.59
  5493.6  222.09  5556.6  224.55    5643  226.56  5682.6  228.09    5735  229.11
#Mann= 9 ,-1 , 0
  4522.9     .05       0  4526.7    .035       0  4564.2     .05       0
  4894.7      .1       0  4992.8     .12       0  4993.7     .05       0
  4997.7     .12       0  5096.8     .05       0  5438.6     .07       0
Bank Sta=4993.7,4997.7
XS Rating Curve= 0 ,0
Exp/Cntr=0.3,0.1

Type RM Length L Ch R = 1 ,15662   ,437,437,437
BEGIN DESCRIPTION:
TRIB 4 TO EIGHTEENMILE CREEK 30.0
END DESCRIPTION:
XS GIS Cut Line= 3
      2493724.99       13487625.        2494025.       13487675.
      2494625.02     13487374.99
#Sta/Elev= 30
  4695.9  218.93  4723.8  217.88    4777  216.53  4850.5   214.2  4868.3  214.05
  4890.4  213.26  4939.2     212  4959.5  210.75  4967.1  210.01  4972.2  210.45
  4979.8  209.49  4997.5  208.41  5002.8  208.41    5012  207.57  5012.3  207.07
  5015.8  207.07    5016  207.57  5022.4  208.73  5044.8  211.06  5062.6  211.24
  5075.5  211.19  5120.2  211.96  5151.1  212.12  5201.3  212.76  5335.5   215.8
  5438.9  218.97    5506  221.25  5514.3  221.74  5620.9  224.98  5670.9  226.63
#Mann= 7 ,-1 , 0
  4695.9     .05       0  4890.4      .1       0    5012     .05       0
    5016      .1       0  5062.6     .12       0  5151.1     .05       0
  5620.9     .07       0
Bank Sta=5012,5016
XS Rating Curve= 0 ,0
Exp/Cntr=0.3,0.1

Type RM Length L Ch R = 1 ,15225   ,459,459,459
BEGIN DESCRIPTION:
TRIB 4 TO EIGHTEENMILE CREEK 29.0
END DESCRIPTION:
XS GIS Cut Line= 3
      2493675.03     13487825.01        2494275.       13488025.
      2494575.01     13487724.99
#Sta/Elev= 30
  4375.4  219.93  4470.2  216.33  4480.8  216.22  4491.3   215.7  4533.5  214.56
  4596.7  212.13  4635.1   211.7  4754.8  208.88  4814.2  208.57  4860.2  208.48
  4891.9  207.83    4913  207.85    4934  206.77  4955.1  206.48  4963.7  206.09
  4963.9  205.59  4967.4  205.59  4967.7  206.09  5005.2  207.45    5022   207.1
  5064.4  207.73  5078.5  208.18  5092.7  209.13  5106.8  210.77  5149.2  211.39
  5163.4  212.18  5190.6  212.96  5333.1  216.33  5361.4  217.57  5432.1  219.43
#Mann= 6 ,-1 , 0
  4375.4     .05       0  4635.1     .07       0  4814.2      .1       0
  4963.7     .05       0  4967.7      .1       0  5190.6     .05       0
Bank Sta=4963.7,4967.7
XS Rating Curve= 0 ,0
Exp/Cntr=0.3,0.1

Type RM Length L Ch R = 1 ,14766   ,459,459,459
BEGIN DESCRIPTION:
TRIB 4 TO EIGHTEENMILE CREEK 28.0
END DESCRIPTION:
XS GIS Cut Line= 3
      2493524.98     13487974.99        2494125.       13488375.
      2494724.97       13488375.
#Sta/Elev= 30
  4288.7   222.1  4396.9   219.2  4561.8  213.33  4569.8  213.14  4605.7   211.7
  4677.7  210.15  4698.9  209.47  4728.9  209.87  4743.9  208.83  4793.5  207.98
  4799.7  207.34  4901.7  206.18  4937.7  206.83  4945.2  204.98  4960.3  204.62
  4981.3  205.12  5037.8  204.51  5038.1  204.01  5041.6  204.01  5041.8  204.51
  5049.8     205  5069.8  208.12  5089.8  206.68  5155.3   207.3  5229.8  210.46
  5339.8   212.7  5416.4  215.18  5509.8  218.63  5539.8  218.91  5609.8  221.78
#Mann= 9 ,-1 , 0
  4288.7     .05       0  4561.8     .07       0  4569.8    .035       0
  4677.7     .07       0  4799.7      .1       0  5037.8     .05       0
  5041.8      .1       0  5155.3     .07       0  5416.4     .12       0
Bank Sta=5037.8,5041.8
XS Rating Curve= 0 ,0
Exp/Cntr=0.3,0.1

Type RM Length L Ch R = 1 ,14307   ,451,451,451
BEGIN DESCRIPTION:
TRIB 4 TO EIGHTEENMILE CREEK 27.0
END DESCRIPTION:
XS GIS Cut Line= 3
      2493524.98     13488324.98        2494075.       13488775.
      2494675.02     13489075.01
#Sta/Elev= 30
    4290  218.05  4445.7  214.61  4569.8  210.87  4610.2  209.42  4659.7  208.88
  4716.4  206.97    4781  206.29  4801.8  205.36  4936.1  204.31  4979.1  202.83
  4991.5  201.67  4991.7  201.17  4995.2  201.17  4995.5  201.67  4997.4  203.25
    5009  203.87  5059.4  203.39  5143.2   203.9  5148.8  203.43  5165.6  205.09
  5193.5  204.96  5215.9  206.33  5247.8   207.2  5327.7   210.6  5372.4   211.8
  5425.5  214.67  5439.5  214.75  5470.2  216.59    5600  221.84  5671.5  224.22
#Mann= 7 ,-1 , 0
    4290     .07       0  4445.7    .035       0  4569.8      .1       0
  4991.5     .05       0  4995.5      .1       0  5247.8     .12       0
    5600     .05       0
Bank Sta=4991.5,4995.5
XS Rating Curve= 0 ,0
Exp/Cntr=0.3,0.1

Type RM Length L Ch R = 1 ,13856   ,443,443,443
BEGIN DESCRIPTION:
TRIB 4 TO EIGHTEENMILE CREEK 26.0
END DESCRIPTION:
XS GIS Cut Line= 3
      2493424.97       13489075.        2493975.       13489125.
        2494575.       13489125.
#Sta/Elev= 30
  4443.5  211.91  4664.4  205.71  4744.8  204.45  4764.9  204.57  4774.9  203.71
    4795  204.55  4821.1  204.02  4915.5  203.37  4935.6  202.68  4955.6  203.16
  4985.8  202.37  5013.8  200.43  5014.1  199.93  5017.6  199.93  5017.8  200.43
  5035.8  202.01  5055.8  201.83  5085.8  202.58  5105.8  202.57  5135.8  201.39
  5220.8  205.24  5245.8  206.46  5255.8  206.34  5275.8  207.51  5325.8  208.76
  5385.8  211.81  5445.8  213.42  5495.8  216.34  5525.8  217.13  5595.8  220.85
#Mann= 5 ,-1 , 0
  4443.5     .12       0  4821.1      .1       0  5013.8     .05       0
  5017.8      .1       0  5220.8     .12       0
Bank Sta=5013.8,5017.8
XS Rating Curve= 0 ,0
Exp/Cntr=0.3,0.1

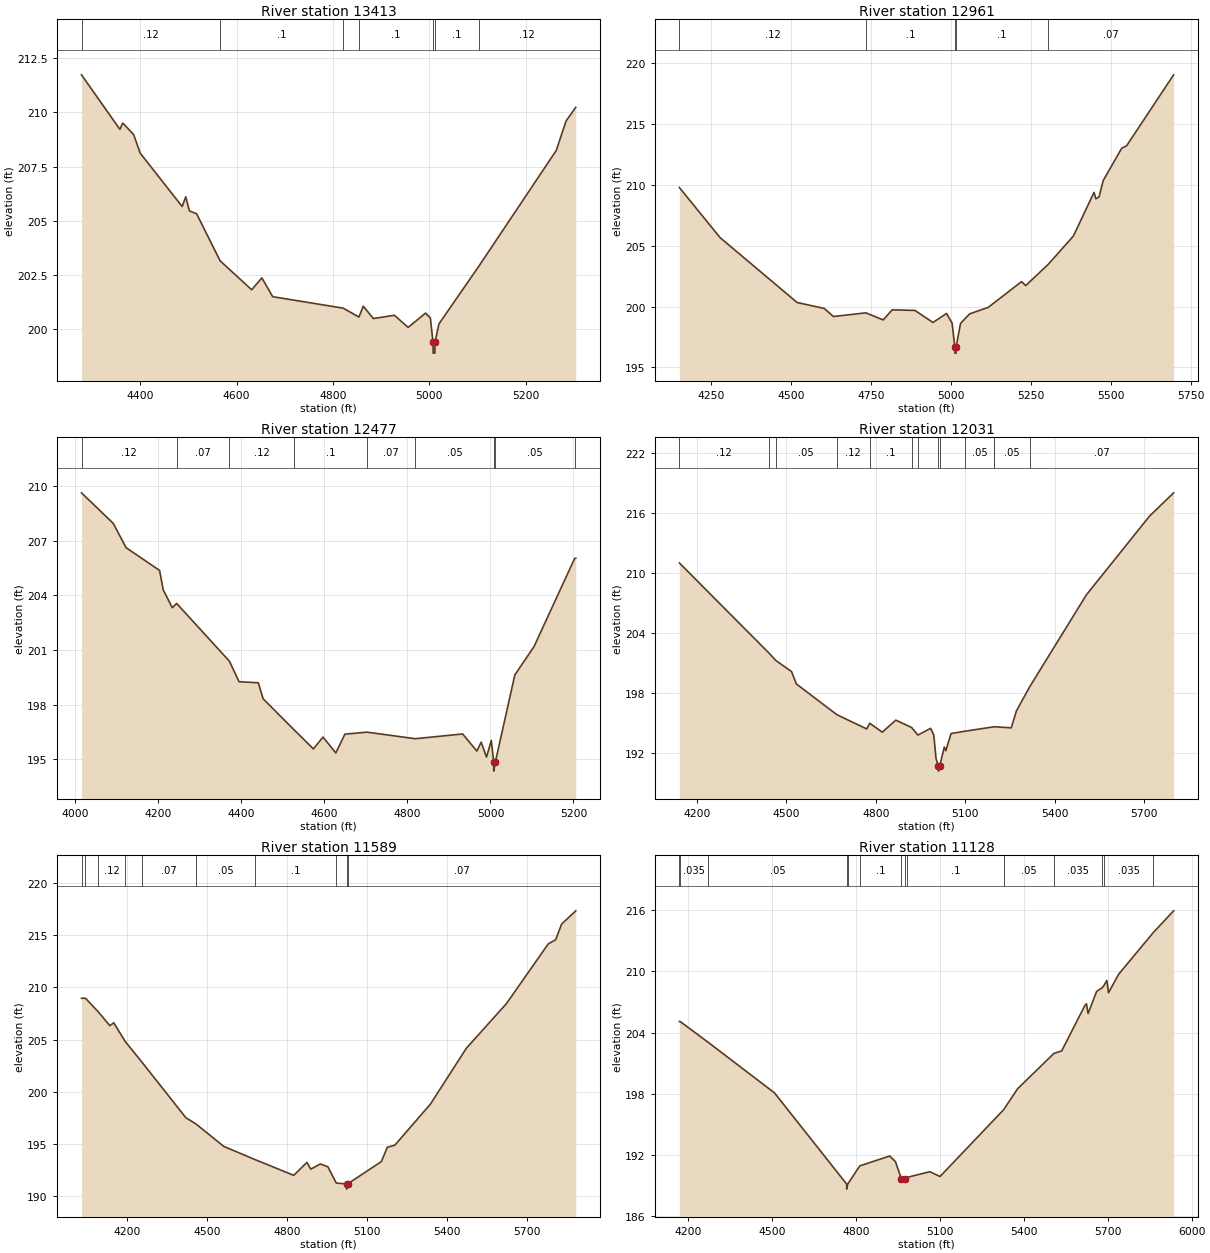
Type RM Length L Ch R = 1 ,13413   ,452,452,452
BEGIN DESCRIPTION:
TRIB 4 TO EIGHTEENMILE CREEK 25.0
END DESCRIPTION:
XS GIS Cut Line= 3
      2493425.01     13489125.01        2494025.       13489525.
      2494324.97     13489475.01
#Sta/Elev= 30
  4278.5  211.74  4358.1  209.22  4364.1  209.51  4386.6  208.98  4400.2  208.12
  4487.3  205.65  4494.8   206.1  4502.3  205.45  4517.4  205.31    4566  203.14
  4631.5   201.8  4652.6  202.35  4675.1  201.48  4821.3  200.95    4854  200.54
  4862.9  201.04  4883.9  200.47  4927.5  200.62    4956  200.06  4992.1  200.72
  5002.1   200.5  5007.7  199.37    5008  198.87  5011.5  198.87  5011.7  199.37
  5019.9  200.22  5102.1  202.87  5263.2  208.24  5283.5   209.6  5303.7  210.24
#Mann= 7 ,-1 , 0
  4278.5     .12       0    4566      .1       0  4821.3     .12       0
    4854      .1       0  5007.7     .05       0  5011.7      .1       0
  5102.1     .12       0
Bank Sta=5007.7,5011.7
XS Rating Curve= 0 ,0
Exp/Cntr=0.3,0.1

Type RM Length L Ch R = 1 ,12961   ,484,484,484
BEGIN DESCRIPTION:
TRIB 4 TO EIGHTEENMILE CREEK 24.0
END DESCRIPTION:
XS GIS Cut Line= 3
      2493375.03     13489325.03        2493975.       13489925.
      2494574.99     13490274.99
#Sta/Elev= 30
  4151.5  209.79  4278.7  205.67  4519.2  200.34    4604  199.85  4632.3  199.19
  4733.8  199.49  4787.9  198.91  4816.1  199.74  4886.9  199.69  4943.4   198.7
  4985.8  199.44  5002.9  198.65  5011.6  196.68  5011.9  196.18  5015.4  196.18
  5015.6  196.68  5029.3  198.62  5057.9  199.41  5115.8  199.94    5220  202.06
  5232.8  201.73  5303.3  203.48  5381.6   205.8  5446.1  209.39  5451.9  208.86
  5461.8  209.02  5474.7  210.36  5532.5  213.02  5547.8  213.22  5694.6  219.05
#Mann= 5 ,-1 , 0
  4151.5     .12       0  4733.8      .1       0  5011.6     .05       0
  5015.6      .1       0  5303.3     .07       0
Bank Sta=5011.6,5015.6
XS Rating Curve= 0 ,0
Exp/Cntr=0.3,0.1

Type RM Length L Ch R = 1 ,12477   ,446,446,446
BEGIN DESCRIPTION:
TRIB 4 TO EIGHTEENMILE CREEK 23.0
END DESCRIPTION:
XS GIS Cut Line= 3
        2493075.       13489975.        2493975.       13490375.
      2494174.97     13490424.99
#Sta/Elev= 30
  4014.6  209.63  4091.2  207.95    4122  206.62  4202.7  205.37  4211.6   204.3
  4233.5  203.32  4243.8  203.56  4371.2  200.38  4394.2  199.26  4440.7   199.2
  4452.3  198.32  4526.3  196.63  4573.4  195.57  4596.6  196.22  4627.4  195.35
  4649.3  196.38  4702.4  196.49    4819  196.13  4933.1  196.39  4967.3  195.45
  4977.6  195.94  4990.6  195.12  5002.1  196.04  5007.8  194.85    5008  194.35
  5011.8  194.85  5058.8  199.63  5105.1  201.19    5203  206.03  5205.6  206.04
#Mann= 9 ,-1 , 0
  4014.6     .12       0  4243.8     .07       0  4371.2     .12       0
  4526.3      .1       0  4702.4     .07       0    4819     .05       0
  5007.8     .05       0  5011.8     .05       0    5203     .07       0
Bank Sta=5007.8,5011.8
XS Rating Curve= 0 ,0
Exp/Cntr=0.3,0.1

Type RM Length L Ch R = 1 ,12031   ,442,442,442
BEGIN DESCRIPTION:
TRIB 4 TO EIGHTEENMILE CREEK 22.0
END DESCRIPTION:
XS GIS Cut Line= 3
      2492924.99       13490225.        2493675.       13490625.
      2494474.96       13490525.
#Sta/Elev= 30
    4142     211  4441.1  202.04  4464.7  201.28  4517.8  200.16  4534.1  198.92
    4670  195.85  4769.9  194.43  4779.7     195    4822  194.11  4867.3  195.31
  4920.1  194.58  4941.4  193.82  4983.9  194.49  4994.5  193.83  5002.1  191.46
  5010.2  190.72  5010.4  190.22  5014.2  190.72  5029.8  192.62  5034.8  192.26
  5052.5  193.97    5098   194.2  5197.4  194.65  5197.7  194.65    5254  194.54
  5271.7  196.25  5315.7  198.63    5506  207.82  5717.6  215.68  5798.2     218
#Mann= 13 ,-1 , 0
    4142     .12       0  4441.1     .07       0  4464.7     .05       0
    4670     .12       0  4779.7      .1       0  4920.1     .12       0
  4941.4      .1       0  5010.2     .05       0  5014.2      .1       0
    5098     .05       0  5197.4      .1       0  5197.7     .05       0
  5315.7     .07       0
Bank Sta=5010.2,5014.2
XS Rating Curve= 0 ,0
Exp/Cntr=0.3,0.1

Type RM Length L Ch R = 1 ,11589   ,461,461,461
BEGIN DESCRIPTION:
TRIB 4 TO EIGHTEENMILE CREEK 21.0
END DESCRIPTION:
XS GIS Cut Line= 3
      2492924.99     13490374.99        2493675.       13490975.
      2494474.99       13490575.
#Sta/Elev= 30
  4029.7  208.96  4044.5  208.97  4091.1  207.71  4136.2  206.34  4150.6  206.62
  4193.7  204.83  4256.9  202.84  4421.1  197.54  4460.1  196.92  4563.6  194.79
  4679.9  193.54  4826.1  192.02  4875.7  193.26  4890.1  192.61  4926.1  193.11
  4954.2  192.84  4985.9  191.28  5024.5   191.2  5024.7   190.7  5028.6   191.2
  5155.1  193.34  5177.5  194.71  5205.4   194.9  5339.6  198.85  5473.7  204.17
  5624.7  208.46  5781.2  214.16  5809.1  214.56  5831.5  216.06  5884.6  217.33
#Mann= 10 ,-1 , 0
  4029.7     .12       0  4044.5     .07       0  4091.1     .12       0
  4193.7     .05       0  4256.9     .07       0  4460.1     .05       0
  4679.9      .1       0  4985.9     .07       0  5024.5     .05       0
  5028.6     .07       0
Bank Sta=5024.5,5028.6
XS Rating Curve= 0 ,0
Exp/Cntr=0.3,0.1

Type RM Length L Ch R = 1 ,11128   ,456,456,456
BEGIN DESCRIPTION:
TRIB 4 TO EIGHTEENMILE CREEK 20.0
END DESCRIPTION:
XS GIS Cut Line= 3
      2492975.03     13491175.01        2493775.       13491375.
      2494575.01     13490874.99
#Sta/Elev= 30
  4167.5  205.09  4170.3  205.09  4270.9  203.04  4507.6  198.09  4765.8  189.14
  4766.1  188.64  4769.9  189.14  4812.8  190.92  4919.9  191.89  4940.5  191.34
  4961.2  189.68    4974  189.63  4981.8  189.79  5063.4  190.35    5100  189.88
    5328  196.45  5377.1  198.48  5507.3  201.96  5535.1   202.2  5617.1  206.61
  5623.6  206.84  5629.5  205.87  5660.1  208.04  5680.4  208.41  5685.2  208.58
  5696.7  209.12  5702.6  207.91  5739.1  209.74  5863.2  213.83  5935.5  215.95
#Mann= 14 ,-1 , 0
  4167.5     .05       0  4170.3    .035       0  4270.9     .05       0
  4765.8     .07       0  4769.9     .05       0  4812.8      .1       0
  4961.2     .05       0    4974     .07       0  4981.8      .1       0
    5328     .05       0  5507.3    .035       0  5680.4     .05       0
  5685.2    .035       0  5863.2     .07       0
Bank Sta=4961.2,4974
XS Rating Curve= 0 ,0
Exp/Cntr=0.3,0.1

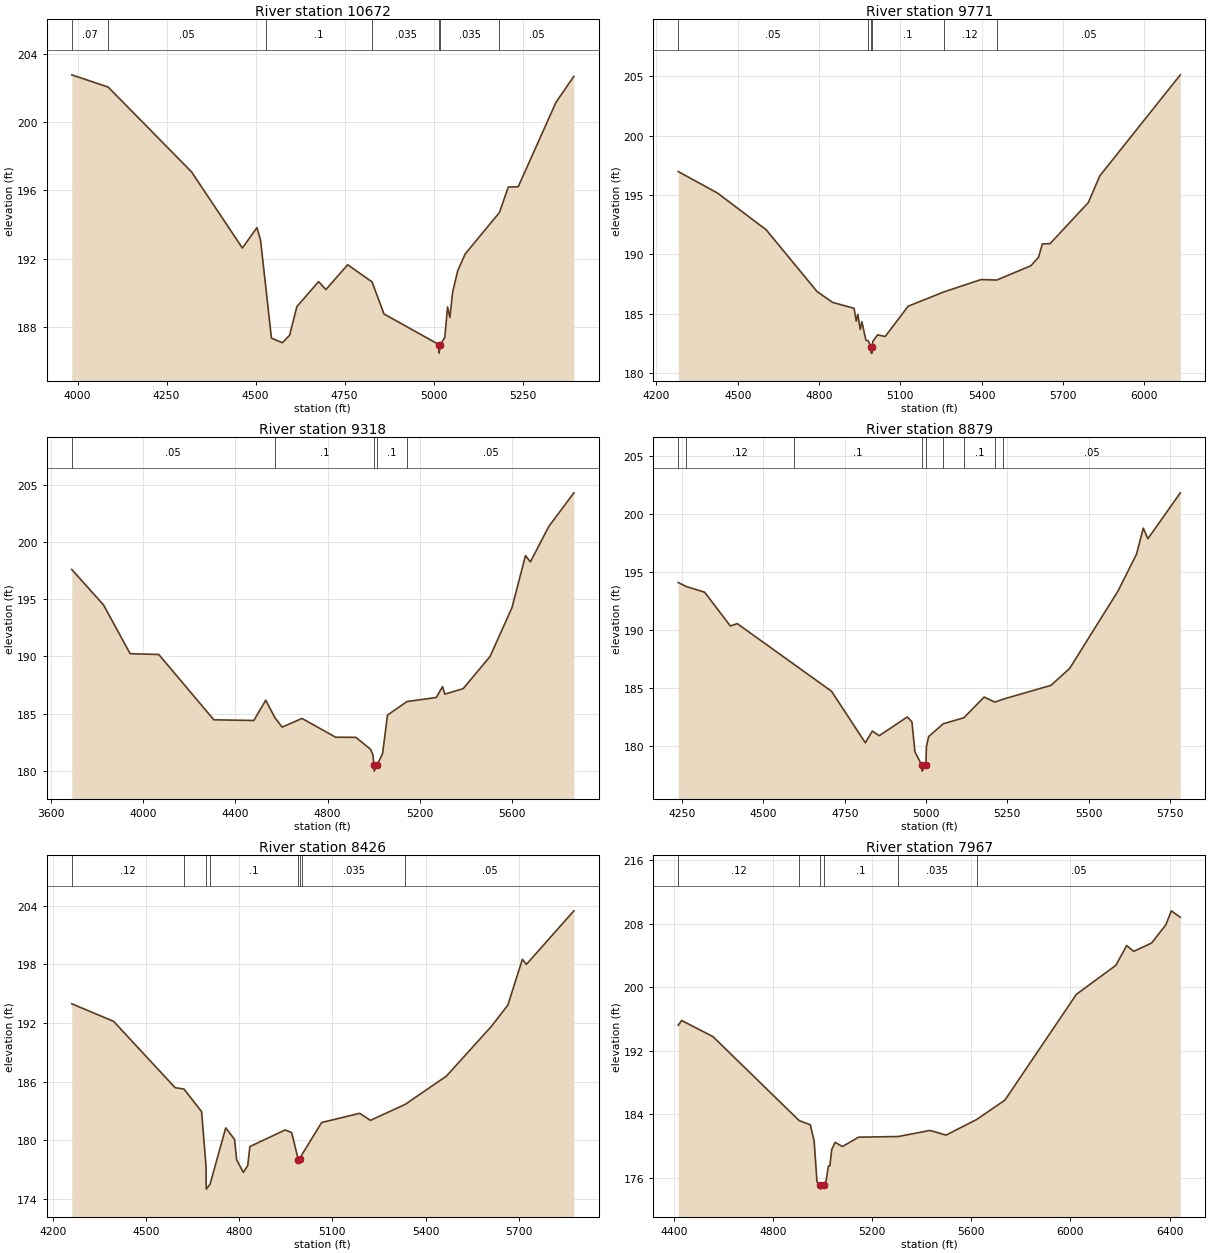
Type RM Length L Ch R = 1 ,10672   ,901,901,901
BEGIN DESCRIPTION:
TRIB 4 TO EIGHTEENMILE CREEK 19.0
END DESCRIPTION:
XS GIS Cut Line= 3
      2493025.02       13491375.        2494025.       13491575.
        2494325.       13491325.
#Sta/Elev= 30
  3983.9  202.79  4086.2  202.07  4320.4  197.09  4463.2  192.62    4504  193.82
  4514.2  193.08  4529.1  190.29  4544.8  187.33  4575.4  187.06  4595.8   187.5
  4616.2  189.18  4677.3  190.65  4697.7  190.18  4758.9  191.64  4827.4  190.63
  4860.9  188.75  5015.3  186.95  5015.6  186.45  5019.4  186.95  5031.7  187.37
  5039.5  189.16    5046  188.55  5053.8  190.04  5068.1  191.29  5088.9  192.27
  5185.3  194.71    5210   196.2    5238  196.22  5344.1  201.18  5394.2   202.7
#Mann= 7 ,-1 , 0
  3983.9     .07       0  4086.2     .05       0  4529.1      .1       0
  4827.4    .035       0  5015.3    .035       0  5019.4    .035       0
  5185.3     .05       0
Bank Sta=5015.3,5019.4
XS Rating Curve= 0 ,0
Exp/Cntr=0.3,0.1

Type RM Length L Ch R = 1 ,9771    ,453,453,453
BEGIN DESCRIPTION:
TRIB 4 TO EIGHTEENMILE CREEK 18.0
END DESCRIPTION:
XS GIS Cut Line= 3
      2493174.97     13491824.98        2493775.       13492225.
      2494574.99     13491425.01
#Sta/Elev= 30
  4280.3  196.98  4424.6  195.18  4604.8  192.08  4792.6  186.88  4849.7  185.97
  4929.3  185.47  4936.9  184.39  4942.9  184.96  4951.9   183.7  4957.9  184.34
  4972.9  182.78  4981.6  182.73  4991.8   182.2  4992.1   181.7  4995.8   181.7
    4996   182.2  4998.4  182.69  5015.6  183.24  5043.9   183.1  5128.7  185.65
  5260.3  186.85  5397.4  187.89  5455.5  187.85  5581.3  189.05  5609.6  189.76
  5623.7  190.89    5652  190.91  5793.4  194.37  5835.8  196.62  6132.8  205.12
#Mann= 6 ,-1 , 0
  4280.3     .05       0  4981.6      .1       0  4991.8     .05       0
    4996      .1       0  5260.3     .12       0  5455.5     .05       0
Bank Sta=4991.8,4996
XS Rating Curve= 0 ,0
Exp/Cntr=0.3,0.1

Type RM Length L Ch R = 1 ,9318    ,439,439,439
BEGIN DESCRIPTION:
TRIB 4 TO EIGHTEENMILE CREEK 17.0
END DESCRIPTION:
XS GIS Cut Line= 3
      2493024.98     13493175.01        2494125.       13492475.
        2494875.       13492025.
#Sta/Elev= 30
  3690.1  197.59  3828.1  194.49  3943.3  190.24  4067.7  190.17  4306.5  184.47
    4480  184.41  4531.7  186.18  4570.9  184.68  4602.8  183.83  4689.2  184.59
  4834.8  182.95  4922.8  182.94  4986.3   181.9  4996.9  181.41  5001.4  180.49
  5001.9  179.99  5013.8  180.49  5038.7  181.52    5060  184.88  5144.4  186.06
  5271.9  186.42  5299.1  187.37  5308.8  186.71  5388.5  187.19  5505.1     190
  5600.4  194.27  5658.7   198.8  5680.1  198.25  5759.8  201.34  5868.6  204.28
#Mann= 5 ,-1 , 0
  3690.1     .05       0  4570.9      .1       0  5001.4     .05       0
  5013.8      .1       0  5144.4     .05       0
Bank Sta=5001.4,5013.8
XS Rating Curve= 0 ,0
Exp/Cntr=0.3,0.1

Type RM Length L Ch R = 1 ,8879    ,453,453,453
BEGIN DESCRIPTION:
TRIB 4 TO EIGHTEENMILE CREEK 16.0
END DESCRIPTION:
XS GIS Cut Line= 3
      2493975.02     13493424.96        2494375.       13492775.
        2494875.       13492175.
#Sta/Elev= 30
  4237.8   194.1  4262.8  193.75  4318.8  193.27  4398.1  190.35  4419.4  190.55
  4593.7  187.04  4709.3  184.71  4813.1  180.26  4834.8  181.27    4856  180.87
  4942.3  182.49  4956.6  182.06  4965.7  179.49    4987  178.31  4987.5  177.81
  4999.5  178.31    5001   179.9  5008.1   180.8  5052.9   181.9  5116.4  182.42
  5178.7  184.21  5211.8  183.77  5237.7  184.03  5384.3  185.22  5441.6  186.68
    5590  193.35  5647.3  196.55  5668.1   198.8  5682.4  197.89    5782  201.85
#Mann= 9 ,-1 , 0
  4237.8     .05       0  4262.8     .12       0  4593.7      .1       0
    4987     .05       0  4999.5      .1       0  5052.9    .035       0
  5116.4      .1       0  5211.8    .035       0  5237.7     .05       0
Bank Sta=4987,4999.5
XS Rating Curve= 0 ,0
Exp/Cntr=0.3,0.1

Type RM Length L Ch R = 1 ,8426    ,459,459,459
BEGIN DESCRIPTION:
TRIB 4 TO EIGHTEENMILE CREEK 15.0
END DESCRIPTION:
XS GIS Cut Line= 3
      2494074.98     13493475.02        2494625.       13492975.
      2494974.98     13492175.04
#Sta/Elev= 30
  4261.1  193.96  4395.9  192.16  4593.9  185.38  4622.5  185.24  4679.1  182.93
  4693.3  177.37  4693.8  175.51  4694.3  175.01  4706.3  175.51  4756.8  181.27
  4785.2  180.09  4791.9  178.01  4813.5  176.72  4827.7  177.43  4834.5  179.36
    4948  181.06    4969  180.79  4990.6  178.01  4997.3  178.08  5001.9  178.52
  5065.6  181.82    5188  182.76  5222.7  182.04  5334.9  183.68  5467.2  186.56
    5613  191.68  5665.2  193.83    5712  198.51  5724.8  197.98  5877.6  203.46
#Mann= 8 ,-1 , 0
  4261.1     .12       0  4622.5      .1       0  4693.8     .07       0
  4706.3      .1       0  4990.6     .05       0  4997.3     .07       0
  5001.9    .035       0  5334.9     .05       0
Bank Sta=4990.6,4997.3
XS Rating Curve= 0 ,0
Exp/Cntr=0.3,0.1

Type RM Length L Ch R = 1 ,7967    ,465,465,465
BEGIN DESCRIPTION:
TRIB 4 TO EIGHTEENMILE CREEK 14.0
END DESCRIPTION:
XS GIS Cut Line= 3
      2494074.96     13493575.02        2494575.       13493275.
      2495375.02     13492074.96
#Sta/Elev= 30
    4418   195.2  4431.6  195.81    4558  193.78  4906.1   183.2  4950.6  182.69
  4966.2  180.65  4977.8  175.49  4991.8  175.08  4992.3  174.58  5004.7  175.08
  5014.7  175.64  5023.7  177.49  5029.7  177.51  5037.2  179.55  5050.7  180.47
  5080.8  179.94  5145.4  181.12  5305.5   181.2  5433.8  181.97  5498.4  181.38
  5621.6  183.34  5735.8  185.78  6024.2   199.1  6183.5  202.75    6227  205.24
  6255.6  204.51  6327.7  205.56  6384.8  207.84  6407.3  209.61  6443.4   208.8
#Mann= 6 ,-1 , 0
    4418     .12       0  4906.1      .1       0  4991.8     .05       0
  5004.7      .1       0  5305.5    .035       0  5621.6     .05       0
Bank Sta=4991.8,5004.7
XS Rating Curve= 0 ,0
Exp/Cntr=0.3,0.1