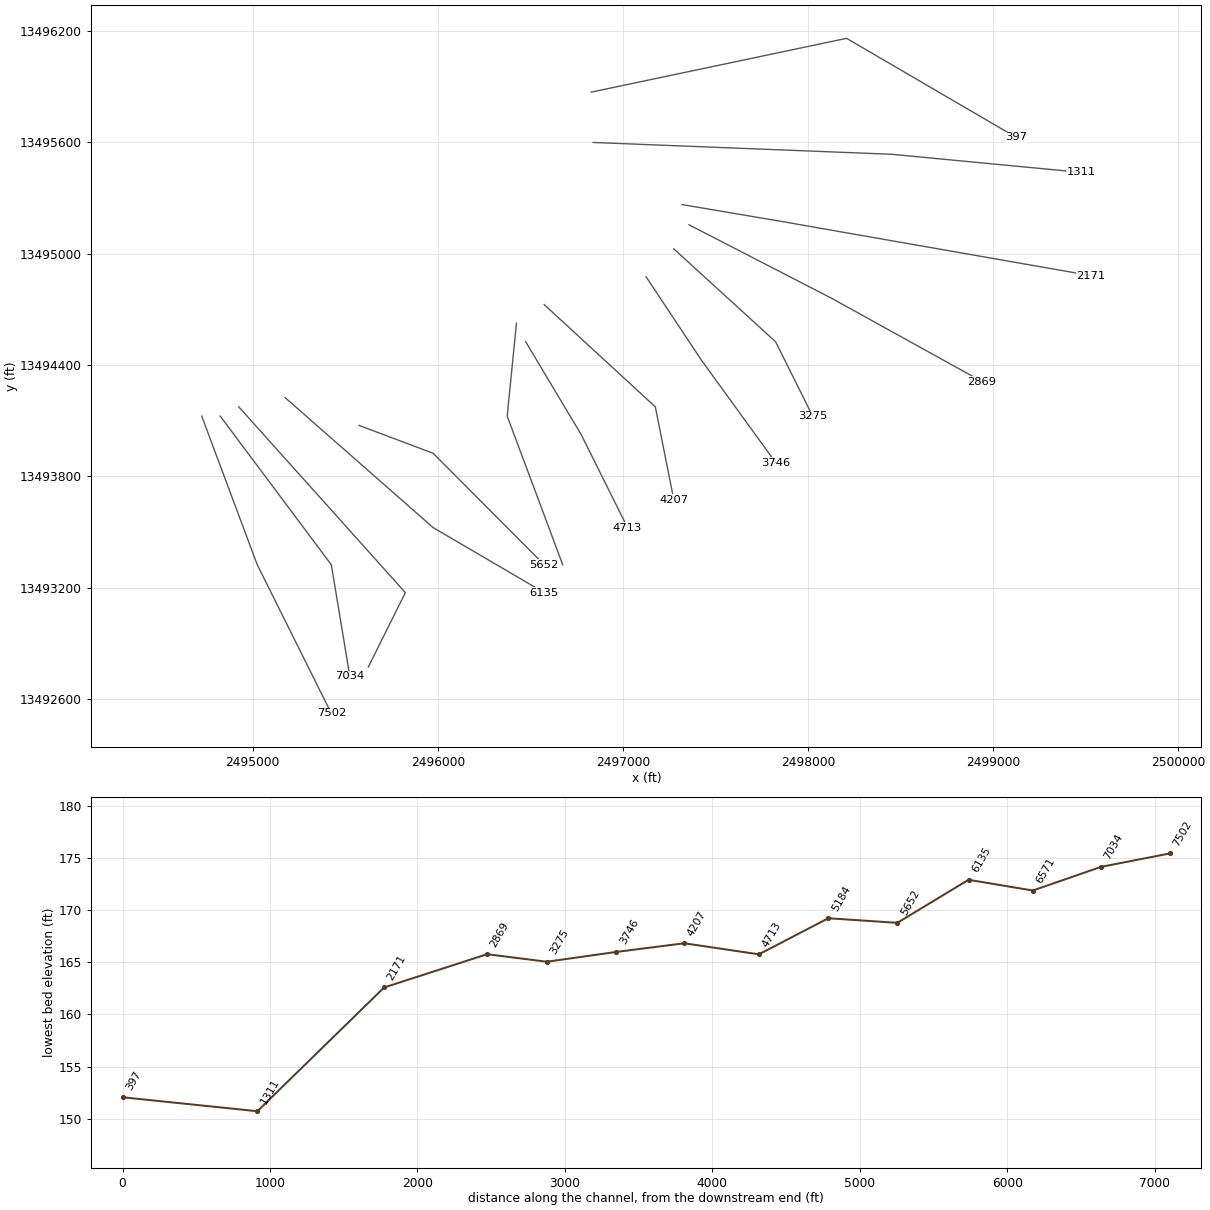
HEC-RAS study TRIB 4 TO EIGHTEENMILE CREEK.prj: TRIB 4 TO EIGHTEENMILE CREEK Base Level Engineering

--- TRIB 4 TO EIGHTEENMILE CREEK.g01 (geometry) --- (continued)

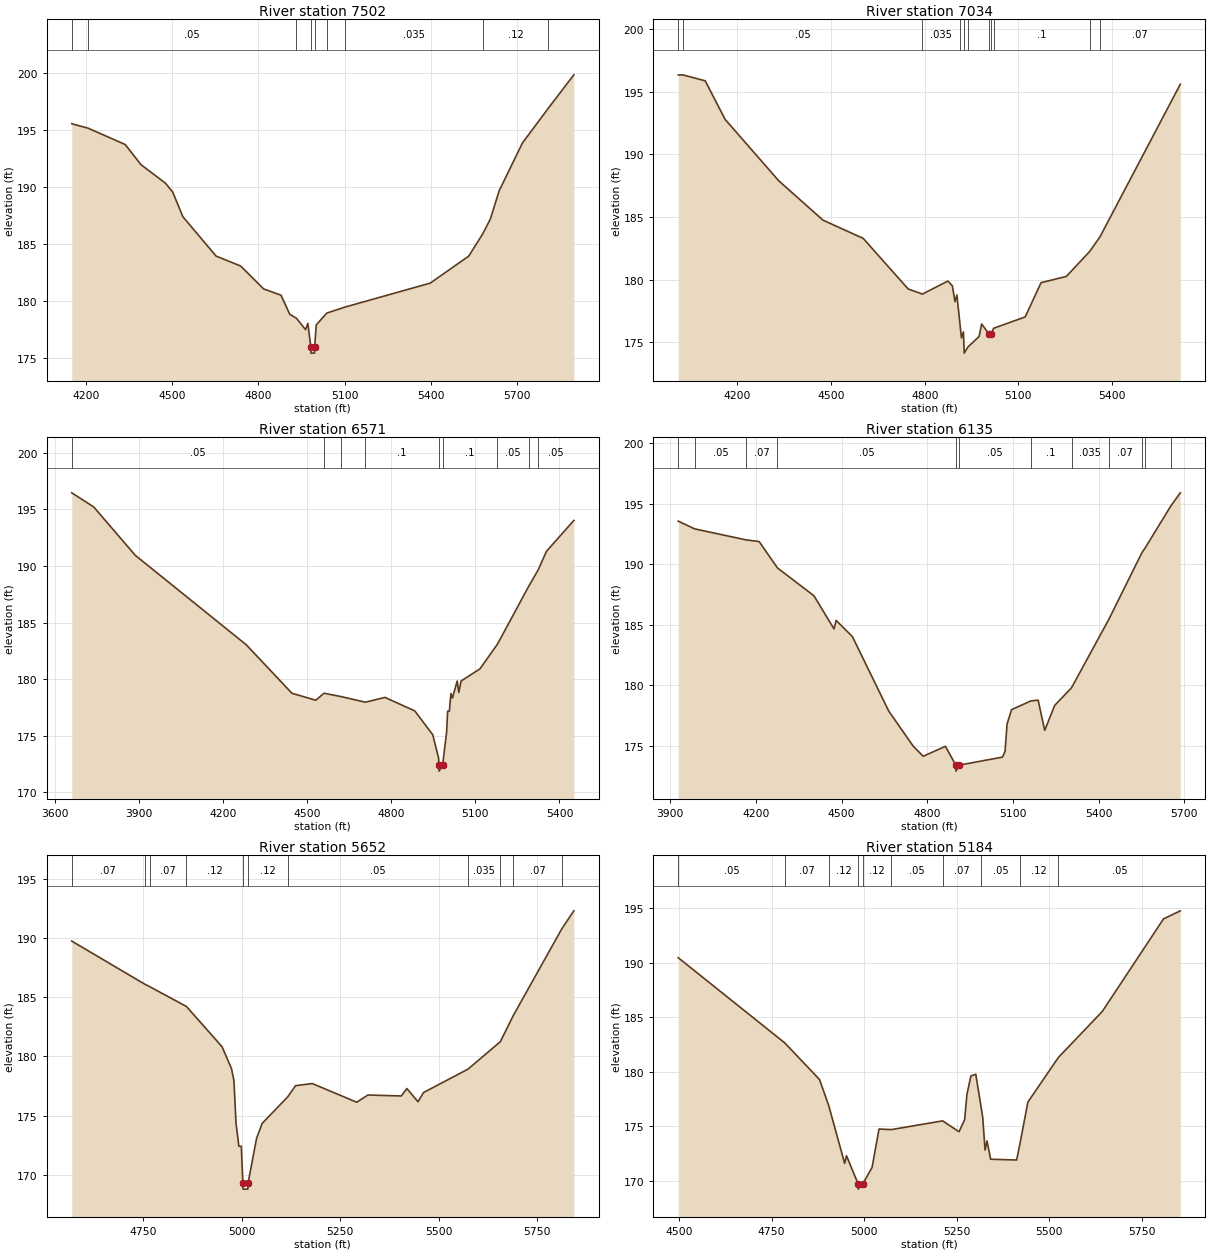
Type RM Length L Ch R = 1 ,7502    ,468,468,468
BEGIN DESCRIPTION:
TRIB 4 TO EIGHTEENMILE CREEK 13.0
END DESCRIPTION:
XS GIS Cut Line= 3
        2494725.     13494124.99        2495025.       13493325.
      2495424.99     13492525.02
#Sta/Elev= 30
  4149.9  195.56  4206.7  195.17  4335.9  193.74  4391.1  191.97  4476.5  190.34
  4501.4  189.57    4537   187.4  4652.7  183.95  4738.2  183.08  4818.3  181.07
  4878.8  180.52  4909.1  178.85  4932.5   178.5  4964.2   177.5  4972.3  178.05
  4982.7  175.94  4983.2  175.44  4995.1  175.44  4995.6  175.94  5001.6  177.92
  5038.1  178.95  5101.8  179.48  5398.4  181.58  5532.6  183.95  5581.6  185.91
    5608  187.21  5638.8  189.69  5719.8  193.88  5810.4  196.94  5898.7  199.85
#Mann= 9 ,-1 , 0
  4149.9     .12       0  4206.7     .05       0  4932.5    .035       0
  4982.7    .035       0  4995.6    .035       0  5038.1      .1       0
  5101.8    .035       0  5581.6     .12       0  5810.4     .05       0
Bank Sta=4982.7,4995.6
XS Rating Curve= 0 ,0
Exp/Cntr=0.3,0.1

Type RM Length L Ch R = 1 ,7034    ,463,463,463
BEGIN DESCRIPTION:
TRIB 4 TO EIGHTEENMILE CREEK 12.0
END DESCRIPTION:
XS GIS Cut Line= 3
      2494824.99     13494125.01        2495425.       13493325.
        2495525.     13492724.99
#Sta/Elev= 30
  4010.4  196.34  4024.5  196.35  4096.9  195.87  4160.4   192.8  4332.3   187.9
    4474  184.76  4603.1   183.3  4746.9  179.27  4792.7  178.86    4874   179.9
  4888.5  179.52  4896.9  178.25  4903.1  178.79  4913.4  176.34  4917.7  175.36
    4924  175.84  4925.8  174.65  4926.3  174.15  4938.8  174.65    4974  175.47
  4982.3  176.47  5007.3  175.64  5012.9  175.64  5020.5  176.13  5121.9  177.04
  5172.6  179.77  5253.7  180.27  5328.4  182.26  5361.4  183.43  5618.7   195.6
#Mann= 11 ,-1 , 0
  4010.4    .035       0  4024.5     .05       0  4792.7    .035       0
  4913.4      .1       0  4925.8     .07       0  4938.8      .1       0
  5007.3     .05       0  5012.9     .07       0  5020.5      .1       0
  5328.4     .12       0  5361.4     .07       0
Bank Sta=5007.3,5012.9
XS Rating Curve= 0 ,0
Exp/Cntr=0.3,0.1

Type RM Length L Ch R = 1 ,6571    ,436,436,436
BEGIN DESCRIPTION:
TRIB 4 TO EIGHTEENMILE CREEK 11.0
END DESCRIPTION:
XS GIS Cut Line= 3
        2494925.       13494175.        2495825.       13493175.
      2495624.99     13492774.97
#Sta/Elev= 30
  3658.8  196.46  3736.9  195.22  3885.6  190.94  4281.8  183.04  4444.7  178.76
  4529.9  178.14  4559.2  178.76    4619  178.47  4706.9  177.97  4777.3  178.39
  4883.4   177.2  4947.7  175.09  4968.7  173.02  4969.6  172.38  4970.1  171.88
  4982.6  172.38  4997.1  175.32  5000.8  177.17    5007  177.17  5012.5  178.74
  5018.1  178.34  5034.9  179.84  5040.5  178.82  5048.9  179.84    5116  180.91
  5178.6  183.09  5290.4  188.21  5324.2  189.66  5353.5  191.29  5451.4  194.02
#Mann= 9 ,-1 , 0
  3658.8     .05       0  4559.2      .1       0    4619     .05       0
  4706.9      .1       0  4969.6     .05       0  4982.6      .1       0
  5178.6     .05       0  5290.4    .035       0  5324.2     .05       0
Bank Sta=4969.6,4982.6
XS Rating Curve= 0 ,0
Exp/Cntr=0.3,0.1

Type RM Length L Ch R = 1 ,6135    ,483,483,483
BEGIN DESCRIPTION:
TRIB 4 TO EIGHTEENMILE CREEK 10.0
END DESCRIPTION:
XS GIS Cut Line= 3
        2495175.       13494225.        2495975.       13493525.
      2496574.97     13493175.02
#Sta/Elev= 30
  3928.2  193.58  3985.6  192.94  4165.5  192.03  4211.5  191.89  4275.6  189.71
  4403.2  187.41  4473.5  184.67  4481.1  185.37    4538  184.03  4665.2  177.87
  4750.6  174.98  4785.7  174.14  4863.6  174.96  4899.8  173.41  4900.3  172.91
  4912.8  173.41  5063.6  174.07  5072.3  174.55  5079.3   176.8    5095  177.99
  5162.1  178.71    5188  178.78  5211.2  176.28  5245.9  178.34  5304.9   179.8
    5435  185.43  5550.7  190.94  5563.4  191.39  5652.8  194.84  5685.8  195.92
#Mann= 12 ,-1 , 0
  3928.2    .035       0  3985.6     .05       0  4165.5     .07       0
  4275.6     .05       0  4899.8     .05       0  4912.8     .05       0
  5162.1      .1       0  5304.9    .035       0    5435     .07       0
  5550.7    .035       0  5563.4     .07       0  5652.8     .05       0
Bank Sta=4899.8,4912.8
XS Rating Curve= 0 ,0
Exp/Cntr=0.3,0.1

Type RM Length L Ch R = 1 ,5652    ,468,468,468
BEGIN DESCRIPTION:
TRIB 4 TO EIGHTEENMILE CREEK 9.0
END DESCRIPTION:
XS GIS Cut Line= 3
      2495574.97     13494075.01        2495975.       13493925.
      2496575.02     13493324.98
#Sta/Elev= 30
    4568  189.76  4753.3  186.12  4766.3   185.9  4859.4  184.23  4949.8  180.83
  4973.9  178.97  4980.1  177.95  4985.4  174.36  4992.6  172.41  4998.8  172.41
  5002.8  169.28  5003.3  168.78  5015.4  168.78  5015.9  169.28  5037.7  173.09
  5051.8  174.34  5116.6  176.58  5136.7  177.53  5179.1  177.71  5292.2  176.13
  5320.5  176.74  5405.4  176.66  5419.5  177.29  5447.8  176.17  5461.9  176.95
  5574.9  178.93    5657  181.25  5689.9  183.46  5813.6  190.82  5843.8  192.32
#Mann= 11 ,-1 , 0
    4568     .07       0  4753.3     .05       0  4766.3     .07       0
  4859.4     .12       0  5002.8     .05       0  5015.9     .12       0
  5116.6     .05       0  5574.9    .035       0    5657     .05       0
  5689.9     .07       0  5813.6     .05       0
Bank Sta=5002.8,5015.9
XS Rating Curve= 0 ,0
Exp/Cntr=0.3,0.1

Type RM Length L Ch R = 1 ,5184    ,471,471,471
BEGIN DESCRIPTION:
TRIB 4 TO EIGHTEENMILE CREEK 8.0
END DESCRIPTION:
XS GIS Cut Line= 3
        2496425.     13494625.04        2496375.       13494125.
      2496674.99     13493325.03
#Sta/Elev= 30
  4497.9  190.44  4785.8  182.63  4879.8  179.27  4904.7  176.87  4947.7  171.58
  4952.7  172.28  4983.8  169.72  4984.3  169.22    4997  169.72  5021.8  171.21
  5040.5  174.73  5074.1  174.68  5212.6  175.48  5256.8  174.48  5271.9  175.59
  5278.1  177.89  5288.8  179.59  5302.1  179.75  5316.8  176.66  5320.8  175.81
  5327.1   172.8  5332.4  173.64  5342.2  171.96  5412.5  171.89    5421  173.31
  5442.8   177.2  5525.2  181.29  5643.9  185.51  5809.4     194  5854.8  194.74
#Mann= 10 ,-1 , 0
  4497.9     .05       0  4785.8     .07       0  4904.7     .12       0
  4983.8     .05       0    4997     .12       0  5074.1     .05       0
  5212.6     .07       0  5316.8     .05       0    5421     .12       0
  5525.2     .05       0
Bank Sta=4983.8,4997
XS Rating Curve= 0 ,0
Exp/Cntr=0.3,0.1

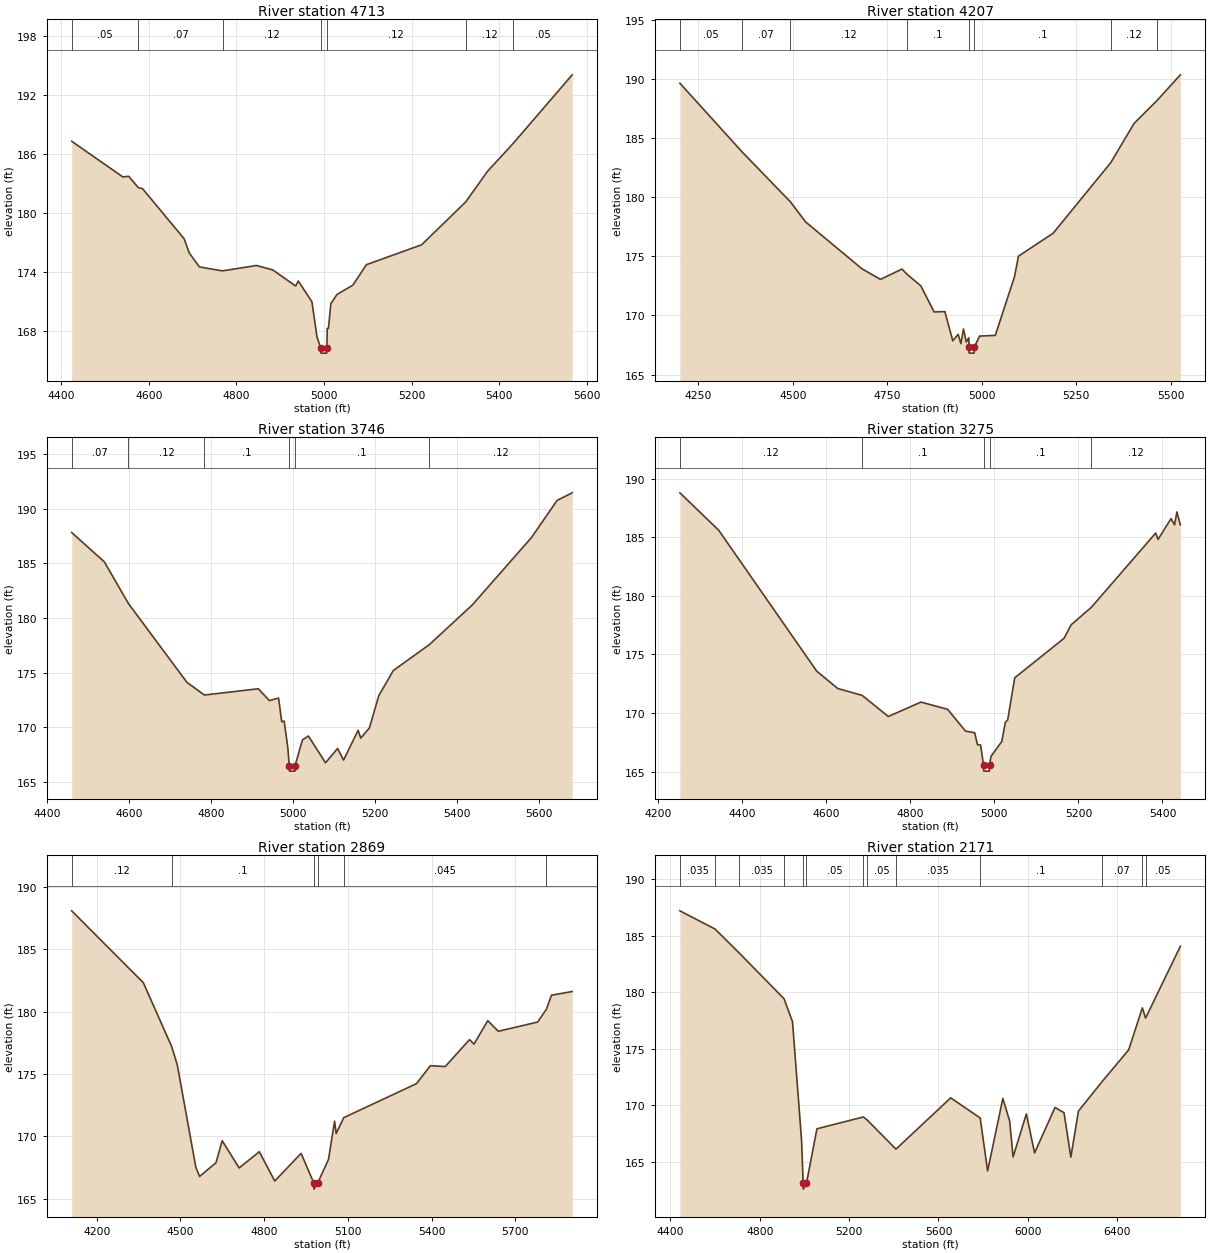
Type RM Length L Ch R = 1 ,4713    ,506,506,506
BEGIN DESCRIPTION:
TRIB 4 TO EIGHTEENMILE CREEK 7.0
END DESCRIPTION:
XS GIS Cut Line= 3
      2496474.98     13494525.04        2496775.       13494025.
      2497025.02     13493524.96
#Sta/Elev= 30
  4424.2  187.32  4540.9  183.69  4554.5  183.75  4576.4  182.59  4585.6  182.51
  4680.8   177.4  4692.5  175.95  4715.8  174.53  4768.4  174.13    4846  174.68
  4882.9  174.23  4935.4  172.59  4941.3   173.1  4972.4  170.99    4984  167.42
  4992.5  166.26    4993  165.76  5006.1  165.76  5006.6  166.26  5007.3  168.28
  5010.1  168.28  5015.7   170.8  5029.7  171.73    5066  172.68  5096.8  174.76
  5222.6  176.78  5323.3  181.14  5373.5  184.28    5432  187.11  5566.4  194.08
#Mann= 7 ,-1 , 0
  4424.2     .05       0  4576.4     .07       0  4768.4     .12       0
  4992.5     .05       0  5006.6     .12       0  5323.3     .12       0
    5432     .05       0
Bank Sta=4992.5,5006.6
XS Rating Curve= 0 ,0
Exp/Cntr=0.3,0.1

Type RM Length L Ch R = 1 ,4207    ,461,461,461
BEGIN DESCRIPTION:
TRIB 4 TO EIGHTEENMILE CREEK 6.0
END DESCRIPTION:
XS GIS Cut Line= 3
        2496575.       13494725.        2497175.       13494175.
      2497274.99     13493675.04
#Sta/Elev= 30
  4201.4  189.62  4366.2  183.81  4493.5  179.61  4534.1   177.9  4682.7  173.95
    4732  173.05  4788.7  173.92    4802  173.49  4838.7   172.5  4873.8   170.3
  4902.2  170.33  4923.2  167.86  4937.3  168.41  4944.7  167.62  4951.5  168.86
  4958.9  167.76  4965.7  168.12    4966  167.32  4966.5  166.82  4979.6  166.82
  4980.1  167.32  4994.1  168.26  5035.7  168.32  5086.7   173.3  5096.9  175.01
  5188.7  176.95  5340.8   182.9  5402.9  186.23  5462.8  188.14  5525.2  190.33
#Mann= 8 ,-1 , 0
  4201.4     .05       0  4366.2     .07       0  4493.5     .12       0
    4802      .1       0    4966     .05       0  4980.1      .1       0
  5340.8     .12       0  5462.8     .05       0
Bank Sta=4966,4980.1
XS Rating Curve= 0 ,0
Exp/Cntr=0.3,0.1

Type RM Length L Ch R = 1 ,3746    ,471,471,471
BEGIN DESCRIPTION:
TRIB 4 TO EIGHTEENMILE CREEK 5.0
END DESCRIPTION:
XS GIS Cut Line= 3
      2497125.02     13494874.97        2497425.       13494425.
      2497825.02     13493874.98
#Sta/Elev= 30
  4459.7  187.81  4539.3  185.13  4598.2  181.31  4740.6  174.12  4783.3  172.95
  4914.9  173.52  4941.9  172.44  4964.4  172.67    4972  170.51    4978  170.57
    4987  168.11  4990.4  166.49  4990.9  165.99  5004.1  165.99  5004.6  166.49
  5022.5  168.84  5037.2   169.2  5078.9  166.75  5108.3  168.06    5123     167
  5158.5  169.73  5164.7  169.01    5186  169.94  5208.8  172.89  5244.3  175.19
  5332.2  177.56  5436.7  181.18  5581.3  187.35  5643.9  190.75  5680.6  191.44
#Mann= 6 ,-1 , 0
  4459.7     .07       0  4598.2     .12       0  4783.3      .1       0
  4990.4     .05       0  5004.6      .1       0  5332.2     .12       0
Bank Sta=4990.4,5004.6
XS Rating Curve= 0 ,0
Exp/Cntr=0.3,0.1

Type RM Length L Ch R = 1 ,3275    ,406,406,406
BEGIN DESCRIPTION:
TRIB 4 TO EIGHTEENMILE CREEK 4.0
END DESCRIPTION:
XS GIS Cut Line= 3
      2497274.98     13495025.02        2497825.       13494525.
      2498024.98     13494125.04
#Sta/Elev= 30
  4252.1  188.79  4344.4   185.6  4577.5  173.58  4627.5   172.1  4685.7  171.51
  4747.8  169.71  4825.5  170.94    4889  170.32  4931.6  168.46  4953.2  168.33
    4960   167.3  4967.4  167.28  4974.4  165.55  4974.9  165.05  4988.2  165.05
  4988.7  165.55  4992.1  166.31  5017.8  167.58  5026.2  169.22  5031.8  169.41
  5048.5  173.01  5165.9  176.38  5182.7  177.53    5231  179.03  5383.9  185.36
  5389.5  184.82  5420.3  186.59  5428.7  186.06  5434.3  187.16  5442.6  186.05
#Mann= 5 ,-1 , 0
  4252.1     .12       0  4685.7      .1       0  4974.4     .05       0
  4988.7      .1       0    5231     .12       0
Bank Sta=4974.4,4988.7
XS Rating Curve= 0 ,0
Exp/Cntr=0.3,0.1

Type RM Length L Ch R = 1 ,2869    ,698,698,698
BEGIN DESCRIPTION:
Mapping XS fe76969b
END DESCRIPTION:
XS GIS Cut Line= 3
      2497356.91     13495154.81      2498127.71       13494759.
      2498940.06     13494311.16
#Sta/Elev= 30
    4110  188.09  4366.7  182.33  4468.5   177.2  4488.6  175.73  4555.1  167.51
  4568.7  166.79  4627.3  167.89  4649.5  169.65  4710.4  167.47  4782.6  168.77
  4837.9  166.42  4932.3  168.64  4977.7  166.27  4978.2  165.77    4992  166.27
  5030.5  168.15  5052.4  171.22  5058.1  170.23  5085.1   171.5  5345.9  174.23
  5395.9  175.67    5449   175.6  5536.1  177.76  5552.2   177.4  5601.5  179.28
  5639.3  178.43  5780.3  179.17  5811.8   180.2  5829.8  181.32  5904.1  181.62
#Mann= 6 ,-1 , 0
    4110     .12       0  4468.5      .1       0  4977.7     .05       0
    4992      .1       0  5085.1    .045       0  5811.8      .1       0
Bank Sta=4977.7,4992
XS Rating Curve= 0 ,0
Exp/Cntr=0.3,0.1

Type RM Length L Ch R = 1 ,2171    ,860,860,860
BEGIN DESCRIPTION:
Mapping XS c5951fbb
END DESCRIPTION:
XS GIS Cut Line= 3
        2497320.     13495263.45      2497854.68     13495173.17
      2499528.07      13494881.3
#Sta/Elev= 30
  4442.4  187.22  4599.7  185.61  4708.2  183.48  4908.6  179.44  4946.6   177.4
  4987.3  166.87  4994.5  163.08    4995  162.58  5008.9  163.08    5056  167.92
    5264  168.97  5280.4  168.71  5409.9  166.12  5654.9  170.66    5787  168.88
  5820.2  164.19  5888.4  170.61  5918.9  168.61  5934.2  165.43  5993.7  169.24
  6030.5  165.79  6121.9  169.81  6162.2  169.35  6192.9  165.41  6226.9  169.49
  6331.6  172.07  6451.8  174.91  6513.1  178.63  6527.5  177.72  6683.3  184.09
#Mann= 13 ,-1 , 0
  4442.4    .035       0  4599.7     .12       0  4708.2    .035       0
  4908.6     .05       0  4994.5     .05       0  5008.9     .05       0
    5264      .1       0  5280.4     .05       0  5409.9    .035       0
    5787      .1       0  6331.6     .07       0  6513.1    .035       0
  6527.5     .05       0
Bank Sta=4994.5,5008.9
XS Rating Curve= 0 ,0
Exp/Cntr=0.3,0.1

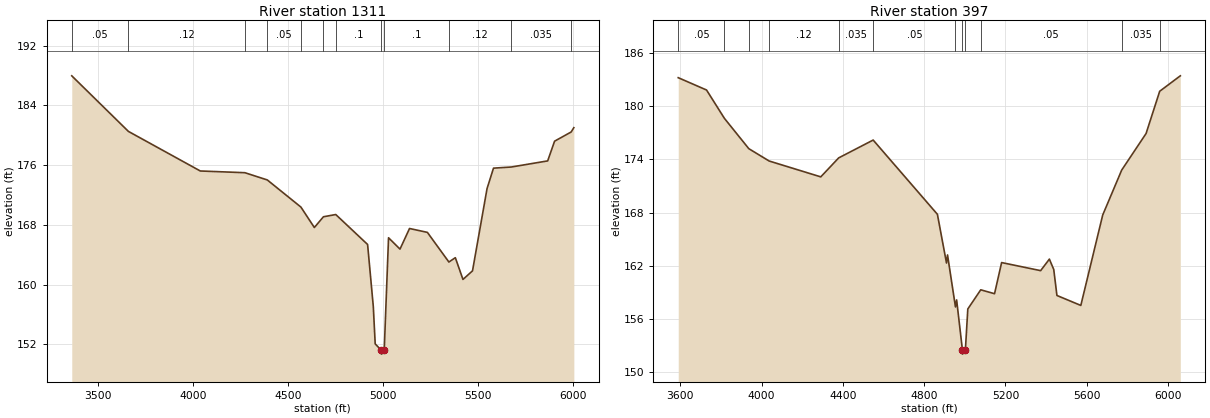
Type RM Length L Ch R = 1 ,1311    ,914,914,914
BEGIN DESCRIPTION:
Mapping XS d1f3b6b1
END DESCRIPTION:
XS GIS Cut Line= 3
      2496839.05     13495597.89       2498451.9     13495534.29
      2499475.97     13495436.86
#Sta/Elev= 30
  3361.9  187.97    3660  180.53  4038.4  175.23    4273     175  4391.1  174.03
    4568   170.4  4638.8  167.66  4686.6   169.1  4751.5   169.4  4919.1  165.39
  4949.1  157.08  4959.1  152.08  4991.9  151.21  4992.4  150.71  5006.6  151.21
  5029.3  166.29  5089.6  164.77  5139.8  167.53  5233.8  167.01    5347  163.04
  5380.9  163.62  5421.1  160.71  5471.3  161.86  5547.9  172.88  5581.8  175.61
  5675.2  175.76    5867  176.58  5903.3  179.22  5990.5  180.45  6004.7  181.03
#Mann= 12 ,-1 , 0
  3361.9     .05       0    3660     .12       0    4273    .035       0
  4391.1     .05       0    4568     .07       0  4686.6     .05       0
  4751.5      .1       0  4991.9     .05       0  5006.6      .1       0
    5347     .12       0  5675.2    .035       0  5990.5     .05       0
Bank Sta=4991.9,5006.6
XS Rating Curve= 0 ,0
Exp/Cntr=0.3,0.1

Type RM Length L Ch R = 1 ,397     ,0,0,0
BEGIN DESCRIPTION:
TRIB 4 TO EIGHTEENMILE CREEK 1.0
END DESCRIPTION:
XS GIS Cut Line= 3
      2496828.68     13495868.73      2498208.31     13496158.35
      2499125.04     13495624.98
#Sta/Elev= 30
  3590.3  183.21  3729.6  181.82  3817.7  178.62  3937.5  175.21  4037.4  173.82
  4291.6  172.03  4379.8  174.17  4549.4  176.18  4865.5  167.81  4910.2  162.32
  4915.3  163.23  4954.3  157.37  4960.1  158.16  4988.4  152.55  4988.9  152.05
  5003.2  152.55  5015.1  157.14  5078.7   159.3  5146.6  158.86  5181.4  162.37
  5373.4  161.46  5416.4  162.76  5437.9  161.59  5453.6  158.66  5571.1  157.54
  5678.8  167.73  5772.3   172.8  5892.2  176.92  5959.2  181.68  6060.6  183.42
#Mann= 12 ,-1 , 0
  3590.3     .05       0  3817.7    .035       0  3937.5     .07       0
  4037.4     .12       0  4379.8    .035       0  4549.4     .05       0
  4954.3      .1       0  4988.4     .05       0  5003.2      .1       0
  5078.7     .05       0  5772.3    .035       0  5959.2     .12       0
Bank Sta=4988.4,5003.2
XS Rating Curve= 0 ,0
Exp/Cntr=0.3,0.1

Chan Stop Cuts=-1
Use User Specified Reach Order=0
Composite Channel Slope=5