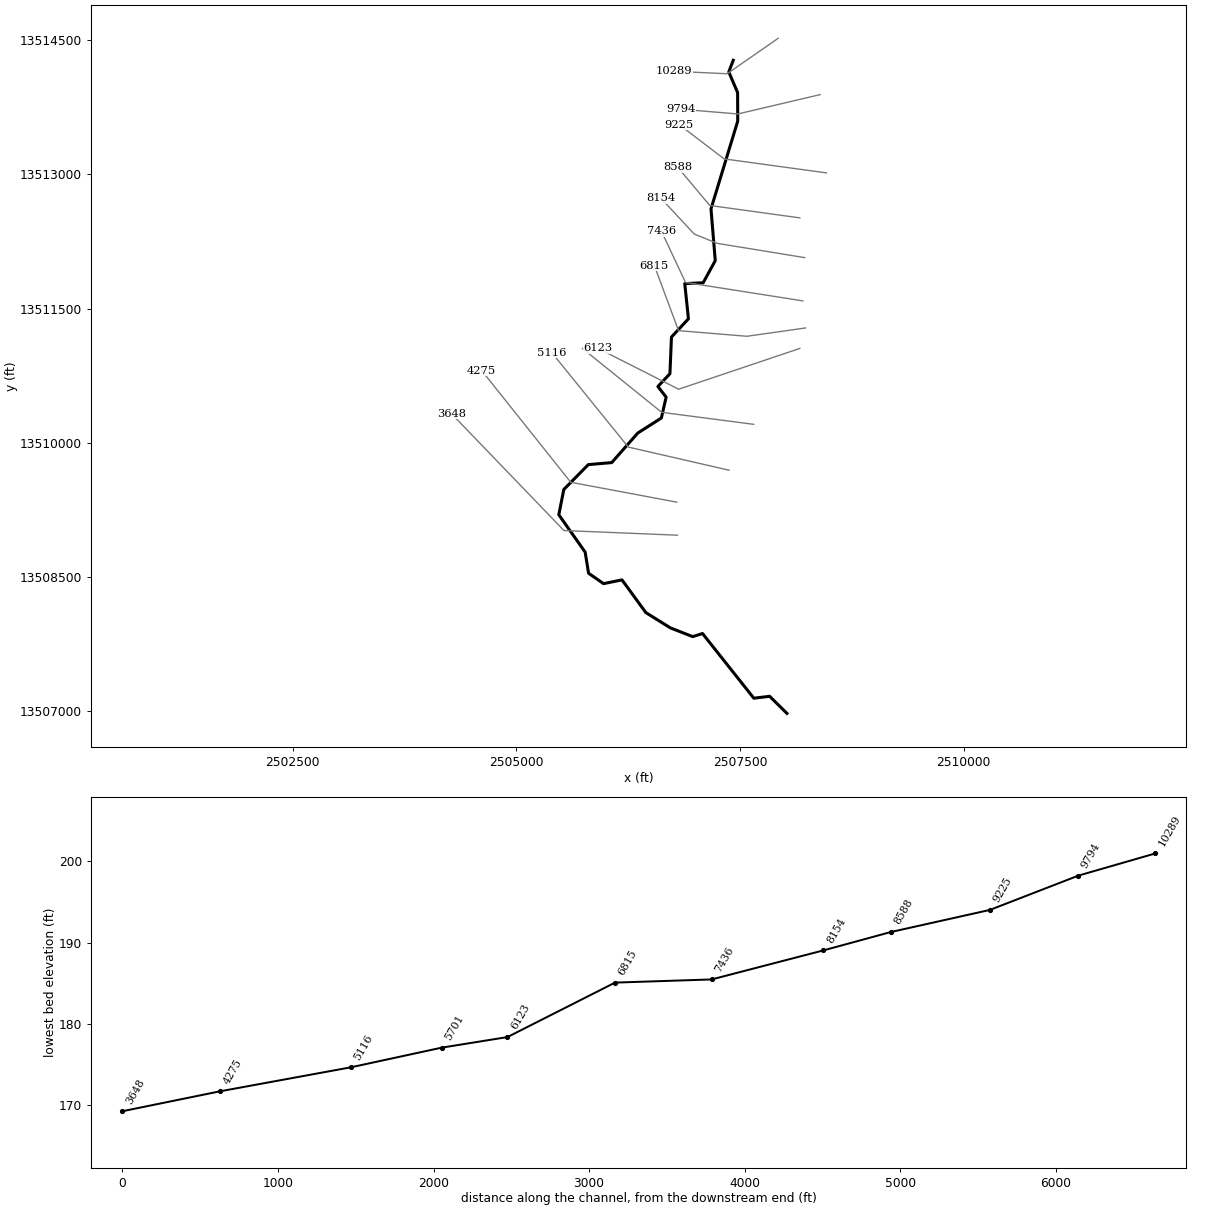
--- TRIB 4 TO FIFTEENMILE CREEK.prj (project) ---

Proj Title=TRIB 4 TO FIFTEENMILE CREEK Base Level Engineering
Current Plan=p01
Default Exp/Contr=0.3,0.1
English Units
Geom File=g01
Flow File=f01
Plan File=p01
BEGIN DESCRIPTION:
TRIB 4 TO FIFTEENMILE CREEK
END DESCRIPTION:

--- TRIB 4 TO FIFTEENMILE CREEK.p01 (plan) ---

Plan Title=Multiple Run
Short Identifier=Multiple
Geom File=g01
Flow File=f01
Subcritical Flow
K Sum by GR= 0
Std Step Tol= 0.01
Critical Tol= 0.01
Num of Std Step Trials= 20
Max Error Tol= 0.3
Flow Tol Ratio= 0.001
Split Flow NTrial= 30
Split Flow Tol= 0.02
Split Flow Ratio= 0.02
Log Output Level= 0
Friction Slope Method= 1
Unsteady Friction Slope Method= 2
Unsteady Bridges Friction Slope Method= 1
Parabolic Critical Depth
Global Vel Dist=  1 , 1 , 1
Global Log Level= 0
CheckData=True
Encroach Param= -1, 0, 0, 0
BEGIN DESCRIPTION:
Multiple Run
END DESCRIPTION:

--- TRIB 4 TO FIFTEENMILE CREEK.f01 (steady flow) ---

Flow Title=Multiple
Number of Profiles=7
Profile Names=10-year,25-year,50-year,1pct_min,100-year,1pct_plu,500-year
River Rch & RM= TRIB 4 TO FIFTEE,Reach-1,10289
     408     633     828     525    1047    2090    1656
Boundary for River Rch & Prof#=TRIB 4 TO FIFTEE,Reach-1,1
Up Type=0
Dn Type=3
Dn Slope=0.005
Boundary for River Rch & Prof#=TRIB 4 TO FIFTEE,Reach-1,2
Up Type=0
Dn Type=3
Dn Slope=0.005
Boundary for River Rch & Prof#=TRIB 4 TO FIFTEE,Reach-1,3
Up Type=0
Dn Type=3
Dn Slope=0.005
Boundary for River Rch & Prof#=TRIB 4 TO FIFTEE,Reach-1,4
Up Type=0
Dn Type=3
Dn Slope=0.005
Boundary for River Rch & Prof#=TRIB 4 TO FIFTEE,Reach-1,5
Up Type=0
Dn Type=3
Dn Slope=0.005
Boundary for River Rch & Prof#=TRIB 4 TO FIFTEE,Reach-1,6
Up Type=0
Dn Type=3
Dn Slope=0.005
Boundary for River Rch & Prof#=TRIB 4 TO FIFTEE,Reach-1,7
Up Type=0
Dn Type=3
Dn Slope=0.005

--- TRIB 4 TO FIFTEENMILE CREEK.g01 (geometry) ---

Geom Title=Existing Conditions

River Reach=TRIB 4 TO FIFTEE,Reach-1
Reach XY= 30
      2507425.00     13514275.00      2507374.89     13514145.08
      2507473.78     13513914.50      2507474.94     13513595.03
      2507176.22     13512614.50      2507223.80     13512035.50
      2507088.74     13511788.38      2506882.87     13511778.63
      2506923.95     13511385.43      2506734.30     13511181.67
      2506717.20     13510771.58      2506582.60     13510628.34
      2506674.75     13510509.78      2506621.39     13510276.48
      2506357.95     13510108.51      2506066.69     13509778.10
      2505805.00     13509755.63      2505530.83     13509477.30
      2505475.06     13509195.03      2505769.53     13508777.45
      2505807.86     13508541.46      2505975.00     13508425.00
      2506181.19     13508467.25      2506448.18     13508101.29
      2506722.56     13507930.48      2506971.60     13507832.84
      2507081.33     13507867.61      2507654.85     13507144.58
      2507831.74     13507165.87      2508025.00     13506975.00

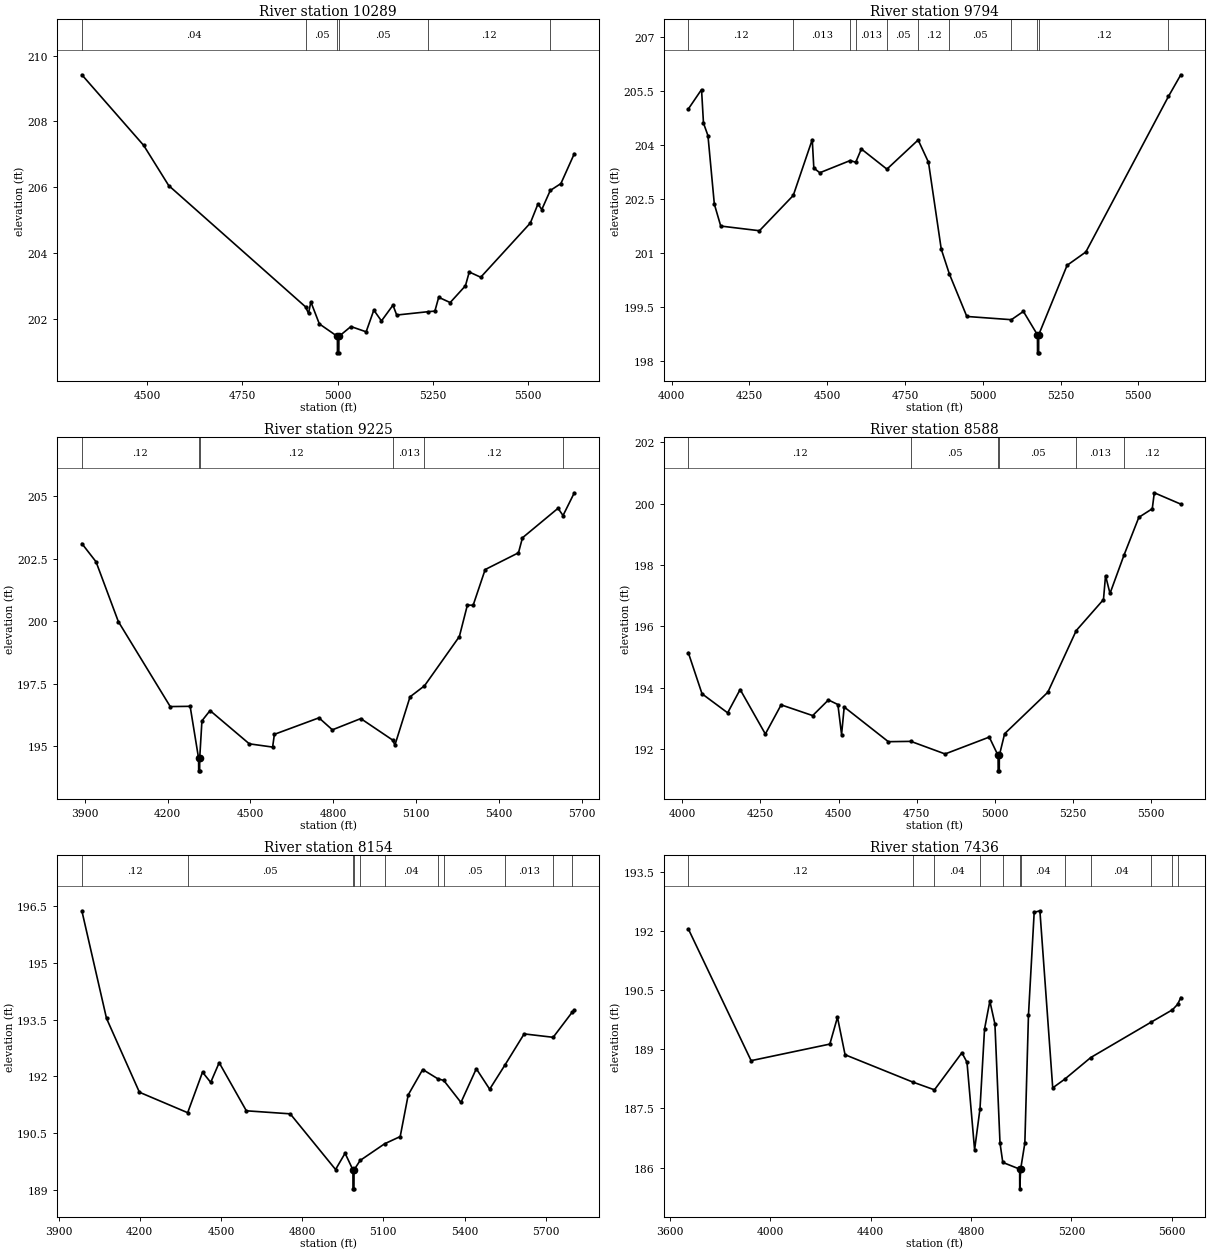
Type RM Length L Ch R = 1,10289,495,495,495
BEGIN DESCRIPTION:
Mapping XS a5751b27
END DESCRIPTION:
XS GIS Cut Line= 3
      2507926.32     13514520.39      2507356.86     13514124.54
      2506759.83     13514152.31
#Sta/Elev= 30
  4329.5  209.42  4491.7  207.27  4557.2  206.05  4915.9  202.36  4923.8  202.16
  4929.9  202.51  4952.2  201.84  4999.5  201.46  4999.7  200.96  5003.2  200.96
  5003.5  201.46  5034.9  201.76  5074.9  201.60  5095.0  202.26  5115.0  201.93
  5145.2  202.41  5155.0  202.11  5235.8  202.21  5255.1  202.23  5265.1  202.65
  5295.2  202.49  5335.2  203.00  5345.2  203.42  5375.3  203.26  5505.4  204.91
  5525.4  205.49  5535.4  205.32  5557.6  205.90  5585.5  206.11  5620.7  207.02
#Mann=6,-1,0
  4329.5    0.04       0  4915.9    0.05       0  4999.5    0.05       0
  5003.5    0.05       0  5235.8    0.12       0  5557.6    0.04       0
Bank Sta=4999.5,5003.5
Exp/Cntr=0.3,0.1

Type RM Length L Ch R = 1,9794,569,569,569
BEGIN DESCRIPTION:
Mapping XS 1d93a890
END DESCRIPTION:
XS GIS Cut Line= 3
      2508396.40     13513891.37      2507475.08     13513674.97
      2506840.90     13513728.17
#Sta/Elev= 30
  4053.6  205.00  4096.1  205.54  4102.3  204.61  4116.7  204.26  4137.2  202.36
  4157.8  201.75  4282.2  201.62  4390.9  202.60  4451.9  204.15  4457.0  203.36
  4476.2  203.23  4574.2  203.57  4591.6  203.52  4609.7  203.89  4691.9  203.33
  4792.3  204.14  4825.5  203.52  4866.5  201.11  4892.6  200.42  4948.7  199.24
  5091.9  199.15  5130.5  199.38  5175.7  198.73  5176.0  198.23  5179.5  198.23
  5179.7  198.73  5271.0  200.66  5331.2  201.03  5596.8  205.35  5636.4  205.95
#Mann=11,-1,0
  4053.6    0.12       0  4390.9   0.013       0  4574.2    0.12       0
  4591.6   0.013       0  4691.9    0.05       0  4792.3    0.12       0
  4892.6    0.05       0  5091.9    0.12       0  5175.7    0.05       0
  5179.7    0.12       0  5596.8    0.04       0
Bank Sta=5175.7,5179.7
Exp/Cntr=0.3,0.1

Type RM Length L Ch R = 1,9225,637,637,637
BEGIN DESCRIPTION:
Mapping XS 79517497
END DESCRIPTION:
XS GIS Cut Line= 3
      2508465.88     13513016.37      2507322.13     13513173.15
      2506822.16     13513555.08
#Sta/Elev= 30
  3889.4  203.10  3940.8  202.37  4021.5  199.98  4209.5  196.58  4281.6  196.59
  4312.2  194.51  4312.5  194.01  4316.0  194.01  4316.2  194.51  4324.3  196.01
  4353.7  196.42  4495.9  195.09  4580.3  194.96  4586.7  195.47  4748.2  196.13
  4796.7  195.65  4899.6  196.10  5015.1  195.24  5023.2  195.04  5078.0  196.97
  5130.3  197.41  5256.6  199.38  5285.7  200.64  5306.5  200.63  5350.1  202.06
  5470.7  202.73  5485.2  203.33  5614.0  204.51  5632.1  204.22  5673.0  205.13
#Mann=6,-1,0
  3889.4    0.12       0  4312.2    0.05       0  4316.2    0.12       0
  5015.1   0.013       0  5130.3    0.12       0  5632.1    0.04       0
Bank Sta=4312.2,4316.2
Exp/Cntr=0.3,0.1

Type RM Length L Ch R = 1,8588,434,434,434
BEGIN DESCRIPTION:
Mapping XS f5338970
END DESCRIPTION:
XS GIS Cut Line= 3
      2508169.33     13512513.44      2507162.41     13512652.32
      2506802.51     13513081.43
#Sta/Elev= 30
  4019.0  195.14  4062.9  193.80  4144.9  193.18  4184.9  193.94  4265.6  192.49
  4316.1  193.44  4417.1  193.09  4467.5  193.60  4497.8  193.45  4509.6  192.47
  4518.0  193.37  4659.3  192.24  4731.5  192.25  4841.0  191.84  4982.4  192.39
  5010.6  191.79  5010.9  191.29  5014.4  191.29  5014.6  191.79  5031.6  192.50
  5169.8  193.85  5260.8  195.86  5348.0  196.87  5354.6  197.65  5368.9  197.07
  5413.4  198.31  5461.2  199.55  5504.2  199.83  5510.7  200.35  5595.5  199.98
#Mann=6,-1,0
  4019.0    0.12       0  4731.5    0.05       0  5010.6    0.05       0
  5014.6    0.05       0  5260.8   0.013       0  5413.4    0.12       0
Bank Sta=5010.6,5014.6
Exp/Cntr=0.3,0.1

Type RM Length L Ch R = 1,8154,718,718,718
BEGIN DESCRIPTION:
Mapping XS 78bc9d1b
END DESCRIPTION:
XS GIS Cut Line= 4
      2508224.89     13512068.99      2507245.74     13512228.71
      2506988.80     13512332.88      2506613.78     13512735.68
#Sta/Elev= 30
  3986.0  196.37  4077.1  193.53  4198.7  191.58  4377.0  191.04  4431.9  192.11
  4462.1  191.84  4493.4  192.36  4593.8  191.09  4755.9  191.01  4923.5  189.54
  4958.6  189.97  4987.7  189.53  4987.9  189.03  4991.4  189.03  4991.7  189.53
  5014.4  189.78  5104.9  190.22  5162.3  190.41  5191.9  191.51  5245.5  192.18
  5300.2  191.94  5323.4  191.89  5386.8  191.31  5443.5  192.20  5492.9  191.66
  5549.5  192.30  5620.3  193.12  5727.5  193.03  5797.5  193.69  5805.7  193.74
#Mann=11,-1,0
  3986.0    0.12       0  4377.0    0.05       0  4987.7    0.05       0
  4991.7    0.05       0  5014.4    0.12       0  5104.9    0.04       0
  5300.2    0.12       0  5323.4    0.05       0  5549.5   0.013       0
  5727.5    0.05       0  5797.5    0.12       0
Bank Sta=4987.7,4991.7
Exp/Cntr=0.3,0.1

Type RM Length L Ch R = 1,7436,621,621,621
BEGIN DESCRIPTION:
Mapping XS fd433c6c
END DESCRIPTION:
XS GIS Cut Line= 3
      2508202.23     13511585.60      2506891.20     13511792.14
      2506620.76     13512367.56
#Sta/Elev= 30
  3672.8  192.05  3923.1  188.71  4236.9  189.13  4267.3  189.81  4297.6  188.86
  4566.4  188.17  4653.9  187.97  4763.3  188.91  4783.6  188.67  4813.9  186.45
  4835.4  187.49  4853.5  189.51  4874.7  190.22  4894.9  189.64  4915.2  186.62
  4926.3  186.13  4993.5  185.96  4993.8  185.46  4997.5  185.96  5014.2  186.62
  5028.6  189.86  5051.4  192.47  5074.2  192.51  5125.3  188.02  5173.1  188.24
  5277.1  188.79  5515.9  189.68  5602.6  190.00  5623.4  190.14  5635.8  190.31
#Mann=12,-1,0
  3672.8    0.12       0  4566.4    0.05       0  4653.9    0.04       0
  4835.4    0.05       0  4926.3    0.04       0  4993.5    0.04       0
  4997.5    0.04       0  5173.1    0.12       0  5277.1    0.04       0
  5515.9    0.05       0  5602.6    0.04       0  5623.4   0.013       0
Bank Sta=4993.5,4997.5
Exp/Cntr=0.3,0.1

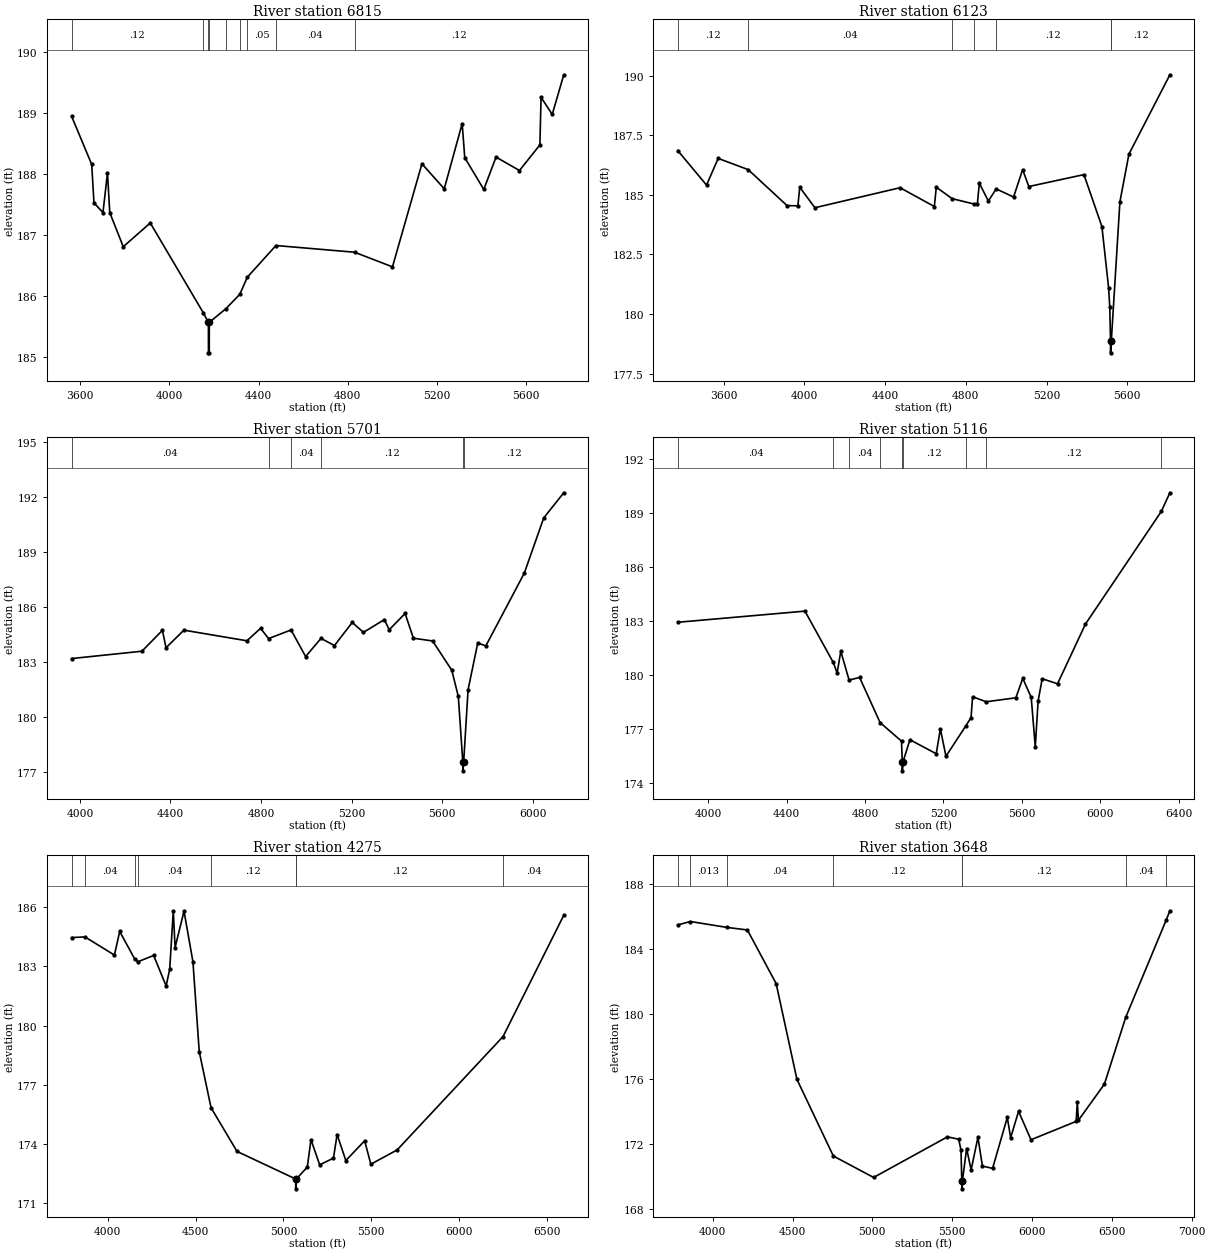
Type RM Length L Ch R = 1,6815,692,692,692
BEGIN DESCRIPTION:
Mapping XS 970424f9
END DESCRIPTION:
XS GIS Cut Line= 4
      2508234.28     13511283.39      2507577.82     13511190.12
      2506813.45     13511253.02      2506543.02     13511981.11
#Sta/Elev= 30
  3561.8  188.95  3652.0  188.16  3662.1  187.53  3702.5  187.37  3722.7  188.02
  3733.0  187.37  3793.4  186.81  3914.6  187.20  4151.8  185.73  4175.2  185.57
  4175.5  185.07  4179.0  185.07  4179.2  185.57  4252.6  185.79  4316.1  186.03
  4349.6  186.31  4478.0  186.83  4830.5  186.72  5000.5  186.48  5132.6  188.17
  5232.7  187.76  5313.1  188.83  5324.6  188.27  5410.0  187.75  5464.9  188.28
  5570.0  188.06  5661.5  188.48  5666.8  189.26  5716.9  188.98  5768.5  189.63
#Mann=9,-1,0
  3561.8    0.12       0  4151.8    0.04       0  4175.2    0.05       0
  4179.2    0.04       0  4252.6    0.05       0  4316.1    0.12       0
  4349.6    0.05       0  4478.0    0.04       0  4830.5    0.12       0
Bank Sta=4175.2,4179.2
Exp/Cntr=0.3,0.1

Type RM Length L Ch R = 1,6123,422,422,422
BEGIN DESCRIPTION:
Mapping XS 69272f55
END DESCRIPTION:
XS GIS Cut Line= 3
      2508169.17     13511054.23      2506814.97     13510598.49
      2505913.90     13511054.24
#Sta/Elev= 30
  3372.7  186.86  3515.5  185.41  3573.2  186.53  3721.6  186.06  3914.4  184.55
  3968.0  184.54  3977.4  185.32  4052.4  184.46  4474.4  185.30  4644.3  184.51
  4653.8  185.32  4732.9  184.84  4838.7  184.62  4857.5  184.63  4867.2  185.49
  4911.8  184.74  4950.5  185.25  5036.8  184.91  5081.7  186.06  5112.4  185.35
  5385.4  185.85  5474.5  183.67  5507.5  181.11  5513.5  180.29  5517.1  178.87
  5517.3  178.37  5521.1  178.87  5563.7  184.71  5608.4  186.71  5811.3  190.04
#Mann=7,-1,0
  3372.7    0.12       0  3721.6    0.04       0  4732.9   0.013       0
  4838.7    0.04       0  4950.5    0.12       0  5517.1    0.05       0
  5521.1    0.12       0
Bank Sta=5517.1,5521.1
Exp/Cntr=0.3,0.1

Type RM Length L Ch R = 1,5701,585,585,585
BEGIN DESCRIPTION:
TRIB 4 TO FIFTEENMILE CREEK 7.0
END DESCRIPTION:
XS GIS Cut Line= 3
      2507652.95     13510205.92      2506624.87     13510340.06
      2505739.20     13511053.85
#Sta/Elev= 30
  3963.2  183.20  4273.8  183.60  4364.5  184.74  4380.4  183.79  4459.4  184.75
  4737.7  184.17  4798.2  184.85  4833.3  184.29  4932.8  184.76  4997.2  183.31
  5065.0  184.30  5124.6  183.91  5203.0  185.17  5252.6  184.63  5345.3  185.33
  5366.2  184.77  5436.6  185.66  5473.3  184.31  5558.1  184.16  5642.9  182.56
  5671.7  181.13  5691.4  177.57  5691.6  177.07  5695.4  177.57  5714.8  181.50
  5757.6  184.05  5793.2  183.89  5963.1  187.86  6049.1  190.88  6137.5  192.25
#Mann=6,-1,0
  3963.2    0.04       0  4833.3   0.013       0  4932.8    0.04       0
  5065.0    0.12       0  5691.4    0.04       0  5695.4    0.12       0
Bank Sta=5691.4,5695.4
Exp/Cntr=0.3,0.1

Type RM Length L Ch R = 1,5116,841,841,841
BEGIN DESCRIPTION:
TRIB 4 TO FIFTEENMILE CREEK 6.0
END DESCRIPTION:
XS GIS Cut Line= 3
      2507377.40     13509693.32      2506251.75     13509951.59
      2505399.11     13511004.70
#Sta/Elev= 30
  3845.1  182.91  4493.9  183.53  4638.2  180.68  4658.1  180.09  4676.7  181.30
  4718.9  179.70  4772.7  179.84  4877.3  177.33  4986.4  176.30  4990.2  175.15
  4990.5  174.65  4994.2  175.15  5029.1  176.38  5163.5  175.60  5184.5  176.98
  5213.0  175.46  5313.7  177.14  5340.9  177.61  5348.9  178.77  5417.9  178.49
  5569.5  178.71  5604.7  179.79  5647.7  178.74  5668.6  175.99  5683.0  178.53
  5703.8  179.77  5782.1  179.49  5924.4  182.81  6311.1  189.07  6355.0  190.11
#Mann=9,-1,0
  3845.1    0.04       0  4638.2   0.013       0  4718.9    0.04       0
  4877.3    0.12       0  4990.2    0.05       0  4994.2    0.12       0
  5313.7    0.03       0  5417.9    0.12       0  6311.1    0.04       0
Bank Sta=4990.2,4994.2
Exp/Cntr=0.3,0.1

Type RM Length L Ch R = 1,4275,627,627,627
BEGIN DESCRIPTION:
TRIB 4 TO FIFTEENMILE CREEK 5.0
END DESCRIPTION:
XS GIS Cut Line= 3
      2506794.27     13509335.86      2505608.29     13509558.43
      2504613.45     13510806.84
#Sta/Elev= 30
  3793.4  184.47  3869.9  184.50  4037.3  183.58  4067.4  184.78  4153.5  183.37
  4171.5  183.24  4260.7  183.56  4331.9  182.01  4352.3  182.87  4372.6  185.83
  4382.8  183.96  4433.7  185.81  4484.5  183.24  4520.4  178.67  4587.7  175.82
  4735.7  173.60  5069.8  172.20  5070.0  171.70  5073.8  172.20  5135.9  172.81
  5156.7  174.20  5206.3  172.92  5284.8  173.26  5305.6  174.46  5355.2  173.14
  5462.5  174.14  5497.8  172.95  5647.8  173.68  6250.7  179.44  6596.4  185.60
#Mann=8,-1,0
  3793.4    0.03       0  3869.9    0.04       0  4153.5   0.013       0
  4171.5    0.04       0  4587.7    0.12       0  5069.8    0.05       0
  5073.8    0.12       0  6250.7    0.04       0
Bank Sta=5069.8,5073.8
Exp/Cntr=0.3,0.1

Type RM Length L Ch R = 1,3648,0,0,0
BEGIN DESCRIPTION:
TRIB 4 TO FIFTEENMILE CREEK 4.0
END DESCRIPTION:
XS GIS Cut Line= 3
      2506800.98     13508966.56      2505532.86     13509018.83
      2504274.97     13510325.03
#Sta/Elev= 30
  3781.0  185.49  3860.2  185.70  4087.0  185.34  4217.3  185.18  4397.5  181.88
  4527.6  175.99  4755.7  171.27  5008.0  169.95  5470.4  172.45  5541.1  172.30
  5555.3  171.63  5560.2  169.75  5560.4  169.25  5564.2  169.75  5590.5  171.73
  5618.8  170.41  5661.2  172.42  5689.5  170.65  5753.1  170.51  5845.2  173.64
  5866.3  172.40  5915.9  174.02  5993.6  172.27  6276.6  173.40  6283.6  174.60
  6290.8  173.47  6453.4  175.69  6587.6  179.82  6841.4  185.81  6863.6  186.36
#Mann=8,-1,0
  3781.0    0.03       0  3860.2   0.013       0  4087.0    0.04       0
  4755.7    0.12       0  5560.2    0.05       0  5564.2    0.12       0
  6587.6    0.04       0  6841.4    0.05       0
Bank Sta=5560.2,5564.2
Exp/Cntr=0.3,0.1

Chan Stop Cuts=-1