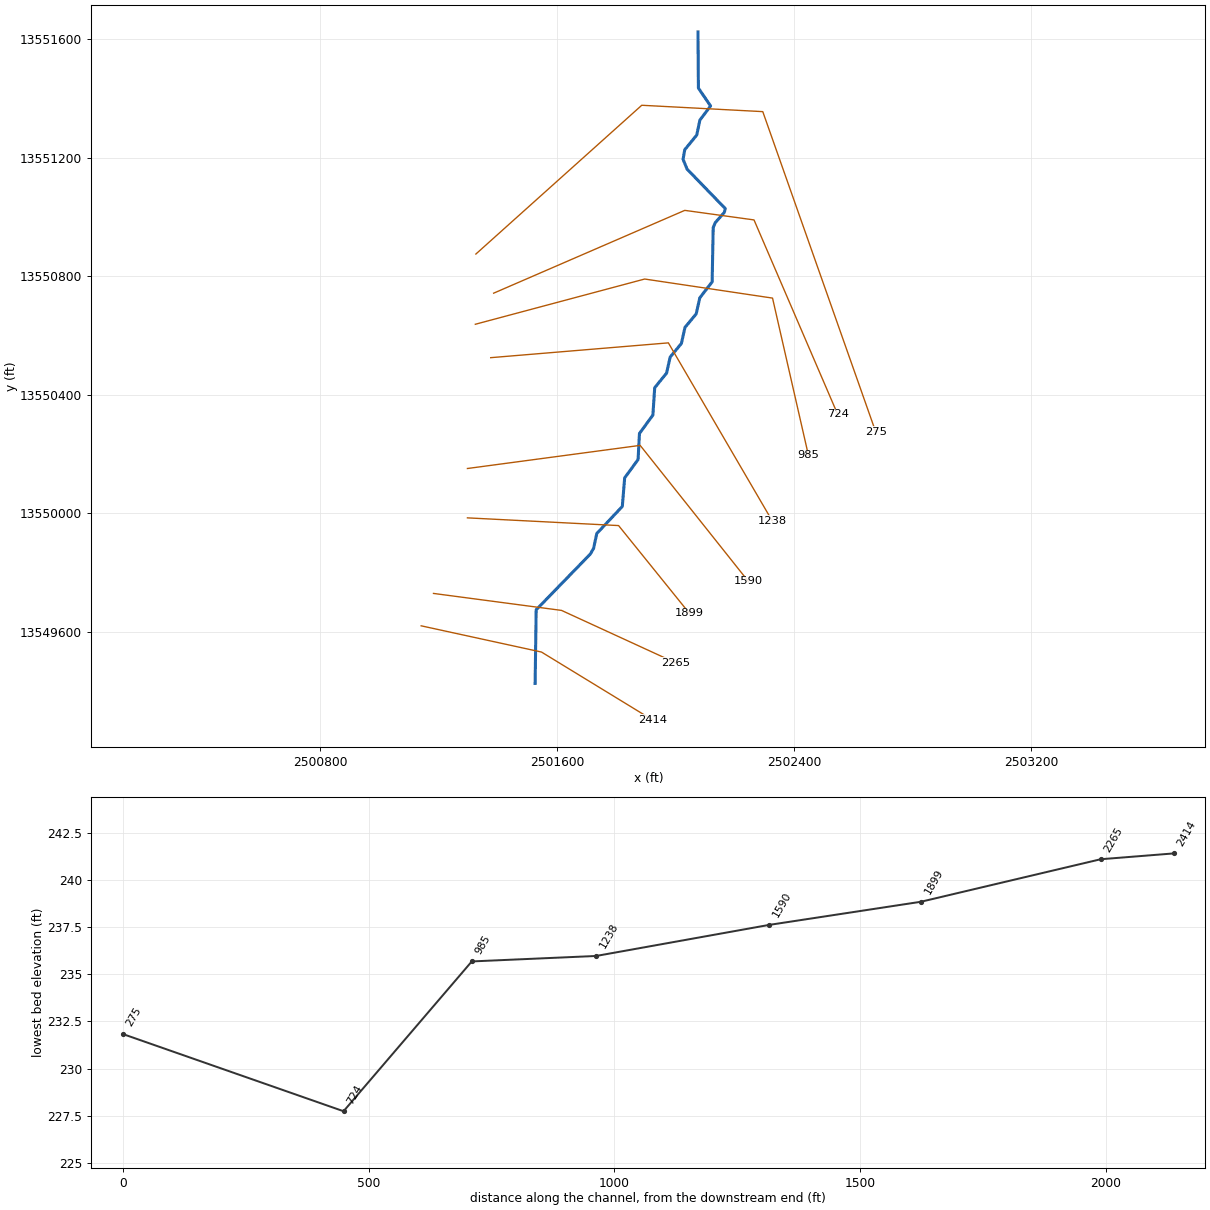
--- TRIB 4 TO FIVEMILE CREEK.prj (project) ---

Proj Title=TRIB 4 TO FIVEMILE CREEK Base Level Engineering
Current Plan=p01
Default Exp/Contr=0.3,0.1
English Units
Geom File=g01
Flow File=f01
Plan File=p01
BEGIN DESCRIPTION:
TRIB 4 TO FIVEMILE CREEK
END DESCRIPTION:

--- TRIB 4 TO FIVEMILE CREEK.p01 (plan) ---

Plan Title=Multiple Run
Short Identifier=Multiple
Geom File=g01
Flow File=f01
Subcritical Flow
K Sum by GR= 0
Std Step Tol= 0.01
Critical Tol= 0.01
Num of Std Step Trials= 20
Max Error Tol= 0.3
Flow Tol Ratio= 0.001
Split Flow NTrial= 30
Split Flow Tol= 0.02
Split Flow Ratio= 0.02
Log Output Level= 0
Friction Slope Method= 1
Unsteady Friction Slope Method= 2
Unsteady Bridges Friction Slope Method= 1
Parabolic Critical Depth
Global Vel Dist=  1 , 1 , 1
Global Log Level= 0
CheckData=True
Encroach Param= -1, 0, 0, 0
BEGIN DESCRIPTION:
Multiple Run
END DESCRIPTION:

--- TRIB 4 TO FIVEMILE CREEK.f01 (steady flow) ---

Flow Title=Multiple
Number of Profiles=7
Profile Names=10-year,25-year,50-year,1pct_min,100-year,1pct_plu,500-year
River Rch & RM= TRIB 4 TO FIVEMI,Reach-1,2414
     394     617     813     520    1038    2072    1672
Boundary for River Rch & Prof#=TRIB 4 TO FIVEMI,Reach-1,1
Up Type=0
Dn Type=3
Dn Slope=0.005
Boundary for River Rch & Prof#=TRIB 4 TO FIVEMI,Reach-1,2
Up Type=0
Dn Type=3
Dn Slope=0.005
Boundary for River Rch & Prof#=TRIB 4 TO FIVEMI,Reach-1,3
Up Type=0
Dn Type=3
Dn Slope=0.005
Boundary for River Rch & Prof#=TRIB 4 TO FIVEMI,Reach-1,4
Up Type=0
Dn Type=3
Dn Slope=0.005
Boundary for River Rch & Prof#=TRIB 4 TO FIVEMI,Reach-1,5
Up Type=0
Dn Type=3
Dn Slope=0.005
Boundary for River Rch & Prof#=TRIB 4 TO FIVEMI,Reach-1,6
Up Type=0
Dn Type=3
Dn Slope=0.005
Boundary for River Rch & Prof#=TRIB 4 TO FIVEMI,Reach-1,7
Up Type=0
Dn Type=3
Dn Slope=0.005

--- TRIB 4 TO FIVEMILE CREEK.g01 (geometry) ---

Geom Title=Existing Conditions

River Reach=TRIB 4 TO FIVEMI,Reach-1
Reach XY= 30
      2501525.00     13549425.00      2501528.53     13549673.54
      2501711.37     13549861.79      2501722.47     13549881.05
      2501733.18     13549931.04      2501819.46     13550022.58
      2501827.36     13550119.02      2501872.65     13550180.97
      2501877.35     13550269.03      2501922.65     13550330.97
      2501928.83     13550423.42      2501968.88     13550472.82
      2501981.08     13550527.20      2502018.92     13550572.80
      2502031.08     13550627.20      2502068.92     13550672.80
      2502081.12     13550727.18      2502122.76     13550780.93
      2502126.39     13550964.57      2502133.47     13550981.19
      2502163.67     13551015.16      2502167.21     13551028.42
      2502038.12     13551161.79      2502024.59     13551195.13
      2502030.31     13551227.19      2502070.81     13551276.73
      2502081.39     13551327.29      2502117.47     13551374.99
      2502076.38     13551435.43      2502075.00     13551625.00

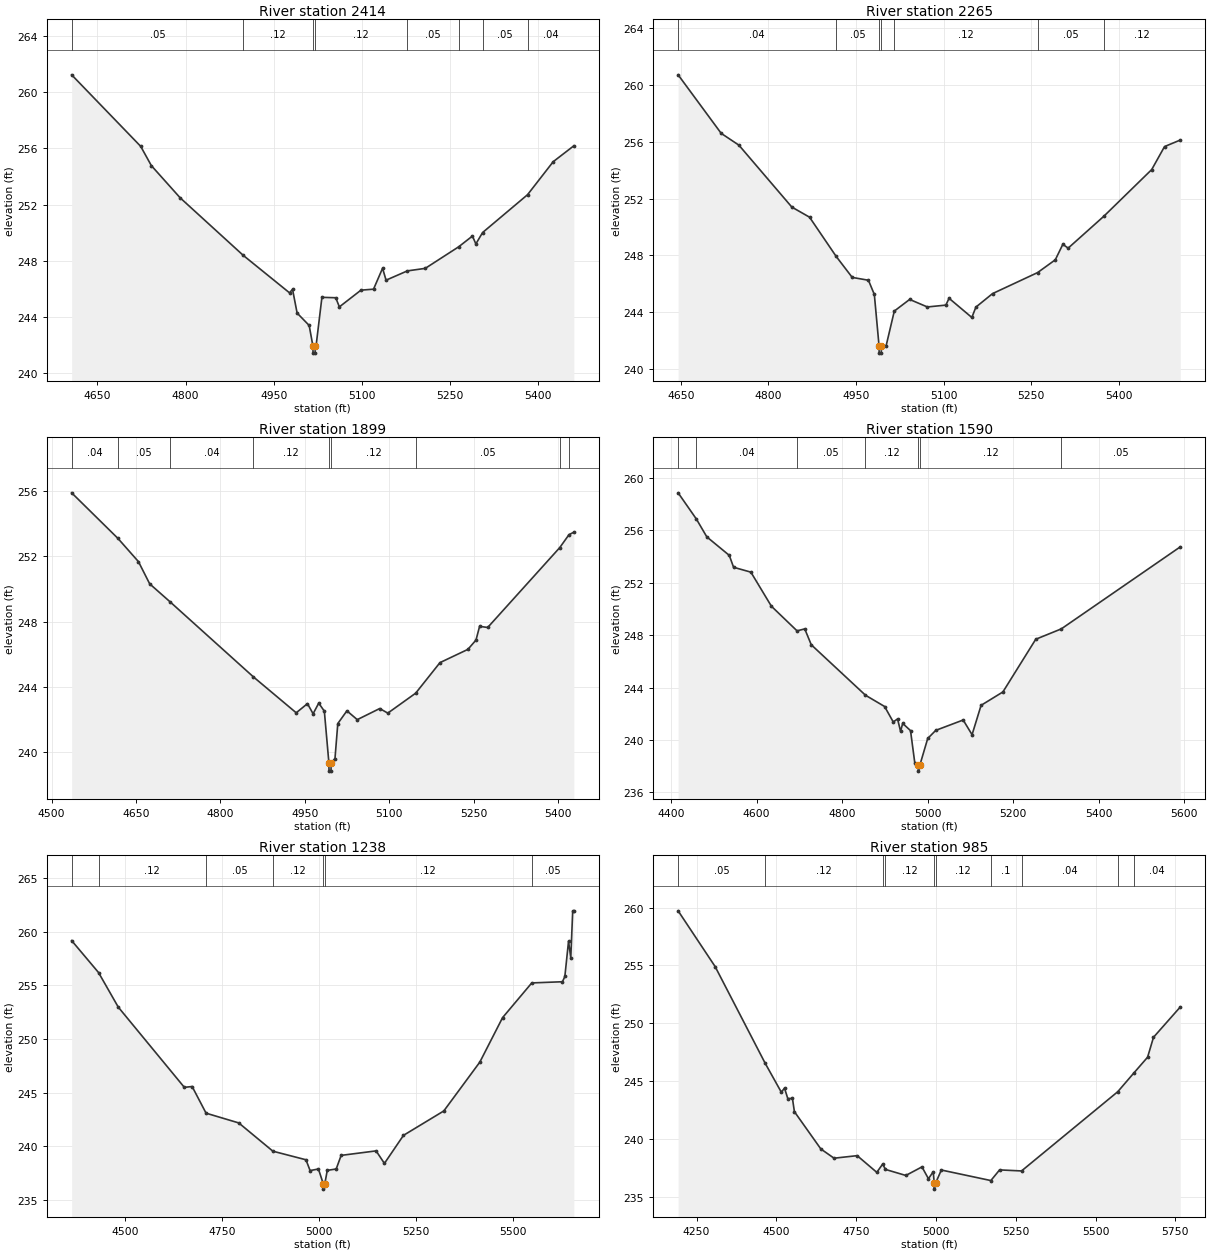
Type RM Length L Ch R = 1,2414,149,149,149
BEGIN DESCRIPTION:
Mapping XS 0129b5da
END DESCRIPTION:
XS GIS Cut Line= 3
      2501140.20     13549619.45      2501546.41     13549530.92
      2501920.70     13549302.18
#Sta/Elev= 30
  4606.2  261.23  4723.7  256.14  4741.8  254.77  4790.8  252.48  4898.3  248.38
  4976.9  245.72  4982.0  245.97  4989.8  244.28  5010.3  243.40  5016.7  241.93
  5016.9  241.43  5020.4  241.43  5020.7  241.93  5022.0  241.93  5032.0  245.40
  5055.5  245.37  5061.7  244.72  5098.4  245.91  5119.8  245.98  5135.2  247.47
  5141.1  246.62  5177.3  247.28  5207.8  247.46  5264.5  248.99  5288.1  249.76
  5293.9  249.20  5305.4  250.01  5381.8  252.70  5425.5  255.05  5460.6  256.18
#Mann=8,-1,0
  4606.2    0.05       0  4898.3    0.12       0  5016.7    0.05       0
  5020.7    0.12       0  5177.3    0.05       0  5264.5    0.12       0
  5305.4    0.05       0  5381.8    0.04       0
Bank Sta=5016.7,5020.7
Exp/Cntr=0.3,0.1

Type RM Length L Ch R = 1,2265,366,366,366
BEGIN DESCRIPTION:
Mapping XS 0b392466
END DESCRIPTION:
XS GIS Cut Line= 3
      2501181.84     13549728.83      2501614.12     13549671.54
      2501999.53     13549494.46
#Sta/Elev= 30
  4645.2  260.71  4719.0  256.59  4749.3  255.76  4840.0  251.40  4870.3  250.69
  4915.9  247.93  4943.4  246.45  4971.2  246.25  4981.3  245.25  4989.4  241.62
  4989.6  241.12  4993.1  241.12  4993.4  241.62  5001.4  241.62  5015.5  244.08
  5041.8  244.90  5072.1  244.37  5103.8  244.50  5109.3  244.98  5148.3  243.63
  5155.3  244.36  5183.8  245.31  5261.0  246.79  5291.3  247.69  5304.2  248.78
  5313.3  248.51  5374.3  250.75  5456.4  254.04  5478.4  255.66  5505.4  256.12
#Mann=7,-1,0
  4645.2    0.04       0  4915.9    0.05       0  4989.4    0.05       0
  4993.4    0.05       0  5015.5    0.12       0  5261.0    0.05       0
  5374.3    0.12       0
Bank Sta=4989.4,4993.4
Exp/Cntr=0.3,0.1

Type RM Length L Ch R = 1,1899,309,309,309
BEGIN DESCRIPTION:
Mapping XS 390a251b
END DESCRIPTION:
XS GIS Cut Line= 3
      2501296.44     13549984.04      2501806.83     13549958.00
      2502046.39     13549661.16
#Sta/Elev= 30
  4535.8  255.89  4618.1  253.10  4654.5  251.68  4674.5  250.32  4710.4  249.23
  4858.7  244.63  4934.9  242.43  4954.9  242.99  4964.9  242.37  4974.9  243.02
  4984.9  242.53  4993.0  239.36  4993.2  238.86  4996.7  238.86  4997.0  239.36
  5003.8  239.63  5008.8  241.77  5025.0  242.55  5043.4  242.01  5083.3  242.69
  5097.7  242.41  5147.2  243.63  5190.4  245.50  5240.0  246.31  5254.4  246.88
  5260.8  247.72  5275.2  247.65  5403.3  252.54  5419.7  253.33  5428.3  253.48
#Mann=9,-1,0
  4535.8    0.04       0  4618.1    0.05       0  4710.4    0.04       0
  4858.7    0.12       0  4993.0    0.05       0  4997.0    0.12       0
  5147.2    0.05       0  5403.3    0.12       0  5419.7    0.05       0
Bank Sta=4993,4997
Exp/Cntr=0.3,0.1

Type RM Length L Ch R = 1,1590,352,352,352
BEGIN DESCRIPTION:
Mapping XS e60881cd
END DESCRIPTION:
XS GIS Cut Line= 3
      2501296.43     13550150.71      2501879.74     13550228.83
      2502244.34     13549770.48
#Sta/Elev= 30
  4416.3  258.86  4459.0  256.86  4483.4  255.50  4535.9  254.09  4546.0  253.18
  4586.4  252.81  4634.4  250.21  4694.4  248.33  4712.4  248.48  4727.6  247.27
  4854.4  243.42  4899.1  242.56  4919.3  241.38  4929.4  241.61  4936.4  240.67
  4941.4  241.27  4959.7  240.72  4969.8  238.23  4977.9  238.13  4978.1  237.63
  4981.9  238.13  4999.9  240.12  5018.7  240.74  5082.8  241.53  5103.6  240.41
  5124.7  242.65  5175.7  243.67  5252.5  247.69  5312.2  248.48  5590.5  254.74
#Mann=7,-1,0
  4416.3    0.05       0  4459.0    0.04       0  4694.4    0.05       0
  4854.4    0.12       0  4977.9    0.05       0  4981.9    0.12       0
  5312.2    0.05       0
Bank Sta=4977.9,4981.9
Exp/Cntr=0.3,0.1

Type RM Length L Ch R = 1,1238,253,253,253
BEGIN DESCRIPTION:
TRIB 4 TO FIVEMILE CREEK 2.0
END DESCRIPTION:
XS GIS Cut Line= 3
      2501375.01     13550525.00      2501975.00     13550575.00
      2502325.00     13549974.99
#Sta/Elev= 30
  4361.1  259.18  4430.5  256.20  4481.5  252.97  4652.1  245.48  4672.2  245.56
  4708.2  243.07  4792.6  242.16  4880.8  239.52  4966.1  238.72  4976.8  237.71
  4998.3  237.86  5010.8  236.48  5011.0  235.98  5014.8  236.48  5021.1  237.73
  5044.2  237.86  5057.0  239.13  5147.2  239.55  5168.7  238.38  5217.9  241.00
  5322.1  243.28  5415.1  247.84  5473.8  251.99  5549.2  255.23  5628.4  255.34
  5634.6  255.83  5644.1  259.12  5649.9  257.59  5654.9  261.96  5657.8  261.96
#Mann=7,-1,0
  4361.1    0.05       0  4430.5    0.12       0  4708.2    0.05       0
  4880.8    0.12       0  5010.8    0.05       0  5014.8    0.12       0
  5549.2    0.05       0
Bank Sta=5010.8,5014.8
Exp/Cntr=0.3,0.1

Type RM Length L Ch R = 1,985,261,261,261
BEGIN DESCRIPTION:
Mapping XS 0deb54b1
END DESCRIPTION:
XS GIS Cut Line= 4
      2501323.00     13550637.80      2501894.94     13550790.57
      2502326.75     13550726.17      2502448.01     13550195.11
#Sta/Elev= 30
  4192.1  259.72  4308.0  254.91  4465.0  246.55  4515.4  244.06  4525.4  244.41
  4535.7  243.51  4550.3  243.52  4556.4  242.38  4639.2  239.16  4680.6  238.36
  4753.1  238.58  4814.5  237.14  4832.9  237.85  4841.8  237.39  4905.5  236.87
  4956.0  237.61  4976.3  236.59  4991.4  237.19  4994.5  236.19  4994.7  235.69
  4998.5  236.19  5016.7  237.34  5171.9  236.43  5199.2  237.35  5268.0  237.26
  5569.4  244.10  5619.0  245.69  5662.9  247.08  5681.4  248.80  5765.4  251.42
#Mann=10,-1,0
  4192.1    0.05       0  4465.0    0.12       0  4832.9    0.05       0
  4841.8    0.12       0  4994.5    0.05       0  4998.5    0.12       0
  5171.9     0.1       0  5268.0    0.04       0  5569.4    0.05       0
  5619.0    0.04       0
Bank Sta=4994.5,4998.5
Exp/Cntr=0.3,0.1

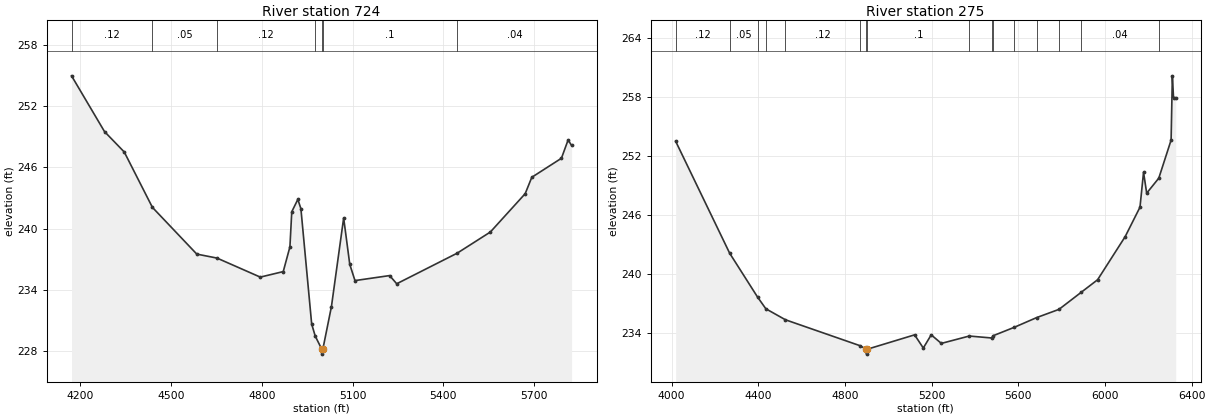
Type RM Length L Ch R = 1,724,449,449,449
BEGIN DESCRIPTION:
Mapping XS b9d7036b
END DESCRIPTION:
XS GIS Cut Line= 4
      2501384.96     13550742.80      2502030.29     13551022.44
      2502264.22     13550990.18      2502546.55     13550334.10
#Sta/Elev= 30
  4170.5  254.94  4279.5  249.49  4344.9  247.49  4437.9  242.08  4584.7  237.51
  4651.6  237.12  4794.7  235.26  4870.6  235.80  4892.7  238.22  4898.8  241.65
  4918.9  242.86  4929.0  241.95  4964.6  230.68  4976.3  229.50  4997.7  228.23
  4997.9  227.73  5001.7  228.23  5030.0  232.38  5070.4  241.04  5090.6  236.51
  5107.8  234.92  5222.4  235.41  5245.9  234.61  5445.8  237.60  5555.6  239.67
  5670.8  243.42  5692.6  245.02  5790.6  246.88  5812.7  248.67  5824.2  248.13
#Mann=7,-1,0
  4170.5    0.12       0  4437.9    0.05       0  4651.6    0.12       0
  4976.3     0.1       0  4997.7    0.05       0  5001.7     0.1       0
  5445.8    0.04       0
Bank Sta=4997.7,5001.7
Exp/Cntr=0.3,0.1

Type RM Length L Ch R = 1,275,0,0,0
BEGIN DESCRIPTION:
TRIB 4 TO FIVEMILE CREEK 1.0
END DESCRIPTION:
XS GIS Cut Line= 4
      2501324.97     13550874.97      2501885.09     13551377.38
      2502293.80     13551355.87      2502674.99     13550275.02
#Sta/Elev= 30
  4018.6  253.47  4267.8  242.09  4396.6  237.63  4434.9  236.44  4525.5  235.32
  4869.1  232.69  4899.1  232.33  4899.4  231.83  4903.1  232.33  5121.4  233.79
  5161.5  232.45  5198.0  233.79  5244.8  232.92  5373.8  233.67  5477.3  233.47
  5483.8  233.70  5580.7  234.55  5684.2  235.54  5787.7  236.38  5891.2  238.13
  5965.9  239.39  6093.1  243.77  6161.6  246.77  6178.0  250.32  6192.5  248.19
  6248.4  249.72  6305.2  253.59  6311.0  260.12  6316.3  257.91  6326.4  257.89
#Mann=16,-1,0
  4018.6    0.12       0  4267.8    0.05       0  4396.6    0.12       0
  4434.9    0.05       0  4525.5    0.12       0  4869.1     0.1       0
  4899.1    0.05       0  4903.1     0.1       0  5373.8    0.05       0
  5477.3     0.1       0  5483.8    0.05       0  5580.7    0.12       0
  5684.2    0.05       0  5787.7    0.12       0  5891.2    0.04       0
  6248.4    0.05       0
Bank Sta=4899.1,4903.1
Exp/Cntr=0.3,0.1

Chan Stop Cuts=-1