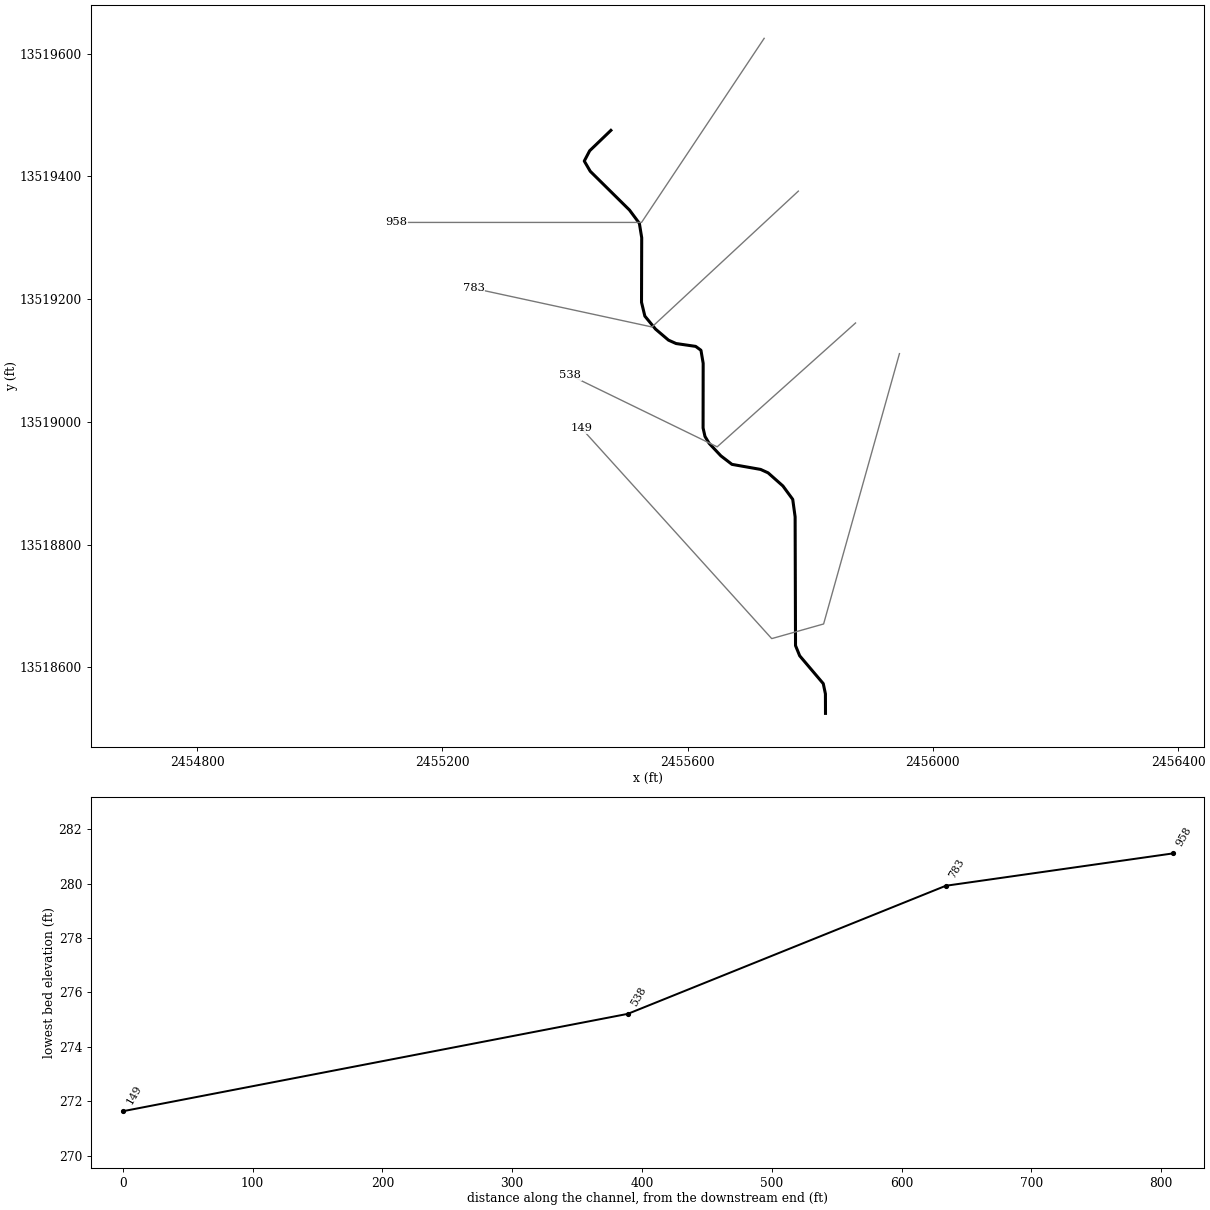
--- TRIB 4 TO HOOSIER CREEK.prj (project) ---

Proj Title=TRIB 4 TO HOOSIER CREEK Base Level Engineering
Current Plan=p01
Default Exp/Contr=0.3,0.1
English Units
Geom File=g01
Flow File=f01
Plan File=p01
Y Axis Title=Elevation
X Axis Title(PF)=Main Channel Distance
X Axis Title(XS)=Station
BEGIN DESCRIPTION:
TRIB 4 TO HOOSIER CREEK
END DESCRIPTION:
DSS Export Rating Curves= 0
DSS Export Rating Curve Sorted= 0
DSS Export Volume Flow Curves= 0
DXF OffsetX= 0
DXF OffsetY= 0
DXF ScaleX= 1
DXF ScaleY= 10

--- TRIB 4 TO HOOSIER CREEK.p01 (plan) ---

Plan Title=Multiple Run
Short Identifier=Multiple
Geom File=g01
Flow File=f01
Subcritical Flow
K Sum by GR= 0
Std Step Tol= 0.01
Critical Tol= 0.01
Num of Std Step Trials= 20
Max Error Tol= 0.3
Flow Tol Ratio= 0.001
Split Flow NTrial= 30
Split Flow Tol= 0.02
Split Flow Ratio= 0.02
Log Output Level= 0
Friction Slope Method= 1
Unsteady Friction Slope Method= 2
Unsteady Bridges Friction Slope Method= 1
Parabolic Critical Depth
Global Vel Dist=  1 , 1 , 1
Global Log Level= 0
CheckData=True
Encroach Param= -1, 0, 0, 0
BEGIN DESCRIPTION:
Multiple Run
END DESCRIPTION:

--- TRIB 4 TO HOOSIER CREEK.f01 (steady flow) ---

Flow Title=Multiple
Number of Profiles=7
Profile Names=10-year,25-year,50-year,1pct_min,100-year,1pct_plu,500-year
River Rch & RM= TRIB 4 TO HOOSIE,Reach-1,958
     229     345     443     276     551    1099     842
Boundary for River Rch & Prof#=TRIB 4 TO HOOSIE,Reach-1,1
Up Type=0
Dn Type=3
Dn Slope=0.005
Boundary for River Rch & Prof#=TRIB 4 TO HOOSIE,Reach-1,2
Up Type=0
Dn Type=3
Dn Slope=0.005
Boundary for River Rch & Prof#=TRIB 4 TO HOOSIE,Reach-1,3
Up Type=0
Dn Type=3
Dn Slope=0.005
Boundary for River Rch & Prof#=TRIB 4 TO HOOSIE,Reach-1,4
Up Type=0
Dn Type=3
Dn Slope=0.005
Boundary for River Rch & Prof#=TRIB 4 TO HOOSIE,Reach-1,5
Up Type=0
Dn Type=3
Dn Slope=0.005
Boundary for River Rch & Prof#=TRIB 4 TO HOOSIE,Reach-1,6
Up Type=0
Dn Type=3
Dn Slope=0.005
Boundary for River Rch & Prof#=TRIB 4 TO HOOSIE,Reach-1,7
Up Type=0
Dn Type=3
Dn Slope=0.005

--- TRIB 4 TO HOOSIER CREEK.g01 (geometry) ---

Geom Title=Existing Conditions
Program Version=4.10

River Reach=TRIB 4 TO HOOSIE,Reach-1
Reach XY= 30
        2455475.       13519475.       2455440.4     13519441.78
      2455431.59     13519425.01      2455441.33     13519408.35
      2455505.33     13519345.17      2455521.44     13519323.53
      2455525.26     13519300.11      2455524.95     13519194.89
       2455530.4     13519172.32      2455547.84     13519151.15
      2455568.97     13519133.17      2455581.32     13519127.65
      2455613.26       13519123.      2455621.89     13519116.68
       2455625.5     13519095.42      2455625.35     13518990.05
      2455628.46     13518976.26      2455635.35     13518964.89
      2455654.43     13518944.59      2455672.45     13518930.75
      2455719.12     13518922.53      2455731.36     13518916.97
      2455755.55     13518895.55      2455771.55     13518873.75
      2455775.46     13518845.25      2455776.12     13518635.46
      2455782.89     13518618.84      2455821.35     13518573.49
      2455824.88      13518556.8        2455825.       13518525.

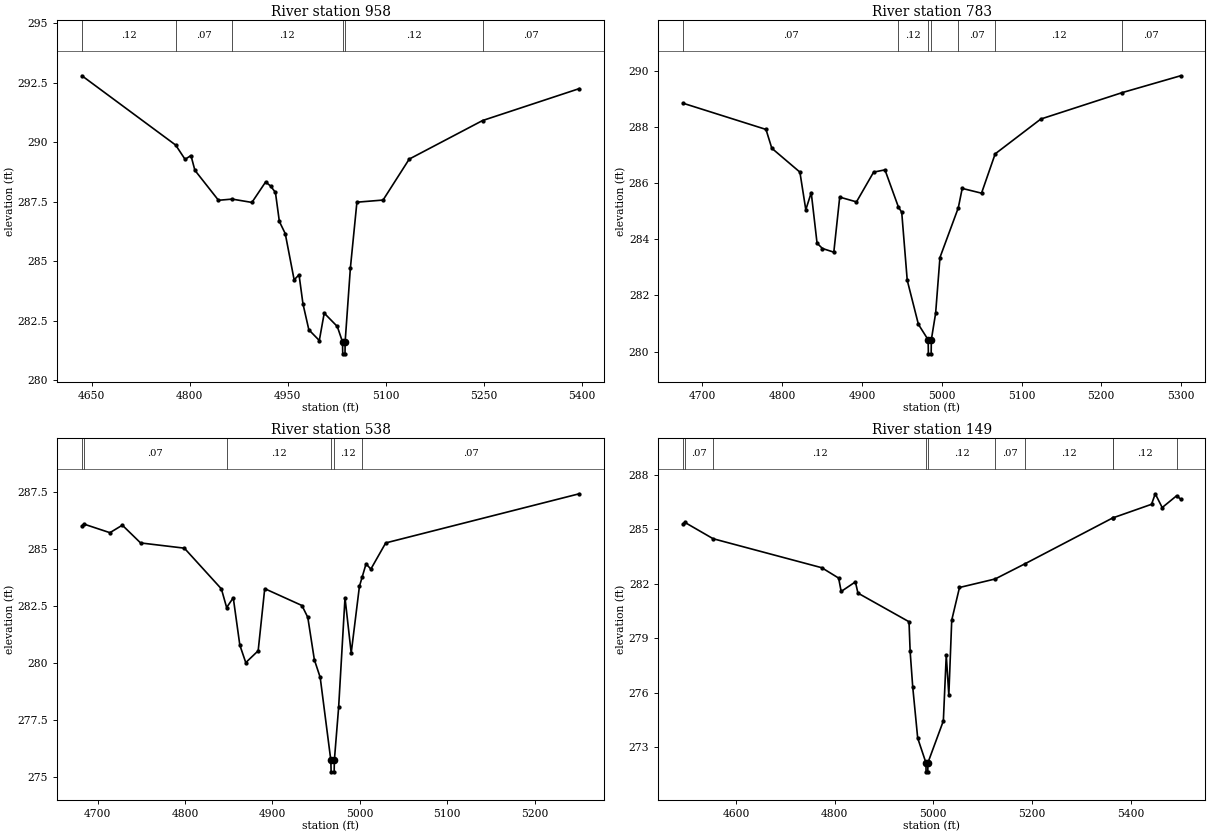
Type RM Length L Ch R = 1 ,958     ,175,175,175
BEGIN DESCRIPTION:
TRIB 4 TO HOOSIER CREEK 2.0
END DESCRIPTION:
XS GIS Cut Line= 3
      2455724.98     13519624.97        2455525.       13519325.
      2455125.02       13519325.
#Sta/Elev= 30
  4635.2  292.79  4778.5  289.88  4792.9  289.28  4801.9  289.44  4807.9  288.82
    4844  287.56  4864.9  287.61  4895.1  287.47  4916.1  288.33  4923.6  288.16
  4931.1  287.89  4937.1  286.67  4946.1  286.16  4959.7  284.22  4967.2  284.43
  4973.2  283.21  4982.2  282.12  4998.2  281.67  5005.7  282.82  5025.7  282.26
  5033.7  281.61    5034  281.11  5037.5  281.11  5037.7  281.61  5045.7  284.71
  5055.7  287.48  5095.7  287.57  5135.7  289.29  5247.9  290.91  5395.7  292.25
#Mann= 6 ,-1 , 0
  4635.2     .12       0  4778.5     .07       0  4864.9     .12       0
  5033.7     .05       0  5037.7     .12       0  5247.9     .07       0
Bank Sta=5033.7,5037.7
XS Rating Curve= 0 ,0
Exp/Cntr=0.3,0.1

Type RM Length L Ch R = 1 ,783     ,245,245,245
BEGIN DESCRIPTION:
Mapping XS bffe2fc7
END DESCRIPTION:
XS GIS Cut Line= 3
      2455780.72     13519376.01      2455541.97     13519154.63
       2455251.2     13519217.56
#Sta/Elev= 30
  4676.2  288.84  4779.8  287.91  4787.1  287.24  4822.3  286.39  4829.7  285.05
  4836.5  285.66  4843.8  283.86  4850.6  283.67  4864.8  283.54  4872.2   285.5
  4893.2  285.33  4914.7  286.39  4928.9  286.47  4945.7  285.15  4949.9  284.96
  4956.8  282.54  4970.8  280.97    4983  280.42  4983.3  279.92  4986.8  279.92
    4987  280.42  4992.4  281.37  4997.8  283.35  5020.8  285.12  5025.7  285.81
  5049.9  285.64    5067  287.04  5124.2  288.28  5226.1  289.22  5299.3  289.82
#Mann= 7 ,-1 , 0
  4676.2     .07       0  4945.7     .12       0    4983     .05       0
    4987     .12       0  5020.8     .07       0    5067     .12       0
  5226.1     .07       0
Bank Sta=4983,4987
XS Rating Curve= 0 ,0
Exp/Cntr=0.3,0.1

Type RM Length L Ch R = 1 ,538     ,389,389,389
BEGIN DESCRIPTION:
Mapping XS 5d27ed33
END DESCRIPTION:
XS GIS Cut Line= 3
        2455874.     13519161.14      2455648.31     13518959.32
      2455408.73     13519075.87
#Sta/Elev= 30
  4681.9  286.02    4684   286.1  4713.9  285.72  4728.1  286.05    4749  285.27
  4799.1  285.04  4841.5  283.25  4847.5  282.43  4855.1  282.86  4862.6  280.78
  4869.4  280.01  4883.6  280.53  4891.1  283.26  4933.7  282.52  4940.4     282
  4947.9  280.14  4954.6  279.36  4966.8  275.71  4967.1  275.21  4970.6  275.21
  4970.8  275.71  4975.7  278.04    4983  282.86  4990.1  280.43  4999.5  283.36
  5002.8  283.79  5007.1  284.35  5012.6  284.12  5029.6  285.27  5251.1  287.43
#Mann= 6 ,-1 , 0
  4681.9     .12       0    4684     .07       0  4847.5     .12       0
  4966.8     .05       0  4970.8     .12       0  5002.8     .07       0
Bank Sta=4966.8,4970.8
XS Rating Curve= 0 ,0
Exp/Cntr=0.3,0.1

Type RM Length L Ch R = 1 ,149     ,0,0,0
BEGIN DESCRIPTION:
TRIB 4 TO HOOSIER CREEK 1.0
END DESCRIPTION:
XS GIS Cut Line= 4
      2455945.61      13519111.2      2455821.92     13518670.69
      2455737.29     13518646.82      2455426.99     13518989.67
#Sta/Elev= 30
  4493.3  285.33  4496.5  285.39  4553.8  284.49    4774  282.89  4808.1  282.32
  4813.3  281.58  4842.1  282.11  4847.3  281.49  4950.8  279.91  4953.1  278.27
  4958.3  276.32  4968.4  273.49  4985.1  272.13  4985.4  271.63  4988.9  271.63
  4989.1  272.13  5020.4  274.44  5026.3  278.07  5031.5  275.86  5037.4     280
  5053.1   281.8  5125.4  282.27    5186  283.11  5363.8  285.64    5364  285.64
  5442.4  286.39  5449.9  286.97    5464  286.21  5493.2  286.86  5501.2  286.68
#Mann= 10 ,-1 , 0
  4493.3     .12       0  4496.5     .07       0  4553.8     .12       0
  4985.1     .05       0  4989.1     .12       0  5125.4     .07       0
    5186     .12       0  5363.8     .07       0    5364     .12       0
  5493.2     .07       0
Bank Sta=4985.1,4989.1
XS Rating Curve= 0 ,0
Exp/Cntr=0.3,0.1

Chan Stop Cuts=-1
Use User Specified Reach Order=0
Composite Channel Slope=5