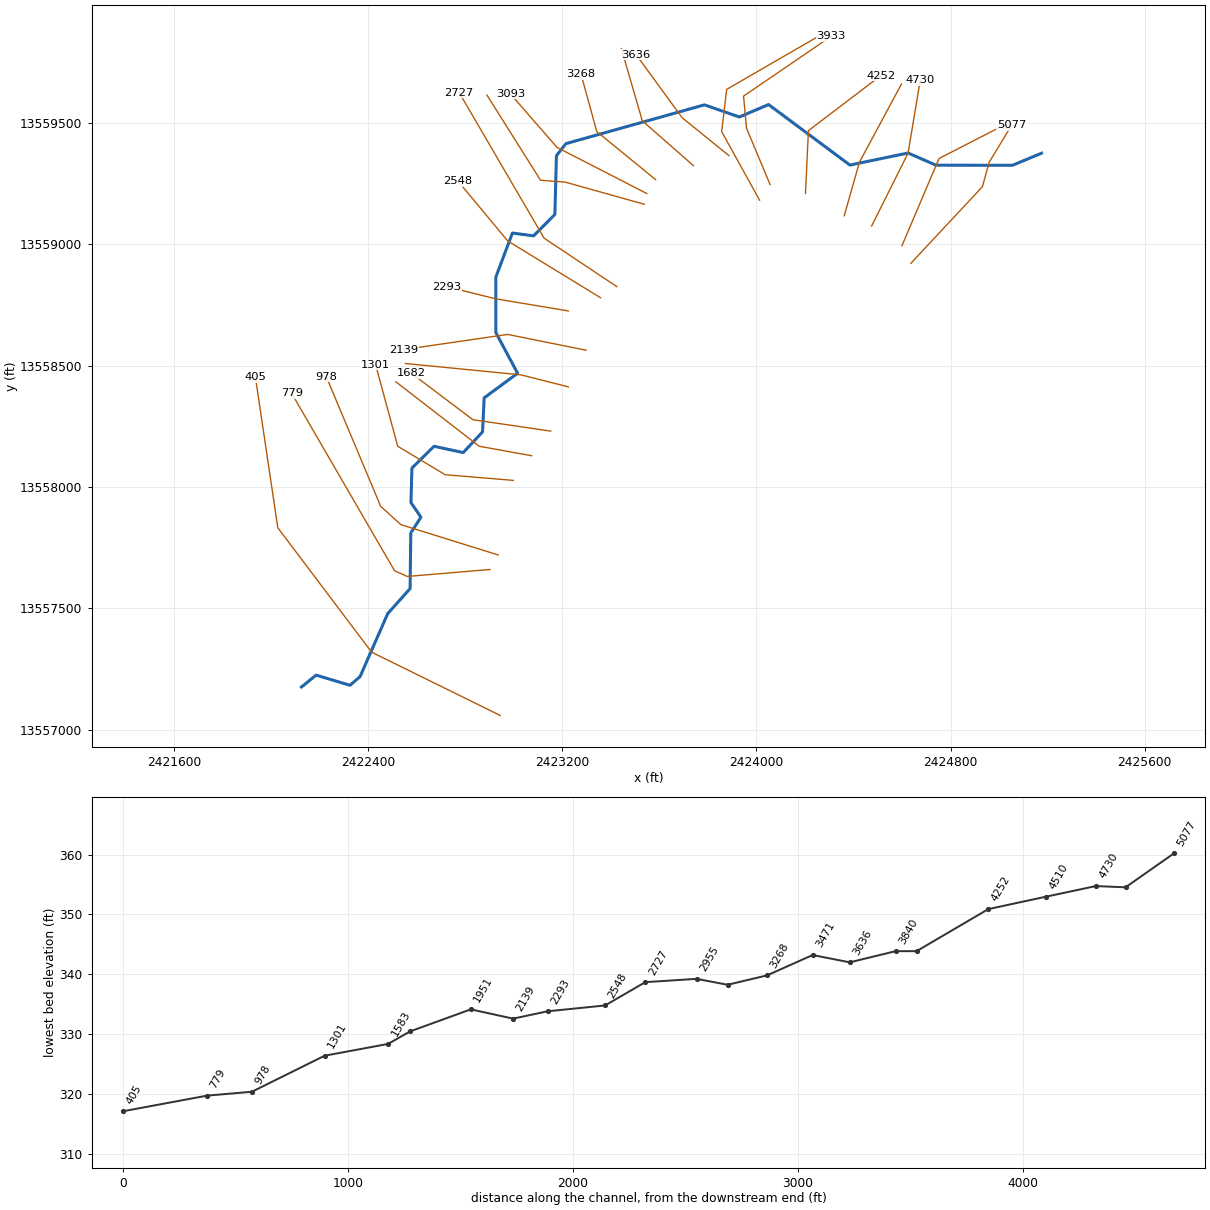
--- TRIB 4 TO SALT CREEK.prj (project) ---

Proj Title=TRIB 4 TO SALT CREEK Base Level Engineering
Current Plan=p01
Default Exp/Contr=0.3,0.1
English Units
Geom File=g01
Flow File=f01
Plan File=p01
BEGIN DESCRIPTION:
TRIB 4 TO SALT CREEK
END DESCRIPTION:

--- TRIB 4 TO SALT CREEK.p01 (plan) ---

Plan Title=Multiple Run
Short Identifier=Multiple
Geom File=g01
Flow File=f01
Subcritical Flow
K Sum by GR= 0
Std Step Tol= 0.01
Critical Tol= 0.01
Num of Std Step Trials= 20
Max Error Tol= 0.3
Flow Tol Ratio= 0.001
Split Flow NTrial= 30
Split Flow Tol= 0.02
Split Flow Ratio= 0.02
Log Output Level= 0
Friction Slope Method= 1
Unsteady Friction Slope Method= 2
Unsteady Bridges Friction Slope Method= 1
Parabolic Critical Depth
Global Vel Dist=  1 , 1 , 1
Global Log Level= 0
CheckData=True
Encroach Param= -1, 0, 0, 0
BEGIN DESCRIPTION:
Multiple Run
END DESCRIPTION:

--- TRIB 4 TO SALT CREEK.f01 (steady flow) ---

Flow Title=Multiple
Number of Profiles=7
Profile Names=10-year,25-year,50-year,1pct_min,100-year,1pct_plu,500-year
River Rch & RM= TRIB 4 TO SALT C,Reach-1,5077
     514     830    1116     728    1453    2900    2439
River Rch & RM= TRIB 4 TO SALT C,Reach-1,3636
     570     923    1243     812    1620    3233    2726
Boundary for River Rch & Prof#=TRIB 4 TO SALT C,Reach-1,1
Up Type=0
Dn Type=3
Dn Slope=0.005
Boundary for River Rch & Prof#=TRIB 4 TO SALT C,Reach-1,2
Up Type=0
Dn Type=3
Dn Slope=0.005
Boundary for River Rch & Prof#=TRIB 4 TO SALT C,Reach-1,3
Up Type=0
Dn Type=3
Dn Slope=0.005
Boundary for River Rch & Prof#=TRIB 4 TO SALT C,Reach-1,4
Up Type=0
Dn Type=3
Dn Slope=0.005
Boundary for River Rch & Prof#=TRIB 4 TO SALT C,Reach-1,5
Up Type=0
Dn Type=3
Dn Slope=0.005
Boundary for River Rch & Prof#=TRIB 4 TO SALT C,Reach-1,6
Up Type=0
Dn Type=3
Dn Slope=0.005
Boundary for River Rch & Prof#=TRIB 4 TO SALT C,Reach-1,7
Up Type=0
Dn Type=3
Dn Slope=0.005

--- TRIB 4 TO SALT CREEK.g01 (geometry) ---

Geom Title=Existing Conditions

River Reach=TRIB 4 TO SALT C,Reach-1
Reach XY= 30
      2425175.00     13559375.00      2425054.99     13559325.02
      2424740.22     13559325.52      2424625.00     13559375.82
      2424385.44     13559326.04      2424050.04     13559575.49
      2423930.03     13559524.20      2423785.69     13559574.23
      2423214.94     13559414.39      2423175.99     13559364.72
      2423169.54     13559122.52      2423081.68     13559034.30
      2422994.63     13559046.05      2422926.22     13558864.50
      2422926.20     13558635.50      2423015.90     13558468.25
      2422878.08     13558366.69      2422871.46     13558226.46
      2422791.71     13558141.21      2422671.58     13558167.19
      2422580.45     13558077.48      2422576.37     13557935.44
      2422617.44     13557875.00      2422575.66     13557809.84
      2422572.93     13557580.86      2422480.54     13557477.42
      2422366.85     13557218.31      2422325.31     13557182.23
      2422185.46     13557224.18      2422125.00     13557175.00

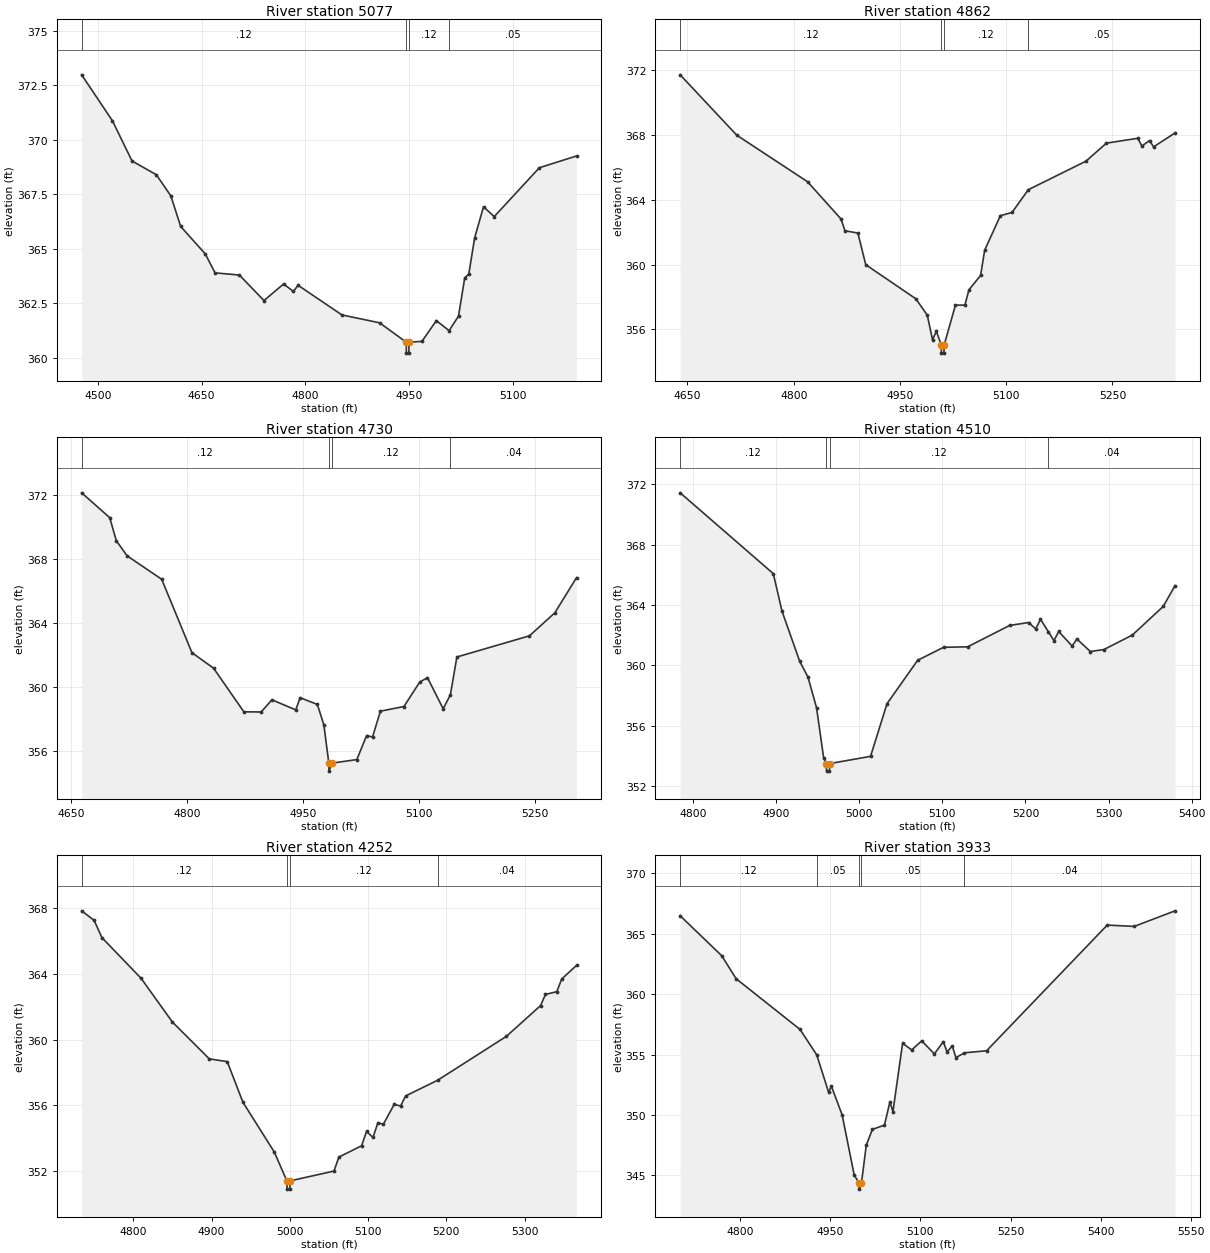
Type RM Length L Ch R = 1,5077,215,215,215
BEGIN DESCRIPTION:
Mapping XS c194a620
END DESCRIPTION:
XS GIS Cut Line= 4
      2424636.27     13558920.93      2424931.42     13559236.91
      2424959.20     13559337.60      2425052.29     13559491.03
#Sta/Elev= 30
  4476.3  372.97  4520.9  370.86  4549.2  369.02  4584.4  368.39  4605.4  367.42
  4619.6  366.02  4655.2  364.76  4669.4  363.89  4704.6  363.79  4740.2  362.62
  4768.6  363.38  4782.7  363.04  4789.6  363.32  4853.1  361.96  4907.6  361.60
  4946.2  360.71  4946.4  360.21  4949.9  360.21  4950.2  360.71  4968.9  360.75
  4989.7  361.70  5008.2  361.24  5021.8  361.91  5030.8  363.66  5036.7  363.84
  5045.2  365.50  5058.0  366.92  5073.5  366.47  5138.8  368.71  5192.6  369.25
#Mann=4,-1,0
  4476.3    0.12       0  4946.2    0.05       0  4950.2    0.12       0
  5008.2    0.05       0
Bank Sta=4946.2,4950.2
Exp/Cntr=0.3,0.1

Type RM Length L Ch R = 1,4862,132,132,132
BEGIN DESCRIPTION:
Mapping XS 85bfc19f
END DESCRIPTION:
XS GIS Cut Line= 3
      2424599.84     13558993.89      2424752.60     13559353.23
      2425026.89     13559493.85
#Sta/Elev= 30
  4639.7  371.69  4719.6  367.97  4819.6  365.10  4866.9  362.80  4872.3  362.08
  4890.6  361.94  4901.7  359.99  4972.4  357.89  4988.6  356.88  4996.0  355.36
  5001.4  355.89  5008.4  355.04  5008.6  354.54  5012.1  354.54  5012.4  355.04
  5028.4  357.50  5041.7  357.50  5047.4  358.44  5063.9  359.33  5069.6  360.88
  5091.8  363.01  5108.3  363.21  5131.2  364.61  5212.7  366.37  5241.5  367.48
  5285.9  367.78  5291.5  367.30  5302.5  367.64  5308.1  367.25  5338.4  368.11
#Mann=4,-1,0
  4639.7    0.12       0  5008.4    0.05       0  5012.4    0.12       0
  5131.2    0.05       0
Bank Sta=5008.4,5012.4
Exp/Cntr=0.3,0.1

Type RM Length L Ch R = 1,4730,220,220,220
BEGIN DESCRIPTION:
TRIB 4_1 TO SALT CREEK 2.0
END DESCRIPTION:
XS GIS Cut Line= 3
      2424475.02     13559075.03      2424625.00     13559375.00
      2424675.00     13559674.99
#Sta/Elev= 30
  4663.8  372.11  4700.1  370.56  4708.5  369.13  4722.5  368.18  4767.2  366.72
  4806.3  362.14  4834.3  361.17  4873.4  358.45  4895.8  358.44  4909.7  359.20
  4940.5  358.57  4946.1  359.33  4968.4  358.91  4976.8  357.64  4983.2  355.25
  4983.4  354.75  4987.2  355.25  5019.4  355.47  5032.1  356.97  5039.7  356.88
  5049.9  358.49  5080.3  358.78  5100.6  360.30  5110.7  360.58  5131.0  358.64
  5140.3  359.51  5148.7  361.87  5242.5  363.19  5275.4  364.63  5303.3  366.82
#Mann=4,-1,0
  4663.8    0.12       0  4983.2    0.05       0  4987.2    0.12       0
  5140.3    0.04       0
Bank Sta=4983.2,4987.2
Exp/Cntr=0.3,0.1

Type RM Length L Ch R = 1,4510,258,258,258
BEGIN DESCRIPTION:
Mapping XS 86374d01
END DESCRIPTION:
XS GIS Cut Line= 3
      2424361.98     13559117.14      2424424.47     13559337.60
      2424597.95     13559660.28
#Sta/Elev= 30
  4784.5  371.44  4896.6  366.08  4907.0  363.60  4928.4  360.26  4938.2  359.24
  4948.6  357.19  4957.2  353.85  4960.4  353.49  4960.6  352.99  4964.1  352.99
  4964.4  353.49  5013.6  353.97  5033.4  357.46  5070.3  360.34  5101.5  361.20
  5130.4  361.23  5181.0  362.65  5203.7  362.84  5212.4  362.42  5218.1  363.06
  5227.7  362.22  5234.3  361.64  5240.0  362.25  5256.2  361.28  5261.9  361.75
  5278.1  360.92  5294.4  361.05  5328.6  362.01  5365.8  363.91  5380.0  365.29
#Mann=4,-1,0
  4784.5    0.12       0  4960.4    0.05       0  4964.4    0.12       0
  5227.7    0.04       0
Bank Sta=4960.4,4964.4
Exp/Cntr=0.3,0.1

Type RM Length L Ch R = 1,4252,319,319,319
BEGIN DESCRIPTION:
Mapping XS aaa3ae15
END DESCRIPTION:
XS GIS Cut Line= 3
      2424202.25     13559209.09      2424214.40     13559467.81
      2424511.53     13559694.11
#Sta/Elev= 30
  4733.9  367.84  4749.8  367.26  4759.8  366.21  4809.9  363.73  4849.9  361.07
  4897.0  358.83  4920.0  358.66  4940.0  356.19  4980.1  353.16  4996.2  351.40
  4996.5  350.90  5000.0  350.90  5000.2  351.40  5056.4  352.00  5062.7  352.85
  5091.7  353.54  5098.0  354.41  5106.3  354.05  5112.6  354.95  5119.4  354.84
  5133.4  356.06  5141.6  355.96  5147.9  356.57  5189.0  357.53  5276.8  360.20
  5320.4  362.07  5326.7  362.75  5341.2  362.92  5347.5  363.69  5366.4  364.52
#Mann=4,-1,0
  4733.9    0.12       0  4996.2    0.05       0  5000.2    0.12       0
  5189.0    0.04       0
Bank Sta=4996.2,5000.2
Exp/Cntr=0.3,0.1

Type RM Length L Ch R = 1,3933,93,93,93
BEGIN DESCRIPTION:
Mapping XS 244a4e7f
END DESCRIPTION:
XS GIS Cut Line= 4
      2424056.41     13559245.61      2423959.20     13559478.23
      2423947.04     13559610.17      2424308.19     13559856.73
#Sta/Elev= 30
  4701.0  366.49  4770.1  363.18  4793.9  361.28  4900.0  357.09  4927.8  354.98
  4947.6  351.88  4952.1  352.40  4970.0  350.01  4990.0  345.05  4998.1  344.37
  4998.3  343.87  5002.1  344.37  5010.1  347.51  5020.2  348.81  5040.3  349.17
  5049.3  351.08  5054.4  350.29  5070.4  355.94  5085.5  355.39  5102.2  356.14
  5123.2  355.06  5138.1  356.08  5144.1  355.23  5153.0  355.71  5159.0  354.75
  5173.1  355.15  5209.9  355.32  5410.3  365.72  5455.1  365.61  5522.9  366.90
#Mann=5,-1,0
  4701.0    0.12       0  4927.8    0.05       0  4998.1    0.05       0
  5002.1    0.05       0  5173.1    0.04       0
Bank Sta=4998.1,5002.1
Exp/Cntr=0.3,0.1

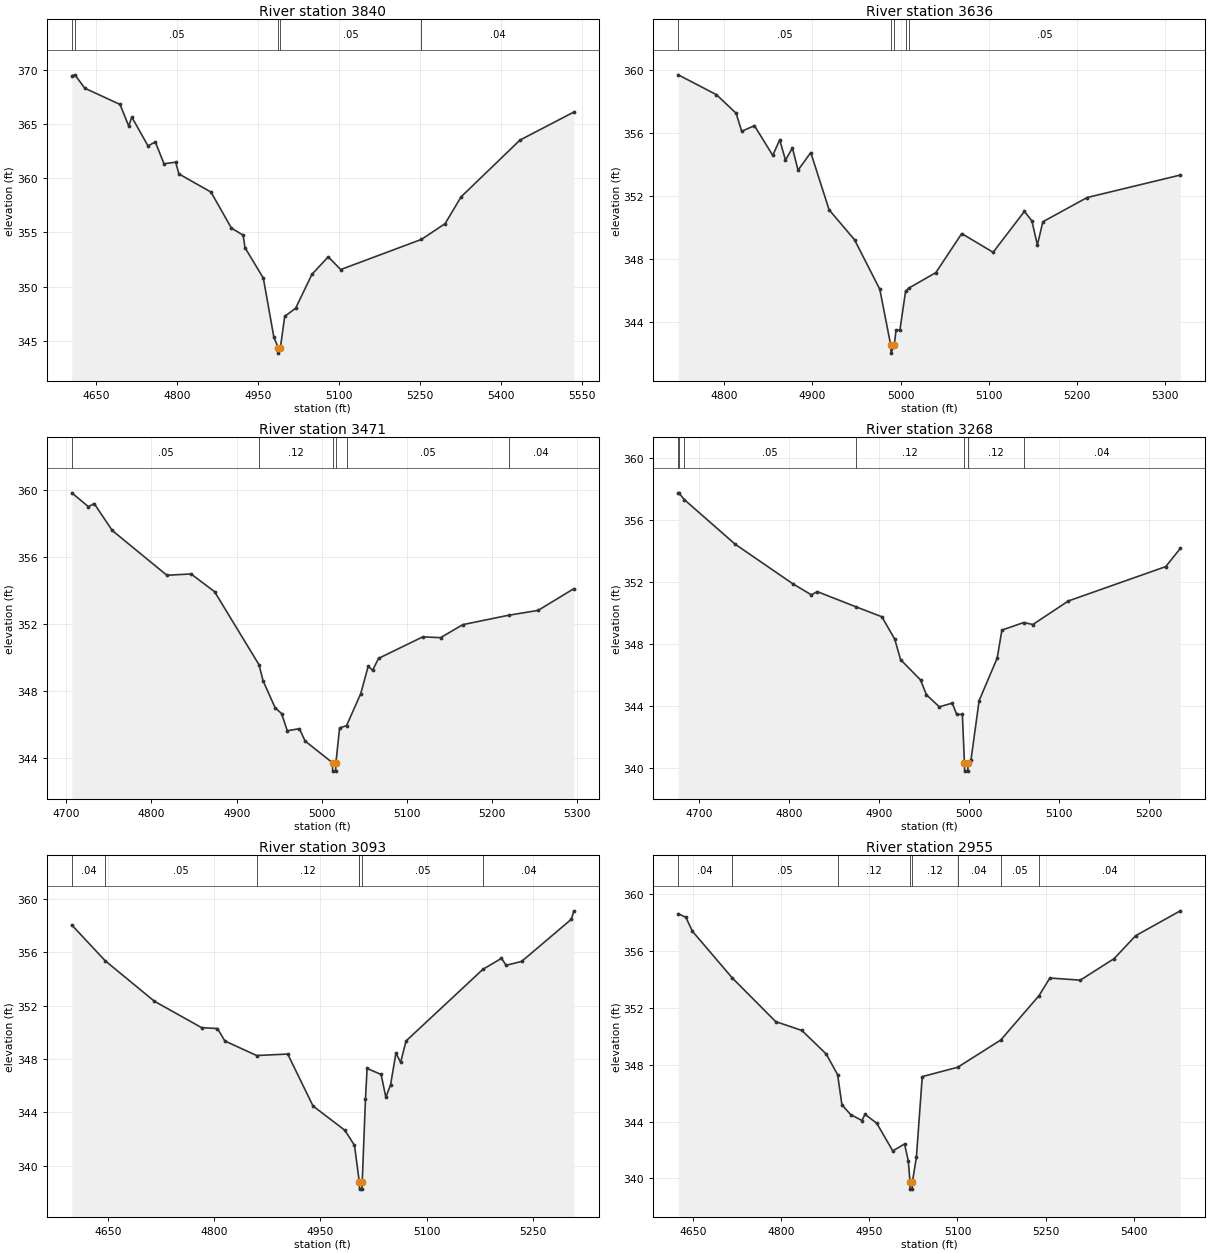
Type RM Length L Ch R = 1,3840,204,204,204
BEGIN DESCRIPTION:
Mapping XS 8cc04327
END DESCRIPTION:
XS GIS Cut Line= 4
      2424013.02     13559181.35      2423856.77     13559464.34
      2423877.60     13559637.95      2424251.32     13559854.22
#Sta/Elev= 30
  4604.7  369.42  4610.5  369.51  4628.8  368.28  4694.1  366.78  4710.2  364.79
  4715.9  365.62  4745.9  362.96  4759.4  363.33  4775.5  361.32  4797.2  361.46
  4803.1  360.38  4862.5  358.71  4900.4  355.39  4922.1  354.74  4925.5  353.59
  4959.5  350.78  4979.0  345.34  4987.1  344.37  4987.3  343.87  4991.1  344.37
  4999.1  347.26  5019.3  348.00  5049.5  351.13  5079.7  352.74  5102.8  351.57
  5252.4  354.35  5296.2  355.80  5325.8  358.27  5434.9  363.50  5534.6  366.08
#Mann=5,-1,0
  4604.7    0.04       0  4610.5    0.05       0  4987.1    0.05       0
  4991.1    0.05       0  5252.4    0.04       0
Bank Sta=4987.1,4991.1
Exp/Cntr=0.3,0.1

Type RM Length L Ch R = 1,3636,165,165,165
BEGIN DESCRIPTION:
Mapping XS a7d31a6b
END DESCRIPTION:
XS GIS Cut Line= 3
      2423886.56     13559365.16      2423693.82     13559521.43
      2423504.39     13559780.91
#Sta/Elev= 30
  4747.9  359.69  4791.2  358.43  4813.5  357.25  4819.9  356.10  4834.3  356.46
  4855.1  354.57  4863.0  355.56  4869.5  354.27  4877.4  355.04  4883.8  353.63
  4898.2  354.75  4919.0  351.11  4947.8  349.21  4976.5  346.06  4988.9  342.50
  4989.2  342.00  4992.9  342.50  4994.9  343.47  4999.3  343.47  5005.8  345.96
  5009.9  346.15  5040.1  347.12  5069.4  349.60  5105.0  348.41  5140.5  351.01
  5149.0  350.40  5155.2  348.87  5161.4  350.35  5211.6  351.89  5317.3  353.32
#Mann=5,-1,0
  4747.9    0.05       0  4988.9    0.05       0  4992.9    0.05       0
  5005.8    0.12       0  5009.9    0.05       0
Bank Sta=4988.9,4992.9
Exp/Cntr=0.3,0.1

Type RM Length L Ch R = 1,3471,203,203,203
BEGIN DESCRIPTION:
Mapping XS a68184f7
END DESCRIPTION:
XS GIS Cut Line= 3
      2423740.69     13559323.51      2423529.75     13559508.41
      2423443.81     13559805.32
#Sta/Elev= 30
  4706.4  359.86  4726.0  359.03  4732.7  359.22  4753.9  357.61  4818.1  354.93
  4846.5  355.01  4874.1  353.95  4926.3  349.58  4931.0  348.63  4945.2  347.01
  4952.8  346.66  4959.5  345.63  4973.7  345.76  4980.4  345.02  5012.6  343.72
  5012.8  343.22  5016.3  343.22  5016.6  343.72  5020.9  345.80  5029.1  345.94
  5045.8  347.86  5054.5  349.49  5059.7  349.25  5066.6  349.96  5118.7  351.25
  5139.5  351.20  5165.7  351.98  5219.3  352.54  5254.0  352.83  5296.0  354.13
#Mann=6,-1,0
  4706.4    0.05       0  4926.3    0.12       0  5012.6    0.05       0
  5016.6    0.12       0  5029.1    0.05       0  5219.3    0.04       0
Bank Sta=5012.6,5016.6
Exp/Cntr=0.3,0.1

Type RM Length L Ch R = 1,3268,175,175,175
BEGIN DESCRIPTION:
Mapping XS 558d63c5
END DESCRIPTION:
XS GIS Cut Line= 3
      2423584.46     13559266.21      2423342.25     13559464.14
      2423277.30     13559700.58
#Sta/Elev= 30
  4676.6  357.74  4677.3  357.74  4683.2  357.31  4739.9  354.43  4803.8  351.89
  4824.6  351.17  4831.1  351.38  4873.7  350.41  4902.9  349.76  4917.2  348.32
  4923.7  347.00  4945.9  345.69  4952.4  344.74  4966.8  343.96  4981.1  344.20
  4986.1  343.47  4992.4  343.47  4994.7  340.32  4994.9  339.82  4998.4  339.82
  4998.7  340.32  5001.9  340.52  5011.0  344.36  5031.1  347.10  5036.3  348.90
  5060.6  349.39  5070.7  349.26  5110.3  350.78  5218.4  352.99  5234.6  354.16
#Mann=7,-1,0
  4676.6    0.05       0  4677.3    0.04       0  4683.2    0.05       0
  4873.7    0.12       0  4994.7    0.05       0  4998.7    0.12       0
  5060.6    0.04       0
Bank Sta=4994.7,4998.7
Exp/Cntr=0.3,0.1

Type RM Length L Ch R = 1,3093,138,138,138
BEGIN DESCRIPTION:
Mapping XS 4fbfa362
END DESCRIPTION:
XS GIS Cut Line= 3
      2423548.01     13559208.92      2423178.19     13559399.04
      2422985.62     13559620.23
#Sta/Elev= 30
  4599.0  358.04  4646.2  355.36  4715.6  352.33  4782.3  350.35  4804.8  350.28
  4815.2  349.35  4860.1  348.26  4904.0  348.37  4939.7  344.48  4984.7  342.66
  4998.3  341.53  5005.1  338.79  5005.2  338.75  5005.4  338.25  5008.9  338.25
  5009.2  338.75  5013.8  345.00  5016.1  347.29  5035.9  346.84  5042.6  345.13
  5049.3  346.08  5056.8  348.44  5063.5  347.75  5071.1  349.35  5179.7  354.72
  5205.9  355.54  5212.5  355.02  5234.4  355.31  5304.6  358.47  5308.1  359.10
#Mann=7,-1,0
  4599.0    0.04       0  4646.2    0.05       0  4860.1    0.12       0
  5005.1    0.05       0  5005.2    0.05       0  5009.2    0.05       0
  5179.7    0.04       0
Bank Sta=5005.2,5009.2
Exp/Cntr=0.3,0.1

Type RM Length L Ch R = 1,2955,228,228,228
BEGIN DESCRIPTION:
Mapping XS 7faffdd8
END DESCRIPTION:
XS GIS Cut Line= 4
      2423537.55     13559164.67      2423212.04     13559255.81
      2423110.48     13559263.62      2422889.57     13559614.48
#Sta/Elev= 30
  4624.8  358.63  4637.8  358.37  4649.0  357.39  4716.9  354.10  4790.7  351.03
  4835.2  350.41  4876.7  348.75  4896.1  347.29  4903.4  345.17  4918.2  344.49
  4937.5  344.07  4942.7  344.51  4962.8  343.87  4989.9  341.93  5010.0  342.42
  5016.3  341.23  5019.3  339.74  5019.5  339.24  5023.0  339.24  5023.3  339.74
  5030.1  341.47  5040.1  347.16  5100.5  347.82  5173.8  349.74  5238.8  352.86
  5257.3  354.10  5309.1  353.95  5366.8  355.47  5403.3  357.08  5479.3  358.83
#Mann=8,-1,0
  4624.8    0.04       0  4716.9    0.05       0  4896.1    0.12       0
  5019.3    0.05       0  5023.3    0.12       0  5100.5    0.04       0
  5173.8    0.05       0  5238.8    0.04       0
Bank Sta=5019.3,5023.3
Exp/Cntr=0.3,0.1

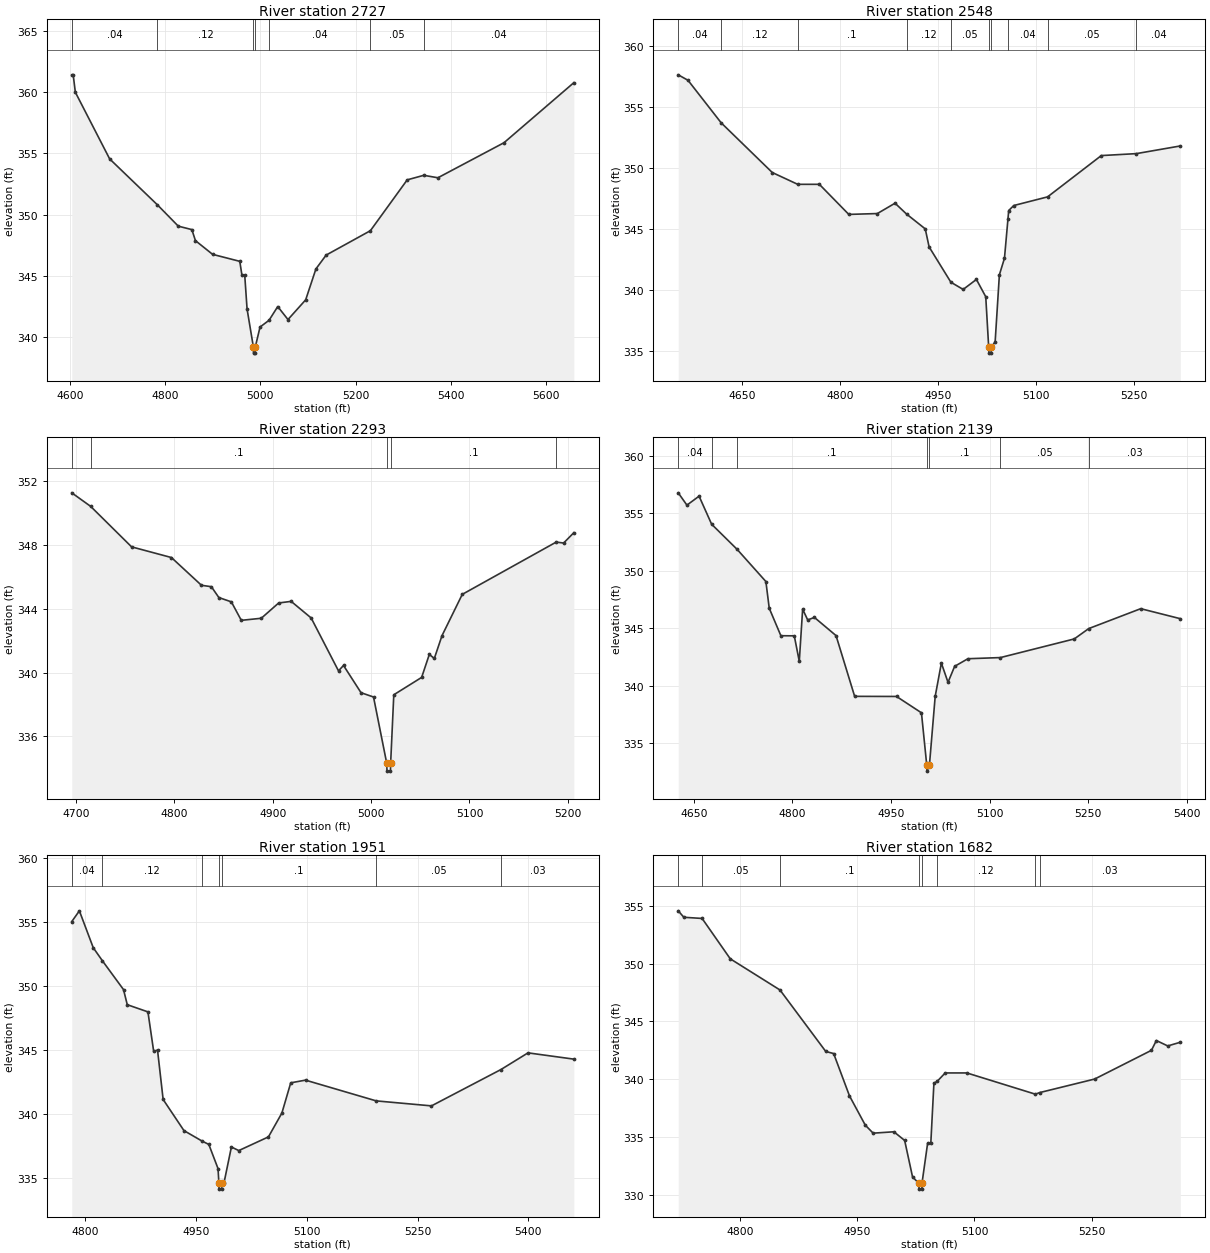
Type RM Length L Ch R = 1,2727,179,179,179
BEGIN DESCRIPTION:
TRIB 4 TO SALT CREEK 6.0
END DESCRIPTION:
XS GIS Cut Line= 3
      2423425.01     13558824.99      2423125.00     13559025.00
      2422774.99     13559625.01
#Sta/Elev= 30
  4603.6  361.40  4606.6  361.40  4611.1  359.98  4683.2  354.54  4783.6  350.79
  4827.5  349.05  4856.0  348.77  4863.5  347.87  4899.6  346.75  4956.7  346.18
  4961.2  345.06  4967.1  345.06  4972.0  342.30  4985.3  339.19  4985.6  338.69
  4989.1  338.69  4989.3  339.19  4999.3  340.82  5018.2  341.37  5036.5  342.49
  5058.0  341.43  5095.2  343.04  5116.7  345.56  5138.2  346.69  5231.2  348.68
  5308.6  352.83  5343.4  353.20  5373.1  353.00  5512.0  355.86  5658.8  360.76
#Mann=7,-1,0
  4603.6    0.04       0  4783.6    0.12       0  4985.3    0.05       0
  4989.3    0.12       0  5018.2    0.04       0  5231.2    0.05       0
  5343.4    0.04       0
Bank Sta=4985.3,4989.3
Exp/Cntr=0.3,0.1

Type RM Length L Ch R = 1,2548,255,255,255
BEGIN DESCRIPTION:
Mapping XS 16ac8e9a
END DESCRIPTION:
XS GIS Cut Line= 3
      2423357.92     13558779.22      2422975.07     13559013.62
      2422770.08     13559260.12
#Sta/Elev= 30
  4552.1  357.64  4567.1  357.19  4617.9  353.70  4696.2  349.62  4735.2  348.65
  4768.4  348.65  4813.5  346.18  4857.3  346.25  4884.4  347.10  4902.0  346.21
  4930.7  344.99  4936.6  343.51  4970.0  340.61  4988.8  340.02  5009.1  340.84
  5023.4  339.42  5027.9  335.29  5028.2  334.79  5031.7  334.79  5031.9  335.29
  5037.8  335.71  5044.3  341.22  5052.1  342.58  5057.5  345.84  5058.6  346.50
  5066.4  346.91  5118.2  347.62  5200.5  351.01  5254.2  351.17  5321.6  351.80
#Mann=10,-1,0
  4552.1    0.04       0  4617.9    0.12       0  4735.2     0.1       0
  4902.0    0.12       0  4970.0    0.05       0  5027.9    0.05       0
  5031.9    0.05       0  5057.5    0.04       0  5118.2    0.05       0
  5254.2    0.04       0
Bank Sta=5027.9,5031.9
Exp/Cntr=0.3,0.1

Type RM Length L Ch R = 1,2293,154,154,154
BEGIN DESCRIPTION:
TRIB 4 TO SALT CREEK 5.0
END DESCRIPTION:
XS GIS Cut Line= 3
      2423224.96     13558725.01      2422925.00     13558775.00
      2422724.95     13558825.01
#Sta/Elev= 30
  4695.8  351.28  4715.0  350.43  4756.6  347.89  4797.1  347.22  4827.6  345.48
  4837.7  345.39  4845.3  344.71  4858.0  344.44  4868.1  343.28  4888.4  343.41
  4906.1  344.37  4918.8  344.47  4939.1  343.43  4966.9  340.11  4972.0  340.45
  4989.8  338.74  5002.5  338.47  5015.9  334.32  5016.2  333.82  5019.7  333.82
  5019.9  334.32  5023.1  338.61  5051.4  339.70  5059.2  341.14  5064.3  340.89
  5072.1  342.32  5092.7  344.91  5188.2  348.19  5195.7  348.13  5206.1  348.78
#Mann=5,-1,0
  4695.8    0.12       0  4715.0     0.1       0  5015.9    0.05       0
  5019.9     0.1       0  5188.2    0.05       0
Bank Sta=5015.9,5019.9
Exp/Cntr=0.3,0.1

Type RM Length L Ch R = 1,2139,188,188,188
BEGIN DESCRIPTION:
Mapping XS 39ca8bd7
END DESCRIPTION:
XS GIS Cut Line= 3
      2423297.98     13558563.10      2422975.07     13558628.20
      2422545.40     13558565.71
#Sta/Elev= 30
  4626.3  356.78  4639.5  355.71  4658.0  356.49  4677.1  354.05  4715.8  351.87
  4759.6  349.07  4764.7  346.75  4782.4  344.36  4802.8  344.35  4810.4  342.13
  4815.5  346.67  4823.2  345.73  4833.4  345.95  4866.3  344.37  4894.6  339.09
  4958.3  339.08  4996.2  337.66  5004.3  333.09  5004.6  332.59  5008.3  333.09
  5017.1  339.09  5026.5  341.98  5036.6  340.31  5046.7  341.70  5066.9  342.36
  5116.3  342.46  5228.6  344.08  5250.6  344.98  5329.7  346.71  5389.9  345.84
#Mann=7,-1,0
  4626.3    0.04       0  4677.1    0.12       0  4715.8     0.1       0
  5004.3    0.05       0  5008.3     0.1       0  5116.3    0.05       0
  5250.6    0.03       0
Bank Sta=5004.3,5008.3
Exp/Cntr=0.3,0.1

Type RM Length L Ch R = 1,1951,269,269,269
BEGIN DESCRIPTION:
Mapping XS df27381a
END DESCRIPTION:
XS GIS Cut Line= 3
      2423225.03     13558412.07      2423029.75     13558461.54
      2422553.19     13558508.41
#Sta/Elev= 30
  4781.4  355.03  4791.7  355.87  4810.5  352.99  4822.9  351.97  4851.5  349.72
  4856.6  348.54  4884.6  347.98  4892.4  344.89  4897.6  345.00  4905.2  341.14
  4933.4  338.71  4957.7  337.90  4967.1  337.63  4979.6  335.74  4980.7  334.64
  4981.0  334.14  4984.5  334.14  4984.7  334.64  4987.7  334.64  4997.7  337.43
  5007.7  337.15  5047.9  338.22  5066.1  340.08  5078.1  342.44  5098.1  342.65
  5193.9  341.03  5268.8  340.64  5363.0  343.48  5399.6  344.78  5461.7  344.29
#Mann=7,-1,0
  4781.4    0.04       0  4822.9    0.12       0  4957.7     0.1       0
  4980.7    0.05       0  4984.7     0.1       0  5193.9    0.05       0
  5363.0    0.03       0
Bank Sta=4980.7,4984.7
Exp/Cntr=0.3,0.1

Type RM Length L Ch R = 1,1682,99,99,99
BEGIN DESCRIPTION:
Mapping XS 856cf443
END DESCRIPTION:
XS GIS Cut Line= 3
      2423152.14     13558229.77      2422831.84     13558276.64
      2422576.63     13558469.35
#Sta/Elev= 30
  4720.3  354.59  4727.5  354.03  4750.9  353.93  4787.0  350.43  4850.7  347.73
  4909.4  342.40  4919.5  342.22  4939.8  338.55  4960.0  336.02  4970.1  335.32
  4996.7  335.44  5010.5  334.69  5020.6  331.53  5028.7  330.97  5029.0  330.47
  5032.5  330.47  5032.7  330.97  5039.9  334.43  5044.0  334.43  5048.0  339.65
  5052.0  339.80  5062.5  340.54  5090.2  340.54  5178.0  338.70  5183.7  338.84
  5254.0  340.01  5326.8  342.50  5333.1  343.35  5347.7  342.88  5363.8  343.20
#Mann=8,-1,0
  4720.3    0.04       0  4750.9    0.05       0  4850.7     0.1       0
  5028.7    0.05       0  5032.7     0.1       0  5052.0    0.12       0
  5178.0    0.05       0  5183.7    0.03       0
Bank Sta=5028.7,5032.7
Exp/Cntr=0.3,0.1

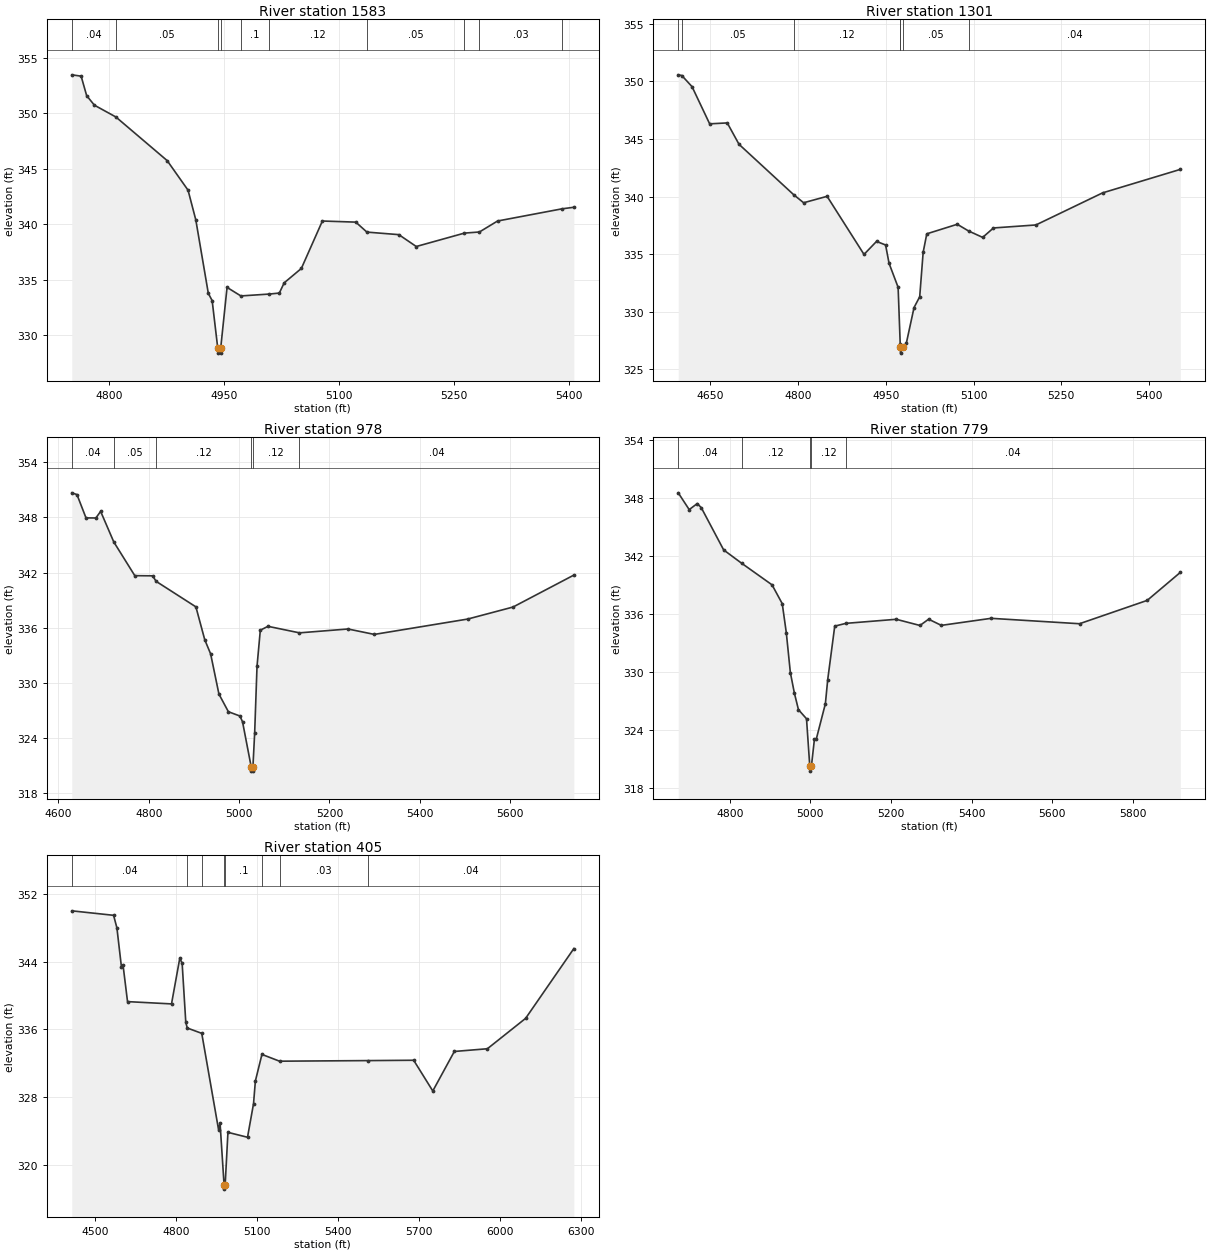
Type RM Length L Ch R = 1,1583,282,282,282
BEGIN DESCRIPTION:
Mapping XS 44fa998a
END DESCRIPTION:
XS GIS Cut Line= 3
      2423074.06     13558128.20      2422857.88     13558167.27
      2422514.13     13558432.89
#Sta/Elev= 30
  4751.9  353.47  4764.1  353.35  4771.3  351.59  4781.4  350.73  4809.3  349.67
  4876.2  345.73  4903.4  343.06  4913.5  340.38  4929.8  333.75  4934.8  333.10
  4942.0  328.86  4942.3  328.36  4945.8  328.36  4946.0  328.86  4954.2  334.29
  4972.2  333.52  5009.3  333.69  5022.3  333.78  5028.6  334.70  5051.0  336.00
  5078.4  340.28  5121.9  340.18  5136.4  339.28  5178.0  339.05  5200.7  337.98
  5263.5  339.19  5283.0  339.29  5306.6  340.28  5390.6  341.38  5406.0  341.52
#Mann=10,-1,0
  4751.9    0.04       0  4809.3    0.05       0  4942.0    0.05       0
  4946.0    0.05       0  4972.2     0.1       0  5009.3    0.12       0
  5136.4    0.05       0  5263.5    0.04       0  5283.0    0.03       0
  5390.6    0.04       0
Bank Sta=4942,4946
Exp/Cntr=0.3,0.1

Type RM Length L Ch R = 1,1301,323,323,323
BEGIN DESCRIPTION:
Mapping XS 20caebfd
END DESCRIPTION:
XS GIS Cut Line= 4
      2422998.52     13558026.64      2422717.25     13558050.08
      2422521.94     13558167.27      2422430.79     13558503.21
#Sta/Elev= 30
  4595.3  350.58  4601.4  350.52  4618.9  349.55  4649.0  346.32  4679.1  346.40
  4699.2  344.54  4792.4  340.17  4809.6  339.46  4849.7  340.02  4912.8  334.97
  4934.2  336.10  4949.7  335.79  4955.6  334.20  4971.1  332.11  4974.7  327.16
  4974.9  326.89  4975.2  326.39  4978.9  326.89  4985.1  327.24  4998.3  330.35
  5008.0  331.29  5013.9  335.16  5020.1  336.76  5072.2  337.59  5091.4  337.01
  5115.6  336.45  5134.1  337.27  5206.6  337.53  5320.6  340.32  5453.4  342.36
#Mann=7,-1,0
  4595.3    0.04       0  4601.4    0.05       0  4792.4    0.12       0
  4974.7    0.05       0  4974.9    0.05       0  4978.9    0.05       0
  5091.4    0.04       0
Bank Sta=4974.9,4978.9
Exp/Cntr=0.3,0.1

Type RM Length L Ch R = 1,978,199,199,199
BEGIN DESCRIPTION:
Mapping XS bc4101fa
END DESCRIPTION:
XS GIS Cut Line= 4
      2422936.02     13557719.34      2422534.96     13557844.35
      2422451.63     13557919.87      2422227.66     13558453.74
#Sta/Elev= 30
  4629.6  350.68  4641.1  350.49  4661.1  347.95  4683.0  347.94  4693.5  348.66
  4722.6  345.33  4769.1  341.66  4808.7  341.64  4816.3  341.04  4904.4  338.26
  4924.0  334.68  4937.0  333.14  4955.4  328.76  4976.3  326.84  5002.0  326.37
  5007.7  325.73  5026.7  320.87  5026.9  320.37  5030.4  320.37  5030.7  320.87
  5034.5  324.53  5039.7  331.78  5047.0  335.72  5064.0  336.14  5133.7  335.43
  5241.1  335.85  5299.4  335.26  5505.9  336.93  5606.4  338.24  5741.1  341.72
#Mann=6,-1,0
  4629.6    0.04       0  4722.6    0.05       0  4816.3    0.12       0
  5026.7    0.05       0  5030.7    0.12       0  5133.7    0.04       0
Bank Sta=5026.7,5030.7
Exp/Cntr=0.3,0.1

Type RM Length L Ch R = 1,779,374,374,374
BEGIN DESCRIPTION:
Mapping XS 5ca85883
END DESCRIPTION:
XS GIS Cut Line= 4
      2422902.13     13557659.45      2422561.00     13557630.81
      2422508.92     13557654.24      2422084.45     13558386.00
#Sta/Elev= 30
  4672.1  348.57  4699.3  346.83  4719.4  347.46  4729.4  347.02  4784.8  342.65
  4829.4  341.27  4904.8  339.03  4930.1  337.08  4940.2  334.06  4950.2  329.94
  4960.2  327.81  4970.3  326.09  4990.3  325.15  4998.4  320.22  4998.6  319.72
  5002.4  320.22  5009.9  323.02  5014.4  323.02  5037.1  326.71  5042.9  329.21
  5060.3  334.75  5088.2  335.04  5212.9  335.46  5271.7  334.82  5293.2  335.47
  5324.7  334.83  5448.1  335.56  5667.5  335.00  5835.4  337.42  5917.5  340.32
#Mann=5,-1,0
  4672.1    0.04       0  4829.4    0.12       0  4998.4    0.05       0
  5002.4    0.12       0  5088.2    0.04       0
Bank Sta=4998.4,5002.4
Exp/Cntr=0.3,0.1

Type RM Length L Ch R = 1,405,0,0,0
BEGIN DESCRIPTION:
LGII4627
END DESCRIPTION:
XS GIS Cut Line= 4
      2422943.95     13557058.13      2422414.37     13557318.72
      2422027.72     13557831.45      2421935.51     13558451.73
#Sta/Elev= 30
  4412.9  350.00  4567.8  349.47  4580.1  347.98  4597.0  343.32  4602.6  343.64
  4619.4  339.27  4782.3  339.00  4813.0  344.41  4821.7  343.79  4835.2  336.81
  4840.7  336.15  4894.3  335.52  4956.5  324.15  4962.1  324.91  4977.0  317.61
  4977.2  317.11  4981.0  317.61  4991.3  323.82  5063.8  323.24  5086.1  327.21
  5092.9  329.89  5117.2  333.03  5182.4  332.23  5509.7  332.30  5679.2  332.34
  5750.0  328.71  5829.8  333.38  5952.2  333.70  6093.7  337.29  6272.4  345.54
#Mann=8,-1,0
  4412.9    0.04       0  4840.7    0.05       0  4894.3     0.1       0
  4977.0    0.05       0  4981.0     0.1       0  5117.2    0.12       0
  5182.4    0.03       0  5509.7    0.04       0
Bank Sta=4977,4981
Exp/Cntr=0.3,0.1

Chan Stop Cuts=-1