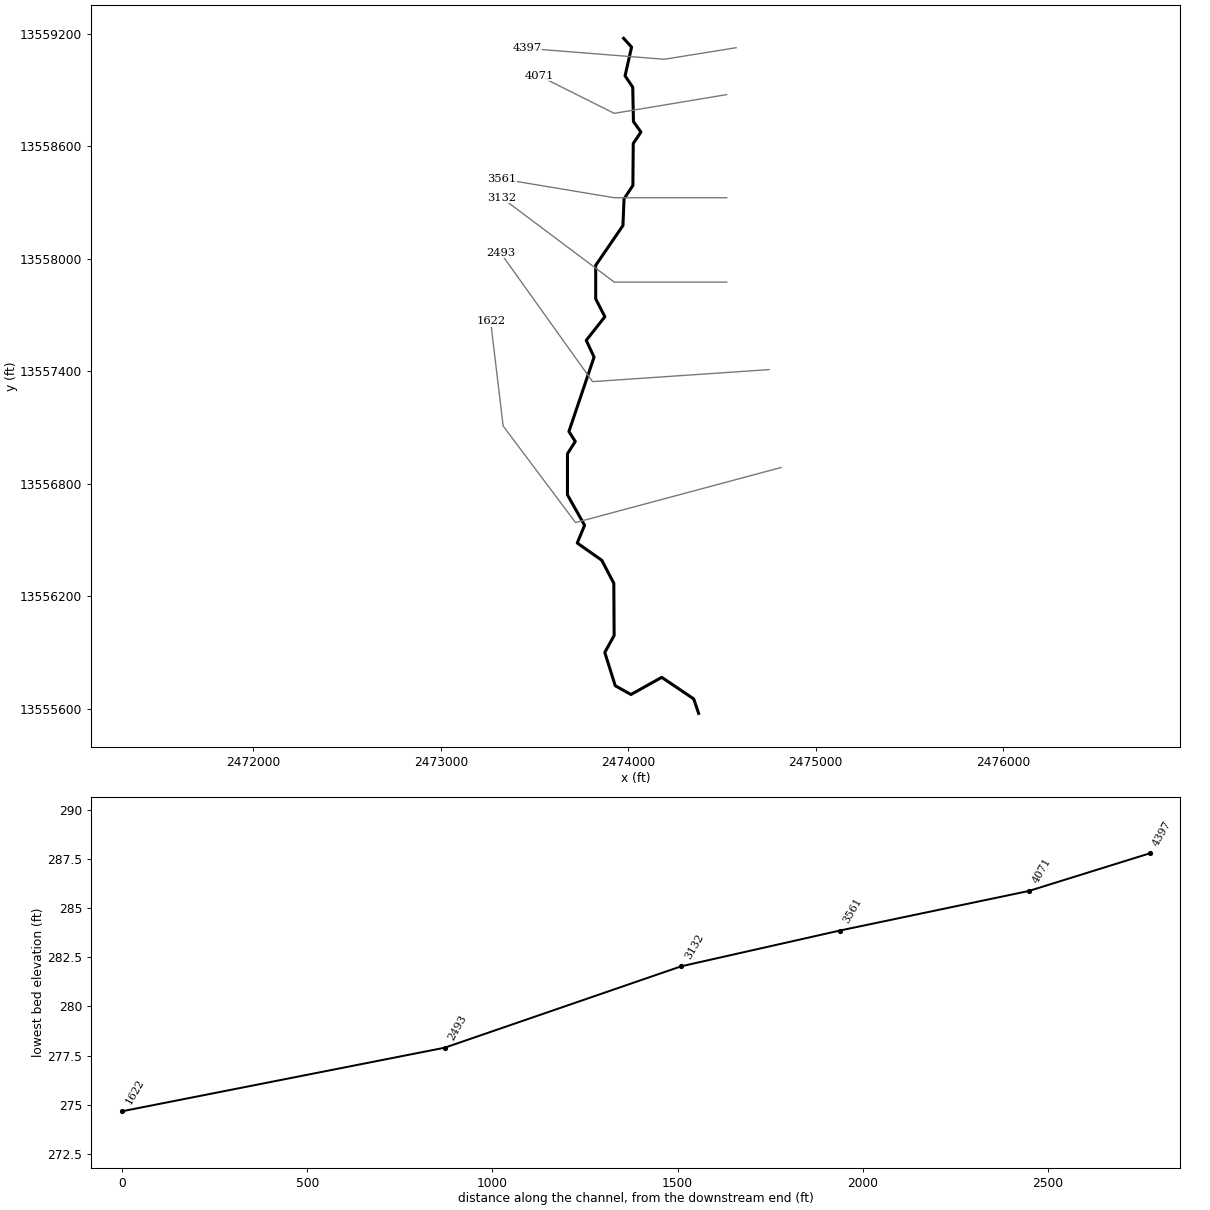
--- TRIB 4 TO SHILOH CREEK.prj (project) ---

Proj Title=TRIB 4 TO SHILOH CREEK Base Level Engineering
Current Plan=p01
Default Exp/Contr=0.3,0.1
English Units
Geom File=g01
Flow File=f01
Plan File=p01
BEGIN DESCRIPTION:
TRIB 4 TO SHILOH CREEK
END DESCRIPTION:

--- TRIB 4 TO SHILOH CREEK.p01 (plan) ---

Plan Title=Multiple Run
Short Identifier=Multiple
Geom File=g01
Flow File=f01
Subcritical Flow
K Sum by GR= 0
Std Step Tol= 0.01
Critical Tol= 0.01
Num of Std Step Trials= 20
Max Error Tol= 0.3
Flow Tol Ratio= 0.001
Split Flow NTrial= 30
Split Flow Tol= 0.02
Split Flow Ratio= 0.02
Log Output Level= 0
Friction Slope Method= 1
Unsteady Friction Slope Method= 2
Unsteady Bridges Friction Slope Method= 1
Parabolic Critical Depth
Global Vel Dist=  1 , 1 , 1
Global Log Level= 0
CheckData=True
Encroach Param= -1, 0, 0, 0
BEGIN DESCRIPTION:
Multiple Run
END DESCRIPTION:

--- TRIB 4 TO SHILOH CREEK.f01 (steady flow) ---

Flow Title=Multiple
Number of Profiles=7
Profile Names=10-year,25-year,50-year,1pct_min,100-year,1pct_plu,500-year
River Rch & RM= TRIB 4 TO SHILOH,Reach-1,4397
     323     498     649     410     818    1631    1285
River Rch & RM= TRIB 4 TO SHILOH,Reach-1,3561
     398     621     815     519    1035    2064    1651
Boundary for River Rch & Prof#=TRIB 4 TO SHILOH,Reach-1,1
Up Type=0
Dn Type=3
Dn Slope=0.005
Boundary for River Rch & Prof#=TRIB 4 TO SHILOH,Reach-1,2
Up Type=0
Dn Type=3
Dn Slope=0.005
Boundary for River Rch & Prof#=TRIB 4 TO SHILOH,Reach-1,3
Up Type=0
Dn Type=3
Dn Slope=0.005
Boundary for River Rch & Prof#=TRIB 4 TO SHILOH,Reach-1,4
Up Type=0
Dn Type=3
Dn Slope=0.005
Boundary for River Rch & Prof#=TRIB 4 TO SHILOH,Reach-1,5
Up Type=0
Dn Type=3
Dn Slope=0.005
Boundary for River Rch & Prof#=TRIB 4 TO SHILOH,Reach-1,6
Up Type=0
Dn Type=3
Dn Slope=0.005
Boundary for River Rch & Prof#=TRIB 4 TO SHILOH,Reach-1,7
Up Type=0
Dn Type=3
Dn Slope=0.005

--- TRIB 4 TO SHILOH CREEK.g01 (geometry) ---

Geom Title=Existing Conditions

River Reach=TRIB 4 TO SHILOH,Reach-1
Reach XY= 30
      2473975.00     13559175.00      2474017.50     13559128.33
      2473982.78     13558975.10      2474023.62     13558914.57
      2474027.46     13558730.86      2474067.44     13558675.00
      2474026.38     13558614.56      2474024.48     13558390.22
      2473977.27     13558319.06      2473971.45     13558176.47
      2473826.20     13557964.50      2473826.24     13557785.50
      2473875.04     13557690.34      2473775.65     13557564.36
      2473817.41     13557475.01      2473683.28     13557078.22
      2473717.21     13557025.10      2473675.65     13556959.84
      2473675.51     13556740.21      2473766.92     13556578.28
      2473727.67     13556483.50      2473858.37     13556391.71
      2473922.76     13556269.07      2473924.46     13555990.21
      2473874.60     13555900.00      2473930.42     13555722.25
      2474014.25     13555675.68      2474178.40     13555767.22
      2474348.85     13555652.27      2474375.00     13555575.00

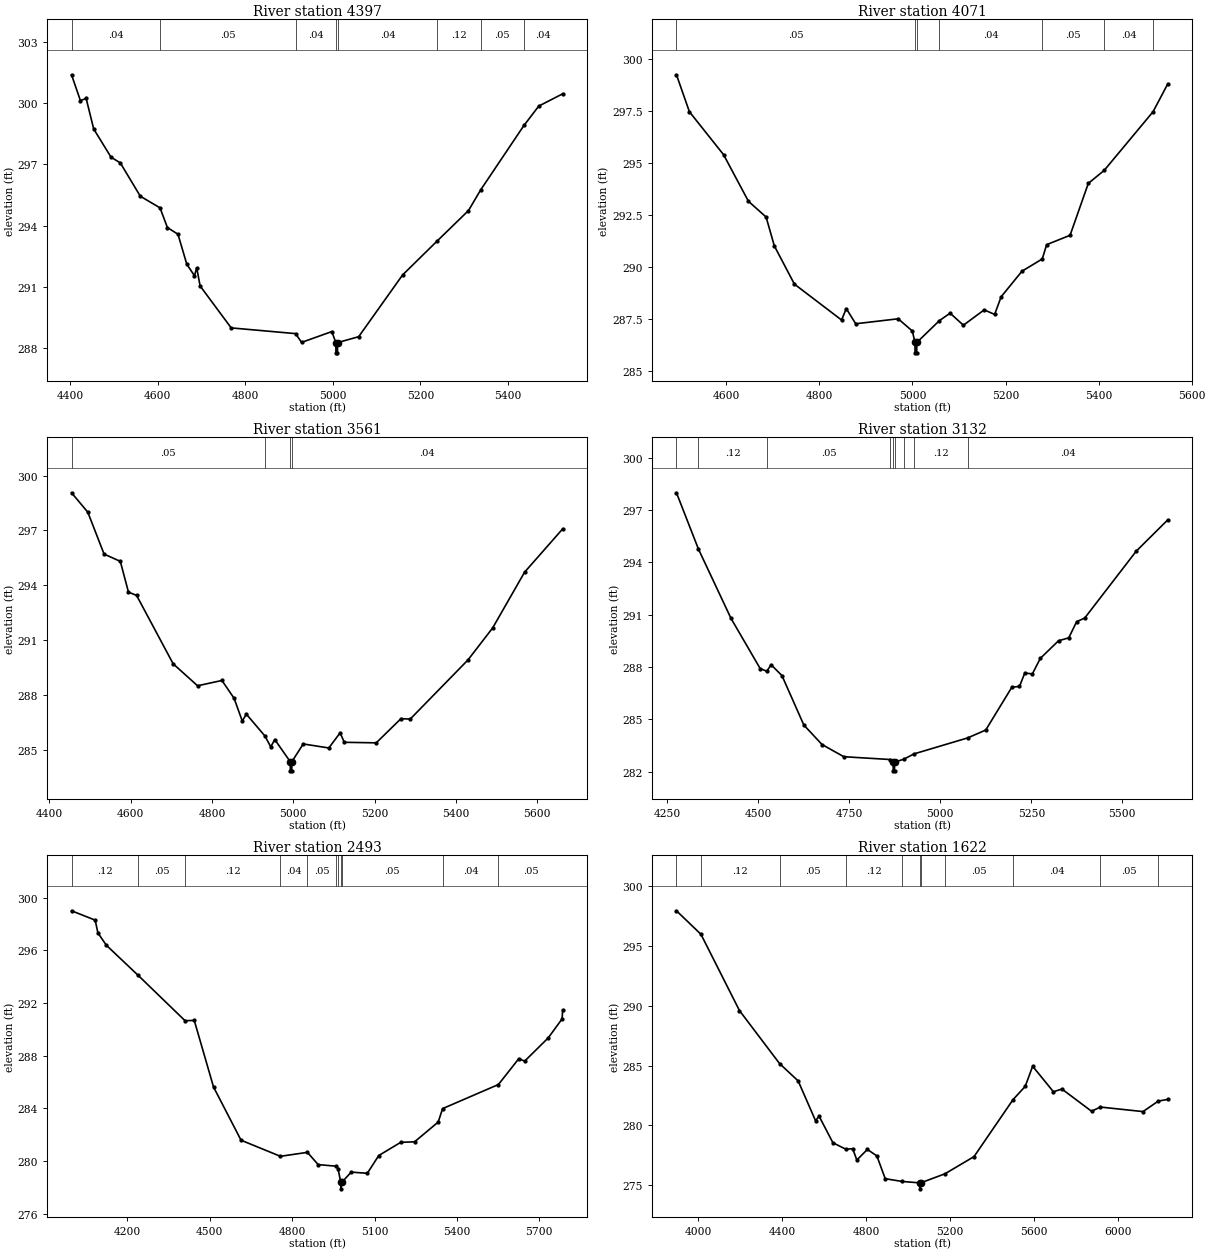
Type RM Length L Ch R = 1,4397,326,326,326
BEGIN DESCRIPTION:
TRIB 4 TO SHILOH CREEK 5.0
END DESCRIPTION:
XS GIS Cut Line= 3
      2474574.99     13559125.00      2474192.17     13559063.34
      2473460.43     13559121.42
#Sta/Elev= 30
  4403.4  301.38  4423.6  300.12  4436.8  300.22  4454.0  298.73  4493.6  297.35
  4514.8  297.07  4560.5  295.44  4605.5  294.87  4622.3  293.91  4646.5  293.58
  4666.7  292.11  4684.2  291.55  4689.2  291.94  4697.1  291.05  4768.0  289.00
  4915.0  288.72  4928.8  288.29  4997.8  288.82  5007.0  288.28  5007.3  287.78
  5010.8  287.78  5011.0  288.28  5059.2  288.57  5159.5  291.59  5238.9  293.26
  5310.0  294.74  5337.8  295.75  5436.6  298.90  5470.5  299.85  5525.2  300.45
#Mann=8,-1,0
  4403.4    0.04       0  4605.5    0.05       0  4915.0    0.04       0
  5007.0    0.04       0  5011.0    0.04       0  5238.9    0.12       0
  5337.8    0.05       0  5436.6    0.04       0
Bank Sta=5007,5011
Exp/Cntr=0.3,0.1

Type RM Length L Ch R = 1,4071,510,510,510
BEGIN DESCRIPTION:
TRIB 4 TO SHILOH CREEK 4.0
END DESCRIPTION:
XS GIS Cut Line= 3
      2474524.96     13558874.99      2473925.00     13558775.00
      2473524.96     13558975.02
#Sta/Elev= 30
  4492.9  299.26  4520.7  297.48  4594.2  295.41  4647.5  293.17  4685.5  292.41
  4703.2  291.02  4746.3  289.18  4847.7  287.45  4857.8  288.00  4878.1  287.27
  4969.3  287.51  4999.8  286.92  5005.4  286.37  5005.6  285.87  5009.1  285.87
  5009.4  286.37  5057.9  287.42  5080.9  287.78  5109.5  287.20  5154.2  287.94
  5176.6  287.72  5190.6  288.57  5235.3  289.80  5278.9  290.39  5288.4  291.08
  5338.7  291.53  5377.9  294.03  5412.2  294.66  5517.0  297.48  5548.4  298.81
#Mann=7,-1,0
  4492.9    0.05       0  5005.4    0.05       0  5009.4    0.05       0
  5057.9    0.04       0  5278.9    0.05       0  5412.2    0.04       0
  5517.0    0.05       0
Bank Sta=5005.4,5009.4
Exp/Cntr=0.3,0.1

Type RM Length L Ch R = 1,3561,429,429,429
BEGIN DESCRIPTION:
TRIB 4 TO SHILOH CREEK 3.0
END DESCRIPTION:
XS GIS Cut Line= 3
      2474524.98     13558325.00      2473925.00     13558325.00
      2473324.96     13558425.01
#Sta/Elev= 30
  4454.6  299.06  4494.6  298.00  4534.6  295.71  4574.6  295.31  4594.6  293.63
  4614.6  293.45  4704.6  289.71  4764.6  288.51  4824.6  288.80  4854.6  287.82
  4874.6  286.58  4884.6  286.96  4930.5  285.76  4944.6  285.17  4954.6  285.57
  4992.6  284.36  4992.8  283.86  4996.3  283.86  4996.6  284.36  5024.6  285.33
  5087.5  285.11  5115.4  285.94  5125.5  285.42  5204.1  285.39  5264.9  286.71
  5287.8  286.69  5429.7  289.92  5490.5  291.67  5569.1  294.72  5662.9  297.09
#Mann=4,-1,0
  4454.6    0.05       0  4930.5    0.04       0  4992.6    0.04       0
  4996.6    0.04       0
Bank Sta=4992.6,4996.6
Exp/Cntr=0.3,0.1

Type RM Length L Ch R = 1,3132,639,639,639
BEGIN DESCRIPTION:
TRIB 4 TO SHILOH CREEK 2.0
END DESCRIPTION:
XS GIS Cut Line= 3
      2474525.04     13557875.00      2473925.00     13557875.00
      2473325.03     13558324.98
#Sta/Elev= 30
  4274.7  297.99  4335.1  294.76  4424.7  290.78  4504.7  287.91  4523.1  287.75
  4534.7  288.13  4564.7  287.50  4624.7  284.67  4674.7  283.55  4734.7  282.85
  4861.6  282.69  4870.2  282.54  4870.5  282.04  4874.0  282.04  4874.2  282.54
  4899.9  282.71  4927.3  283.01  5075.2  283.93  5124.7  284.38  5196.6  286.84
  5217.4  286.88  5232.0  287.65  5252.9  287.60  5274.7  288.49  5324.7  289.50
  5352.9  289.67  5374.7  290.60  5396.6  290.80  5538.3  294.64  5624.7  296.43
#Mann=9,-1,0
  4274.7    0.05       0  4335.1    0.12       0  4523.1    0.05       0
  4861.6    0.12       0  4870.2    0.05       0  4874.2    0.12       0
  4899.9    0.05       0  4927.3    0.12       0  5075.2    0.04       0
Bank Sta=4870.2,4874.2
Exp/Cntr=0.3,0.1

Type RM Length L Ch R = 1,2493,871,871,871
BEGIN DESCRIPTION:
Mapping XS 4f214197
END DESCRIPTION:
XS GIS Cut Line= 3
      2474750.78     13557408.34      2473809.36     13557344.15
      2473318.34     13558031.59
#Sta/Elev= 30
  3996.8  299.01  4082.8  298.30  4092.8  297.33  4123.7  296.39  4239.2  294.11
  4410.3  290.66  4443.6  290.69  4513.8  285.63  4614.0  281.59  4757.3  280.37
  4855.7  280.67  4894.7  279.74  4960.1  279.62  4966.9  279.44  4977.1  278.40
  4977.3  277.90  4981.1  278.40  5015.2  279.17  5073.7  279.08  5115.5  280.43
  5195.4  281.43  5245.8  281.47  5331.8  282.97  5347.8  283.99  5551.1  285.82
  5625.5  287.79  5646.4  287.59  5732.4  289.36  5782.8  290.80  5785.2  291.49
#Mann=11,-1,0
  3996.8    0.12       0  4239.2    0.05       0  4410.3    0.12       0
  4757.3    0.04       0  4855.7    0.05       0  4960.1    0.04       0
  4966.9    0.05       0  4977.1    0.05       0  4981.1    0.05       0
  5347.8    0.04       0  5551.1    0.05       0
Bank Sta=4977.1,4981.1
Exp/Cntr=0.3,0.1

Type RM Length L Ch R = 1,1622,0,0,0
BEGIN DESCRIPTION:
TRIB 4 TO SHILOH CREEK 1.0
END DESCRIPTION:
XS GIS Cut Line= 4
      2474814.94     13556886.27      2473718.83     13556592.58
      2473332.64     13557107.50      2473265.90     13557665.10
#Sta/Elev= 30
  3897.1  297.96  4013.7  295.99  4197.3  289.60  4388.4  285.16  4476.8  283.71
  4559.6  280.38  4576.7  280.75  4642.4  278.53  4703.9  277.99  4736.8  278.03
  4756.3  277.08  4806.5  277.97  4851.7  277.43  4891.7  275.52  4971.2  275.29
  5056.5  275.17  5056.7  274.67  5060.5  275.17  5176.2  275.93  5314.7  277.37
  5500.8  282.15  5558.5  283.25  5593.9  284.94  5692.9  282.80  5733.4  283.03
  5874.4  281.17  5916.6  281.52  6119.8  281.14  6192.5  282.02  6237.1  282.16
#Mann=11,-1,0
  3897.1    0.05       0  4013.7    0.12       0  4388.4    0.05       0
  4703.9    0.12       0  4971.2    0.03       0  5056.5    0.03       0
  5060.5    0.03       0  5176.2    0.05       0  5500.8    0.04       0
  5916.6    0.05       0  6192.5    0.04       0
Bank Sta=5056.5,5060.5
Exp/Cntr=0.3,0.1

Chan Stop Cuts=-1