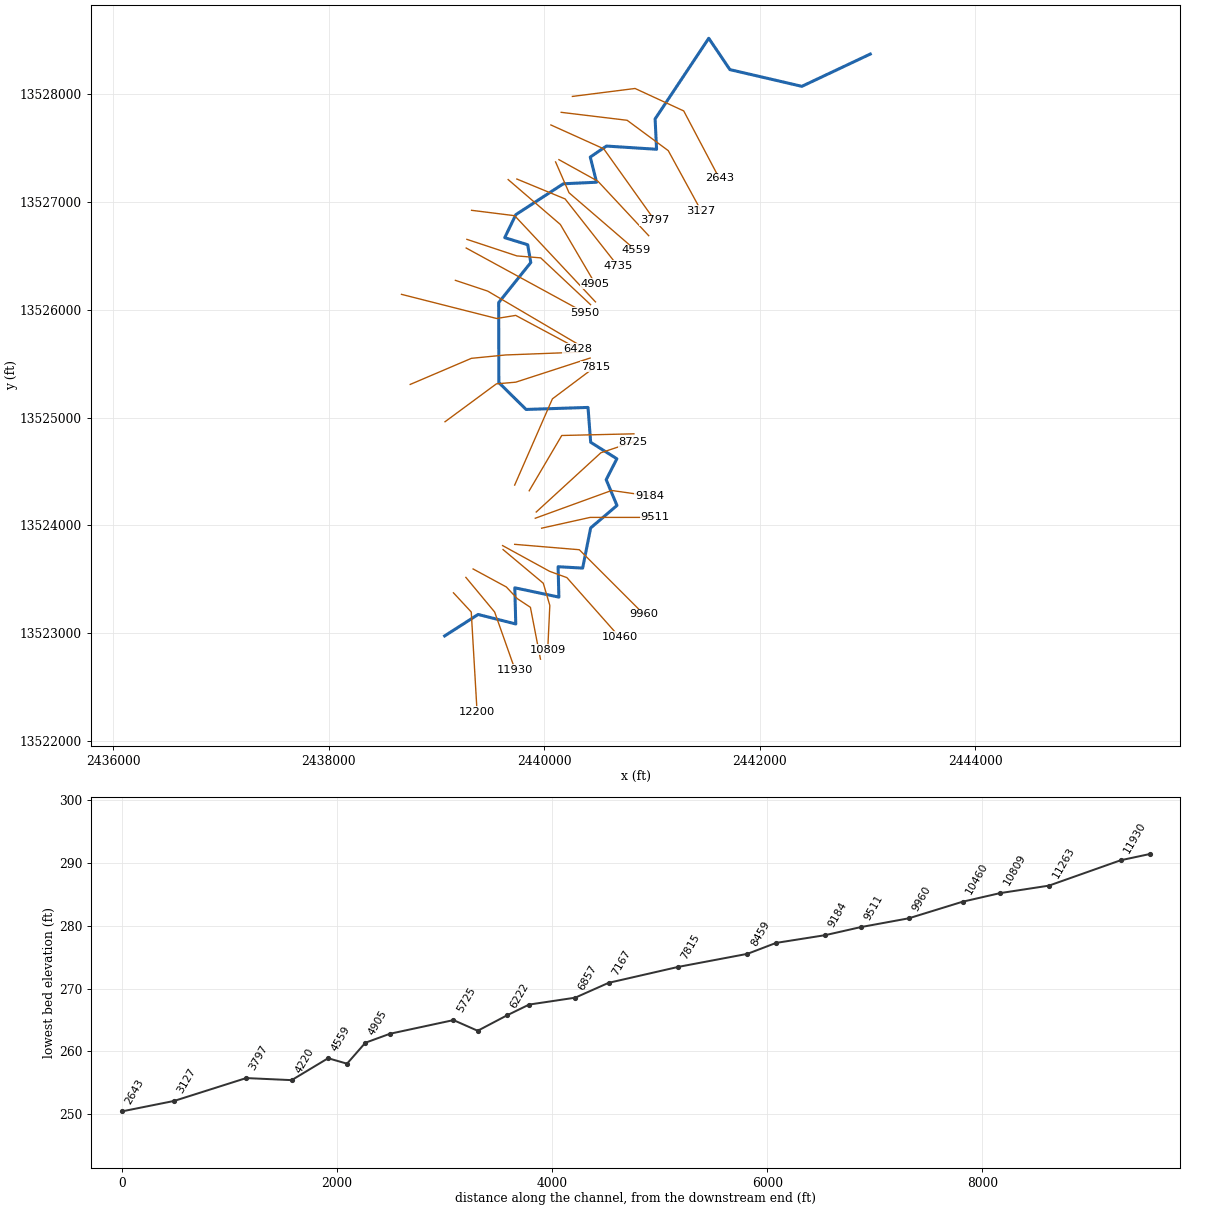
--- TRIB 4 TO SMITH CREEK.prj (project) ---

Proj Title=TRIB 4 TO SMITH CREEK Base Level Engineering
Current Plan=p01
Default Exp/Contr=0.3,0.1
English Units
Geom File=g01
Flow File=f01
Plan File=p01
BEGIN DESCRIPTION:
TRIB 4 TO SMITH CREEK
END DESCRIPTION:

--- TRIB 4 TO SMITH CREEK.p01 (plan) ---

Plan Title=Multiple Run
Short Identifier=Multiple
Geom File=g01
Flow File=f01
Subcritical Flow
K Sum by GR= 0
Std Step Tol= 0.01
Critical Tol= 0.01
Num of Std Step Trials= 20
Max Error Tol= 0.3
Flow Tol Ratio= 0.001
Split Flow NTrial= 30
Split Flow Tol= 0.02
Split Flow Ratio= 0.02
Log Output Level= 0
Friction Slope Method= 1
Unsteady Friction Slope Method= 2
Unsteady Bridges Friction Slope Method= 1
Parabolic Critical Depth
Global Vel Dist=  1 , 1 , 1
Global Log Level= 0
CheckData=True
Encroach Param= -1, 0, 0, 0
BEGIN DESCRIPTION:
Multiple Run
END DESCRIPTION:

--- TRIB 4 TO SMITH CREEK.f01 (steady flow) ---

Flow Title=Multiple
Number of Profiles=7
Profile Names=10-year,25-year,50-year,1pct_min,100-year,1pct_plu,500-year
River Rch & RM= TRIB 4 TO SMITH ,Reach-1,12200
     158     232     293     180     358     715     529
River Rch & RM= TRIB 4 TO SMITH ,Reach-1,9960
     827    1358    1846    1214    2423    4834    4130
River Rch & RM= TRIB 4 TO SMITH ,Reach-1,7167
     869    1432    1950    1284    2562    5113    4382
River Rch & RM= TRIB 4 TO SMITH ,Reach-1,6428
    1109    1851    2542    1688    3367    6719    5850
River Rch & RM= TRIB 4 TO SMITH ,Reach-1,4220
    1178    1970    2710    1800    3592    7167    6252
Boundary for River Rch & Prof#=TRIB 4 TO SMITH ,Reach-1,1
Up Type=0
Dn Type=3
Dn Slope=0.005
Boundary for River Rch & Prof#=TRIB 4 TO SMITH ,Reach-1,2
Up Type=0
Dn Type=3
Dn Slope=0.005
Boundary for River Rch & Prof#=TRIB 4 TO SMITH ,Reach-1,3
Up Type=0
Dn Type=3
Dn Slope=0.005
Boundary for River Rch & Prof#=TRIB 4 TO SMITH ,Reach-1,4
Up Type=0
Dn Type=3
Dn Slope=0.005
Boundary for River Rch & Prof#=TRIB 4 TO SMITH ,Reach-1,5
Up Type=0
Dn Type=3
Dn Slope=0.005
Boundary for River Rch & Prof#=TRIB 4 TO SMITH ,Reach-1,6
Up Type=0
Dn Type=3
Dn Slope=0.005
Boundary for River Rch & Prof#=TRIB 4 TO SMITH ,Reach-1,7
Up Type=0
Dn Type=3
Dn Slope=0.005

--- TRIB 4 TO SMITH CREEK.g01 (geometry) ---

Geom Title=Existing Conditions

River Reach=TRIB 4 TO SMITH ,Reach-1
Reach XY= 30
      2439075.00     13522975.00      2439385.68     13523174.25
      2439735.11     13523086.10      2439726.28     13523421.63
      2440135.24     13523335.35      2440128.05     13523617.46
      2440355.77     13523604.41      2440430.11     13523977.30
      2440674.41     13524185.62      2440574.15     13524425.01
      2440673.43     13524618.96      2440430.28     13524772.29
      2440405.58     13525095.65      2439830.71     13525076.88
      2439578.04     13525326.42      2439576.58     13526068.95
      2439874.51     13526440.22      2439845.66     13526605.60
      2439632.65     13526671.30      2439735.76     13526884.70
      2440176.56     13527171.26      2440485.11     13527185.62
      2440426.50     13527419.13      2440576.56     13527521.24
      2441041.79     13527491.44      2441028.31     13527773.27
      2441526.25     13528521.65      2441722.42     13528230.71
      2442390.22     13528075.52      2443025.00     13528375.00

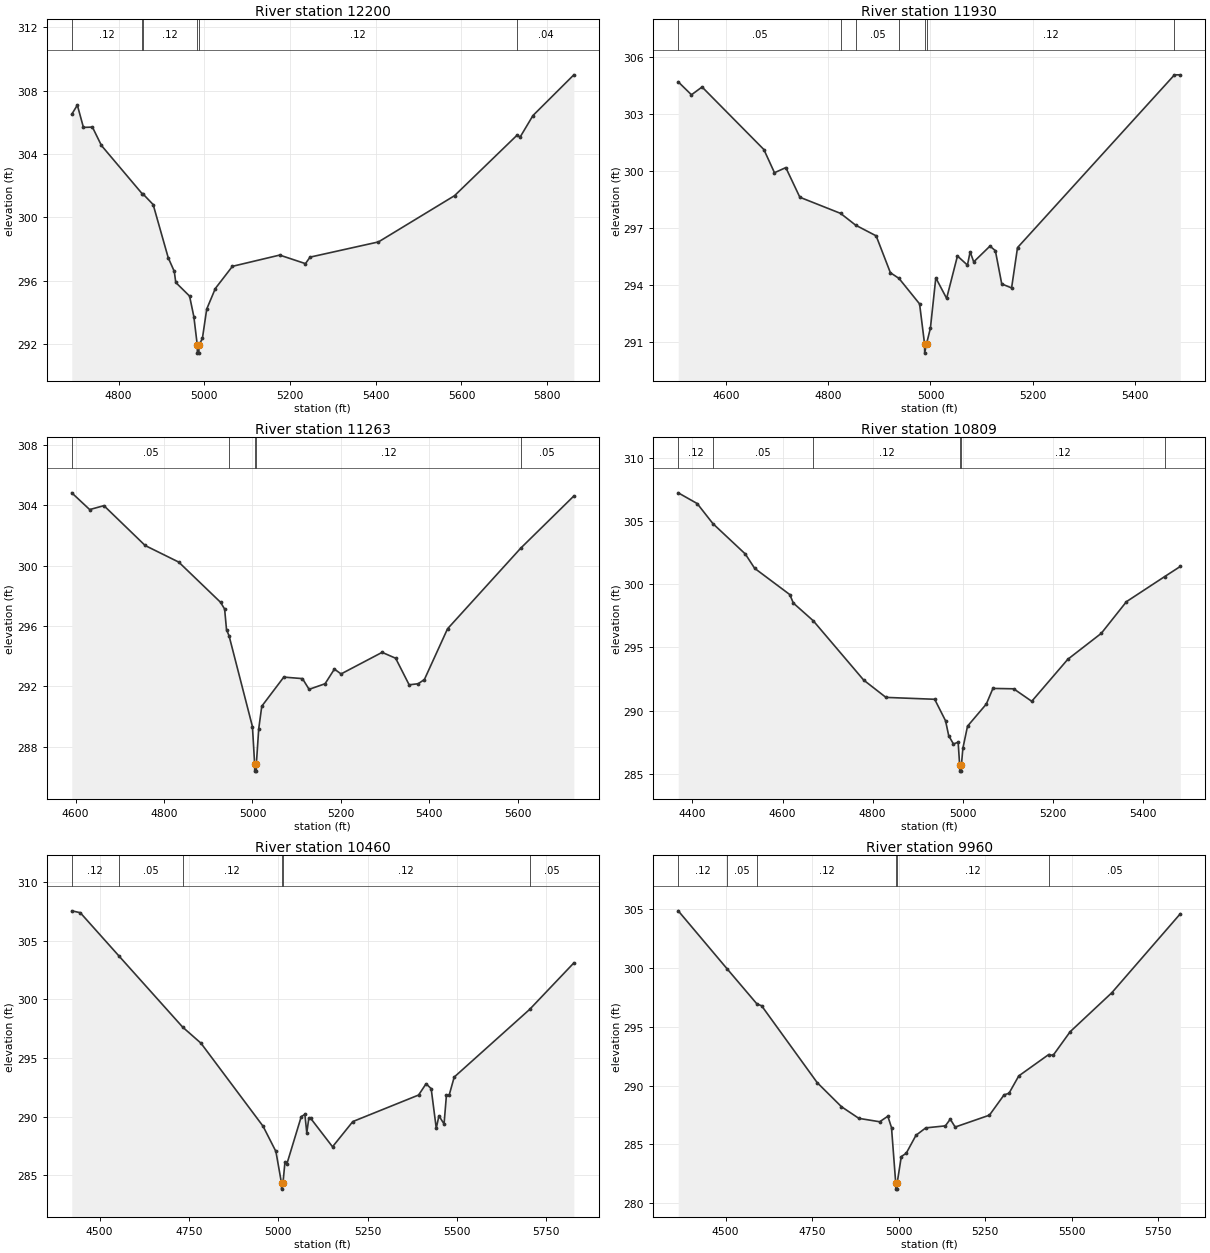
Type RM Length L Ch R = 1,12200,270,270,270
BEGIN DESCRIPTION:
Mapping XS 9c07b6a0
END DESCRIPTION:
XS GIS Cut Line= 3
      2439157.06     13523375.12      2439322.03     13523197.13
      2439376.06     13522269.78
#Sta/Elev= 30
  4690.6  306.50  4703.6  307.08  4717.8  305.67  4738.8  305.69  4759.8  304.53
  4855.3  301.47  4857.8  301.44  4880.5  300.80  4915.7  297.44  4929.8  296.58
  4933.3  295.88  4965.5  295.02  4975.5  293.72  4983.5  291.92  4983.7  291.42
  4987.2  291.42  4987.5  291.92  4995.5  292.36  5005.5  294.20  5025.6  295.50
  5065.5  296.90  5175.8  297.61  5235.9  297.07  5246.6  297.48  5406.2  298.44
  5583.8  301.36  5729.7  305.18  5736.8  305.06  5766.8  306.42  5862.2  308.99
#Mann=6,-1,0
  4690.6    0.12       0  4855.3    0.05       0  4857.8    0.12       0
  4983.5    0.05       0  4987.5    0.12       0  5729.7    0.04       0
Bank Sta=4983.5,4987.5
Exp/Cntr=0.3,0.1

Type RM Length L Ch R = 1,11930,667,667,667
BEGIN DESCRIPTION:
Mapping XS 5a626ced
END DESCRIPTION:
XS GIS Cut Line= 3
      2439272.13     13523518.29      2439539.04     13523197.13
      2439727.83     13522663.33
#Sta/Elev= 30
  4505.8  304.70  4531.7  304.02  4552.5  304.43  4673.6  301.14  4694.4  299.92
  4716.6  300.19  4744.1  298.63  4824.0  297.78  4853.5  297.16  4893.6  296.60
  4921.5  294.66  4938.4  294.36  4978.7  293.02  4988.4  290.93  4988.7  290.43
  4992.4  290.93  4999.9  291.74  5010.5  294.39  5031.7  293.31  5052.9  295.54
  5072.5  295.06  5077.8  295.76  5084.8  295.23  5116.6  296.06  5127.2  295.82
  5139.7  294.07  5159.0  293.86  5170.6  295.98  5478.2  305.07  5489.6  305.07
#Mann=7,-1,0
  4505.8    0.05       0  4824.0    0.12       0  4853.5    0.05       0
  4938.4    0.12       0  4988.4    0.05       0  4992.4    0.12       0
  5478.2    0.05       0
Bank Sta=4988.4,4992.4
Exp/Cntr=0.3,0.1

Type RM Length L Ch R = 1,11263,454,454,454
BEGIN DESCRIPTION:
Mapping XS 1d14c31b
END DESCRIPTION:
XS GIS Cut Line= 5
      2439339.38     13523596.45      2439647.55     13523429.34
      2439749.54     13523320.83      2439871.07     13523240.54
      2439964.26     13522759.42
#Sta/Elev= 30
  4591.5  304.83  4632.0  303.72  4664.2  303.98  4757.4  301.34  4833.4  300.24
  4927.8  297.58  4937.1  297.13  4941.4  295.76  4947.1  295.36  5000.0  289.34
  5004.9  286.89  5005.2  286.39  5008.7  286.39  5008.9  286.89  5014.2  289.19
  5021.1  290.69  5070.9  292.62  5113.1  292.52  5128.1  291.81  5164.2  292.18
  5185.3  293.15  5200.4  292.83  5293.2  294.26  5323.8  293.87  5354.3  292.11
  5374.7  292.18  5388.8  292.46  5441.1  295.82  5606.5  301.16  5726.7  304.62
#Mann=5,-1,0
  4591.5    0.05       0  4947.1    0.12       0  5004.9    0.05       0
  5008.9    0.12       0  5606.5    0.05       0
Bank Sta=5004.9,5008.9
Exp/Cntr=0.3,0.1

Type RM Length L Ch R = 1,10809,349,349,349
BEGIN DESCRIPTION:
Mapping XS f616dbc1
END DESCRIPTION:
XS GIS Cut Line= 4
      2439617.13     13523776.59      2439990.43     13523464.06
      2440051.19     13523257.90      2440031.66     13522845.54
#Sta/Elev= 30
  4368.4  307.24  4410.5  306.39  4445.4  304.80  4517.2  302.40  4538.1  301.26
  4616.1  299.18  4623.9  298.51  4668.1  297.11  4780.1  292.41  4829.5  291.04
  4937.7  290.89  4961.8  289.19  4968.9  288.00  4979.4  287.35  4989.8  287.49
  4993.1  285.70  4993.4  285.20  4996.9  285.20  4997.1  285.70  5000.3  287.01
  5010.6  288.76  5052.3  290.51  5067.0  291.75  5113.1  291.72  5153.2  290.73
  5233.3  294.06  5307.5  296.11  5363.4  298.62  5448.4  300.61  5483.0  301.41
#Mann=6,-1,0
  4368.4    0.12       0  4445.4    0.05       0  4668.1    0.12       0
  4993.1    0.05       0  4997.1    0.12       0  5448.4    0.05       0
Bank Sta=4993.1,4997.1
Exp/Cntr=0.3,0.1

Type RM Length L Ch R = 1,10460,500,500,500
BEGIN DESCRIPTION:
Mapping XS 91eba960
END DESCRIPTION:
XS GIS Cut Line= 4
      2439612.82     13523813.45      2440049.02     13523574.74
      2440209.61     13523516.14      2440697.91     13522964.91
#Sta/Elev= 30
  4422.4  307.55  4446.2  307.39  4553.3  303.74  4732.6  297.64  4783.8  296.27
  4957.6  289.19  4993.5  287.04  5009.2  284.33  5009.4  283.83  5013.2  284.33
  5018.7  286.10  5024.1  285.97  5064.4  290.01  5074.5  290.20  5079.9  288.63
  5085.5  289.87  5090.6  289.87  5151.9  287.44  5208.7  289.59  5392.7  291.85
  5413.6  292.81  5427.9  292.39  5442.1  289.02  5449.6  290.08  5463.9  289.38
  5470.5  291.82  5478.1  291.83  5492.3  293.38  5703.4  299.15  5827.0  303.11
#Mann=6,-1,0
  4422.4    0.12       0  4553.3    0.05       0  4732.6    0.12       0
  5009.2    0.05       0  5013.2    0.12       0  5703.4    0.05       0
Bank Sta=5009.2,5013.2
Exp/Cntr=0.3,0.1

Type RM Length L Ch R = 1,9960,449,449,449
BEGIN DESCRIPTION:
TRIB 4 TO SMITH CREEK 14.0
END DESCRIPTION:
XS GIS Cut Line= 3
      2439724.99     13523825.00      2440325.00     13523775.00
      2440924.99     13523175.01
#Sta/Elev= 30
  4363.2  304.86  4504.0  299.94  4590.9  296.93  4604.0  296.79  4764.6  290.25
  4834.8  288.20  4885.0  287.21  4945.2  286.92  4968.8  287.39  4979.4  286.42
  4991.6  281.69  4991.8  281.19  4995.3  281.19  4995.6  281.69  5007.7  283.96
  5021.9  284.24  5050.1  285.77  5078.4  286.40  5135.0  286.57  5149.1  287.14
  5163.3  286.47  5262.3  287.48  5304.7  289.21  5318.8  289.34  5347.1  290.82
  5433.7  292.64  5446.1  292.56  5495.6  294.58  5615.8  297.89  5813.8  304.61
#Mann=6,-1,0
  4363.2    0.12       0  4504.0    0.05       0  4590.9    0.12       0
  4991.6    0.05       0  4995.6    0.12       0  5433.7    0.05       0
Bank Sta=4991.6,4995.6
Exp/Cntr=0.3,0.1

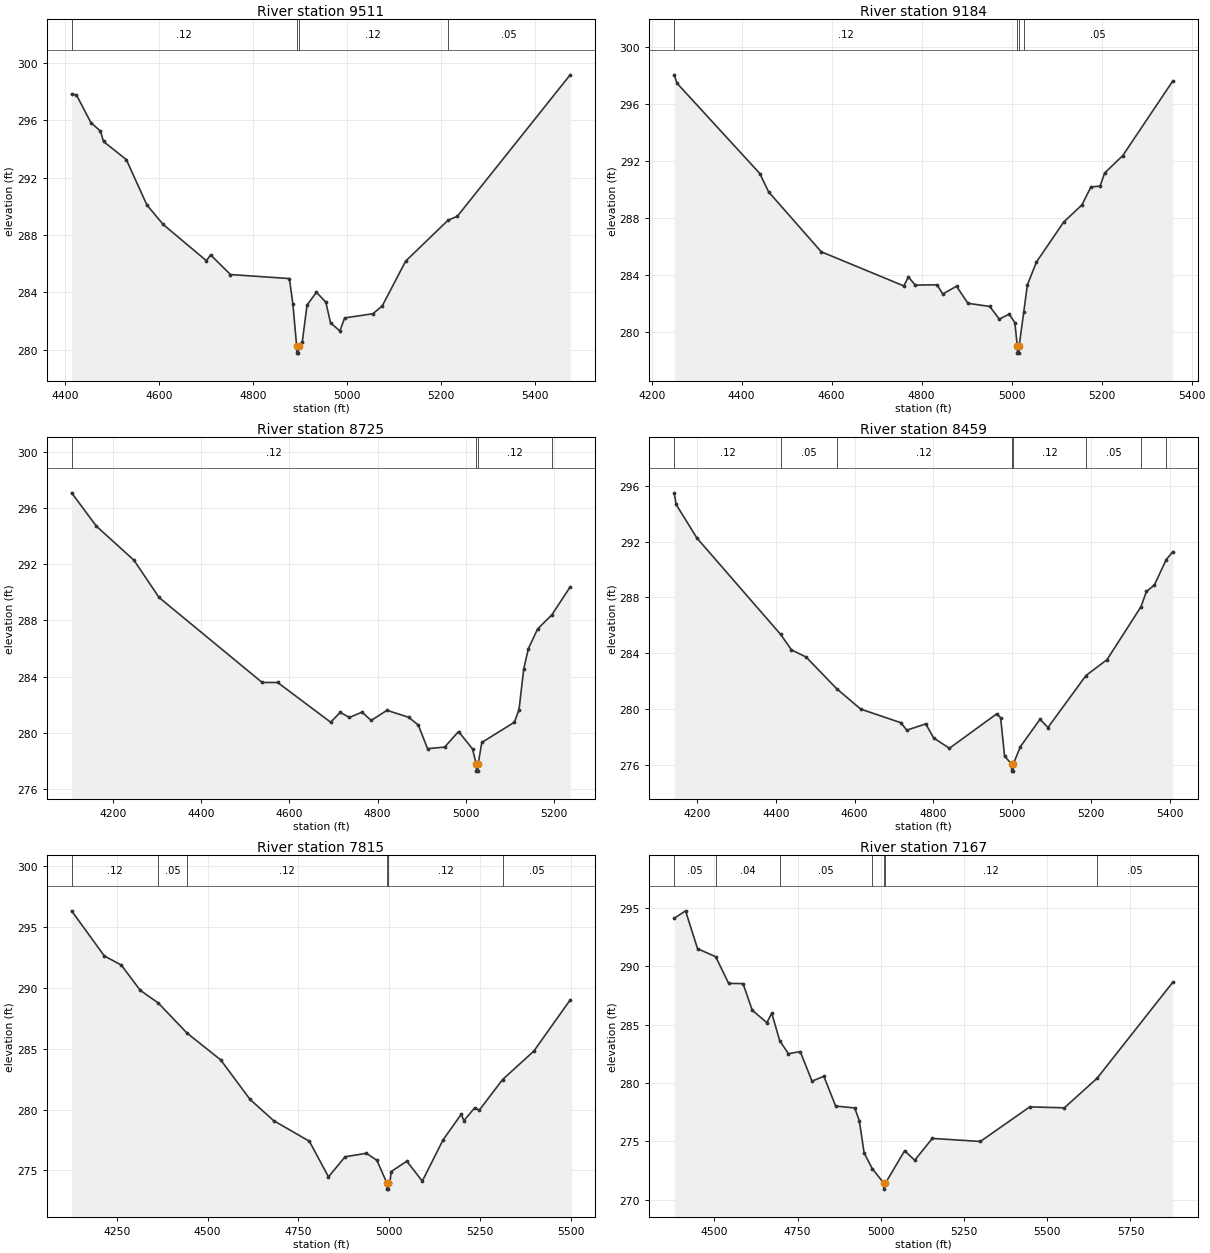
Type RM Length L Ch R = 1,9511,327,327,327
BEGIN DESCRIPTION:
TRIB 4 TO SMITH CREEK 13.0
END DESCRIPTION:
XS GIS Cut Line= 3
      2439974.98     13523975.00      2440425.00     13524075.00
      2441025.00     13524075.00
#Sta/Elev= 30
  4414.0  297.82  4424.3  297.75  4455.0  295.83  4475.5  295.23  4481.9  294.51
  4530.5  293.25  4574.1  290.10  4608.7  288.74  4700.9  286.21  4709.8  286.62
  4752.1  285.25  4877.5  284.97  4885.0  283.17  4892.9  280.28  4893.2  279.78
  4896.8  279.78  4897.0  280.28  4905.0  280.58  4915.0  283.12  4935.0  284.02
  4955.0  283.33  4965.0  281.89  4985.0  281.32  4995.0  282.23  5055.0  282.52
  5075.0  283.06  5125.0  286.19  5214.8  289.02  5235.0  289.31  5475.0  299.15
#Mann=4,-1,0
  4414.0    0.12       0  4892.9    0.05       0  4897.0    0.12       0
  5214.8    0.05       0
Bank Sta=4892.9,4897
Exp/Cntr=0.3,0.1

Type RM Length L Ch R = 1,9184,459,459,459
BEGIN DESCRIPTION:
TRIB 4 TO SMITH CREEK 12.0
END DESCRIPTION:
XS GIS Cut Line= 3
      2439916.07     13524067.21      2440625.00     13524325.00
      2440975.00     13524275.00
#Sta/Elev= 30
  4250.2  298.06  4256.4  297.47  4440.6  291.12  4459.9  289.84  4576.9  285.63
  4760.5  283.23  4770.5  283.86  4785.8  283.29  4834.3  283.31  4846.9  282.66
  4877.5  283.21  4902.8  282.01  4951.3  281.79  4972.6  280.90  4994.6  281.25
  5007.1  280.65  5012.6  279.01  5012.9  278.51  5016.5  278.51  5016.7  279.01
  5026.8  281.38  5034.9  283.30  5055.1  284.91  5115.7  287.72  5156.1  288.92
  5176.3  290.19  5196.5  290.24  5206.6  291.16  5247.0  292.39  5358.1  297.63
#Mann=4,-1,0
  4250.2    0.12       0  5012.6    0.05       0  5016.7    0.12       0
  5026.8    0.05       0
Bank Sta=5012.6,5016.7
Exp/Cntr=0.3,0.1

Type RM Length L Ch R = 1,8725,266,266,266
BEGIN DESCRIPTION:
TRIB 4 TO SMITH CREEK 11.0
END DESCRIPTION:
XS GIS Cut Line= 3
      2439924.99     13524124.99      2440525.00     13524675.00
      2440825.02     13524775.01
#Sta/Elev= 30
  4106.4  297.08  4162.8  294.70  4247.9  292.28  4304.7  289.63  4538.4  283.58
  4573.5  283.58  4693.7  280.75  4715.3  281.45  4736.3  281.09  4764.7  281.47
  4785.6  280.88  4821.4  281.60  4870.7  281.10  4892.3  280.55  4913.3  278.87
  4952.0  278.98  4983.6  280.09  5015.2  278.85  5023.7  277.77  5024.0  277.27
  5027.6  277.27  5027.9  277.77  5036.3  279.31  5110.1  280.75  5120.6  281.64
  5131.2  284.51  5141.7  285.98  5162.8  287.39  5194.9  288.39  5236.6  290.38
#Mann=4,-1,0
  4106.4    0.12       0  5023.7    0.05       0  5027.9    0.12       0
  5194.9    0.05       0
Bank Sta=5023.7,5027.9
Exp/Cntr=0.3,0.1

Type RM Length L Ch R = 1,8459,644,644,644
BEGIN DESCRIPTION:
Mapping XS a0554b77
END DESCRIPTION:
XS GIS Cut Line= 3
      2439859.80     13524322.15      2440161.87     13524835.15
      2440831.86     13524850.74
#Sta/Elev= 30
  4142.1  295.50  4146.9  294.67  4199.6  292.26  4412.2  285.34  4439.7  284.23
  4476.8  283.72  4554.6  281.44  4615.4  279.98  4716.9  279.01  4732.6  278.47
  4780.6  278.92  4800.6  277.91  4840.6  277.17  4960.6  279.64  4970.6  279.36
  4980.6  276.61  4998.5  276.03  4998.8  275.53  5002.4  275.53  5002.7  276.03
  5020.6  277.28  5070.6  279.25  5090.7  278.66  5187.2  282.39  5240.7  283.53
  5326.7  287.32  5340.7  288.42  5360.7  288.88  5391.0  290.71  5407.6  291.28
#Mann=8,-1,0
  4142.1    0.12       0  4412.2    0.05       0  4554.6    0.12       0
  4998.5    0.05       0  5002.7    0.12       0  5187.2    0.05       0
  5326.7    0.12       0  5391.0    0.05       0
Bank Sta=4998.5,5002.7
Exp/Cntr=0.3,0.1

Type RM Length L Ch R = 1,7815,648,648,648
BEGIN DESCRIPTION:
TRIB 4 TO SMITH CREEK 9.0
END DESCRIPTION:
XS GIS Cut Line= 3
      2439724.99     13524374.99      2440075.00     13525175.00
      2440474.98     13525474.98
#Sta/Elev= 30
  4125.4  296.35  4215.5  292.64  4262.2  291.89  4314.5  289.81  4364.0  288.77
  4443.3  286.29  4535.9  284.09  4617.0  280.83  4681.7  279.09  4780.3  277.39
  4832.9  274.46  4878.6  276.11  4937.4  276.40  4966.3  275.82  4993.8  273.95
  4994.0  273.45  4997.7  273.45  4998.0  273.95  5001.8  273.95  5005.9  274.90
  5048.6  275.75  5091.3  274.11  5148.6  277.51  5198.6  279.61  5205.9  279.09
  5235.1  280.12  5248.6  279.96  5312.6  282.47  5398.6  284.81  5498.6  289.02
#Mann=6,-1,0
  4125.4    0.12       0  4364.0    0.05       0  4443.3    0.12       0
  4993.8    0.05       0  4998.0    0.12       0  5312.6    0.05       0
Bank Sta=4993.8,4998
Exp/Cntr=0.3,0.1

Type RM Length L Ch R = 1,7167,310,310,310
BEGIN DESCRIPTION:
Mapping XS 0652cbe1
END DESCRIPTION:
XS GIS Cut Line= 4
      2439078.57     13524962.78      2439555.10     13525314.32
      2439734.79     13525329.95      2440424.92     13525553.92
#Sta/Elev= 30
  4379.1  294.09  4413.1  294.73  4449.2  291.49  4503.8  290.80  4542.6  288.52
  4585.9  288.50  4613.6  286.22  4657.5  285.16  4672.2  285.97  4696.1  283.61
  4722.3  282.50  4757.8  282.68  4793.2  280.15  4828.7  280.57  4864.2  278.02
  4921.4  277.86  4935.2  276.77  4949.8  274.00  4974.0  272.67  5009.1  271.41
  5009.4  270.91  5013.5  271.41  5071.5  274.20  5101.7  273.38  5154.5  275.25
  5299.0  274.99  5447.4  277.95  5551.4  277.87  5649.7  280.40  5877.2  288.62
#Mann=7,-1,0
  4379.1    0.05       0  4503.8    0.04       0  4696.1    0.05       0
  4974.0    0.12       0  5009.1    0.05       0  5013.5    0.12       0
  5649.7    0.05       0
Bank Sta=5009.1,5013.5
Exp/Cntr=0.3,0.1

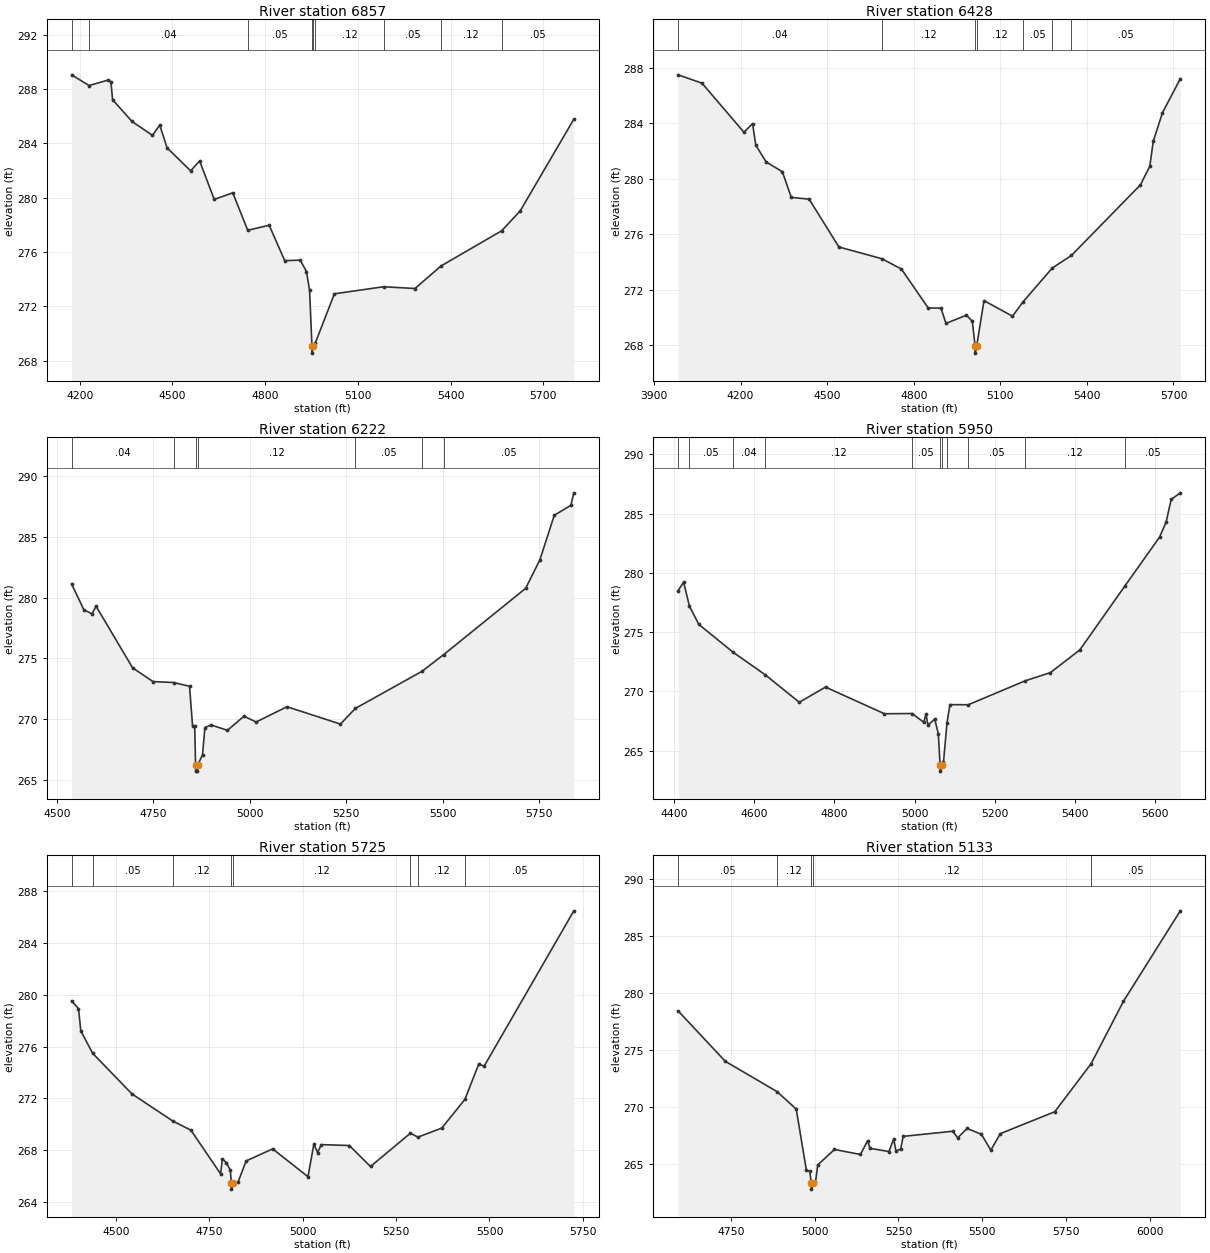
Type RM Length L Ch R = 1,6857,429,429,429
BEGIN DESCRIPTION:
Mapping XS d03692d0
END DESCRIPTION:
XS GIS Cut Line= 4
      2438755.60     13525309.10      2439323.33     13525551.30
      2439641.04     13525582.55      2440328.57     13525608.59
#Sta/Elev= 30
  4174.1  289.05  4230.4  288.26  4293.0  288.67  4301.1  288.52  4306.6  287.22
  4369.1  285.62  4435.5  284.59  4459.1  285.35  4482.8  283.67  4559.0  281.98
  4588.1  282.71  4635.3  279.87  4695.3  280.36  4743.7  277.60  4813.1  277.97
  4863.4  275.36  4913.6  275.40  4933.7  274.56  4943.7  273.19  4951.5  269.05
  4951.9  268.55  4956.0  269.05  4962.3  269.30  5024.1  272.92  5183.4  273.44
  5284.7  273.31  5368.9  274.97  5565.0  277.56  5624.9  279.02  5798.6  285.78
#Mann=9,-1,0
  4174.1    0.05       0  4230.4    0.04       0  4743.7    0.05       0
  4951.5    0.05       0  4956.0    0.05       0  4962.3    0.12       0
  5183.4    0.05       0  5368.9    0.12       0  5565.0    0.05       0
Bank Sta=4951.5,4956
Exp/Cntr=0.3,0.1

Type RM Length L Ch R = 1,6428,206,206,206
BEGIN DESCRIPTION:
Mapping XS a08a90e0
END DESCRIPTION:
XS GIS Cut Line= 4
      2438674.87     13526145.06      2439557.70     13525921.09
      2439734.79     13525949.74      2440307.70     13525642.45
#Sta/Elev= 30
  3983.5  287.48  4066.2  286.88  4211.6  283.35  4241.6  283.97  4252.5  282.43
  4288.4  281.21  4344.7  280.51  4375.7  278.66  4437.6  278.53  4540.7  275.09
  4690.3  274.24  4757.4  273.50  4850.2  270.70  4894.3  270.69  4911.8  269.59
  4982.7  270.18  5003.0  269.74  5012.8  267.95  5013.2  267.45  5018.1  267.95
  5043.5  271.23  5142.1  270.11  5179.6  271.16  5279.9  273.57  5346.4  274.48
  5585.6  279.56  5618.1  280.90  5630.0  282.69  5661.9  284.75  5723.8  287.20
#Mann=7,-1,0
  3983.5    0.04       0  4690.3    0.12       0  5012.8    0.05       0
  5018.1    0.12       0  5179.6    0.05       0  5279.9    0.12       0
  5346.4    0.05       0
Bank Sta=5012.8,5018.1
Exp/Cntr=0.3,0.1

Type RM Length L Ch R = 1,6222,272,272,272
BEGIN DESCRIPTION:
TRIB 4 TO SMITH CREEK 6.0
END DESCRIPTION:
XS GIS Cut Line= 3
      2439175.00     13526275.00      2439475.00     13526175.00
      2440325.01     13525674.99
#Sta/Elev= 30
  4538.2  281.13  4569.8  279.01  4590.9  278.67  4601.5  279.30  4696.3  274.23
  4749.0  273.10  4802.7  273.02  4843.9  272.71  4851.8  269.44  4857.3  269.44
  4859.6  266.23  4860.0  265.73  4864.5  265.73  4864.9  266.23  4877.6  267.07
  4883.7  269.31  4899.4  269.53  4942.3  269.09  4985.2  270.25  5016.6  269.77
  5096.6  271.03  5235.3  269.60  5273.9  270.89  5446.7  273.94  5503.1  275.32
  5715.6  280.77  5752.7  283.13  5789.8  286.78  5832.8  287.60  5840.6  288.63
#Mann=7,-1,0
  4538.2    0.04       0  4802.7    0.12       0  4859.6    0.05       0
  4864.9    0.12       0  5273.9    0.05       0  5446.7    0.12       0
  5503.1    0.05       0
Bank Sta=4859.6,4864.9
Exp/Cntr=0.3,0.1

Type RM Length L Ch R = 1,5950,225,225,225
BEGIN DESCRIPTION:
TRIB 4 TO SMITH CREEK 5.0
END DESCRIPTION:
XS GIS Cut Line= 3
      2439275.03     13526574.98      2439825.00     13526275.00
      2440375.03     13525974.98
#Sta/Elev= 30
  4410.0  278.51  4423.7  279.23  4438.3  277.19  4461.7  275.66  4547.2  273.31
  4626.5  271.43  4712.3  269.09  4777.8  270.37  4924.9  268.12  4993.5  268.14
  5022.7  267.41  5028.4  268.07  5033.6  267.16  5050.2  267.67  5059.2  266.43
  5063.7  263.78  5064.1  263.28  5069.1  263.78  5072.1  264.02  5080.8  267.34
  5088.2  268.89  5133.9  268.88  5276.0  270.90  5338.8  271.59  5412.4  273.51
  5524.1  278.87  5611.2  283.02  5627.4  284.27  5640.2  286.20  5663.0  286.76
#Mann=11,-1,0
  4410.0    0.04       0  4438.3    0.05       0  4547.2    0.04       0
  4626.5    0.12       0  4993.5    0.05       0  5063.7    0.05       0
  5069.1    0.05       0  5080.8    0.12       0  5133.9    0.05       0
  5276.0    0.12       0  5524.1    0.05       0
Bank Sta=5063.7,5069.1
Exp/Cntr=0.3,0.1

Type RM Length L Ch R = 1,5725,592,592,592
BEGIN DESCRIPTION:
Mapping XS 336f97af
END DESCRIPTION:
XS GIS Cut Line= 4
      2439281.67     13526655.46      2439745.20     13526501.82
      2439966.56     13526483.59      2440429.33     13526049.41
#Sta/Elev= 30
  4381.0  279.53  4399.3  278.93  4405.6  277.21  4437.2  275.48  4542.5  272.34
  4651.6  270.25  4700.6  269.53  4779.7  266.17  4784.9  267.32  4795.4  267.02
  4805.9  266.45  4808.7  265.48  4809.1  264.98  4814.1  265.48  4827.0  265.55
  4848.3  267.16  4919.3  268.09  5014.0  265.94  5029.7  268.46  5039.7  267.81
  5049.7  268.42  5124.7  268.35  5181.4  266.73  5288.2  269.30  5308.6  269.00
  5372.4  269.70  5434.3  271.92  5471.5  274.66  5485.7  274.48  5726.0  286.49
#Mann=8,-1,0
  4381.0    0.04       0  4437.2    0.05       0  4651.6    0.12       0
  4808.7    0.05       0  4814.1    0.12       0  5288.2    0.05       0
  5308.6    0.12       0  5434.3    0.05       0
Bank Sta=4808.7,4814.1
Exp/Cntr=0.3,0.1

Type RM Length L Ch R = 1,5133,228,228,228
BEGIN DESCRIPTION:
TRIB 4 TO SMITH CREEK 4.0
END DESCRIPTION:
XS GIS Cut Line= 3
      2439324.96     13526925.01      2439725.00     13526875.00
      2440474.97     13526075.03
#Sta/Elev= 30
  4592.0  278.44  4733.1  274.01  4887.3  271.36  4944.8  269.82  4975.0  264.47
  4985.1  264.37  4989.9  263.30  4990.3  262.80  4995.3  263.30  5002.2  263.42
  5009.1  264.93  5058.9  266.28  5136.6  265.84  5158.0  267.05  5164.9  266.38
  5221.6  266.10  5235.7  267.20  5242.6  266.14  5256.7  266.32  5264.0  267.43
  5412.5  267.88  5426.7  267.30  5455.0  268.12  5497.5  267.62  5525.9  266.22
  5554.2  267.67  5716.8  269.59  5825.4  273.81  5922.0  279.29  6091.7  287.22
#Mann=5,-1,0
  4592.0    0.05       0  4887.3    0.12       0  4989.9    0.05       0
  4995.3    0.12       0  5825.4    0.05       0
Bank Sta=4989.9,4995.3
Exp/Cntr=0.3,0.1

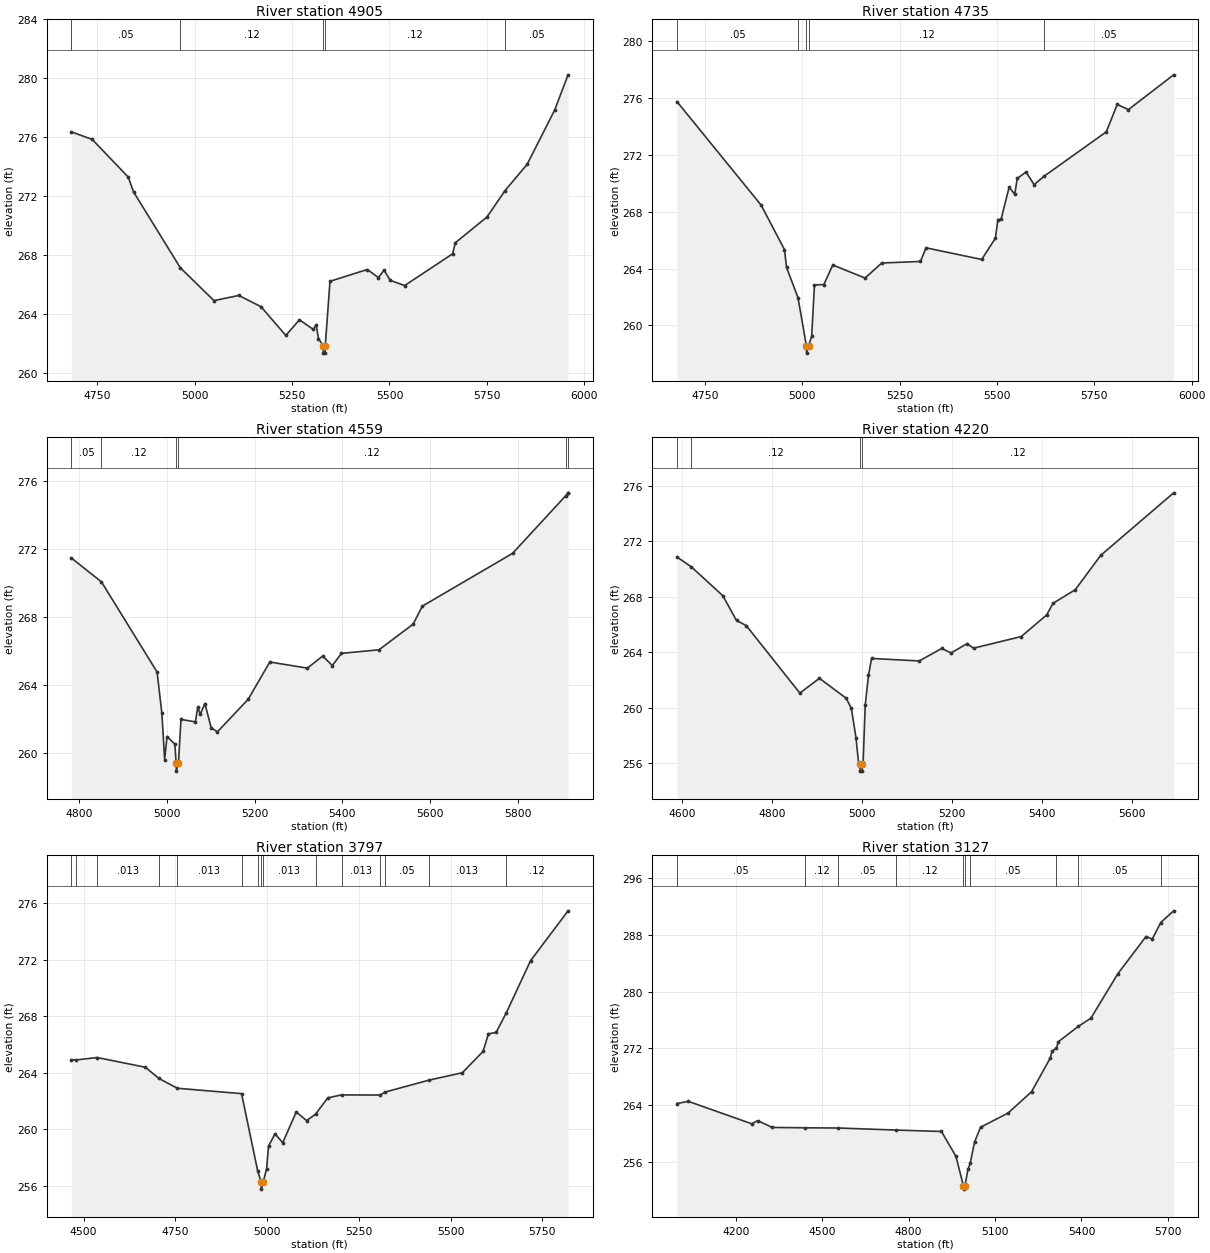
Type RM Length L Ch R = 1,4905,170,170,170
BEGIN DESCRIPTION:
Mapping XS f0b09bd9
END DESCRIPTION:
XS GIS Cut Line= 3
      2439664.46     13527210.17      2440148.85     13526793.49
      2440470.86     13526245.55
#Sta/Elev= 30
  4683.8  276.37  4737.3  275.86  4829.6  273.31  4843.4  272.30  4963.3  267.16
  5049.7  264.93  5113.3  265.28  5170.4  264.52  5234.0  262.57  5269.1  263.63
  5304.5  262.98  5311.9  263.30  5317.8  262.36  5329.9  261.87  5330.3  261.37
  5334.9  261.37  5335.3  261.87  5347.4  266.24  5443.1  267.04  5471.8  266.49
  5486.1  267.00  5501.7  266.31  5538.9  265.95  5661.9  268.10  5669.0  268.85
  5750.2  270.60  5796.6  272.39  5853.3  274.17  5924.1  277.86  5958.3  280.24
#Mann=5,-1,0
  4683.8    0.05       0  4963.3    0.12       0  5329.9    0.05       0
  5335.3    0.12       0  5796.6    0.05       0
Bank Sta=5329.9,5335.3
Exp/Cntr=0.3,0.1

Type RM Length L Ch R = 1,4735,176,176,176
BEGIN DESCRIPTION:
Mapping XS 8d76febf
END DESCRIPTION:
XS GIS Cut Line= 3
      2439745.23     13527215.35      2440193.12     13527030.47
      2440681.94     13526409.04
#Sta/Elev= 30
  4678.6  275.76  4894.7  268.47  4954.5  265.34  4959.9  264.08  4989.4  261.94
  5011.0  258.54  5011.4  258.04  5016.4  258.54  5024.5  259.23  5031.6  262.85
  5055.6  262.87  5078.6  264.25  5161.5  263.33  5204.3  264.39  5303.7  264.50
  5318.1  265.46  5460.9  264.64  5496.2  266.14  5502.5  267.45  5510.6  267.46
  5531.4  269.73  5545.9  269.24  5552.2  270.35  5574.8  270.80  5595.6  269.91
  5621.9  270.52  5780.8  273.63  5808.9  275.56  5837.7  275.20  5953.8  277.65
#Mann=5,-1,0
  4678.6    0.05       0  4989.4    0.12       0  5011.0    0.05       0
  5016.4    0.12       0  5621.9    0.05       0
Bank Sta=5011,5016.4
Exp/Cntr=0.3,0.1

Type RM Length L Ch R = 1,4559,339,339,339
BEGIN DESCRIPTION:
Mapping XS f231a707
END DESCRIPTION:
XS GIS Cut Line= 3
      2440104.60     13527374.18      2440229.58     13527087.76
      2440851.00     13526552.14
#Sta/Elev= 30
  4782.3  271.47  4851.0  270.06  4977.8  264.75  4988.7  262.32  4995.0  259.59
  5000.5  260.95  5018.4  260.50  5021.1  259.41  5021.6  258.91  5026.6  259.41
  5032.3  261.96  5065.1  261.81  5070.7  262.69  5076.1  262.26  5086.9  262.89
  5101.0  261.48  5115.2  261.22  5185.5  263.14  5234.9  265.34  5320.5  264.98
  5355.6  265.69  5377.5  265.13  5398.4  265.85  5483.9  266.06  5561.8  267.57
  5582.7  268.63  5788.5  271.74  5910.3  275.15  5914.8  275.30  5915.2  275.31
#Mann=6,-1,0
  4782.3    0.05       0  4851.0    0.12       0  5021.1    0.05       0
  5026.6    0.12       0  5910.3    0.05       0  5914.8    0.12       0
Bank Sta=5021.1,5026.6
Exp/Cntr=0.3,0.1

Type RM Length L Ch R = 1,4220,423,423,423
BEGIN DESCRIPTION:
Mapping XS ca73233f
END DESCRIPTION:
XS GIS Cut Line= 3
      2440135.83     13527395.05      2440497.81     13527194.53
      2440968.85     13526689.65
#Sta/Elev= 30
  4587.8  270.87  4619.7  270.16  4689.7  268.08  4720.2  266.29  4741.9  265.92
  4861.0  261.05  4904.5  262.12  4964.0  260.68  4975.5  259.95  4985.8  257.84
  4991.5  256.02  4994.4  255.92  4994.8  255.42  4999.5  255.42  4999.9  255.92
  5001.6  255.92  5006.3  260.17  5013.6  262.32  5020.5  263.55  5126.5  263.37
  5176.3  264.27  5197.3  263.95  5233.0  264.62  5247.1  264.29  5353.2  265.13
  5409.8  266.69  5424.0  267.53  5473.4  268.51  5530.0  270.99  5692.1  275.50
#Mann=4,-1,0
  4587.8    0.05       0  4619.7    0.12       0  4994.4    0.05       0
  4999.9    0.12       0
Bank Sta=4994.4,4999.9
Exp/Cntr=0.3,0.1

Type RM Length L Ch R = 1,3797,670,670,670
BEGIN DESCRIPTION:
Mapping XS 03cbc1ba
END DESCRIPTION:
XS GIS Cut Line= 3
      2440061.19     13527717.09      2440551.63     13527495.74
      2441024.70     13526831.70
#Sta/Elev= 30
  4466.6  264.92  4479.6  264.91  4537.0  265.08  4668.3  264.39  4705.0  263.60
  4755.6  262.90  4930.3  262.52  4974.2  257.05  4983.7  256.25  4984.1  255.75
  4989.2  256.25  4998.6  257.20  5003.8  258.80  5021.6  259.67  5042.5  259.04
  5079.3  261.22  5107.6  260.61  5131.9  261.06  5165.2  262.22  5202.7  262.43
  5308.5  262.42  5321.3  262.63  5440.0  263.47  5531.8  264.00  5588.3  265.51
  5603.1  266.76  5624.0  266.86  5651.9  268.26  5717.7  271.94  5820.0  275.48
#Mann=15,-1,0
  4466.6   0.013       0  4479.6    0.05       0  4537.0   0.013       0
  4705.0    0.05       0  4755.6   0.013       0  4930.3    0.12       0
  4974.2   0.013       0  4983.7    0.03       0  4989.2   0.013       0
  5131.9    0.05       0  5202.7   0.013       0  5308.5    0.12       0
  5321.3    0.05       0  5440.0   0.013       0  5651.9    0.12       0
Bank Sta=4983.7,4989.2
Exp/Cntr=0.3,0.1

Type RM Length L Ch R = 1,3127,484,484,484
BEGIN DESCRIPTION:
Mapping XS 4c033a93
END DESCRIPTION:
XS GIS Cut Line= 4
      2440156.66     13527834.29      2440768.64     13527760.50
      2441150.58     13527478.38      2441454.42     13526922.79
#Sta/Elev= 30
  3995.6  264.20  4035.3  264.50  4255.8  261.33  4276.0  261.78  4326.3  260.82
  4441.6  260.77  4556.3  260.74  4756.8  260.45  4913.9  260.25  4964.1  256.75
  4990.0  252.61  4990.5  252.11  4995.7  252.61  5005.8  254.90  5013.6  255.73
  5028.8  258.76  5049.7  260.85  5145.1  262.85  5226.7  265.86  5292.1  270.65
  5297.8  271.60  5313.1  272.01  5319.6  272.92  5388.6  275.08  5432.6  276.24
  5526.4  282.53  5624.1  287.78  5645.9  287.43  5675.3  289.76  5720.1  291.41
#Mann=10,-1,0
  3995.6    0.05       0  4441.6    0.12       0  4556.3    0.05       0
  4756.8    0.12       0  4990.0    0.05       0  4995.7    0.12       0
  5013.6    0.05       0  5313.1    0.12       0  5388.6    0.05       0
  5675.3   0.013       0
Bank Sta=4990,4995.7
Exp/Cntr=0.3,0.1

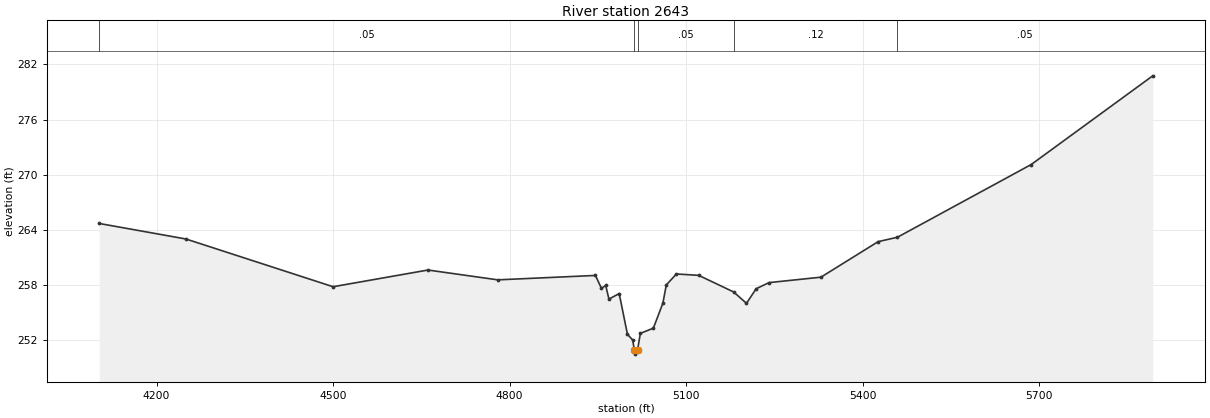
Type RM Length L Ch R = 1,2643,0,0,0
BEGIN DESCRIPTION:
Mapping XS 8d1c693d
END DESCRIPTION:
XS GIS Cut Line= 4
      2440260.81     13527981.85      2440842.43     13528055.64
      2441293.81     13527847.31      2441623.66     13527222.33
#Sta/Elev= 30
  4102.6  264.68  4249.9  262.99  4500.0  257.79  4661.2  259.61  4779.8  258.54
  4945.8  259.02  4956.0  257.61  4963.2  257.93  4968.7  256.44  4986.1  257.05
  5000.1  252.62  5009.1  251.98  5011.7  250.95  5012.2  250.45  5017.4  250.95
  5022.1  252.71  5044.2  253.28  5060.3  255.99  5066.2  257.99  5083.4  259.18
  5121.2  259.03  5180.6  257.22  5202.4  255.98  5218.8  257.57  5240.8  258.24
  5328.9  258.83  5426.1  262.70  5458.9  263.18  5686.2  271.10  5892.7  280.76
#Mann=5,-1,0
  4102.6    0.05       0  5011.7    0.05       0  5017.4    0.05       0
  5180.6    0.12       0  5458.9    0.05       0
Bank Sta=5011.7,5017.4
Exp/Cntr=0.3,0.1

Chan Stop Cuts=-1