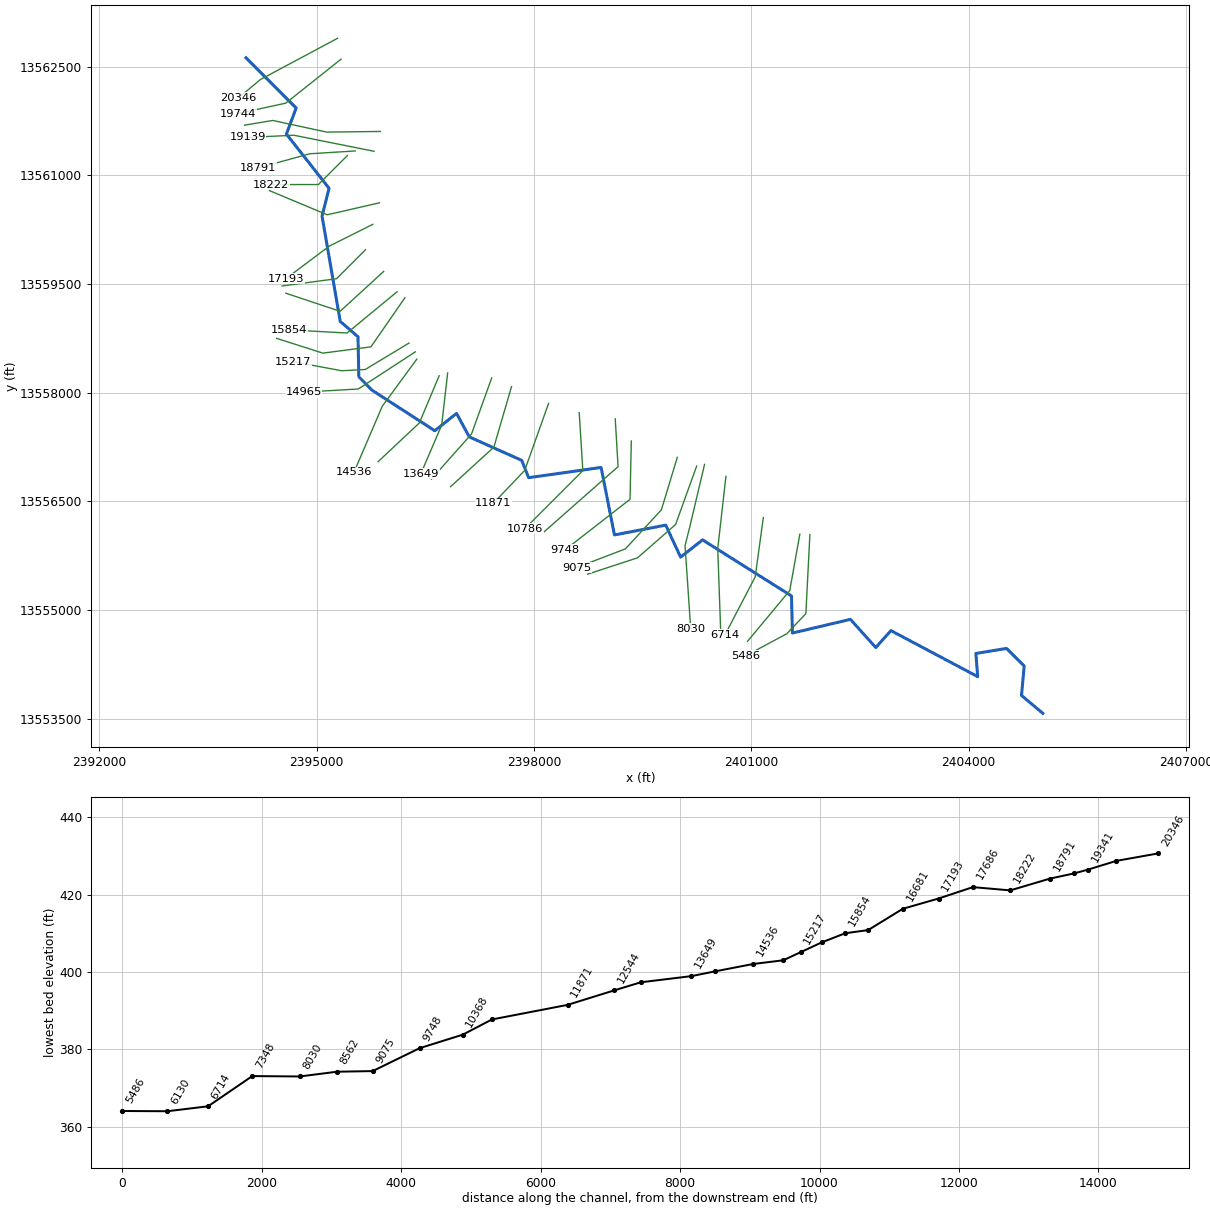
--- TRIB 4 TO THOMAS CREEK.prj (project) ---

Proj Title=TRIB 4 TO THOMAS CREEK Base Level Engineering
Current Plan=p01
Default Exp/Contr=0.3,0.1
English Units
Geom File=g01
Flow File=f01
Plan File=p01
BEGIN DESCRIPTION:
TRIB 4 TO THOMAS CREEK
END DESCRIPTION:

--- TRIB 4 TO THOMAS CREEK.p01 (plan) ---

Plan Title=Multiple Run
Short Identifier=Multiple
Geom File=g01
Flow File=f01
Subcritical Flow
K Sum by GR= 0
Std Step Tol= 0.01
Critical Tol= 0.01
Num of Std Step Trials= 20
Max Error Tol= 0.3
Flow Tol Ratio= 0.001
Split Flow NTrial= 30
Split Flow Tol= 0.02
Split Flow Ratio= 0.02
Log Output Level= 0
Friction Slope Method= 1
Unsteady Friction Slope Method= 2
Unsteady Bridges Friction Slope Method= 1
Parabolic Critical Depth
Global Vel Dist=  1 , 1 , 1
Global Log Level= 0
CheckData=True
Encroach Param= -1, 0, 0, 0
BEGIN DESCRIPTION:
Multiple Run
END DESCRIPTION:

--- TRIB 4 TO THOMAS CREEK.f01 (steady flow) ---

Flow Title=Multiple
Number of Profiles=7
Profile Names=10-year,25-year,50-year,1pct_min,100-year,1pct_plu,500-year
River Rch & RM= TRIB 4 TO THOMAS,Reach-1,20346
     723    1198    1638    1085    2165    4320    3753
River Rch & RM= TRIB 4 TO THOMAS,Reach-1,18791
     917    1536    2114    1409    2811    5608    4927
River Rch & RM= TRIB 4 TO THOMAS,Reach-1,13984
    1348    2300    3206    2160    4309    8598    7728
River Rch & RM= TRIB 4 TO THOMAS,Reach-1,10786
    1396    2385    3327    2242    4474    8926    8032
River Rch & RM= TRIB 4 TO THOMAS,Reach-1,8562
    1797    3084    4317    2917    5820   11612   10497
River Rch & RM= TRIB 4 TO THOMAS,Reach-1,2888
    1901    3270    4583    3099    6184   12338   11175
Boundary for River Rch & Prof#=TRIB 4 TO THOMAS,Reach-1,1
Up Type=0
Dn Type=3
Dn Slope=0.005
Boundary for River Rch & Prof#=TRIB 4 TO THOMAS,Reach-1,2
Up Type=0
Dn Type=3
Dn Slope=0.005
Boundary for River Rch & Prof#=TRIB 4 TO THOMAS,Reach-1,3
Up Type=0
Dn Type=3
Dn Slope=0.005
Boundary for River Rch & Prof#=TRIB 4 TO THOMAS,Reach-1,4
Up Type=0
Dn Type=3
Dn Slope=0.005
Boundary for River Rch & Prof#=TRIB 4 TO THOMAS,Reach-1,5
Up Type=0
Dn Type=3
Dn Slope=0.005
Boundary for River Rch & Prof#=TRIB 4 TO THOMAS,Reach-1,6
Up Type=0
Dn Type=3
Dn Slope=0.005
Boundary for River Rch & Prof#=TRIB 4 TO THOMAS,Reach-1,7
Up Type=0
Dn Type=3
Dn Slope=0.005

--- TRIB 4 TO THOMAS CREEK.g01 (geometry) ---

Geom Title=Existing Conditions

River Reach=TRIB 4 TO THOMAS,Reach-1
Reach XY= 30
      2394025.00     13562625.00      2394717.52     13561931.06
      2394582.85     13561571.77      2395171.97     13560823.61
      2395074.96     13560440.34      2395326.05     13558985.44
      2395571.49     13558773.75      2395582.79     13558221.58
      2395761.62     13558038.54      2396631.12     13557476.76
      2396931.68     13557716.05      2397107.47     13557391.65
      2397831.57     13557067.31      2397926.47     13556828.61
      2398927.47     13556969.55      2399111.26     13556038.19
      2399818.98     13556173.39      2400024.76     13555731.97
      2400327.57     13555970.05      2401555.57     13555195.99
      2401567.94     13554683.97      2402369.07     13554872.77
      2402718.33     13554483.95      2402928.14     13554717.47
      2404125.36     13554082.20      2404100.53     13554402.15
      2404523.37     13554471.87      2404767.40     13554228.34
      2404730.52     13553822.56      2405025.00     13553575.00

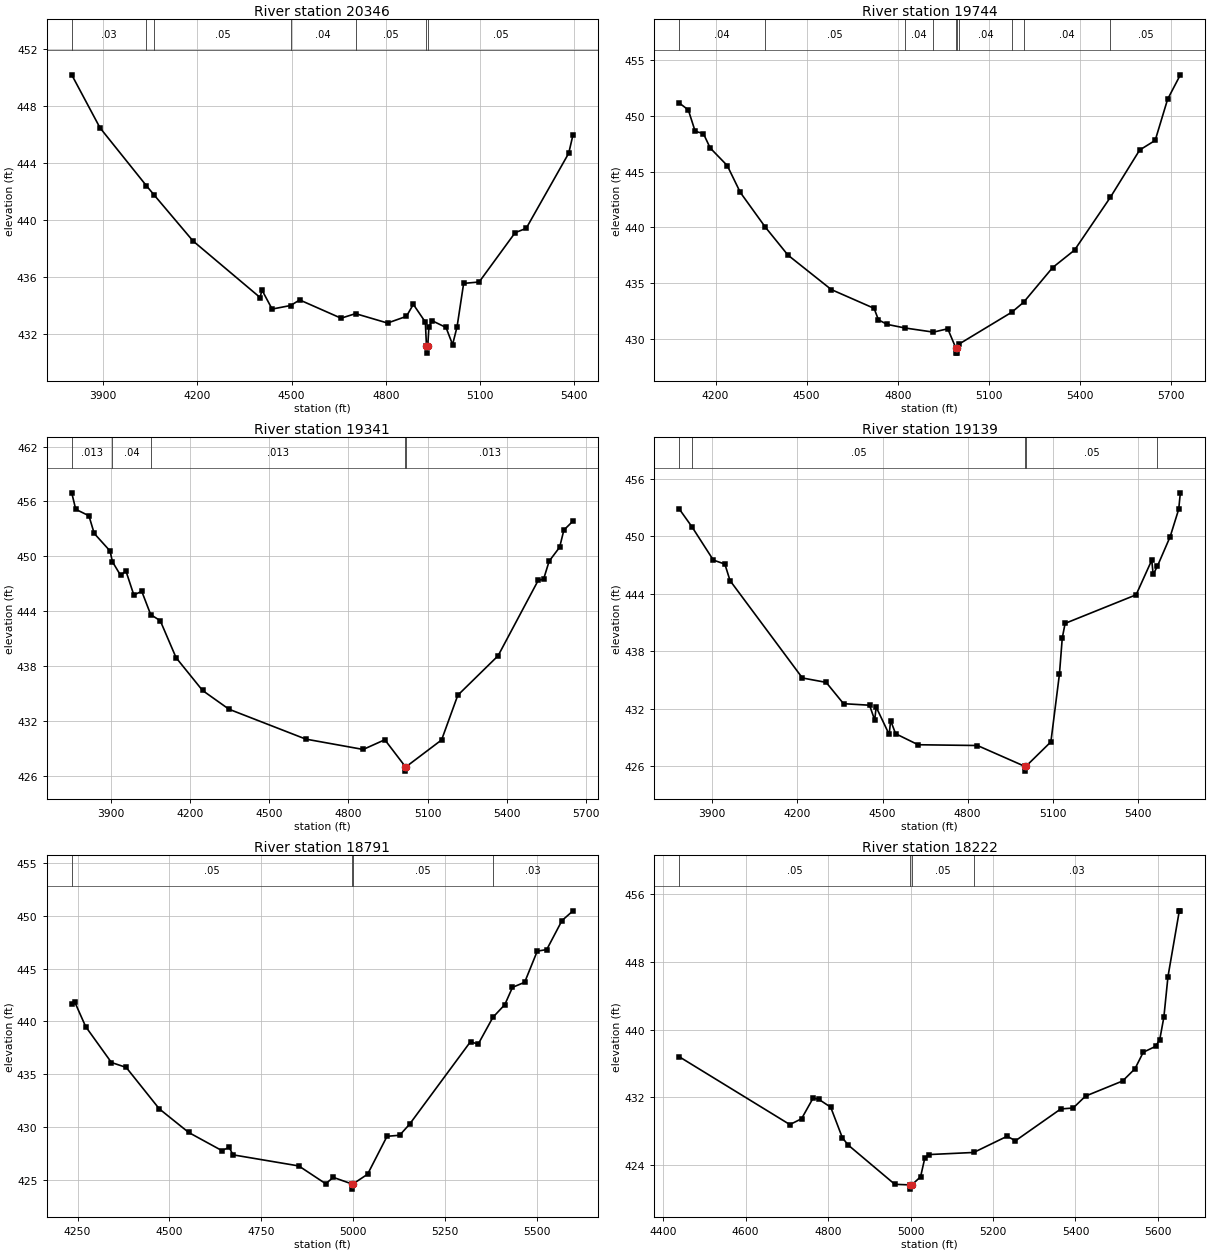
Type RM Length L Ch R = 1,20346,602,602,602
BEGIN DESCRIPTION:
TRIB 4 TO THOMAS CREEK 37.0
END DESCRIPTION:
XS GIS Cut Line= 3
      2395288.17     13562893.16      2394225.00     13562325.00
      2393924.98     13562074.98
#Sta/Elev= 30
  3799.8  450.20  3889.9  446.48  4037.6  442.42  4063.0  441.75  4185.8  438.55
  4399.6  434.58  4405.3  435.11  4437.8  433.77  4496.6  434.02  4525.6  434.41
  4657.3  433.13  4703.5  433.45  4805.3  432.79  4865.4  433.26  4887.4  434.10
  4925.6  432.86  4929.3  431.18  4929.5  430.68  4933.3  431.18  4937.2  432.54
  4947.6  432.95  4991.5  432.48  5012.4  431.28  5026.7  432.53  5047.6  435.57
  5097.0  435.67  5211.6  439.13  5246.7  439.43  5382.1  444.70  5395.8  445.99
#Mann=7,-1,0
  3799.8    0.03       0  4037.6    0.04       0  4063.0    0.05       0
  4496.6    0.04       0  4703.5    0.05       0  4929.3    0.05       0
  4933.3    0.05       0
Bank Sta=4929.3,4933.3
Exp/Cntr=0.3,0.1

Type RM Length L Ch R = 1,19744,403,403,403
BEGIN DESCRIPTION:
Mapping XS 808296e7
END DESCRIPTION:
XS GIS Cut Line= 3
      2395337.62     13562605.92      2394573.71     13561998.26
      2393914.00     13561855.03
#Sta/Elev= 30
  4079.7  451.15  4110.1  450.52  4132.6  448.61  4159.8  448.40  4182.2  447.11
  4238.3  445.54  4281.5  443.13  4363.7  440.03  4438.5  437.52  4581.1  434.44
  4722.0  432.76  4736.4  431.73  4765.3  431.32  4823.9  431.00  4917.6  430.63
  4964.7  430.93  4990.7  429.25  4991.0  428.75  4994.5  428.75  4994.7  429.25
  5003.1  429.58  5176.0  432.42  5214.5  433.30  5310.3  436.41  5382.3  437.97
  5500.2  442.69  5596.9  446.93  5648.0  447.79  5688.9  451.47  5730.9  453.66
#Mann=10,-1,0
  4079.7    0.04       0  4363.7    0.05       0  4823.9    0.04       0
  4917.6    0.05       0  4990.7    0.05       0  4994.7    0.05       0
  5003.1    0.04       0  5176.0    0.05       0  5214.5    0.04       0
  5500.2    0.05       0
Bank Sta=4990.7,4994.7
Exp/Cntr=0.3,0.1

Type RM Length L Ch R = 1,19341,202,202,202
BEGIN DESCRIPTION:
Mapping XS 08ad3c6a
END DESCRIPTION:
XS GIS Cut Line= 4
      2395880.12     13561607.63      2395137.94     13561598.95
      2394395.75     13561759.54      2394005.14     13561694.44
#Sta/Elev= 30
  3753.0  456.94  3768.1  455.14  3818.1  454.43  3838.1  452.50  3898.1  450.58
  3907.0  449.41  3938.1  447.91  3958.1  448.40  3988.1  445.77  4018.1  446.17
  4052.0  443.62  4088.1  442.96  4148.1  438.91  4248.2  435.33  4348.2  433.28
  4639.2  430.01  4856.3  428.88  4938.2  429.94  5015.6  427.01  5015.8  426.51
  5019.7  427.01  5153.1  429.92  5214.5  434.81  5366.9  439.12  5518.9  447.37
  5539.2  447.49  5560.3  449.47  5600.0  450.99  5616.0  452.87  5650.6  453.85
#Mann=5,-1,0
  3753.0   0.013       0  3907.0    0.04       0  4052.0   0.013       0
  5015.6    0.03       0  5019.7   0.013       0
Bank Sta=5015.6,5019.7
Exp/Cntr=0.3,0.1

Type RM Length L Ch R = 1,19139,348,348,348
BEGIN DESCRIPTION:
Mapping XS 31a476ce
END DESCRIPTION:
XS GIS Cut Line= 3
      2395793.31     13561334.20      2394686.55     13561555.55
      2394049.25     13561525.20
#Sta/Elev= 30
  3782.9  452.86  3828.2  450.98  3903.6  447.51  3944.3  447.09  3962.5  445.37
  4217.5  435.22  4301.3  434.76  4362.5  432.54  4454.2  432.38  4472.4  430.83
  4477.5  432.19  4523.4  429.33  4528.5  430.78  4546.0  429.41  4625.4  428.26
  4834.5  428.18  5001.2  426.01  5001.4  425.51  5005.3  426.01  5093.3  428.56
  5123.4  435.61  5133.4  439.38  5143.4  440.91  5393.7  443.89  5448.8  447.50
  5453.8  446.01  5468.8  446.88  5513.8  449.96  5543.8  452.81  5549.6  454.52
#Mann=5,-1,0
  3782.9    0.04       0  3828.2    0.05       0  5001.2    0.05       0
  5005.3    0.05       0  5468.8   0.013       0
Bank Sta=5001.2,5005.3
Exp/Cntr=0.3,0.1

Type RM Length L Ch R = 1,18791,569,569,569
BEGIN DESCRIPTION:
Mapping XS 7126d3f3
END DESCRIPTION:
XS GIS Cut Line= 3
      2395532.92     13561338.54      2394903.57     13561299.48
      2394196.10     13561104.16
#Sta/Elev= 30
  4234.2  441.64  4242.1  441.86  4272.2  439.51  4342.3  436.12  4382.4  435.66
  4472.6  431.74  4552.7  429.51  4642.9  427.80  4662.9  428.11  4673.0  427.40
  4852.3  426.35  4925.5  424.67  4946.3  425.27  4996.0  424.66  4996.3  424.16
  5000.2  424.66  5039.6  425.57  5092.5  429.15  5126.8  429.25  5153.8  430.29
  5319.7  438.09  5340.5  437.85  5380.7  440.39  5413.1  441.59  5433.9  443.22
  5467.1  443.70  5501.4  446.64  5527.2  446.79  5568.7  449.53  5598.7  450.45
#Mann=4,-1,0
  4234.2    0.05       0  4996.0    0.05       0  5000.2    0.05       0
  5380.7    0.03       0
Bank Sta=4996,5000.2
Exp/Cntr=0.3,0.1

Type RM Length L Ch R = 1,18222,536,536,536
BEGIN DESCRIPTION:
TRIB 4 TO THOMAS CREEK 33.0
END DESCRIPTION:
XS GIS Cut Line= 3
      2395424.98     13561274.98      2395025.00     13560875.00
      2394374.96     13560875.00
#Sta/Elev= 30
  4438.7  436.80  4707.4  428.76  4735.7  429.45  4763.9  431.91  4778.1  431.73
  4806.4  430.82  4834.7  427.20  4848.8  426.34  4961.9  421.69  4998.7  421.62
  4999.0  421.12  5003.0  421.62  5024.4  422.58  5034.4  424.75  5044.4  425.21
  5153.3  425.46  5234.4  427.38  5254.4  426.84  5364.4  430.61  5394.4  430.72
  5424.4  432.13  5514.4  433.92  5544.4  435.37  5564.4  437.32  5594.4  438.02
  5604.4  438.81  5614.4  441.47  5624.4  446.28  5651.9  454.06  5654.4  454.06
#Mann=4,-1,0
  4438.7    0.05       0  4998.7    0.05       0  5003.0    0.05       0
  5153.3    0.03       0
Bank Sta=4998.7,5003
Exp/Cntr=0.3,0.1

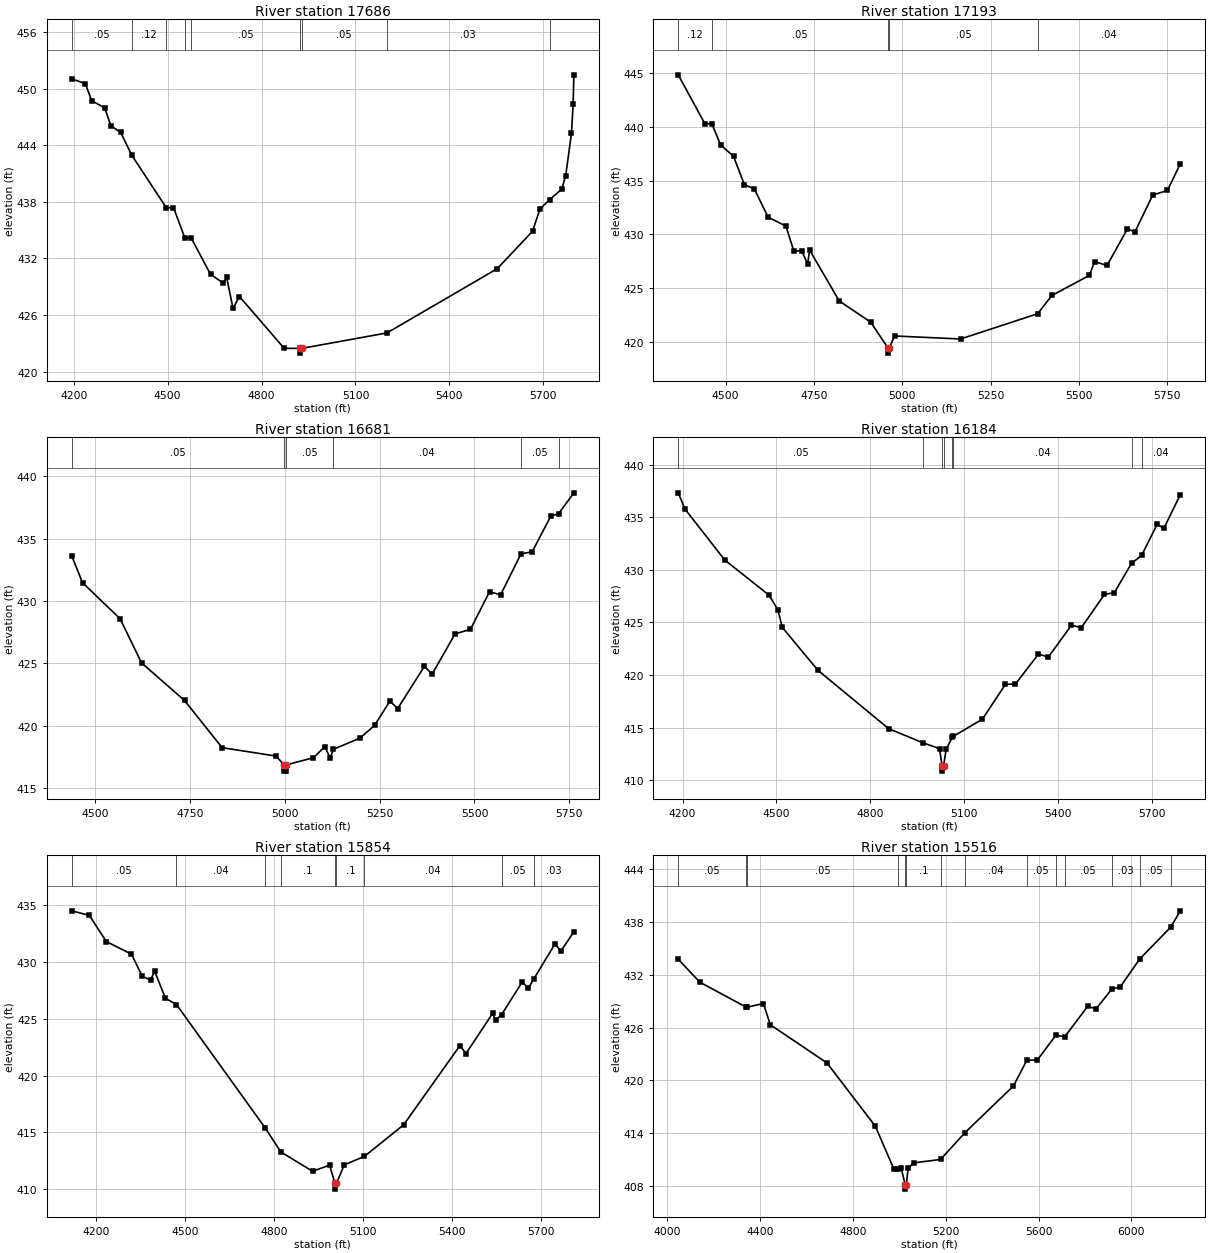
Type RM Length L Ch R = 1,17686,493,493,493
BEGIN DESCRIPTION:
Mapping XS 1e1c8f6b
END DESCRIPTION:
XS GIS Cut Line= 3
      2395867.14     13560622.40      2395146.62     13560457.46
      2394349.00     13560791.25
#Sta/Elev= 30
  4193.7  451.02  4236.9  450.52  4257.4  448.71  4298.8  447.95  4319.0  446.04
  4349.8  445.35  4385.6  442.92  4495.8  437.36  4518.6  437.39  4555.0  434.16
  4575.0  434.17  4637.0  430.31  4678.1  429.37  4688.3  430.00  4708.8  426.70
  4729.3  427.96  4872.2  422.47  4923.3  422.46  4923.6  421.96  4927.6  422.46
  5200.6  424.10  5552.5  430.90  5665.5  434.87  5689.3  437.24  5719.8  438.21
  5758.5  439.33  5771.5  440.76  5789.9  445.26  5795.3  448.34  5797.5  451.45
#Mann=9,-1,0
  4193.7    0.05       0  4385.6    0.12       0  4495.8    0.05       0
  4555.0    0.12       0  4575.0    0.05       0  4923.3    0.05       0
  4927.6    0.05       0  5200.6    0.03       0  5719.8   0.075       0
Bank Sta=4923.3,4927.6
Exp/Cntr=0.3,0.1

Type RM Length L Ch R = 1,17193,512,512,512
BEGIN DESCRIPTION:
TRIB 4 TO THOMAS CREEK 31.0
END DESCRIPTION:
XS GIS Cut Line= 3
      2395775.00     13560325.00      2395175.00     13560025.00
      2394575.02     13559575.02
#Sta/Elev= 30
  4366.2  444.79  4441.7  440.25  4461.3  440.26  4486.4  438.28  4522.7  437.25
  4553.5  434.60  4581.4  434.23  4620.6  431.60  4670.9  430.78  4693.2  428.47
  4715.6  428.49  4732.4  427.26  4738.0  428.56  4821.8  423.84  4911.2  421.87
  4959.2  419.51  4959.5  419.01  4964.0  419.51  4978.3  420.60  5165.2  420.32
  5383.3  422.66  5423.5  424.35  5529.7  426.21  5544.3  427.49  5579.7  427.13
  5637.0  430.50  5658.9  430.26  5708.9  433.65  5750.6  434.08  5787.0  436.55
#Mann=5,-1,0
  4366.2    0.12       0  4461.3    0.05       0  4959.2    0.05       0
  4964.0    0.05       0  5383.3    0.04       0
Bank Sta=4959.2,4964
Exp/Cntr=0.3,0.1

Type RM Length L Ch R = 1,16681,497,497,497
BEGIN DESCRIPTION:
TRIB 4 TO THOMAS CREEK 30.0
END DESCRIPTION:
XS GIS Cut Line= 3
      2395675.02     13559975.02      2395275.00     13559575.00
      2394524.95     13559474.99
#Sta/Elev= 30
  4439.3  433.60  4467.6  431.46  4566.6  428.57  4623.2  425.03  4736.3  422.02
  4835.3  418.24  4976.7  417.57  4999.1  416.86  4999.4  416.36  5003.5  416.36
  5003.9  416.86  5075.6  417.43  5105.9  418.32  5119.8  417.41  5128.3  418.11
  5198.0  419.00  5237.0  420.03  5277.4  421.98  5297.6  421.37  5368.2  424.76
  5388.4  424.13  5448.9  427.36  5489.3  427.72  5539.7  430.74  5568.7  430.48
  5622.5  433.77  5651.9  433.93  5701.1  436.80  5721.3  436.98  5761.7  438.66
#Mann=6,-1,0
  4439.3    0.05       0  4999.1    0.05       0  5003.9    0.05       0
  5128.3    0.04       0  5622.5    0.05       0  5721.3    0.04       0
Bank Sta=4999.1,5003.9
Exp/Cntr=0.3,0.1

Type RM Length L Ch R = 1,16184,330,330,330
BEGIN DESCRIPTION:
TRIB 4 TO THOMAS CREEK 29.0
END DESCRIPTION:
XS GIS Cut Line= 3
      2395924.97     13559674.97      2395325.00     13559125.00
      2394574.97     13559375.01
#Sta/Elev= 30
  4186.2  437.33  4207.4  435.80  4335.1  430.93  4476.3  427.60  4504.6  426.21
  4518.8  424.53  4632.3  420.46  4858.6  414.90  4967.7  413.56  5021.2  413.00
  5029.3  411.36  5029.6  410.86  5034.2  411.36  5042.3  412.93  5061.8  414.06
  5065.4  414.17  5158.2  415.80  5232.0  419.12  5263.6  419.14  5337.4  421.99
  5369.0  421.71  5442.8  424.74  5474.4  424.51  5548.2  427.66  5579.9  427.84
  5634.8  430.62  5667.3  431.39  5716.9  434.35  5738.0  433.94  5790.7  437.16
#Mann=8,-1,0
  4186.2    0.05       0  4967.7     0.1       0  5029.3    0.05       0
  5034.2     0.1       0  5061.8    0.05       0  5065.4    0.04       0
  5634.8    0.05       0  5667.3    0.04       0
Bank Sta=5029.3,5034.2
Exp/Cntr=0.3,0.1

Type RM Length L Ch R = 1,15854,338,338,338
BEGIN DESCRIPTION:
Mapping XS 66e25816
END DESCRIPTION:
XS GIS Cut Line= 3
      2396110.17     13559394.10      2395420.06     13558825.52
      2394621.41     13558868.92
#Sta/Elev= 30
  4117.1  434.45  4176.4  434.05  4233.8  431.75  4318.4  430.65  4355.0  428.71
  4382.9  428.36  4396.6  429.16  4433.2  426.77  4470.3  426.23  4770.5  415.37
  4822.6  413.29  4929.6  411.60  4987.0  412.13  5005.2  410.53  5005.6  410.03
  5010.2  410.53  5036.4  412.16  5104.3  412.90  5236.7  415.67  5426.9  422.63
  5447.0  421.92  5537.1  425.45  5547.1  424.84  5567.3  425.34  5637.3  428.22
  5657.3  427.64  5675.3  428.44  5747.4  431.55  5767.4  430.92  5811.1  432.60
#Mann=9,-1,0
  4117.1    0.05       0  4470.3    0.04       0  4770.5    0.05       0
  4822.6     0.1       0  5005.2    0.05       0  5010.2     0.1       0
  5104.3    0.04       0  5567.3    0.05       0  5675.3    0.03       0
Bank Sta=5005.2,5010.2
Exp/Cntr=0.3,0.1

Type RM Length L Ch R = 1,15516,299,299,299
BEGIN DESCRIPTION:
Mapping XS e9e75475
END DESCRIPTION:
XS GIS Cut Line= 4
      2396218.66     13559311.61      2395749.92     13558634.54
      2395085.86     13558547.74      2394448.93     13558751.38
#Sta/Elev= 30
  4048.5  433.77  4141.7  431.16  4341.8  428.32  4344.2  428.32  4415.2  428.74
  4444.9  426.33  4689.0  421.99  4897.1  414.81  4977.8  409.89  4994.0  409.89
  5008.1  410.10  5025.7  408.16  5026.1  407.66  5030.7  408.16  5038.3  410.04
  5062.4  410.64  5178.1  411.03  5283.7  414.09  5492.1  419.38  5549.4  422.29
  5595.1  422.33  5674.1  425.12  5713.3  424.98  5811.1  428.41  5848.5  428.15
  5915.0  430.38  5952.1  430.64  6035.3  433.79  6169.3  437.42  6210.4  439.27
#Mann=14,-1,0
  4048.5    0.05       0  4341.8    0.04       0  4344.2    0.05       0
  4994.0     0.1       0  5025.7    0.05       0  5030.7     0.1       0
  5178.1    0.05       0  5283.7    0.04       0  5549.4    0.05       0
  5674.1    0.04       0  5713.3    0.05       0  5915.0    0.03       0
  6035.3    0.05       0  6169.3    0.03       0
Bank Sta=5025.7,5030.7
Exp/Cntr=0.3,0.1

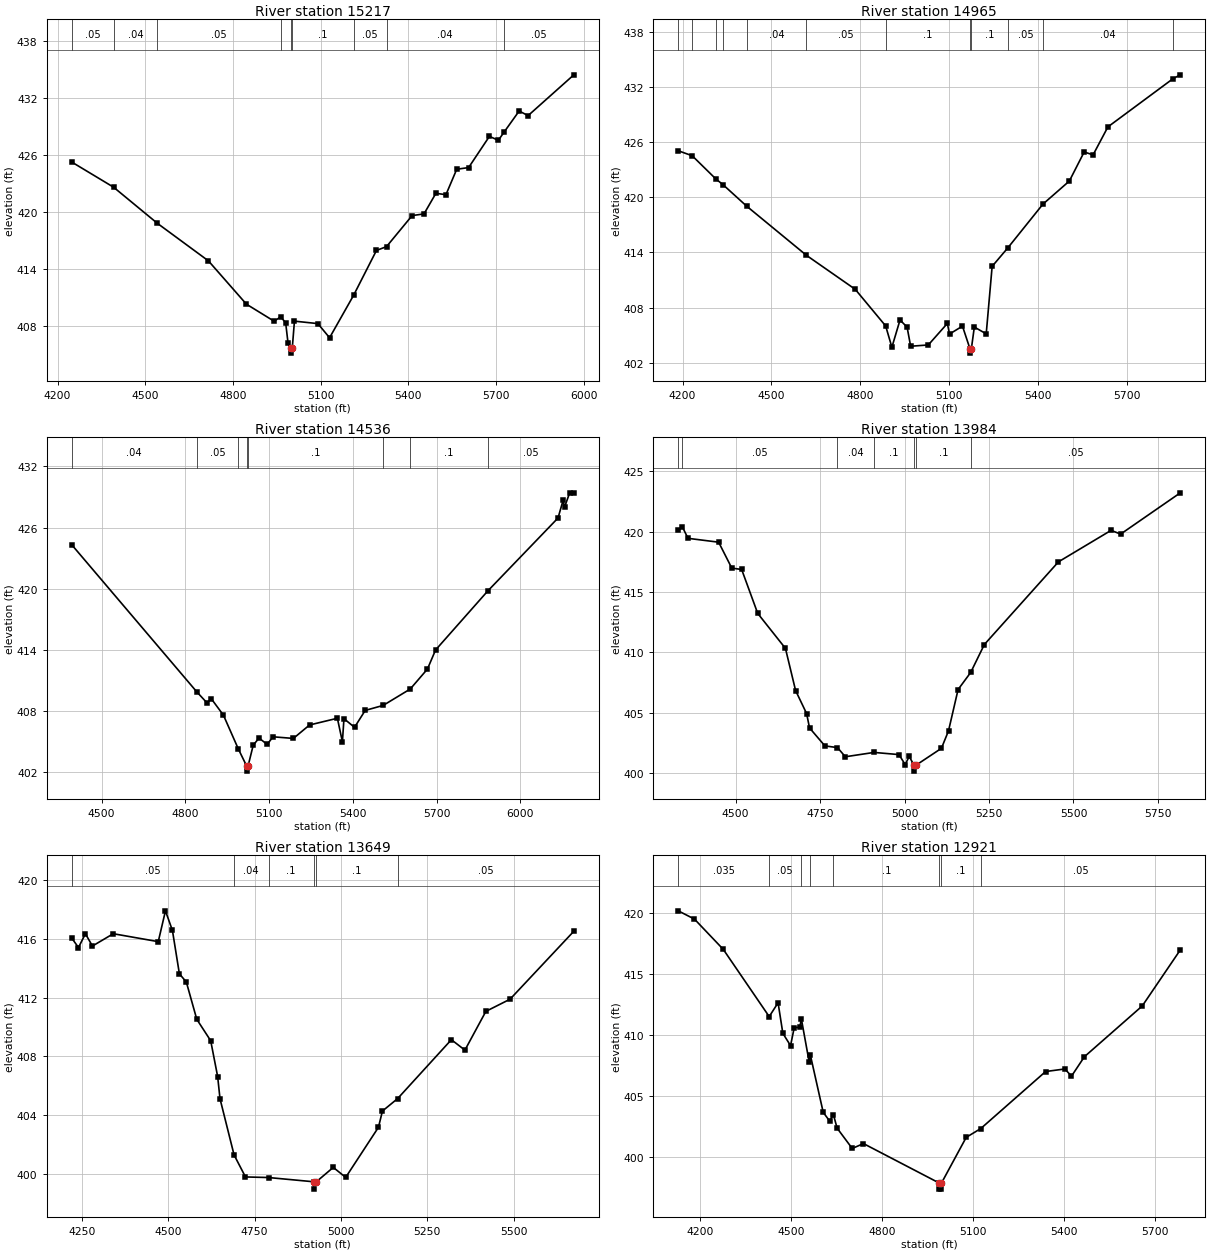
Type RM Length L Ch R = 1,15217,252,252,252
BEGIN DESCRIPTION:
Mapping XS b11736e1
END DESCRIPTION:
XS GIS Cut Line= 4
      2396275.10     13558686.63      2395671.80     13558322.04
      2395346.28     13558304.68      2394671.04     13558430.21
#Sta/Elev= 30
  4248.6  425.28  4391.7  422.63  4541.7  418.82  4716.1  414.87  4846.0  410.31
  4941.0  408.51  4963.1  408.97  4980.3  408.36  4988.6  406.18  4997.8  405.65
  4998.2  405.15  5002.9  405.65  5010.4  408.52  5090.5  408.26  5130.6  406.77
  5213.1  411.26  5291.0  415.97  5325.4  416.37  5413.0  419.64  5453.7  419.82
  5494.4  421.99  5528.7  421.84  5565.6  424.52  5606.3  424.70  5677.5  427.99
  5708.0  427.57  5726.8  428.40  5779.2  430.66  5809.7  430.17  5966.3  434.47
#Mann=9,-1,0
  4248.6    0.05       0  4391.7    0.04       0  4541.7    0.05       0
  4963.1     0.1       0  4997.8    0.05       0  5002.9     0.1       0
  5213.1    0.05       0  5325.4    0.04       0  5726.8    0.05       0
Bank Sta=4997.8,5002.9
Exp/Cntr=0.3,0.1

Type RM Length L Ch R = 1,14965,429,429,429
BEGIN DESCRIPTION:
Mapping XS 8b79cffc
END DESCRIPTION:
XS GIS Cut Line= 3
      2396361.93     13558565.12      2395576.31     13558052.95
      2394821.09     13558009.54
#Sta/Elev= 30
  4185.5  425.08  4232.5  424.54  4312.4  422.01  4336.5  421.39  4416.3  419.05
  4618.2  413.69  4782.8  409.99  4885.5  406.00  4906.5  403.68  4933.9  406.65
  4957.8  405.87  4969.8  403.79  5029.4  403.93  5093.6  406.27  5101.0  405.12
  5144.7  405.98  5169.7  403.54  5170.1  403.04  5174.8  403.54  5184.7  405.88
  5224.8  405.14  5244.8  412.49  5297.9  414.51  5416.3  419.27  5505.3  421.78
  5555.4  424.95  5585.4  424.63  5635.5  427.68  5854.8  432.92  5879.8  433.35
#Mann=12,-1,0
  4185.5    0.04       0  4232.5    0.05       0  4312.4    0.04       0
  4336.5    0.05       0  4416.3    0.04       0  4618.2    0.05       0
  4885.5     0.1       0  5169.7    0.05       0  5174.8     0.1       0
  5297.9    0.05       0  5416.3    0.04       0  5854.8    0.05       0
Bank Sta=5169.7,5174.8
Exp/Cntr=0.3,0.1

Type RM Length L Ch R = 1,14536,552,552,552
BEGIN DESCRIPTION:
Mapping XS c1644355
END DESCRIPTION:
XS GIS Cut Line= 3
      2396383.62     13558465.30      2395906.17     13557814.23
      2395515.55     13556902.78
#Sta/Elev= 30
  4392.9  424.31  4840.6  409.88  4877.8  408.78  4892.5  409.21  4936.4  407.58
  4989.8  404.26  5019.5  402.59  5019.9  402.09  5024.6  402.59  5043.0  404.63
  5063.8  405.34  5093.1  404.71  5114.0  405.46  5186.9  405.30  5244.9  406.62
  5344.6  407.28  5362.6  404.97  5368.2  407.24  5406.1  406.39  5444.3  408.05
  5508.6  408.54  5605.7  410.15  5667.3  412.11  5696.4  413.98  5883.3  419.77
  6135.2  426.94  6153.3  428.66  6158.7  428.01  6176.9  429.41  6191.9  429.41
#Mann=8,-1,0
  4392.9    0.04       0  4840.6    0.05       0  4989.8     0.1       0
  5019.5    0.05       0  5024.6     0.1       0  5508.6    0.05       0
  5605.7     0.1       0  5883.3    0.05       0
Bank Sta=5019.5,5024.6
Exp/Cntr=0.3,0.1

Type RM Length L Ch R = 1,13984,335,335,335
BEGIN DESCRIPTION:
Mapping XS 17154318
END DESCRIPTION:
XS GIS Cut Line= 3
      2396691.76     13558235.24      2396418.32     13557584.20
      2395849.87     13557050.45
#Sta/Elev= 30
  4330.3  420.13  4342.7  420.40  4359.2  419.46  4449.9  419.14  4488.8  416.99
  4518.0  416.88  4565.5  413.24  4647.6  410.34  4677.6  406.85  4710.2  404.94
  4718.9  403.75  4764.4  402.26  4801.6  402.12  4824.8  401.36  4909.9  401.72
  4983.6  401.54  5001.9  400.71  5013.9  401.39  5027.8  400.67  5028.3  400.17
  5034.5  400.67  5109.2  402.06  5130.2  403.51  5158.5  406.93  5195.9  408.35
  5236.2  410.66  5455.5  417.51  5611.3  420.12  5639.6  419.81  5816.2  423.23
#Mann=7,-1,0
  4330.3    0.04       0  4342.7    0.05       0  4801.6    0.04       0
  4909.9     0.1       0  5027.8    0.05       0  5034.5     0.1       0
  5195.9    0.05       0
Bank Sta=5027.8,5034.5
Exp/Cntr=0.3,0.1

Type RM Length L Ch R = 1,13649,728,728,728
BEGIN DESCRIPTION:
Mapping XS d20e0ebf
END DESCRIPTION:
XS GIS Cut Line= 3
      2396808.95     13558274.29      2396726.48     13557553.82
      2396440.02     13556885.39
#Sta/Elev= 30
  4221.4  416.05  4240.8  415.41  4260.9  416.35  4281.1  415.51  4341.5  416.35
  4471.6  415.81  4492.4  417.91  4512.6  416.57  4532.7  413.62  4552.8  413.06
  4583.0  410.52  4623.3  409.06  4643.4  406.62  4650.2  405.11  4690.9  401.28
  4723.9  399.78  4790.5  399.74  4921.7  399.45  4922.2  398.95  4928.8  399.45
  4977.9  400.43  5013.8  399.75  5108.5  403.16  5120.1  404.27  5164.1  405.12
  5319.5  409.13  5358.7  408.42  5419.3  411.06  5489.3  411.89  5673.8  416.52
#Mann=6,-1,0
  4221.4    0.05       0  4690.9    0.04       0  4790.5     0.1       0
  4921.7    0.05       0  4928.8     0.1       0  5164.1    0.05       0
Bank Sta=4921.7,4928.8
Exp/Cntr=0.3,0.1

Type RM Length L Ch R = 1,12921,377,377,377
BEGIN DESCRIPTION:
Mapping XS 166147ea
END DESCRIPTION:
XS GIS Cut Line= 3
      2397416.57     13558204.82      2397138.81     13557432.29
      2396584.43     13556808.61
#Sta/Elev= 30
  4127.9  420.14  4181.5  419.46  4276.5  416.98  4427.8  411.48  4457.1  412.61
  4472.8  410.11  4498.2  409.10  4510.3  410.57  4528.9  410.61  4533.7  411.31
  4559.6  407.77  4563.8  408.30  4605.9  403.64  4627.2  402.92  4639.5  403.45
  4651.8  402.34  4701.6  400.68  4738.6  401.08  4988.4  397.85  4988.9  397.35
  4995.4  397.35  4995.9  397.85  5077.4  401.59  5125.4  402.31  5339.2  406.98
  5402.7  407.19  5424.5  406.60  5467.0  408.19  5657.8  412.35  5783.3  416.94
#Mann=8,-1,0
  4127.9   0.035       0  4427.8    0.05       0  4533.7     0.1       0
  4563.8    0.05       0  4639.5     0.1       0  4988.4    0.05       0
  4995.9     0.1       0  5125.4    0.05       0
Bank Sta=4988.4,4995.9
Exp/Cntr=0.3,0.1

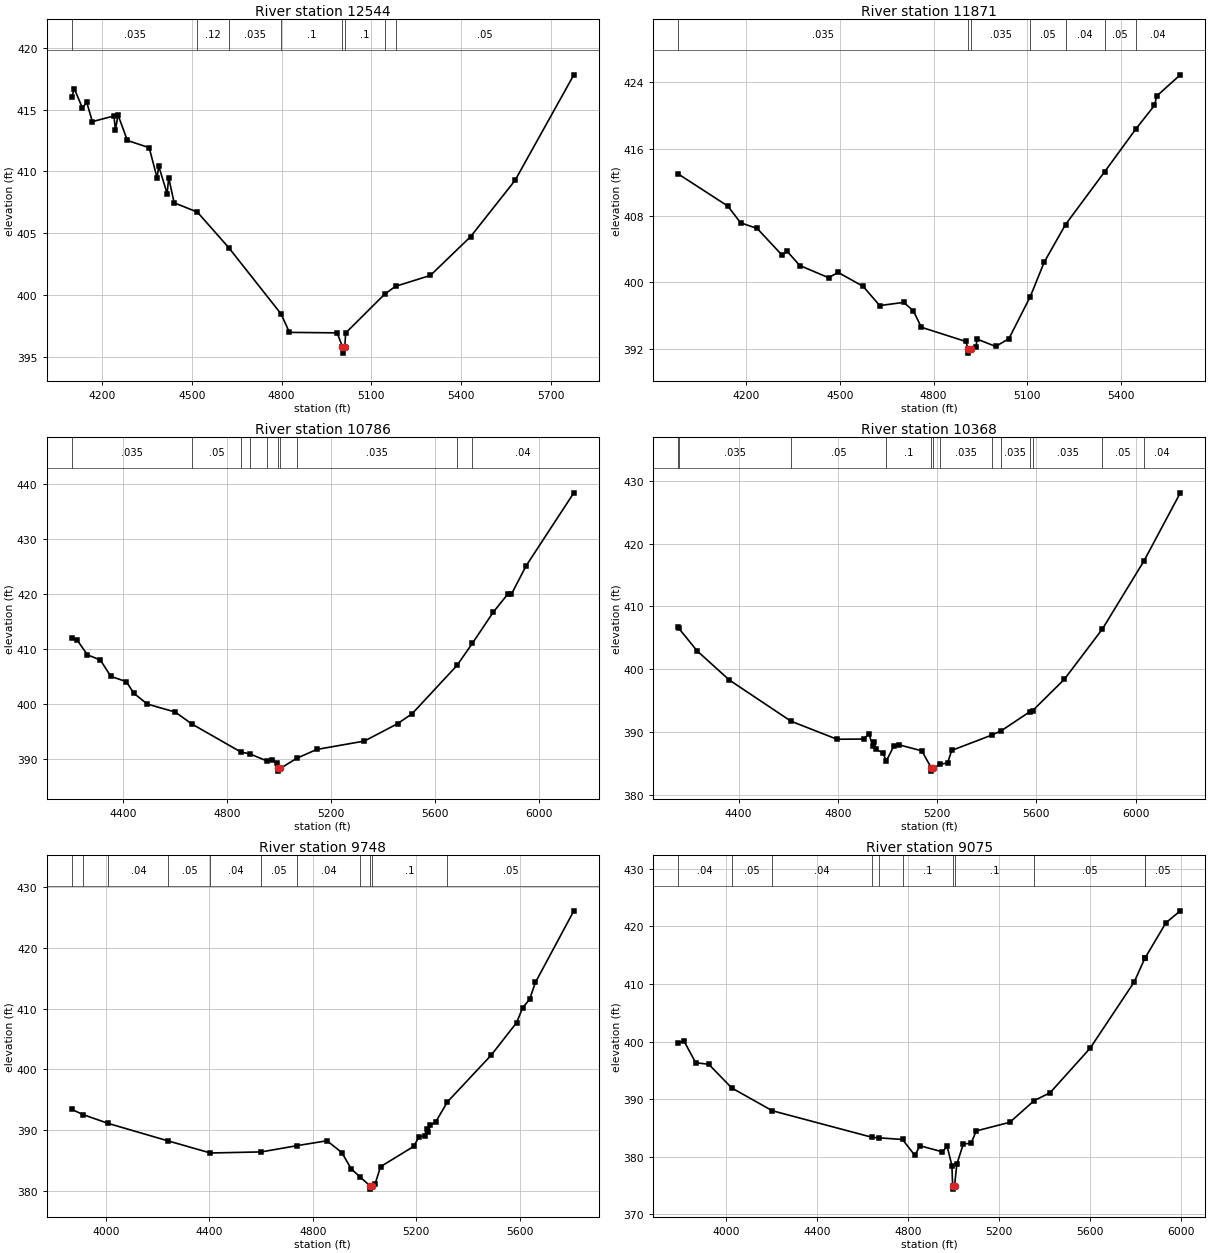
Type RM Length L Ch R = 1,12544,673,673,673
BEGIN DESCRIPTION:
Mapping XS 2fb73d10
END DESCRIPTION:
XS GIS Cut Line= 3
      2397690.02     13558083.31      2397446.97     13557250.00
      2396848.97     13556704.00
#Sta/Elev= 30
  4099.0  416.04  4107.7  416.67  4134.2  415.15  4149.3  415.57  4167.7  414.02
  4239.9  414.48  4245.1  413.33  4253.5  414.57  4284.7  412.50  4357.7  411.91
  4384.2  409.46  4389.5  410.43  4417.7  408.19  4422.9  409.49  4441.0  407.45
  4518.6  406.70  4623.2  403.83  4798.5  398.45  4826.4  396.96  4985.9  396.92
  5003.7  395.78  5004.2  395.28  5011.4  395.78  5014.3  396.91  5145.3  400.07
  5181.0  400.69  5297.4  401.57  5431.8  404.71  5580.5  409.27  5776.8  417.81
#Mann=8,-1,0
  4099.0   0.035       0  4518.6    0.12       0  4623.2   0.035       0
  4798.5     0.1       0  5003.7    0.05       0  5011.4     0.1       0
  5145.3   0.035       0  5181.0    0.05       0
Bank Sta=5003.7,5011.4
Exp/Cntr=0.3,0.1

Type RM Length L Ch R = 1,11871,1085,1085,1085
BEGIN DESCRIPTION:
Mapping XS c4e40d8c
END DESCRIPTION:
XS GIS Cut Line= 3
      2398202.18     13557853.29      2397872.32     13556928.82
      2397439.12     13556473.96
#Sta/Elev= 30
  3981.6  412.98  4140.6  409.13  4181.5  407.13  4234.6  406.45  4314.8  403.24
  4330.2  403.74  4371.1  402.01  4463.5  400.55  4494.3  401.18  4574.4  399.51
  4627.5  397.21  4704.7  397.59  4735.5  396.57  4761.0  394.61  4903.5  392.91
  4911.1  392.01  4911.6  391.51  4918.9  392.01  4935.2  392.27  4940.5  393.18
  4999.2  392.31  5041.7  393.24  5110.4  398.29  5154.9  402.41  5223.3  406.92
  5348.6  413.24  5448.6  418.36  5508.5  421.20  5515.7  422.32  5591.3  424.86
#Mann=7,-1,0
  3981.6   0.035       0  4911.1   0.035       0  4918.9   0.035       0
  5110.4    0.05       0  5223.3    0.04       0  5348.6    0.05       0
  5448.6    0.04       0
Bank Sta=4911.1,4918.9
Exp/Cntr=0.3,0.1

Type RM Length L Ch R = 1,10786,418,418,418
BEGIN DESCRIPTION:
TRIB 4 TO THOMAS CREEK 19.0
END DESCRIPTION:
XS GIS Cut Line= 3
      2398625.00     13557725.02      2398675.00     13556925.00
      2397874.97     13556124.97
#Sta/Elev= 30
  4202.8  411.86  4222.9  411.62  4262.9  408.90  4313.0  407.94  4353.1  404.97
  4413.2  404.01  4440.8  401.94  4493.4  399.94  4601.1  398.48  4665.9  396.29
  4854.4  391.20  4887.1  390.90  4953.0  389.61  4974.3  389.81  4994.4  389.18
  4997.8  388.24  4998.3  387.74  5005.9  388.24  5068.8  390.07  5145.8  391.68
  5329.7  393.21  5456.9  396.36  5513.5  398.19  5685.7  406.95  5745.4  410.99
  5824.6  416.59  5881.2  419.92  5895.3  419.90  5951.9  425.06  6135.8  438.35
#Mann=10,-1,0
  4202.8   0.035       0  4665.9    0.05       0  4854.4     0.1       0
  4887.1   0.035       0  4953.0     0.1       0  4997.8    0.05       0
  5005.9     0.1       0  5068.8   0.035       0  5685.7    0.05       0
  5745.4    0.04       0
Bank Sta=4997.8,5005.9
Exp/Cntr=0.3,0.1

Type RM Length L Ch R = 1,10368,620,620,620
BEGIN DESCRIPTION:
Mapping XS 34130696
END DESCRIPTION:
XS GIS Cut Line= 3
      2399122.32     13557640.62      2399161.38     13556980.90
      2398139.58     13556080.33
#Sta/Elev= 30
  4156.9  406.74  4159.7  406.49  4232.7  402.94  4362.9  398.29  4611.1  391.75
  4796.5  388.88  4904.7  388.91  4925.6  389.77  4939.9  387.78  4946.5  388.42
  4954.1  387.25  4982.5  386.70  4994.6  385.39  5025.2  387.76  5046.1  388.00
  5138.1  387.04  5176.8  384.31  5177.3  383.81  5184.9  384.31  5212.3  384.89
  5242.6  385.13  5258.6  387.10  5419.4  389.53  5457.2  390.20  5573.5  393.25
  5585.1  393.44  5712.1  398.39  5865.8  406.40  6034.0  417.27  6179.8  428.06
#Mann=13,-1,0
  4156.9    0.05       0  4159.7   0.035       0  4611.1    0.05       0
  4994.6     0.1       0  5176.8    0.05       0  5184.9     0.1       0
  5212.3   0.035       0  5419.4    0.05       0  5457.2   0.035       0
  5573.5    0.05       0  5585.1   0.035       0  5865.8    0.05       0
  6034.0    0.04       0
Bank Sta=5176.8,5184.9
Exp/Cntr=0.3,0.1

Type RM Length L Ch R = 1,9748,673,673,673
BEGIN DESCRIPTION:
Mapping XS 96e8dd88
END DESCRIPTION:
XS GIS Cut Line= 3
      2399344.14     13557334.48      2399326.31     13556529.51
      2398428.95     13555831.56
#Sta/Elev= 30
  3868.0  393.42  3911.1  392.57  4009.7  391.10  4242.1  388.22  4404.3  386.25
  4601.6  386.43  4739.8  387.46  4855.0  388.26  4912.9  386.31  4948.2  383.68
  4983.5  382.29  5022.9  380.81  5023.4  380.31  5031.1  380.81  5041.4  381.16
  5062.3  384.00  5190.8  387.34  5211.6  388.95  5232.4  389.06  5240.5  390.15
  5246.9  389.76  5255.0  390.79  5275.8  391.37  5321.0  394.65  5489.4  402.29
  5588.9  407.69  5611.5  410.10  5638.7  411.50  5661.3  414.28  5810.0  426.06
#Mann=11,-1,0
  3868.0   0.035       0  3911.1    0.05       0  4009.7    0.04       0
  4242.1    0.05       0  4404.3    0.04       0  4601.6    0.05       0
  4739.8    0.04       0  4983.5     0.1       0  5022.9    0.05       0
  5031.1     0.1       0  5321.0    0.05       0
Bank Sta=5022.9,5031.1
Exp/Cntr=0.3,0.1

Type RM Length L Ch R = 1,9075,513,513,513
BEGIN DESCRIPTION:
Mapping XS 3c6b8b3d
END DESCRIPTION:
XS GIS Cut Line= 4
      2399978.92     13557108.65      2399759.07     13556384.21
      2399262.76     13555845.58      2398589.23     13555587.96
#Sta/Elev= 30
  3787.8  399.69  3812.5  400.15  3864.8  396.33  3922.0  396.08  4023.1  391.97
  4201.4  388.01  4641.2  383.39  4672.1  383.30  4775.3  383.01  4830.0  380.23
  4851.6  381.93  4950.8  380.86  4971.8  381.82  4992.8  378.48  4996.0  374.89
  4996.5  374.39  5004.3  374.89  5014.3  378.70  5042.7  382.21  5077.8  382.38
  5099.4  384.49  5248.0  386.00  5355.1  389.77  5424.8  391.12  5601.1  398.85
  5795.5  410.37  5843.1  414.55  5844.5  414.61  5935.0  420.64  5998.4  422.72
#Mann=11,-1,0
  3787.8    0.04       0  4023.1    0.05       0  4201.4    0.04       0
  4641.2    0.03       0  4672.1    0.05       0  4775.3     0.1       0
  4996.0    0.05       0  5004.3     0.1       0  5355.1    0.05       0
  5843.1    0.03       0  5844.5    0.05       0
Bank Sta=4996,5004.3
Exp/Cntr=0.3,0.1

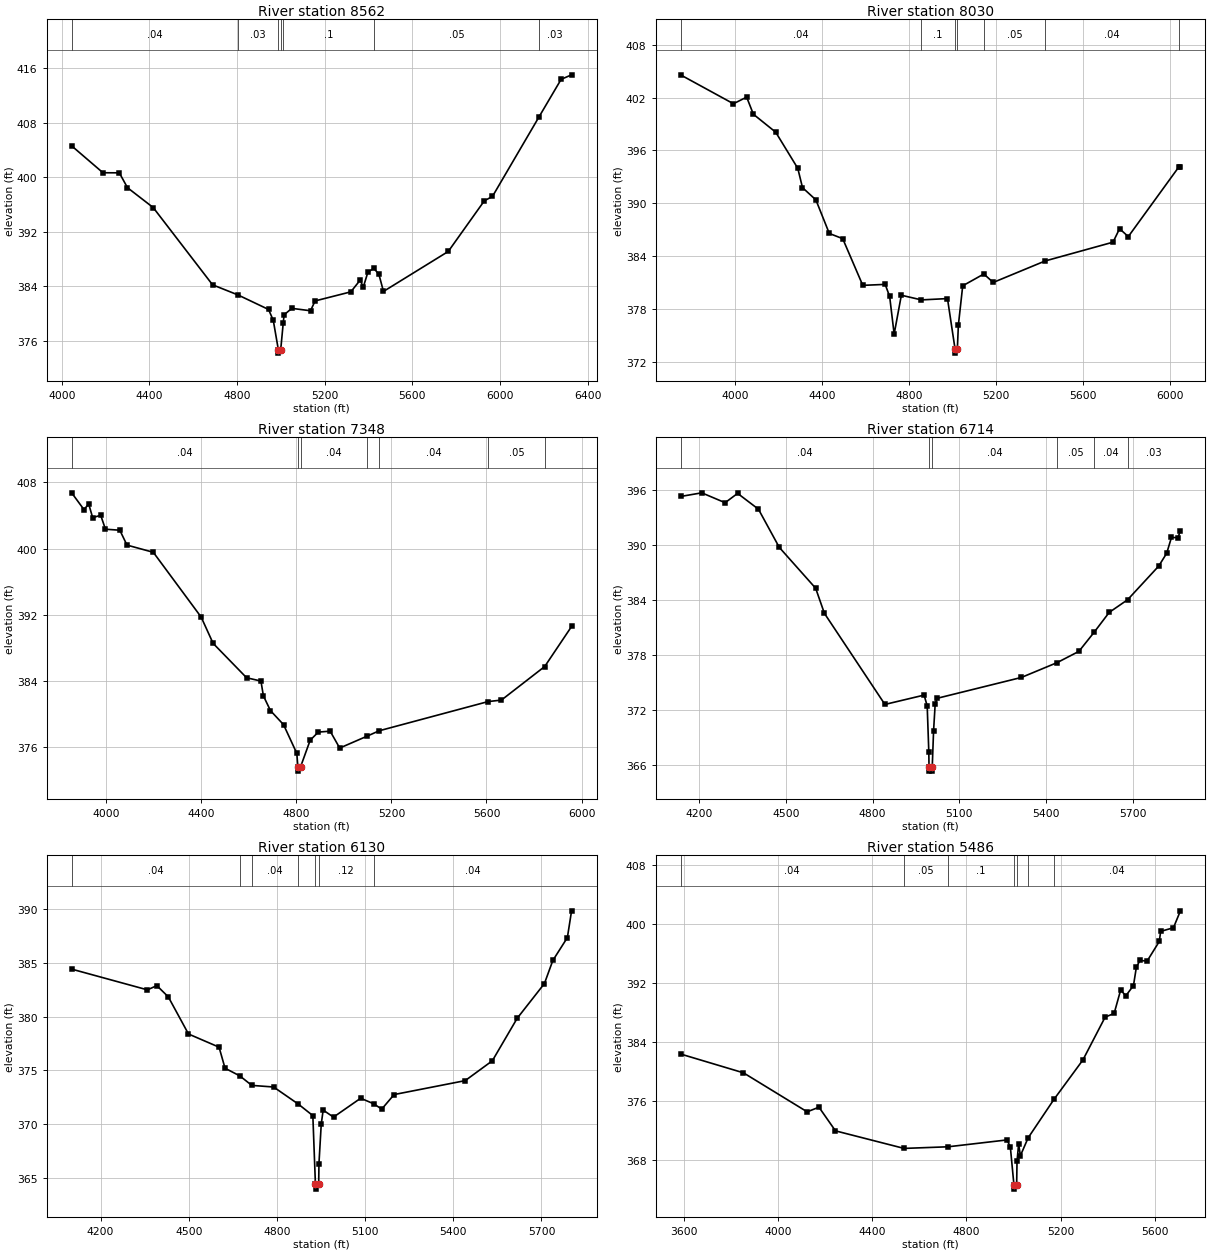
Type RM Length L Ch R = 1,8562,532,532,532
BEGIN DESCRIPTION:
Mapping XS 6b35fe05
END DESCRIPTION:
XS GIS Cut Line= 4
      2400246.45     13556989.58      2399955.65     13556182.29
      2399430.48     13555722.22      2398740.41     13555496.54
#Sta/Elev= 30
  4044.7  404.60  4187.7  400.66  4262.2  400.65  4299.6  398.47  4417.0  395.56
  4688.0  384.24  4803.8  382.76  4943.5  380.63  4965.2  379.03  4988.3  374.73
  4988.8  374.23  4999.1  374.73  5010.4  378.58  5014.6  379.85  5049.9  380.79
  5135.1  380.44  5156.2  381.88  5319.2  383.21  5361.9  384.93  5376.1  383.90
  5397.0  386.08  5423.8  386.66  5447.3  385.79  5468.2  383.27  5764.1  389.13
  5928.7  396.55  5965.8  397.19  6178.4  408.85  6279.3  414.35  6327.0  415.01
#Mann=7,-1,0
  4044.7    0.04       0  4803.8    0.03       0  4988.3    0.03       0
  4999.1    0.03       0  5010.4     0.1       0  5423.8    0.05       0
  6178.4    0.03       0
Bank Sta=4988.3,4999.1
Exp/Cntr=0.3,0.1

Type RM Length L Ch R = 1,8030,682,682,682
BEGIN DESCRIPTION:
Mapping XS 6288914f
END DESCRIPTION:
XS GIS Cut Line= 4
      2400354.95     13557011.27      2400150.96     13556147.57
      2400085.86     13555891.49      2400163.98     13554745.64
#Sta/Elev= 30
  3749.0  404.58  3992.5  401.30  4053.4  402.05  4084.2  400.11  4187.0  398.07
  4288.6  393.97  4310.3  391.78  4371.9  390.39  4433.6  386.58  4495.3  385.99
  4587.7  380.69  4690.7  380.80  4711.3  379.43  4732.0  375.16  4765.1  379.57
  4857.5  379.04  4977.4  379.19  5012.0  373.50  5012.5  373.00  5022.9  373.50
  5027.5  376.17  5047.5  380.64  5144.7  381.98  5187.8  381.02  5426.9  383.46
  5739.1  385.59  5769.2  387.12  5809.3  386.22  6042.3  394.14  6049.2  394.15
#Mann=7,-1,0
  3749.0    0.04       0  4857.5     0.1       0  5012.0    0.05       0
  5022.9     0.1       0  5144.7    0.05       0  5426.9    0.04       0
  6042.3    0.05       0
Bank Sta=5012,5022.9
Exp/Cntr=0.3,0.1

Type RM Length L Ch R = 1,7348,634,634,634
BEGIN DESCRIPTION:
Mapping XS a8da5a62
END DESCRIPTION:
XS GIS Cut Line= 3
      2400650.09     13556846.32      2400537.25     13555848.09
      2400576.31     13554749.97
#Sta/Elev= 30
  3854.6  406.75  3906.2  404.73  3926.4  405.39  3943.0  403.74  3976.7  404.04
  3996.8  402.35  4057.2  402.23  4087.4  400.43  4198.1  399.56  4399.4  391.73
  4449.7  388.55  4590.6  384.39  4651.0  383.99  4661.3  382.20  4691.2  380.41
  4746.1  378.72  4801.9  375.25  4806.4  373.60  4806.9  373.10  4817.5  373.60
  4858.2  376.84  4892.3  377.82  4942.3  377.93  4982.4  375.89  5097.0  377.32
  5148.5  377.98  5606.8  381.51  5662.8  381.69  5845.0  385.75  5958.0  390.59
#Mann=7,-1,0
  3854.6    0.04       0  4806.4    0.04       0  4817.5    0.04       0
  5097.0    0.05       0  5148.5    0.04       0  5606.8    0.05       0
  5845.0    0.03       0
Bank Sta=4806.4,4817.5
Exp/Cntr=0.3,0.1

Type RM Length L Ch R = 1,6714,584,584,584
BEGIN DESCRIPTION:
Mapping XS 28bd9126
END DESCRIPTION:
XS GIS Cut Line= 3
      2401166.59     13556277.80      2401053.74     13555457.46
      2400637.37     13554659.41
#Sta/Elev= 30
  4136.1  395.31  4209.6  395.71  4290.3  394.63  4333.5  395.65  4405.5  393.92
  4477.5  389.75  4603.3  385.28  4633.5  382.54  4842.7  372.58  4978.2  373.60
  4988.9  372.42  4994.5  367.37  4995.2  365.79  4995.7  365.29  5005.9  365.29
  5006.4  365.79  5011.0  369.73  5016.6  372.68  5023.3  373.25  5314.6  375.53
  5438.0  377.15  5513.3  378.38  5566.0  380.47  5618.1  382.64  5681.6  384.02
  5789.2  387.70  5816.9  389.11  5833.4  390.84  5855.5  390.80  5864.3  391.55
#Mann=6,-1,0
  4136.1    0.04       0  4995.2    0.04       0  5006.4    0.04       0
  5438.0    0.05       0  5566.0    0.04       0  5681.6    0.03       0
Bank Sta=4995.2,5006.4
Exp/Cntr=0.3,0.1

Type RM Length L Ch R = 1,6130,644,644,644
BEGIN DESCRIPTION:
Mapping XS 4f307afc
END DESCRIPTION:
XS GIS Cut Line= 3
      2401670.34     13556048.58      2401531.46     13555270.83
      2400949.29     13554570.84
#Sta/Elev= 30
  4101.9  384.39  4359.5  382.47  4391.7  382.86  4430.6  381.82  4499.3  378.38
  4603.3  377.16  4623.6  375.21  4673.9  374.50  4714.6  373.62  4788.9  373.47
  4873.2  371.88  4922.3  370.82  4931.0  364.51  4931.5  364.01  4942.2  364.51
  4943.1  366.38  4950.9  370.04  4957.4  371.33  4992.6  370.68  5085.0  372.43
  5129.7  371.91  5156.6  371.42  5198.7  372.77  5440.5  374.06  5532.9  375.90
  5617.5  379.84  5710.0  383.05  5738.6  385.19  5788.1  387.31  5802.4  389.79
#Mann=7,-1,0
  4101.9    0.04       0  4673.9     0.1       0  4714.6    0.04       0
  4873.2    0.12       0  4931.0    0.05       0  4942.2    0.12       0
  5129.7    0.04       0
Bank Sta=4931,4942.2
Exp/Cntr=0.3,0.1

Type RM Length L Ch R = 1,5486,584,584,584
BEGIN DESCRIPTION:
Mapping XS 226df0da
END DESCRIPTION:
XS GIS Cut Line= 4
      2401809.24     13556041.68      2401753.68     13554951.38
      2401489.79     13554673.61      2400920.35     13554368.05
#Sta/Elev= 30
  3587.2  382.39  3854.2  379.84  4124.6  374.55  4174.6  375.18  4244.7  371.97
  4535.6  369.59  4722.3  369.81  4972.6  370.74  4986.7  369.78  5002.1  364.57
  5002.6  364.07  5013.4  364.57  5015.0  367.84  5021.9  370.20  5029.2  368.59
  5062.1  371.02  5172.0  376.25  5294.5  381.58  5388.9  387.39  5427.1  387.89
  5454.7  391.06  5476.6  390.28  5509.1  391.67  5521.4  394.16  5536.7  395.08
  5566.8  394.98  5618.7  397.65  5624.4  399.01  5678.8  399.51  5708.3  401.80
#Mann=7,-1,0
  3587.2    0.04       0  4535.6    0.05       0  4722.3     0.1       0
  5002.1    0.05       0  5013.4     0.1       0  5062.1    0.03       0
  5172.0    0.04       0
Bank Sta=5002.1,5013.4
Exp/Cntr=0.3,0.1