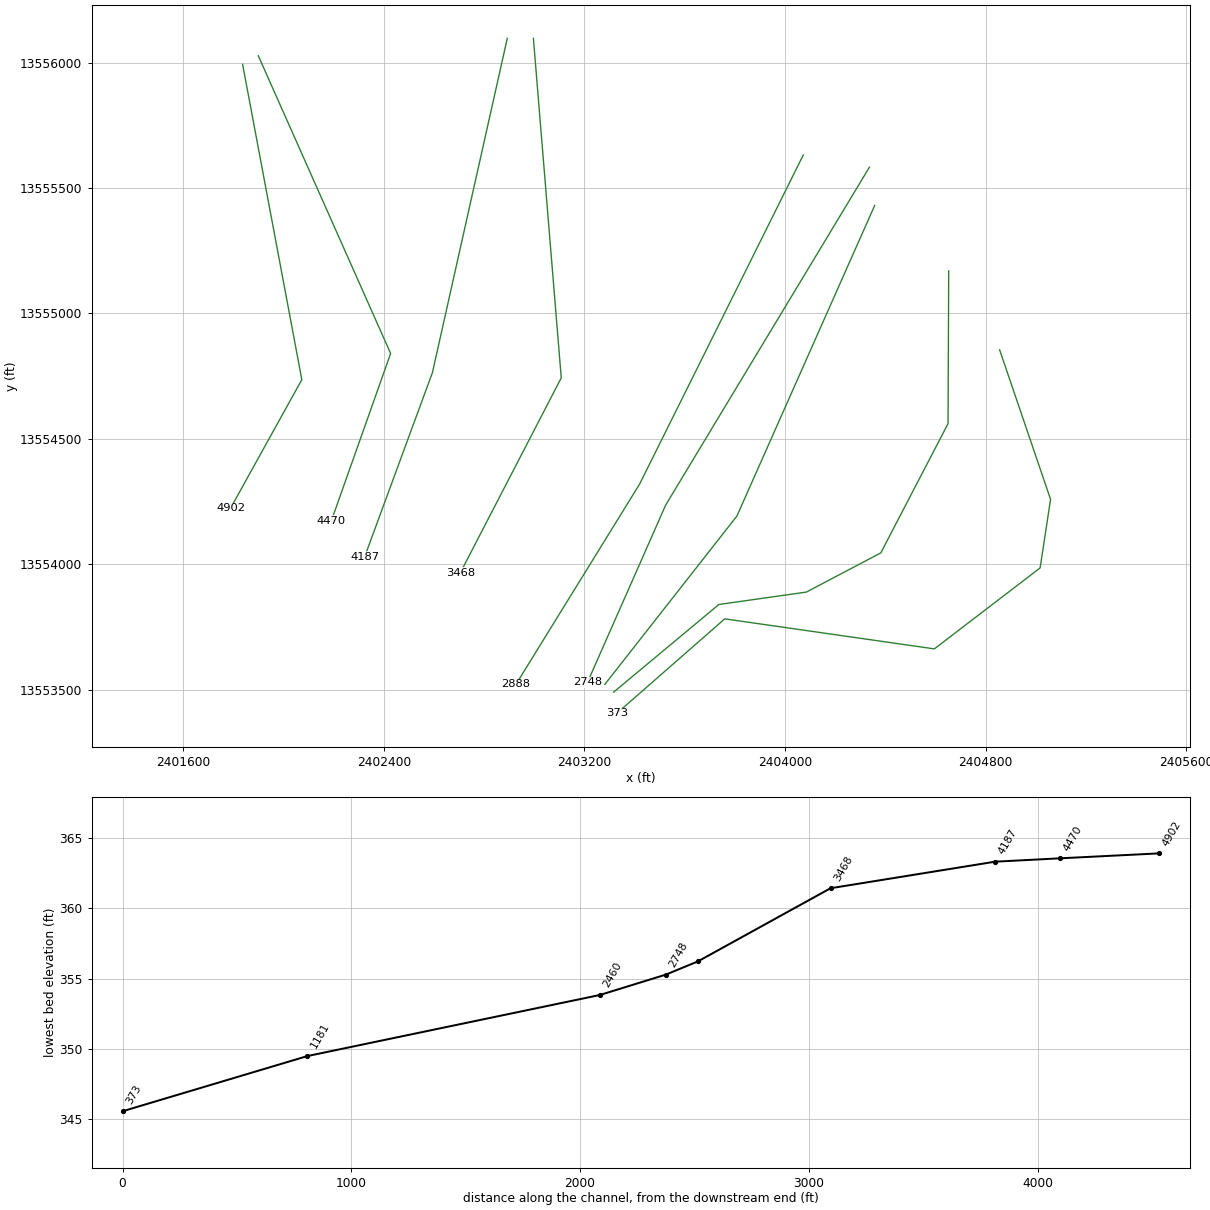
HEC-RAS study TRIB 4 TO THOMAS CREEK.prj: TRIB 4 TO THOMAS CREEK Base Level Engineering

--- TRIB 4 TO THOMAS CREEK.g01 (geometry) --- (continued)

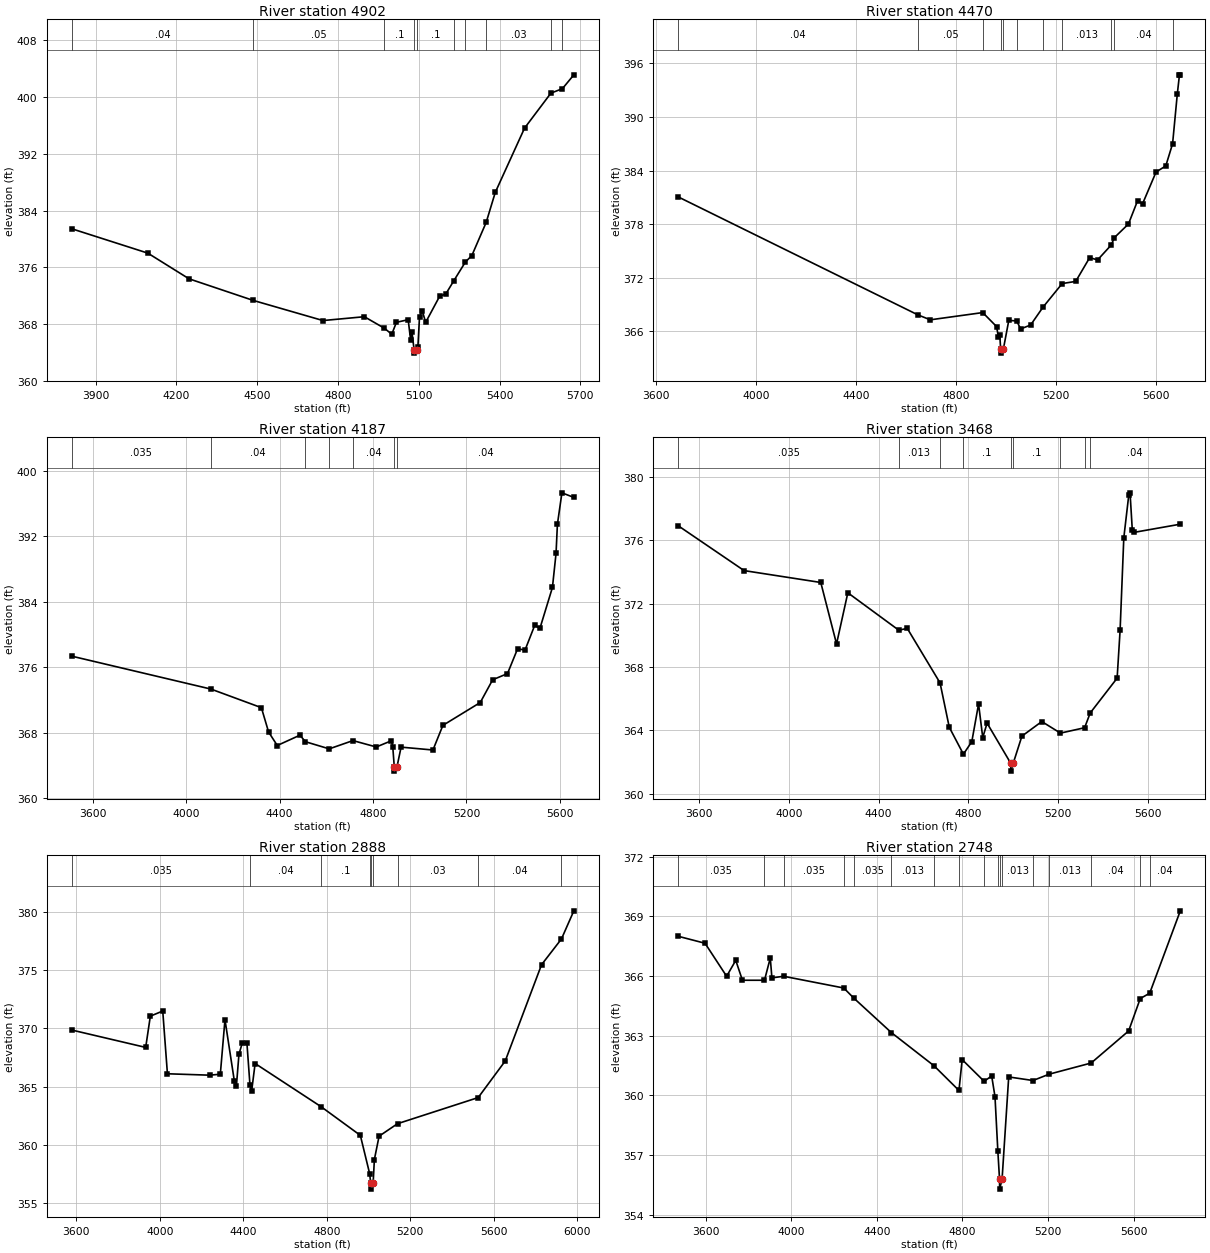
Type RM Length L Ch R = 1,4902,432,432,432
BEGIN DESCRIPTION:
Mapping XS 5ab53759
END DESCRIPTION:
XS GIS Cut Line= 3
      2401837.02     13555993.05      2402073.13     13554736.11
      2401789.19     13554223.64
#Sta/Elev= 30
  3811.2  381.43  4093.6  378.00  4246.7  374.38  4485.7  371.33  4744.2  368.50
  4897.9  369.04  4972.6  367.41  4999.7  366.57  5017.0  368.25  5060.7  368.62
  5069.5  365.83  5074.6  366.93  5082.5  364.41  5083.0  363.91  5093.8  364.41
  5096.8  364.80  5102.8  369.01  5112.9  369.86  5125.7  368.25  5178.1  371.96
  5199.9  372.21  5230.7  374.14  5273.4  376.76  5297.2  377.66  5350.4  382.33
  5384.2  386.56  5492.9  395.61  5590.8  400.54  5633.5  401.17  5676.0  403.12
#Mann=10,-1,0
  3811.2    0.04       0  4485.7    0.05       0  4972.6     0.1       0
  5082.5    0.05       0  5093.8     0.1       0  5230.7    0.03       0
  5273.4    0.12       0  5350.4    0.03       0  5590.8    0.12       0
  5633.5    0.03       0
Bank Sta=5082.5,5093.8
Exp/Cntr=0.3,0.1

Type RM Length L Ch R = 1,4470,283,283,283
BEGIN DESCRIPTION:
Mapping XS 8bc84470
END DESCRIPTION:
XS GIS Cut Line= 3
      2401899.52     13556027.76      2402427.29     13554840.27
      2402191.19     13554173.64
#Sta/Elev= 30
  3690.3  381.05  4648.4  367.84  4697.8  367.29  4907.3  368.10  4962.7  366.53
  4970.0  365.35  4975.5  365.58  4978.8  364.06  4979.3  363.56  4990.1  364.06
  5011.5  367.23  5042.9  367.16  5059.0  366.27  5098.8  366.71  5148.3  368.71
  5224.9  371.35  5278.9  371.59  5334.9  374.26  5366.2  373.99  5420.7  375.66
  5433.7  376.50  5489.8  378.02  5526.0  380.61  5546.3  380.29  5600.1  383.84
  5638.9  384.52  5666.1  387.00  5684.9  392.55  5693.6  394.72  5697.0  394.72
#Mann=11,-1,0
  3690.3    0.04       0  4648.4    0.05       0  4907.3    0.04       0
  4978.8    0.04       0  4990.1    0.04       0  5042.9   0.013       0
  5148.3    0.04       0  5224.9   0.013       0  5420.7    0.03       0
  5433.7    0.04       0  5666.1    0.03       0
Bank Sta=4978.8,4990.1
Exp/Cntr=0.3,0.1

Type RM Length L Ch R = 1,4187,719,719,719
BEGIN DESCRIPTION:
Mapping XS d2dd13ba
END DESCRIPTION:
XS GIS Cut Line= 3
      2402892.57     13556097.21      2402593.96     13554763.88
      2402323.54     13554028.90
#Sta/Elev= 30
  3510.6  377.36  4106.6  373.34  4322.4  371.07  4353.2  368.10  4390.4  366.45
  4487.4  367.71  4511.1  366.91  4612.8  366.04  4714.4  367.05  4814.3  366.27
  4879.0  367.03  4884.8  366.31  4891.4  363.82  4891.9  363.32  4902.7  363.82
  4920.5  366.25  5056.9  365.90  5099.5  368.91  5259.4  371.70  5312.6  374.48
  5376.0  375.23  5419.2  378.26  5451.2  378.11  5492.5  381.12  5515.1  380.78
  5568.4  385.75  5583.9  389.92  5589.7  393.46  5609.0  397.31  5660.1  396.75
#Mann=7,-1,0
  3510.6   0.035       0  4106.6    0.04       0  4511.1   0.013       0
  4612.8    0.05       0  4714.4    0.04       0  4891.4    0.04       0
  4902.7    0.04       0
Bank Sta=4891.4,4902.7
Exp/Cntr=0.3,0.1

Type RM Length L Ch R = 1,3468,580,580,580
BEGIN DESCRIPTION:
Mapping XS 2a18d8a5
END DESCRIPTION:
XS GIS Cut Line= 3
      2402996.74     13556097.25      2403107.85     13554743.05
      2402705.08     13553965.30
#Sta/Elev= 30
  3508.2  376.92  3801.4  374.09  4142.6  373.34  4212.8  369.46  4263.0  372.69
  4489.6  370.33  4527.6  370.44  4673.5  367.00  4714.5  364.20  4777.4  362.50
  4814.8  363.29  4844.9  365.67  4863.5  363.55  4882.8  364.46  4987.9  361.93
  4988.4  361.43  4999.2  361.93  5037.8  363.64  5126.3  364.56  5209.4  363.83
  5316.9  364.17  5341.7  365.10  5461.6  367.30  5474.8  370.32  5491.3  376.16
  5513.5  378.87  5519.1  379.00  5529.2  376.63  5535.6  376.50  5742.8  377.02
#Mann=9,-1,0
  3508.2   0.035       0  4489.6   0.013       0  4673.5    0.04       0
  4777.4     0.1       0  4987.9    0.05       0  4999.2     0.1       0
  5209.4    0.04       0  5316.9    0.03       0  5341.7    0.04       0
Bank Sta=4987.9,4999.2
Exp/Cntr=0.3,0.1

Type RM Length L Ch R = 1,2888,140,140,140
BEGIN DESCRIPTION:
Mapping XS aeb2ad30
END DESCRIPTION:
XS GIS Cut Line= 3
      2404073.14     13555631.97      2403420.35     13554319.44
      2402927.27     13553520.79
#Sta/Elev= 30
  3578.8  369.86  3932.8  368.37  3955.1  371.05  4014.5  371.49  4036.9  366.11
  4238.5  365.99  4290.2  366.07  4312.5  370.75  4357.2  365.51  4367.3  365.07
  4379.5  367.79  4395.3  368.74  4417.7  368.72  4432.3  365.12  4440.1  364.62
  4456.9  366.99  4772.6  363.29  4960.8  360.83  5005.6  357.53  5010.3  356.72
  5010.8  356.22  5022.1  356.72  5028.0  358.76  5050.6  360.76  5138.9  361.83
  5525.2  364.07  5654.8  367.21  5828.6  375.46  5924.0  377.67  5983.3  380.08
#Mann=9,-1,0
  3578.8   0.035       0  4432.3    0.04       0  4772.6     0.1       0
  5005.6    0.04       0  5010.3    0.05       0  5022.1    0.04       0
  5138.9    0.03       0  5525.2    0.04       0  5924.0    0.03       0
Bank Sta=5010.3,5022.1
Exp/Cntr=0.3,0.1

Type RM Length L Ch R = 1,2748,288,288,288
BEGIN DESCRIPTION:
Mapping XS 853fdb22
END DESCRIPTION:
XS GIS Cut Line= 3
      2404336.99     13555583.29      2403524.52     13554236.11
      2403212.51     13553528.90
#Sta/Elev= 30
  3472.0  367.99  3597.2  367.64  3698.1  365.98  3740.8  366.78  3771.9  365.78
  3875.1  365.78  3902.1  366.90  3909.7  365.90  3964.4  365.98  4245.5  365.39
  4292.7  364.88  4467.9  363.15  4667.3  361.48  4783.8  360.24  4798.8  361.79
  4901.5  360.70  4936.7  360.97  4952.2  359.93  4965.5  357.20  4973.4  355.78
  4973.9  355.28  4985.3  355.78  5016.3  360.92  5129.6  360.74  5205.8  361.06
  5401.6  361.62  5576.6  363.23  5631.0  364.86  5675.2  365.13  5818.2  369.27
#Mann=17,-1,0
  3472.0   0.035       0  3875.1   0.013       0  3964.4   0.035       0
  4245.5   0.013       0  4292.7   0.035       0  4467.9   0.013       0
  4667.3    0.04       0  4783.8   0.013       0  4901.5     0.1       0
  4965.5   0.013       0  4973.4    0.03       0  4985.3   0.013       0
  5129.6    0.04       0  5205.8   0.013       0  5401.6    0.04       0
  5631.0   0.013       0  5675.2    0.04       0
Bank Sta=4973.4,4985.3
Exp/Cntr=0.3,0.1

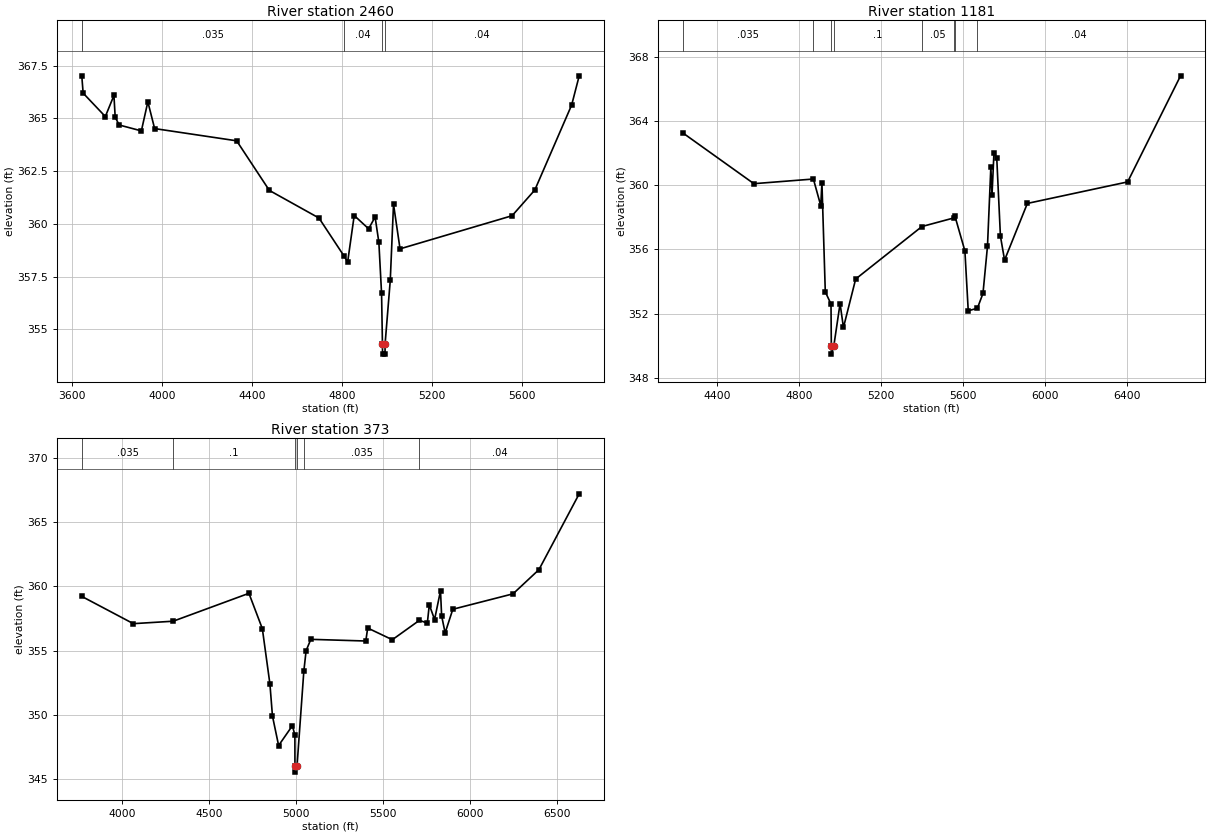
Type RM Length L Ch R = 1,2460,1279,1279,1279
BEGIN DESCRIPTION:
Mapping XS dd48c12a
END DESCRIPTION:
XS GIS Cut Line= 3
      2404357.84     13555430.52      2403808.39     13554191.81
      2403281.74     13553520.68
#Sta/Elev= 30
  3644.9  367.02  3650.9  366.20  3749.4  365.09  3787.6  366.09  3793.2  365.06
  3810.9  364.69  3909.4  364.41  3938.2  365.79  3968.2  364.52  4332.4  363.94
  4477.5  361.59  4697.9  360.28  4807.8  358.50  4825.2  358.20  4854.3  360.40
  4918.3  359.77  4947.0  360.33  4963.7  359.13  4975.7  356.71  4979.6  354.33
  4980.1  353.83  4991.0  353.83  4991.5  354.33  5014.3  357.32  5028.8  360.93
  5057.7  358.82  5555.2  360.39  5656.1  361.61  5819.7  365.64  5853.1  367.02
#Mann=4,-1,0
  3644.9   0.035       0  4807.8    0.04       0  4979.6    0.04       0
  4991.5    0.04       0
Bank Sta=4979.6,4991.5
Exp/Cntr=0.3,0.1

Type RM Length L Ch R = 1,1181,808,808,808
BEGIN DESCRIPTION:
Mapping XS b4b69634
END DESCRIPTION:
XS GIS Cut Line= 6
      2404653.12     13555169.92      2404650.52     13554560.56
      2404382.29     13554044.93      2404085.42     13553888.68
      2403736.46     13553839.20      2403316.77     13553489.67
#Sta/Elev= 30
  4234.4  363.25  4579.3  360.10  4869.4  360.39  4905.3  358.73  4911.0  360.16
  4927.4  353.36  4955.2  352.60  4956.8  349.98  4957.3  349.48  4968.8  349.98
  4999.4  352.63  5015.9  351.14  5075.5  354.16  5398.3  357.43  5555.3  357.97
  5559.3  358.08  5607.9  355.91  5624.2  352.18  5668.8  352.34  5696.0  353.26
  5718.0  356.20  5734.4  361.13  5740.1  359.40  5749.6  362.03  5763.2  361.70
  5781.1  356.83  5801.3  355.34  5912.4  358.87  6401.1  360.21  6659.1  366.82
#Mann=8,-1,0
  4234.4   0.035       0  4869.4     0.1       0  4956.8    0.05       0
  4968.8     0.1       0  5398.3    0.05       0  5555.3   0.035       0
  5559.3    0.05       0  5668.8    0.04       0
Bank Sta=4956.8,4968.8
Exp/Cntr=0.3,0.1

Type RM Length L Ch R = 1,373,0,0,0
BEGIN DESCRIPTION:
Mapping XS 6793bd2b
END DESCRIPTION:
XS GIS Cut Line= 6
      2404856.24     13554854.85      2405059.38     13554258.48
      2405017.71     13553985.04      2404595.83     13553662.12
      2403759.90     13553781.91      2403329.27     13553404.92
#Sta/Elev= 30
  3769.9  359.22  4065.8  357.10  4294.3  357.29  4729.1  359.46  4806.1  356.71
  4849.6  352.41  4864.2  349.91  4899.5  347.62  4978.4  349.16  4992.9  348.44
  4993.2  346.05  4993.7  345.55  5005.3  346.05  5044.2  353.40  5057.3  355.00
  5084.4  355.88  5399.9  355.75  5410.7  356.76  5552.1  355.85  5707.6  357.36
  5753.0  357.14  5764.3  358.57  5794.6  357.42  5828.6  359.66  5835.0  357.71
  5855.2  356.38  5899.2  358.22  6244.8  359.42  6393.4  361.30  6624.6  367.20
#Mann=6,-1,0
  3769.9   0.035       0  4294.3     0.1       0  4993.2    0.05       0
  5005.3     0.1       0  5044.2   0.035       0  5707.6    0.04       0
Bank Sta=4993.2,5005.3
Exp/Cntr=0.3,0.1

Chan Stop Cuts=-1