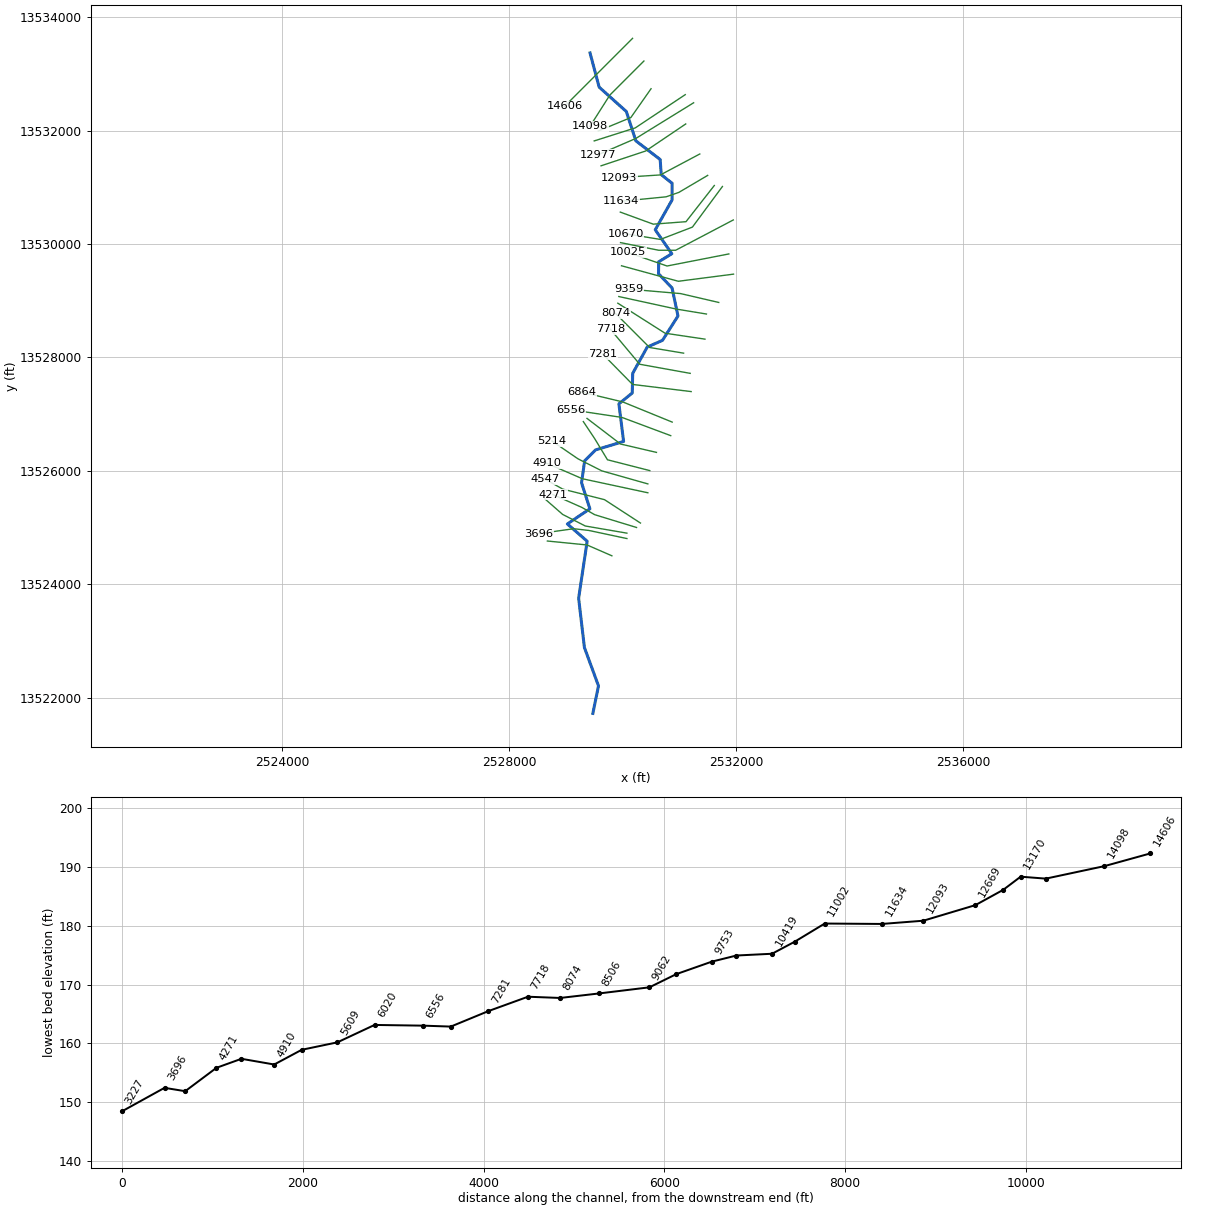
--- TRIB 4 TO TWELVEMILE CREEK.prj (project) ---

Proj Title=TRIB 4 TO TWELVEMILE CREEK Base Level Engineering
Current Plan=p01
Default Exp/Contr=0.3,0.1
English Units
Geom File=g01
Flow File=f01
Plan File=p01
BEGIN DESCRIPTION:
TRIB 4 TO TWELVEMILE CREEK
END DESCRIPTION:

--- TRIB 4 TO TWELVEMILE CREEK.p01 (plan) ---

Plan Title=Multiple Run
Short Identifier=Multiple
Geom File=g01
Flow File=f01
Subcritical Flow
K Sum by GR= 0
Std Step Tol= 0.01
Critical Tol= 0.01
Num of Std Step Trials= 20
Max Error Tol= 0.3
Flow Tol Ratio= 0.001
Split Flow NTrial= 30
Split Flow Tol= 0.02
Split Flow Ratio= 0.02
Log Output Level= 0
Friction Slope Method= 1
Unsteady Friction Slope Method= 2
Unsteady Bridges Friction Slope Method= 1
Parabolic Critical Depth
Global Vel Dist=  1 , 1 , 1
Global Log Level= 0
CheckData=True
Encroach Param= -1, 0, 0, 0
BEGIN DESCRIPTION:
Multiple Run
END DESCRIPTION:

--- TRIB 4 TO TWELVEMILE CREEK.f01 (steady flow) ---

Flow Title=Multiple
Number of Profiles=7
Profile Names=10-year,25-year,50-year,1pct_min,100-year,1pct_plu,500-year
River Rch & RM= TRIB 4 TO TWELVE,Reach-1,14606
     758    1228    1653    1078    2151    4291    3597
River Rch & RM= TRIB 4 TO TWELVE,Reach-1,13449
     792    1284    1730    1128    2250    4490    3766
River Rch & RM= TRIB 4 TO TWELVE,Reach-1,12093
     969    1586    2151    1411    2814    5615    4765
River Rch & RM= TRIB 4 TO TWELVE,Reach-1,9753
    1180    1950    2662    1755    3502    6988    5999
River Rch & RM= TRIB 4 TO TWELVE,Reach-1,7281
    1386    2310    3170    2100    4190    8359    7245
River Rch & RM= TRIB 4 TO TWELVE,Reach-1,6020
    1563    2617    3604    2395    4778    9534    8314
River Rch & RM= TRIB 4 TO TWELVE,Reach-1,2672
    1608    2695    3712    2467    4922    9820    8568
Boundary for River Rch & Prof#=TRIB 4 TO TWELVE,Reach-1,1
Up Type=0
Dn Type=3
Dn Slope=0.005
Boundary for River Rch & Prof#=TRIB 4 TO TWELVE,Reach-1,2
Up Type=0
Dn Type=3
Dn Slope=0.005
Boundary for River Rch & Prof#=TRIB 4 TO TWELVE,Reach-1,3
Up Type=0
Dn Type=3
Dn Slope=0.005
Boundary for River Rch & Prof#=TRIB 4 TO TWELVE,Reach-1,4
Up Type=0
Dn Type=3
Dn Slope=0.005
Boundary for River Rch & Prof#=TRIB 4 TO TWELVE,Reach-1,5
Up Type=0
Dn Type=3
Dn Slope=0.005
Boundary for River Rch & Prof#=TRIB 4 TO TWELVE,Reach-1,6
Up Type=0
Dn Type=3
Dn Slope=0.005
Boundary for River Rch & Prof#=TRIB 4 TO TWELVE,Reach-1,7
Up Type=0
Dn Type=3
Dn Slope=0.005

--- TRIB 4 TO TWELVEMILE CREEK.g01 (geometry) ---

Geom Title=Existing Conditions

River Reach=TRIB 4 TO TWELVE,Reach-1
Reach XY= 30
      2529425.00     13533368.01      2529586.11     13532764.92
      2530064.93     13532335.00      2530232.70     13531818.53
      2530661.78     13531488.67      2530680.36     13531222.30
      2530872.95     13531069.16      2530871.46     13530776.46
      2530574.67     13530249.79      2530867.17     13529828.22
      2530635.94     13529685.43      2530632.53     13529474.99
      2530871.55     13529223.75      2530975.83     13528730.02
      2530702.34     13528300.98      2530432.75     13528181.46
      2530177.23     13527719.07      2530169.49     13527372.56
      2529934.12     13527181.76      2530017.19     13526518.79
      2529522.57     13526369.48      2529330.52     13526177.43
      2529275.51     13525790.21      2529422.95     13525330.84
      2529025.55     13525064.36      2529374.52     13524759.80
      2529224.40     13523754.95      2529326.22     13522885.50
      2529574.48     13522209.78      2529475.00     13521725.00

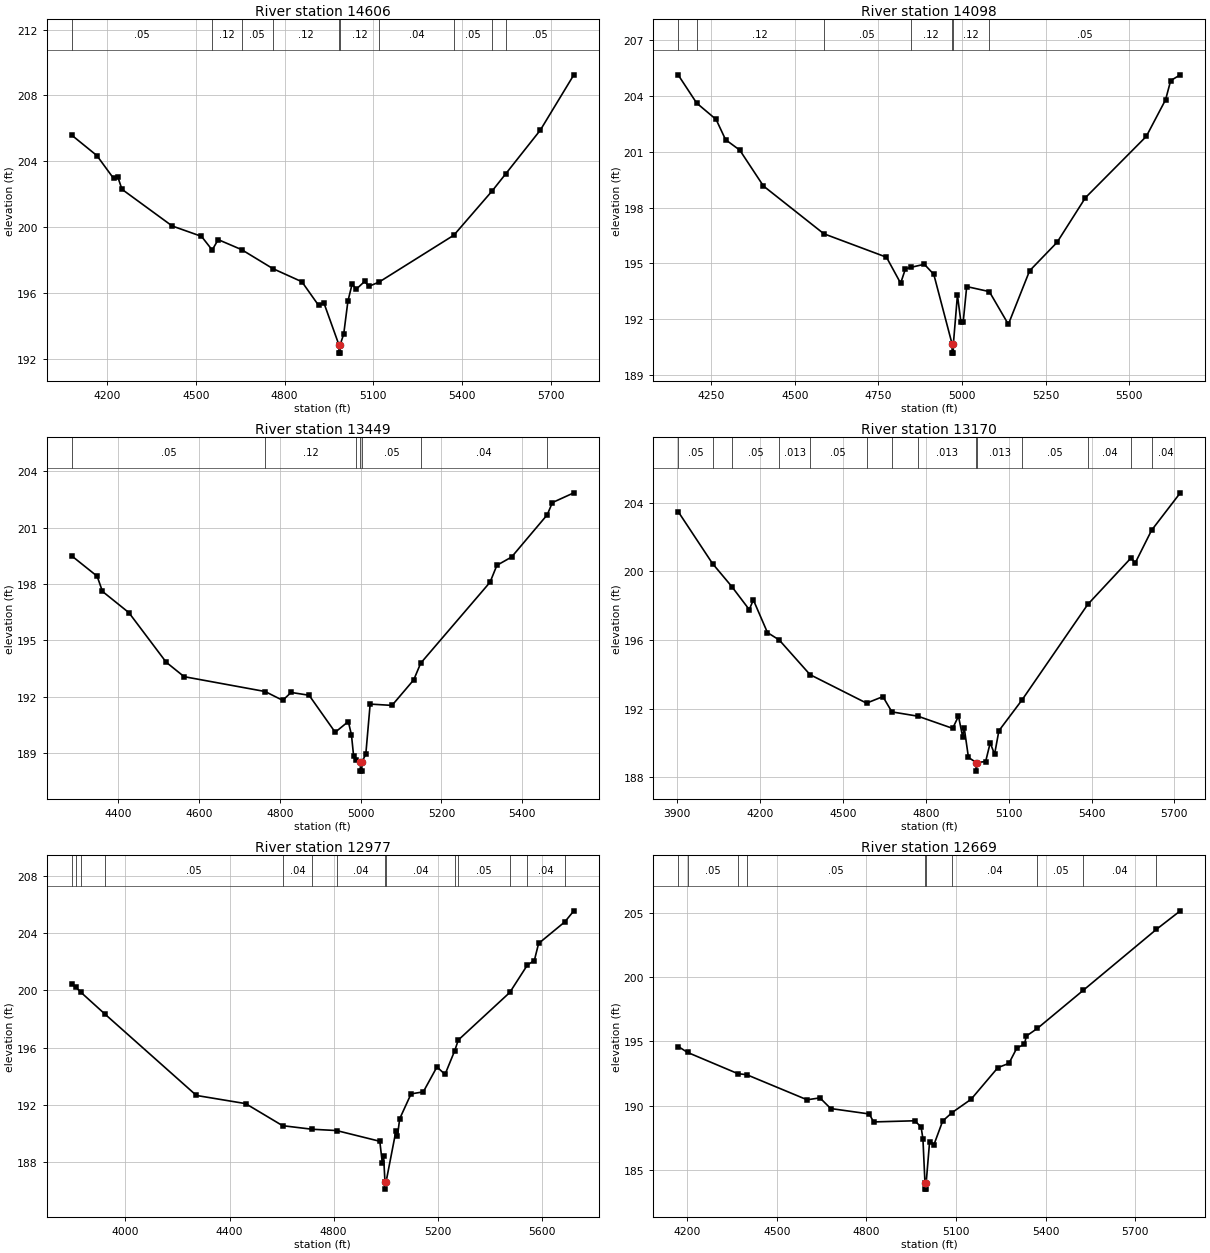
Type RM Length L Ch R = 1,14606,508,508,508
BEGIN DESCRIPTION:
TRIB 4 TO TWELVEMILE CREEK 31.0
END DESCRIPTION:
XS GIS Cut Line= 3
      2530175.01     13533625.01      2529575.00     13533025.00
      2528974.98     13532424.98
#Sta/Elev= 30
  4080.5  205.58  4165.4  204.34  4221.9  202.95  4236.1  203.04  4250.2  202.29
  4419.9  200.06  4518.9  199.43  4555.1  198.60  4575.5  199.23  4654.8  198.62
  4760.0  197.47  4858.3  196.67  4914.9  195.23  4932.6  195.39  4983.6  192.83
  4983.9  192.33  4987.4  192.33  4987.6  192.83  4999.8  193.50  5013.9  195.49
  5028.0  196.52  5042.2  196.22  5070.5  196.69  5084.6  196.39  5119.2  196.65
  5372.0  199.50  5501.9  202.20  5548.2  203.25  5664.4  205.89  5777.6  209.25
#Mann=10,-1,0
  4080.5    0.05       0  4555.1    0.12       0  4654.8    0.05       0
  4760.0    0.12       0  4983.6    0.05       0  4987.6    0.12       0
  5119.2    0.04       0  5372.0    0.05       0  5501.9    0.12       0
  5548.2    0.05       0
Bank Sta=4983.6,4987.6
Exp/Cntr=0.3,0.1

Type RM Length L Ch R = 1,14098,649,649,649
BEGIN DESCRIPTION:
TRIB 4 TO TWELVEMILE CREEK 30.0
END DESCRIPTION:
XS GIS Cut Line= 3
      2530375.02     13533225.02      2529775.00     13532625.00
      2529424.99     13532074.98
#Sta/Elev= 30
  4151.9  205.13  4207.0  203.62  4265.1  202.74  4293.4  201.65  4335.8  201.09
  4406.5  199.16  4587.1  196.59  4774.2  195.33  4816.6  193.93  4830.8  194.70
  4846.3  194.78  4887.3  194.95  4915.6  194.41  4970.2  190.67  4970.4  190.17
  4973.9  190.17  4974.2  190.67  4986.3  193.29  4996.9  191.82  5003.4  191.82
  5014.0  193.75  5081.6  193.48  5138.5  191.72  5202.0  194.60  5284.1  196.13
  5368.8  198.53  5550.8  201.83  5608.4  203.80  5623.6  204.83  5652.4  205.14
#Mann=7,-1,0
  4151.9    0.05       0  4207.0    0.12       0  4587.1    0.05       0
  4846.3    0.12       0  4970.2    0.05       0  4974.2    0.12       0
  5081.6    0.05       0
Bank Sta=4970.2,4974.2
Exp/Cntr=0.3,0.1

Type RM Length L Ch R = 1,13449,279,279,279
BEGIN DESCRIPTION:
Mapping XS acb67c52
END DESCRIPTION:
XS GIS Cut Line= 3
      2530500.67     13532736.42      2530144.79     13532228.64
      2529568.86     13531990.47
#Sta/Elev= 30
  4284.5  199.50  4347.3  198.42  4360.5  197.61  4425.9  196.48  4518.3  193.84
  4562.7  193.07  4763.2  192.28  4806.8  191.81  4827.7  192.23  4872.2  192.08
  4936.8  190.11  4969.3  190.68  4977.1  189.97  4982.5  188.83  4989.0  188.65
  4999.0  188.54  4999.3  188.04  5002.8  188.04  5003.0  188.54  5012.6  188.93
  5023.4  191.61  5077.5  191.54  5131.3  192.90  5148.6  193.79  5320.3  198.10
  5337.2  199.00  5373.6  199.44  5461.9  201.69  5474.6  202.34  5527.8  202.86
#Mann=7,-1,0
  4284.5    0.05       0  4763.2    0.12       0  4989.0    0.05       0
  4999.0    0.05       0  5003.0    0.05       0  5148.6    0.04       0
  5461.9    0.05       0
Bank Sta=4999,5003
Exp/Cntr=0.3,0.1

Type RM Length L Ch R = 1,13170,193,193,193
BEGIN DESCRIPTION:
Mapping XS 9e877549
END DESCRIPTION:
XS GIS Cut Line= 3
      2531103.99     13532632.28      2530222.92     13532046.35
      2529499.01     13531816.61
#Sta/Elev= 30
  3903.9  203.48  4028.0  200.46  4097.8  199.12  4160.9  197.78  4175.9  198.34
  4226.9  196.44  4269.4  196.01  4381.0  193.99  4585.6  192.33  4644.8  192.71
  4677.4  191.82  4771.5  191.57  4897.4  190.86  4918.4  191.57  4933.4  190.38
  4939.4  190.87  4954.5  189.17  4982.5  188.87  4982.8  188.37  4986.6  188.87
  5016.8  188.93  5033.3  190.02  5049.1  189.35  5064.7  190.72  5147.8  192.50
  5386.4  198.08  5543.9  200.80  5557.8  200.48  5617.5  202.40  5721.5  204.58
#Mann=14,-1,0
  3903.9    0.05       0  4028.0   0.013       0  4097.8    0.05       0
  4269.4   0.013       0  4381.0    0.05       0  4585.6   0.013       0
  4677.4    0.05       0  4771.5   0.013       0  4982.5    0.03       0
  4986.6   0.013       0  5147.8    0.05       0  5386.4    0.04       0
  5543.9    0.05       0  5617.5    0.04       0
Bank Sta=4982.5,4986.6
Exp/Cntr=0.3,0.1

Type RM Length L Ch R = 1,12977,308,308,308
BEGIN DESCRIPTION:
Mapping XS 6690655f
END DESCRIPTION:
XS GIS Cut Line= 3
      2531251.59     13532489.08      2530231.60     13531859.72
      2529560.63     13531569.69
#Sta/Elev= 30
  3793.8  200.46  3808.9  200.24  3827.8  199.89  3922.5  198.33  4272.8  192.67
  4462.0  192.10  4603.9  190.56  4717.5  190.31  4811.3  190.22  4977.6  189.47
  4987.1  187.97  4992.1  188.42  4997.5  186.63  4997.7  186.13  5001.6  186.63
  5039.8  190.21  5045.3  189.82  5054.0  191.04  5097.7  192.78  5144.7  192.92
  5197.2  194.66  5228.3  194.14  5265.4  195.79  5279.2  196.54  5477.1  199.86
  5544.9  201.78  5571.4  202.09  5587.8  203.28  5688.7  204.79  5723.3  205.56
#Mann=14,-1,0
  3793.8    0.04       0  3808.9    0.05       0  3827.8    0.04       0
  3922.5    0.05       0  4603.9    0.04       0  4717.5    0.05       0
  4811.3    0.04       0  4997.5    0.04       0  5001.6    0.04       0
  5265.4   0.013       0  5279.2    0.05       0  5477.1   0.013       0
  5544.9    0.04       0  5688.7   0.013       0
Bank Sta=4997.5,5001.6
Exp/Cntr=0.3,0.1

Type RM Length L Ch R = 1,12669,576,576,576
BEGIN DESCRIPTION:
Mapping XS 40b2937a
END DESCRIPTION:
XS GIS Cut Line= 3
      2531112.64     13532115.77      2530405.21     13531638.36
      2529619.79     13531378.00
#Sta/Elev= 30
  4170.2  194.61  4201.4  194.15  4369.9  192.50  4399.5  192.42  4601.7  190.47
  4644.6  190.62  4680.6  189.79  4809.5  189.37  4824.5  188.75  4962.3  188.84
  4983.3  188.35  4989.4  187.44  4996.2  184.03  4996.5  183.53  5000.1  183.53
  5000.3  184.03  5011.8  187.23  5026.4  186.99  5055.5  188.82  5087.2  189.48
  5150.6  190.51  5240.4  192.97  5277.3  193.30  5303.8  194.49  5329.4  194.79
  5335.5  195.42  5372.8  196.02  5526.9  198.99  5771.1  203.71  5851.1  205.15
#Mann=10,-1,0
  4170.2    0.04       0  4201.4    0.05       0  4369.9    0.04       0
  4399.5    0.05       0  4996.2    0.05       0  5000.3    0.05       0
  5087.2    0.04       0  5372.8    0.05       0  5526.9    0.04       0
  5771.1    0.05       0
Bank Sta=4996.2,5000.3
Exp/Cntr=0.3,0.1

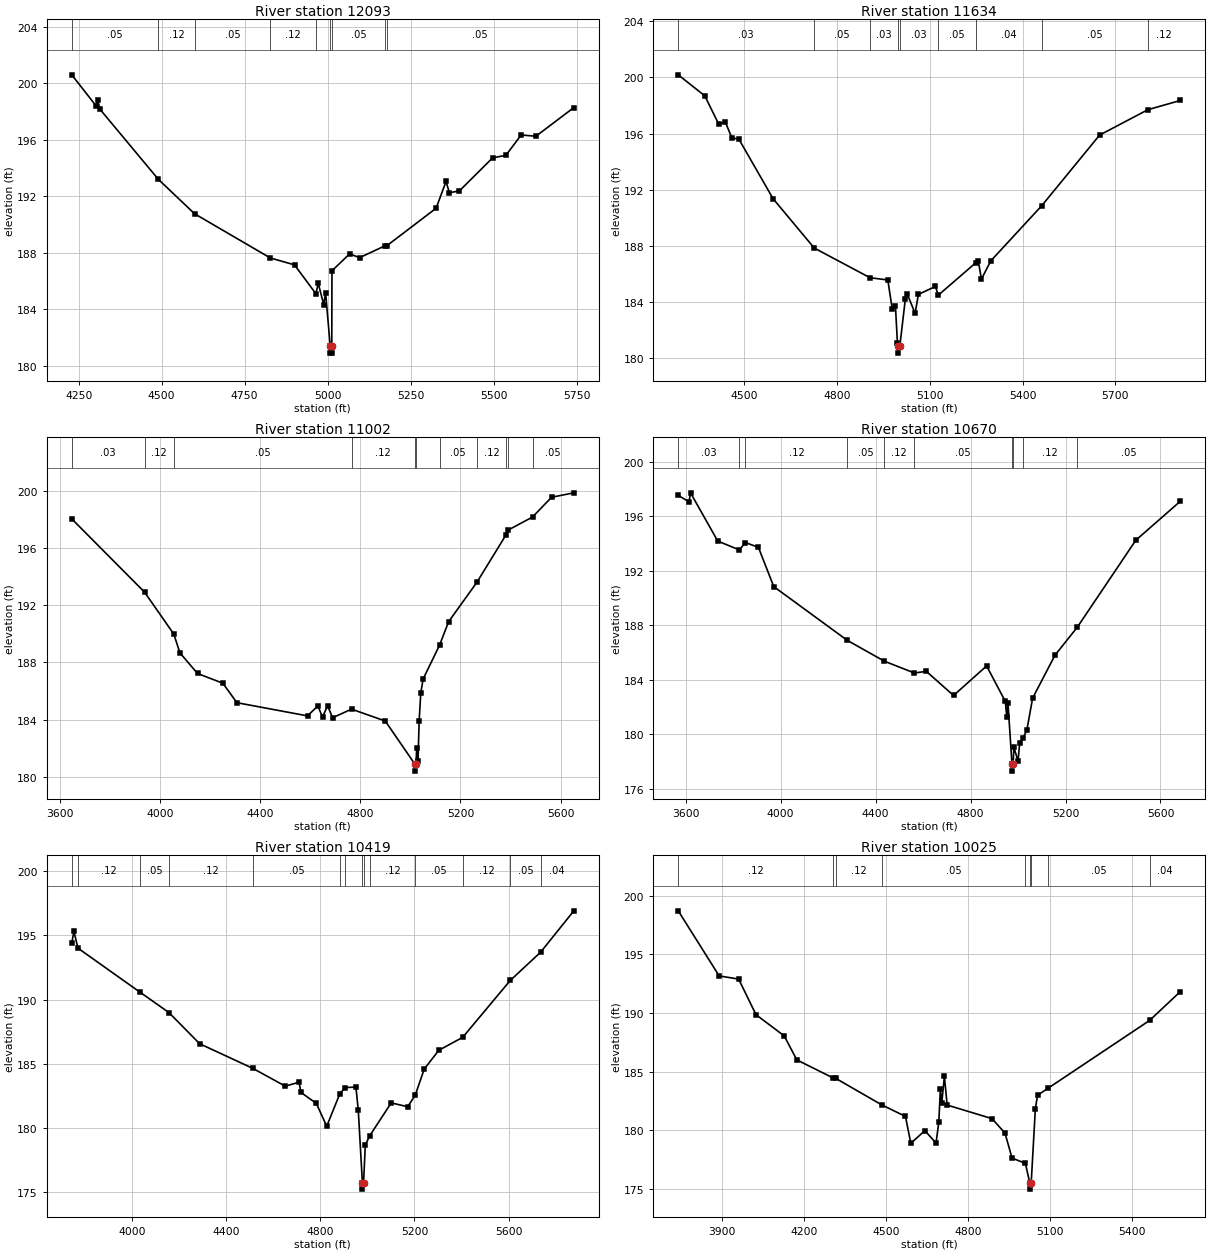
Type RM Length L Ch R = 1,12093,459,459,459
BEGIN DESCRIPTION:
Mapping XS 807224af
END DESCRIPTION:
XS GIS Cut Line= 3
      2531360.04     13531586.27      2530665.62     13531217.36
      2529940.82     13531169.61
#Sta/Elev= 30
  4229.1  200.59  4301.7  198.41  4307.4  198.78  4314.1  198.15  4490.3  193.18
  4599.1  190.75  4827.3  187.62  4900.2  187.13  4964.5  185.09  4971.8  185.82
  4988.2  184.31  4993.8  185.17  5007.8  181.38  5008.1  180.88  5012.1  180.88
  5012.5  181.38  5013.0  186.71  5066.2  187.91  5096.2  187.64  5173.7  188.49
  5178.1  188.48  5326.7  191.14  5356.8  193.04  5366.8  192.24  5396.9  192.37
  5497.1  194.71  5537.2  194.89  5583.0  196.33  5627.4  196.24  5741.8  198.27
#Mann=9,-1,0
  4229.1    0.05       0  4490.3    0.12       0  4599.1    0.05       0
  4827.3    0.12       0  4964.5    0.05       0  5007.8    0.05       0
  5012.5    0.05       0  5173.7    0.04       0  5178.1    0.05       0
Bank Sta=5007.8,5012.5
Exp/Cntr=0.3,0.1

Type RM Length L Ch R = 1,11634,632,632,632
BEGIN DESCRIPTION:
Mapping XS 7a30209c
END DESCRIPTION:
XS GIS Cut Line= 4
      2531498.92     13531208.65      2530991.15     13530909.20
      2530765.45     13530831.07      2529975.54     13530752.95
#Sta/Elev= 30
  4287.7  200.19  4373.5  198.69  4418.5  196.67  4440.0  196.82  4461.4  195.66
  4482.9  195.63  4594.1  191.35  4727.0  187.83  4907.4  185.71  4964.8  185.55
  4978.9  183.51  4989.5  183.68  4995.9  181.04  4998.8  180.83  4999.2  180.33
  5003.6  180.83  5021.3  184.17  5027.1  184.57  5053.0  183.17  5063.6  184.52
  5118.8  185.09  5127.6  184.46  5249.1  186.78  5257.2  186.90  5267.2  185.61
  5297.4  186.91  5462.1  190.85  5649.1  195.89  5804.9  197.70  5909.8  198.36
#Mann=9,-1,0
  4287.7    0.03       0  4727.0    0.05       0  4907.4    0.03       0
  4998.8    0.03       0  5003.6    0.03       0  5127.6    0.05       0
  5249.1    0.04       0  5462.1    0.05       0  5804.9    0.12       0
Bank Sta=4998.8,5003.6
Exp/Cntr=0.3,0.1

Type RM Length L Ch R = 1,11002,332,332,332
BEGIN DESCRIPTION:
Mapping XS 15de2279
END DESCRIPTION:
XS GIS Cut Line= 4
      2531616.14     13531030.72      2531117.01     13530392.70
      2530539.76     13530349.30      2529959.10     13530561.63
#Sta/Elev= 30
  3646.1  198.02  3937.2  192.90  4054.1  189.97  4078.4  188.66  4148.9  187.22
  4250.1  186.54  4306.2  185.18  4588.5  184.26  4629.6  184.95  4648.7  184.18
  4668.8  184.97  4688.8  184.13  4764.6  184.73  4899.4  183.90  5017.3  180.90
  5017.7  180.40  5022.2  180.90  5025.2  182.03  5030.3  181.14  5034.9  183.92
  5041.3  185.85  5050.8  186.84  5116.5  189.20  5152.7  190.84  5266.1  193.60
  5381.3  196.88  5389.7  197.23  5488.1  198.15  5564.2  199.53  5653.3  199.84
#Mann=11,-1,0
  3646.1    0.03       0  3937.2    0.12       0  4054.1    0.05       0
  4764.6    0.12       0  5017.3    0.05       0  5022.2    0.12       0
  5116.5    0.05       0  5266.1    0.12       0  5381.3    0.05       0
  5389.7    0.12       0  5488.1    0.05       0
Bank Sta=5017.3,5022.2
Exp/Cntr=0.3,0.1

Type RM Length L Ch R = 1,10670,251,251,251
BEGIN DESCRIPTION:
Mapping XS 4679a28c
END DESCRIPTION:
XS GIS Cut Line= 4
      2531759.39     13531013.39      2531229.86     13530297.22
      2530665.62     13530080.20      2530053.72     13530180.02
#Sta/Elev= 30
  3568.4  197.54  3613.9  197.07  3620.1  197.73  3734.9  194.19  3826.0  193.54
  3851.3  194.08  3906.1  193.73  3970.8  190.85  4281.0  186.90  4436.4  185.38
  4563.2  184.51  4613.7  184.63  4728.3  182.86  4867.6  185.03  4946.4  182.42
  4952.3  181.31  4957.6  182.30  4974.5  177.81  4974.8  177.31  4979.4  177.81
  4982.3  179.07  5000.0  178.05  5006.9  179.38  5020.3  179.72  5036.9  180.30
  5061.3  182.66  5155.4  185.81  5249.7  187.87  5496.0  194.25  5683.6  197.11
#Mann=10,-1,0
  3568.4    0.03       0  3826.0    0.05       0  3851.3    0.12       0
  4281.0    0.05       0  4436.4    0.12       0  4563.2    0.05       0
  4974.5    0.05       0  4979.4    0.05       0  5020.3    0.12       0
  5249.7    0.05       0
Bank Sta=4974.5,4979.4
Exp/Cntr=0.3,0.1

Type RM Length L Ch R = 1,10419,394,394,394
BEGIN DESCRIPTION:
Mapping XS 21d50a57
END DESCRIPTION:
XS GIS Cut Line= 4
      2531950.37     13530423.09      2530934.72     13529889.23
      2530635.24     13529889.23      2529962.45     13530023.79
#Sta/Elev= 30
  3744.2  194.42  3753.4  195.32  3770.2  194.01  4034.2  190.58  4156.7  189.00
  4287.5  186.57  4513.9  184.65  4651.0  183.27  4710.5  183.58  4717.1  182.79
  4783.2  181.93  4827.3  180.15  4882.6  182.66  4905.2  183.16  4951.3  183.20
  4961.3  181.43  4978.9  175.76  4979.2  175.26  4983.8  175.76  4991.3  178.70
  5010.3  179.42  5101.3  181.97  5171.3  181.67  5203.4  182.57  5241.6  184.60
  5303.5  186.06  5405.1  187.07  5606.8  191.49  5735.9  193.69  5877.2  196.91
#Mann=14,-1,0
  3744.2    0.05       0  3770.2    0.12       0  4034.2    0.05       0
  4156.7    0.12       0  4513.9    0.05       0  4882.6    0.12       0
  4905.2    0.05       0  4978.9    0.05       0  4983.8    0.05       0
  5010.3    0.12       0  5203.4    0.05       0  5405.1    0.12       0
  5606.8    0.05       0  5735.9    0.04       0
Bank Sta=4978.9,4983.8
Exp/Cntr=0.3,0.1

Type RM Length L Ch R = 1,10025,272,272,272
BEGIN DESCRIPTION:
Mapping XS dffeb511
END DESCRIPTION:
XS GIS Cut Line= 3
      2531872.22     13529824.13      2530782.81     13529611.45
      2530092.99     13529850.07
#Sta/Elev= 30
  3738.5  198.73  3888.5  193.17  3959.8  192.90  4023.5  189.86  4126.7  188.05
  4173.1  186.00  4304.8  184.47  4316.4  184.41  4484.0  182.16  4571.2  181.17
  4590.8  178.87  4642.3  179.96  4683.2  178.89  4693.4  180.69  4699.0  183.47
  4704.1  182.30  4713.8  184.59  4724.0  182.14  4888.5  180.98  4936.0  179.74
  4961.8  177.61  5010.7  177.16  5027.0  175.46  5027.4  174.96  5031.9  175.46
  5047.2  181.83  5055.3  182.98  5095.3  183.60  5466.0  189.37  5578.4  191.83
#Mann=9,-1,0
  3738.5    0.12       0  4304.8    0.05       0  4316.4    0.12       0
  4484.0    0.05       0  5010.7    0.04       0  5027.0    0.05       0
  5031.9    0.04       0  5095.3    0.05       0  5466.0    0.04       0
Bank Sta=5027,5031.9
Exp/Cntr=0.3,0.1

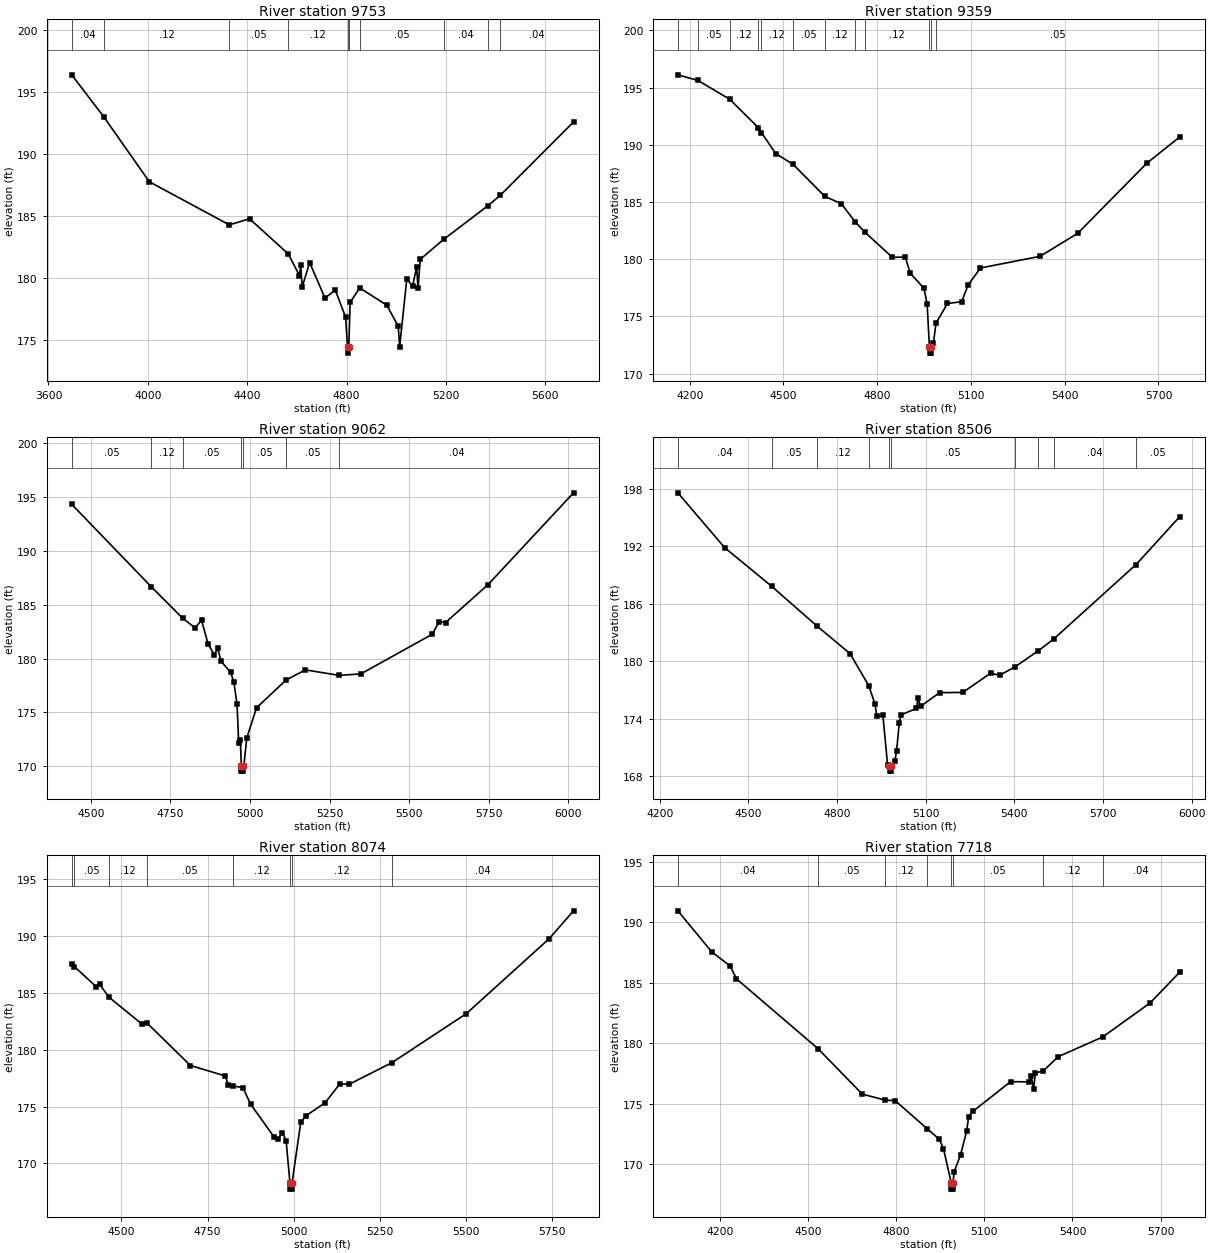
Type RM Length L Ch R = 1,9753,394,394,394
BEGIN DESCRIPTION:
Mapping XS 11a114ac
END DESCRIPTION:
XS GIS Cut Line= 3
      2531954.67     13529468.22      2530982.46     13529342.36
      2529979.90     13529615.78
#Sta/Elev= 30
  3693.8  196.40  3824.4  192.96  4006.1  187.76  4328.1  184.28  4409.4  184.77
  4565.4  181.93  4610.3  180.18  4615.3  181.01  4621.1  179.26  4651.4  181.23
  4713.0  178.36  4754.4  179.02  4795.9  176.83  4803.7  174.42  4804.1  173.92
  4808.7  174.42  4814.3  178.02  4852.9  179.19  4961.7  177.79  5007.8  176.10
  5013.5  174.44  5042.3  179.91  5065.4  179.33  5082.1  180.89  5087.3  179.15
  5096.5  181.50  5190.1  183.10  5368.4  185.82  5419.3  186.68  5713.3  192.59
#Mann=10,-1,0
  3693.8    0.04       0  3824.4    0.12       0  4328.1    0.05       0
  4565.4    0.12       0  4803.7    0.05       0  4808.7    0.12       0
  4852.9    0.05       0  5190.1    0.04       0  5368.4    0.05       0
  5419.3    0.04       0
Bank Sta=4803.7,4808.7
Exp/Cntr=0.3,0.1

Type RM Length L Ch R = 1,9359,297,297,297
BEGIN DESCRIPTION:
Mapping XS 5f3711db
END DESCRIPTION:
XS GIS Cut Line= 3
      2531694.29     13528969.09      2531021.53     13529125.34
      2530110.04     13529203.47
#Sta/Elev= 30
  4162.4  196.11  4226.4  195.62  4328.0  193.98  4419.5  191.50  4429.6  191.07
  4475.3  189.23  4531.3  188.28  4632.9  185.48  4685.2  184.85  4730.4  183.24
  4759.8  182.38  4848.7  180.16  4889.7  180.19  4906.2  178.77  4950.0  177.44
  4960.0  176.07  4967.2  172.29  4967.7  171.79  4972.4  171.79  4972.9  172.29
  4980.1  172.69  4988.3  174.41  5025.0  176.13  5070.4  176.28  5090.5  177.72
  5130.6  179.23  5321.3  180.25  5441.8  182.26  5662.6  188.38  5767.9  190.68
#Mann=12,-1,0
  4162.4    0.12       0  4226.4    0.05       0  4328.0    0.12       0
  4419.5    0.05       0  4429.6    0.12       0  4531.3    0.05       0
  4632.9    0.12       0  4730.4    0.05       0  4759.8    0.12       0
  4967.2    0.05       0  4972.9    0.12       0  4988.3    0.05       0
Bank Sta=4967.2,4972.9
Exp/Cntr=0.3,0.1

Type RM Length L Ch R = 1,9062,556,556,556
BEGIN DESCRIPTION:
Mapping XS 5316d8a1
END DESCRIPTION:
XS GIS Cut Line= 3
      2531477.29     13528765.09      2530947.74     13528851.90
      2529932.10     13529073.26
#Sta/Elev= 30
  4440.0  194.32  4689.4  186.68  4787.9  183.76  4827.4  182.85  4847.7  183.57
  4867.9  181.38  4888.2  180.33  4898.1  181.01  4908.5  179.77  4938.9  178.72
  4949.0  177.86  4959.1  175.76  4964.5  172.16  4969.6  172.46  4972.6  170.05
  4973.1  169.55  4977.9  169.55  4978.3  170.05  4980.6  170.05  4989.7  172.62
  5020.4  175.43  5113.6  178.02  5173.9  178.95  5280.8  178.44  5348.2  178.58
  5573.0  182.27  5593.5  183.43  5614.0  183.34  5747.0  186.85  6016.1  195.39
#Mann=7,-1,0
  4440.0    0.05       0  4689.4    0.12       0  4787.9    0.05       0
  4972.6    0.05       0  4978.3    0.05       0  5113.6    0.05       0
  5280.8    0.04       0
Bank Sta=4972.6,4978.3
Exp/Cntr=0.3,0.1

Type RM Length L Ch R = 1,8506,432,432,432
BEGIN DESCRIPTION:
Mapping XS d858fef5
END DESCRIPTION:
XS GIS Cut Line= 3
      2531451.23     13528322.39      2530748.09     13528426.56
      2529914.72     13528956.10
#Sta/Elev= 30
  4261.3  197.60  4419.2  191.88  4579.0  187.82  4731.1  183.70  4843.8  180.80
  4907.3  177.44  4928.6  175.50  4934.8  174.23  4955.0  174.36  4971.2  169.11
  4977.3  169.01  4977.7  168.51  4982.5  168.51  4983.0  169.01  4995.4  169.54
  5001.3  170.59  5010.6  173.56  5016.5  174.39  5068.2  175.06  5074.1  176.11
  5082.4  175.28  5147.0  176.71  5225.7  176.74  5319.7  178.75  5350.2  178.52
  5402.6  179.42  5481.7  181.10  5533.9  182.34  5811.8  190.10  5959.5  195.10
#Mann=10,-1,0
  4261.3    0.04       0  4579.0    0.05       0  4731.1    0.12       0
  4907.3    0.05       0  4977.3    0.05       0  4983.0    0.05       0
  5402.6    0.04       0  5481.7    0.05       0  5533.9    0.04       0
  5811.8    0.05       0
Bank Sta=4977.3,4983
Exp/Cntr=0.3,0.1

Type RM Length L Ch R = 1,8074,356,356,356
BEGIN DESCRIPTION:
TRIB 4 TO TWELVEMILE CREEK 17.0
END DESCRIPTION:
XS GIS Cut Line= 3
      2531074.97     13528075.01      2530475.00     13528175.00
      2529874.98     13528775.02
#Sta/Elev= 30
  4355.6  187.53  4363.2  187.31  4426.5  185.54  4436.7  185.74  4463.4  184.62
  4558.3  182.28  4574.5  182.33  4700.3  178.61  4801.6  177.69  4809.2  176.93
  4824.9  176.80  4852.3  176.67  4875.1  175.20  4943.6  172.30  4953.7  172.13
  4967.4  172.70  4978.0  171.99  4989.2  168.24  4989.7  167.74  4994.6  167.74
  4995.0  168.24  5020.4  173.60  5034.6  174.17  5091.1  175.33  5133.6  176.99
  5161.8  176.97  5285.1  178.86  5501.2  183.17  5741.7  189.76  5812.4  192.21
#Mann=8,-1,0
  4355.6    0.04       0  4363.2    0.05       0  4463.4    0.12       0
  4574.5    0.05       0  4824.9    0.12       0  4989.2    0.05       0
  4995.0    0.12       0  5285.1    0.04       0
Bank Sta=4989.2,4995
Exp/Cntr=0.3,0.1

Type RM Length L Ch R = 1,7718,437,437,437
BEGIN DESCRIPTION:
Mapping XS 9f932b22
END DESCRIPTION:
XS GIS Cut Line= 3
      2531190.82     13527719.09      2530301.04     13527879.68
      2529784.53     13528496.02
#Sta/Elev= 30
  4056.6  190.94  4171.8  187.55  4235.5  186.36  4255.6  185.33  4533.8  179.55
  4684.2  175.80  4761.2  175.31  4796.4  175.26  4906.2  172.92  4946.6  172.07
  4960.8  171.29  4987.4  168.45  4987.9  167.95  4992.8  167.95  4993.3  168.45
  4996.9  169.36  5019.0  170.79  5039.8  172.75  5046.4  173.93  5060.7  174.37
  5189.4  176.83  5253.2  176.81  5259.7  177.28  5267.5  176.23  5274.0  177.54
  5301.2  177.73  5352.1  178.90  5502.9  180.52  5664.3  183.33  5764.9  185.87
#Mann=8,-1,0
  4056.6    0.04       0  4533.8    0.05       0  4761.2    0.12       0
  4906.2    0.05       0  4987.4    0.05       0  4993.3    0.05       0
  5301.2    0.12       0  5502.9    0.04       0
Bank Sta=4987.4,4993.3
Exp/Cntr=0.3,0.1

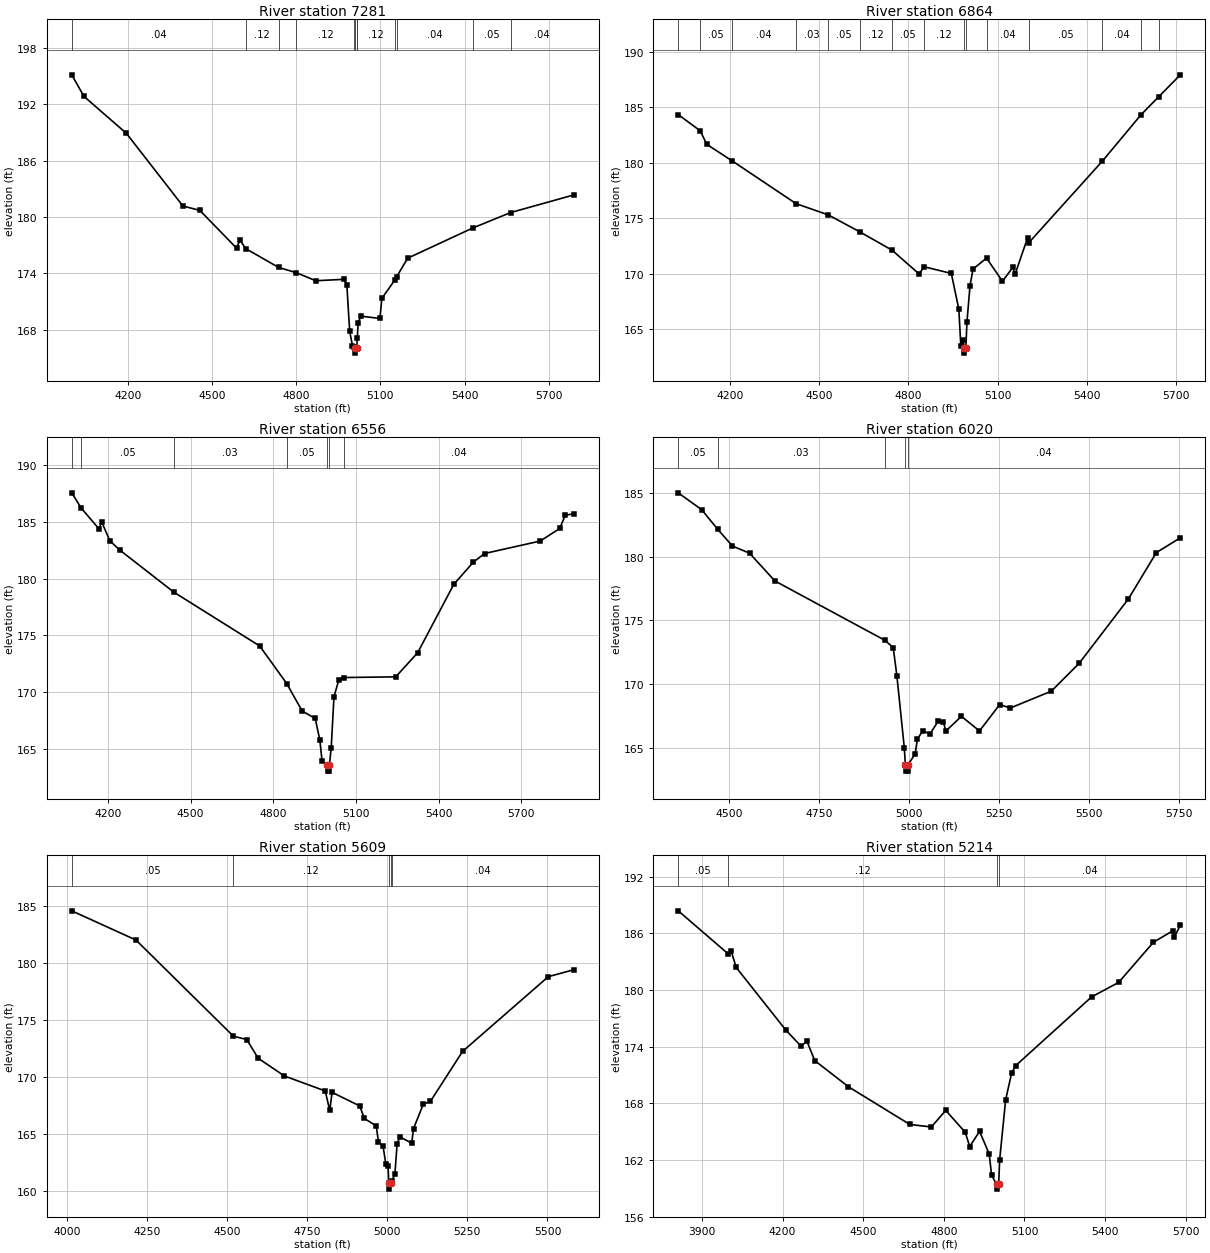
Type RM Length L Ch R = 1,7281,417,417,417
BEGIN DESCRIPTION:
Mapping XS 84b91811
END DESCRIPTION:
XS GIS Cut Line= 3
      2531208.19     13527397.91      2530175.17     13527523.78
      2529650.02     13528057.61
#Sta/Elev= 30
  4000.2  195.15  4043.7  192.85  4194.8  188.92  4396.3  181.18  4456.7  180.71
  4587.7  176.69  4599.5  177.56  4620.2  176.64  4737.8  174.63  4800.5  174.08
  4869.8  173.22  4970.5  173.37  4980.6  172.76  4990.7  167.85  5000.7  166.28
  5007.9  166.17  5009.6  166.01  5010.1  165.51  5015.8  166.01  5017.8  167.09
  5020.9  168.76  5031.0  169.45  5098.5  169.20  5105.5  171.34  5151.7  173.30
  5157.7  173.62  5197.4  175.62  5429.6  178.84  5564.2  180.48  5789.7  182.36
#Mann=12,-1,0
  4000.2    0.04       0  4620.2    0.12       0  4737.8    0.05       0
  4800.5    0.12       0  5007.9    0.05       0  5009.6    0.05       0
  5015.8    0.05       0  5017.8    0.12       0  5151.7    0.05       0
  5157.7    0.04       0  5429.6    0.05       0  5564.2    0.04       0
Bank Sta=5009.6,5015.8
Exp/Cntr=0.3,0.1

Type RM Length L Ch R = 1,6864,308,308,308
BEGIN DESCRIPTION:
Mapping XS e37096de
END DESCRIPTION:
XS GIS Cut Line= 3
      2530873.96     13526859.71      2530001.56     13527215.62
      2529278.33     13527388.85
#Sta/Elev= 30
  4027.3  184.36  4100.9  182.90  4123.4  181.67  4208.3  180.19  4423.2  176.33
  4530.6  175.33  4638.0  173.78  4745.4  172.14  4836.2  170.00  4852.9  170.65
  4944.2  170.05  4969.5  166.83  4976.3  163.50  4984.9  164.04  4986.9  163.37
  4987.4  162.87  4993.1  163.37  4996.8  165.69  5007.1  168.96  5017.4  170.45
  5062.6  171.43  5116.1  169.34  5151.1  170.61  5158.1  169.96  5200.2  173.24
  5205.0  172.83  5451.6  180.17  5581.5  184.35  5641.2  185.98  5713.2  187.94
#Mann=15,-1,0
  4027.3    0.04       0  4100.9    0.05       0  4208.3    0.04       0
  4423.2    0.03       0  4530.6    0.05       0  4638.0    0.12       0
  4745.4    0.05       0  4852.9    0.12       0  4986.9    0.05       0
  4993.1    0.12       0  5062.6    0.04       0  5205.0    0.05       0
  5451.6    0.04       0  5581.5    0.05       0  5641.2    0.04       0
Bank Sta=4986.9,4993.1
Exp/Cntr=0.3,0.1

Type RM Length L Ch R = 1,6556,536,536,536
BEGIN DESCRIPTION:
Mapping XS 37c4032a
END DESCRIPTION:
XS GIS Cut Line= 3
      2530847.94     13526620.99      2529988.54     13526942.18
      2529094.47     13527076.73
#Sta/Elev= 30
  4069.0  187.56  4103.1  186.22  4168.2  184.37  4177.0  185.02  4207.3  183.33
  4242.9  182.52  4439.0  178.81  4750.9  174.06  4848.9  170.75  4904.8  168.33
  4952.3  167.67  4968.9  165.78  4977.2  163.91  4996.6  163.53  4997.1  163.03
  5003.2  163.03  5003.7  163.53  5010.3  165.11  5020.4  169.60  5037.3  171.02
  5056.7  171.28  5244.3  171.34  5323.8  173.46  5455.2  179.50  5526.0  181.45
  5566.5  182.21  5768.7  183.31  5839.5  184.42  5859.7  185.60  5890.6  185.70
#Mann=7,-1,0
  4069.0    0.04       0  4103.1    0.05       0  4439.0    0.03       0
  4848.9    0.05       0  4996.6    0.05       0  5003.7    0.05       0
  5056.7    0.04       0
Bank Sta=4996.6,5003.7
Exp/Cntr=0.3,0.1

Type RM Length L Ch R = 1,6020,411,411,411
BEGIN DESCRIPTION:
Mapping XS 377bf430
END DESCRIPTION:
XS GIS Cut Line= 3
      2530596.22     13526325.85      2529962.50     13526473.43
      2529372.20     13526924.84
#Sta/Elev= 30
  4359.0  185.04  4424.2  183.71  4468.6  182.17  4509.3  180.86  4557.1  180.29
  4627.2  178.11  4932.1  173.45  4955.8  172.87  4966.0  170.64  4986.6  164.99
  4989.5  163.65  4990.0  163.15  4996.2  163.15  4996.7  163.65  5016.7  164.50
  5023.0  165.68  5037.5  166.30  5058.3  166.09  5081.1  167.10  5094.7  167.05
  5101.9  166.30  5145.0  167.46  5195.3  166.31  5251.5  168.39  5280.5  168.11
  5394.8  169.44  5472.3  171.64  5608.8  176.70  5686.3  180.34  5752.8  181.50
#Mann=5,-1,0
  4359.0    0.05       0  4468.6    0.03       0  4932.1    0.04       0
  4989.5    0.04       0  4996.7    0.04       0
Bank Sta=4989.5,4996.7
Exp/Cntr=0.3,0.1

Type RM Length L Ch R = 1,5609,395,395,395
BEGIN DESCRIPTION:
Mapping XS 92828e3b
END DESCRIPTION:
XS GIS Cut Line= 4
      2530479.02     13526004.68      2529732.46     13526195.65
      2529506.77     13526568.92      2529307.13     13526868.38
#Sta/Elev= 30
  4015.7  184.58  4216.0  182.02  4520.2  173.59  4561.7  173.30  4597.4  171.66
  4679.0  170.11  4806.7  168.79  4820.6  167.09  4828.1  168.67  4914.1  167.48
  4929.0  166.38  4965.8  165.73  4972.5  164.36  4987.2  163.93  4995.9  162.35
  5002.7  162.20  5004.9  160.69  5005.4  160.19  5012.2  160.69  5014.7  160.94
  5024.0  161.49  5030.9  164.15  5039.5  164.77  5076.4  164.22  5082.2  165.50
  5112.7  167.64  5134.6  167.87  5235.2  172.26  5502.7  178.81  5582.4  179.42
#Mann=5,-1,0
  4015.7    0.05       0  4520.2    0.12       0  5004.9    0.05       0
  5012.2    0.12       0  5014.7    0.04       0
Bank Sta=5004.9,5012.2
Exp/Cntr=0.3,0.1

Type RM Length L Ch R = 1,5214,304,304,304
BEGIN DESCRIPTION:
Mapping XS 63f8a836
END DESCRIPTION:
XS GIS Cut Line= 4
      2530444.31     13525770.30      2529632.64     13526000.34
      2529211.63     13526213.01      2528755.90     13526525.52
#Sta/Elev= 30
  3811.9  188.39  3997.9  183.83  4008.7  184.14  4027.6  182.39  4212.8  175.74
  4268.5  174.07  4291.0  174.56  4319.8  172.53  4445.2  169.76  4673.3  165.77
  4753.7  165.50  4807.1  167.26  4879.6  164.94  4896.3  163.43  4933.0  165.04
  4968.7  162.65  4977.8  160.38  4996.5  159.42  4997.0  158.92  5004.0  159.42
  5007.7  162.03  5030.0  168.38  5052.3  171.22  5067.4  172.00  5349.6  179.27
  5450.5  180.81  5579.7  185.06  5651.5  186.27  5657.5  185.64  5679.8  186.85
#Mann=4,-1,0
  3811.9    0.05       0  3997.9    0.12       0  4996.5    0.04       0
  5004.0    0.04       0
Bank Sta=4996.5,5004
Exp/Cntr=0.3,0.1

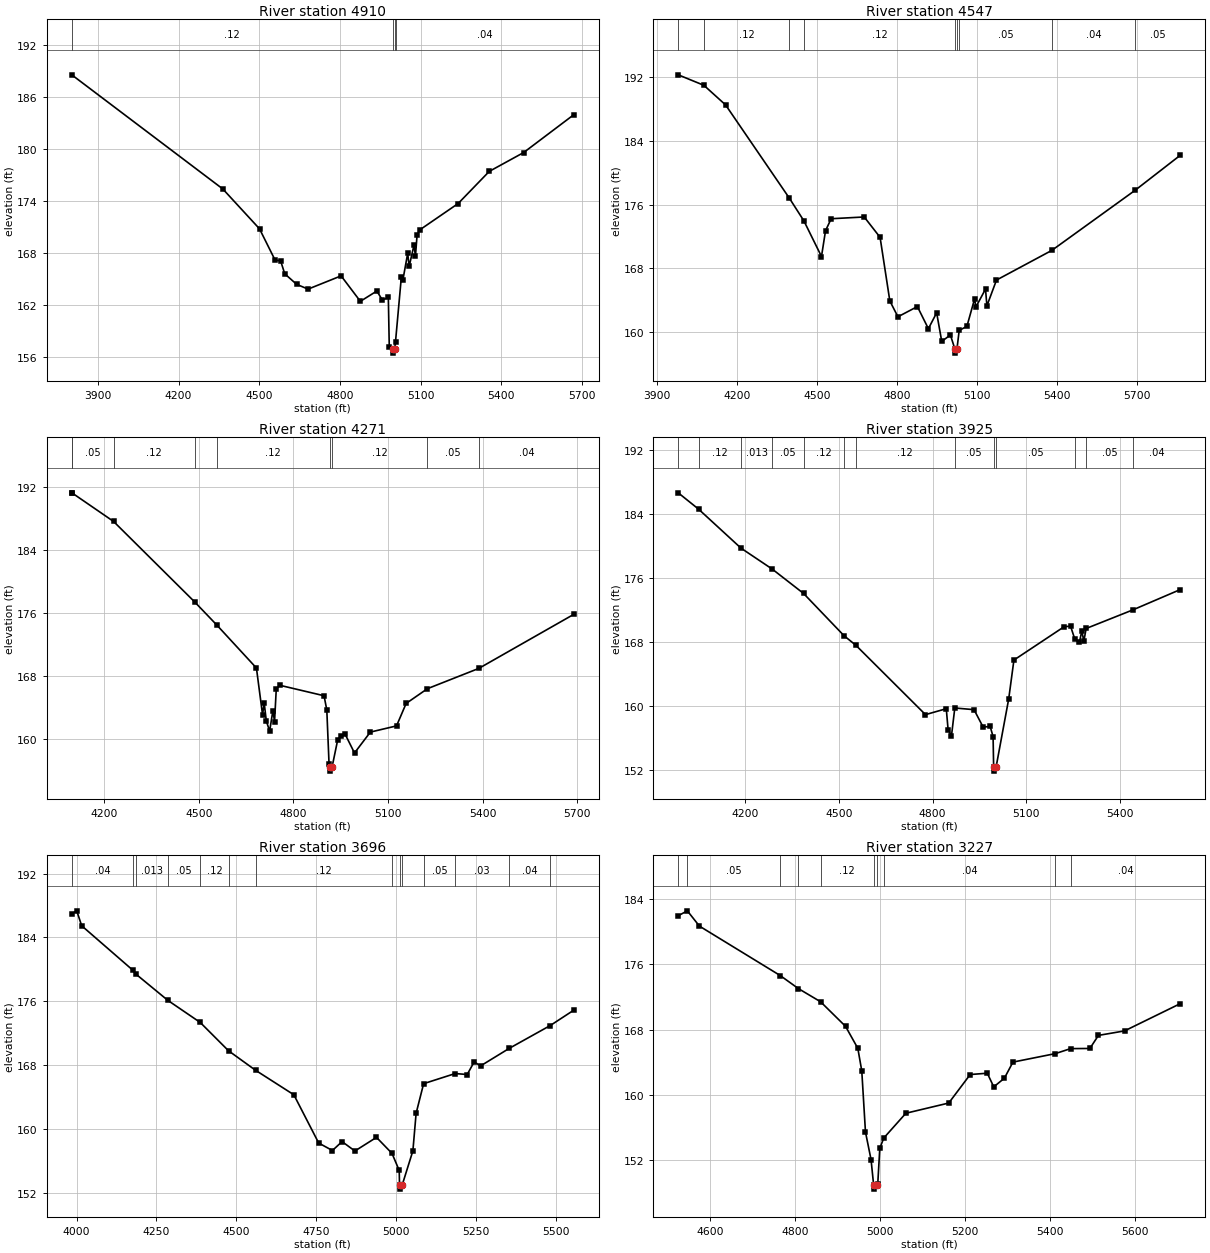
Type RM Length L Ch R = 1,4910,363,363,363
BEGIN DESCRIPTION:
Mapping XS 0f63c9e2
END DESCRIPTION:
XS GIS Cut Line= 3
      2530444.23     13525614.06      2529289.76     13525861.45
      2528660.38     13526134.90
#Sta/Elev= 30
  3803.1  188.55  4364.8  175.37  4501.2  170.77  4559.1  167.16  4579.6  167.08
  4595.0  165.58  4639.3  164.36  4681.8  163.81  4804.6  165.34  4876.2  162.40
  4937.5  163.59  4958.0  162.55  4980.2  162.85  4983.7  157.09  4996.1  156.92
  4996.6  156.42  5003.6  156.92  5006.9  157.74  5028.7  165.24  5034.2  164.84
  5052.2  167.95  5057.6  166.43  5075.6  168.88  5081.1  167.64  5087.1  170.07
  5098.0  170.67  5239.7  173.69  5355.4  177.40  5483.5  179.58  5670.0  183.95
#Mann=4,-1,0
  3803.1    0.12       0  4996.1    0.05       0  5003.6    0.12       0
  5006.9    0.04       0
Bank Sta=4996.1,5003.6
Exp/Cntr=0.3,0.1

Type RM Length L Ch R = 1,4547,276,276,276
BEGIN DESCRIPTION:
Mapping XS 5f5703b9
END DESCRIPTION:
XS GIS Cut Line= 4
      2530314.06     13525080.20      2529680.38     13525492.53
      2528942.53     13525679.16      2528625.69     13525857.11
#Sta/Elev= 30
  3980.4  192.24  4076.4  190.93  4157.8  188.47  4396.5  176.80  4451.1  173.95
  4516.9  169.49  4532.1  172.72  4553.2  174.22  4677.0  174.44  4736.4  171.89
  4772.9  163.93  4803.2  161.94  4876.1  163.22  4917.3  160.45  4948.3  162.44
  4967.3  158.86  4999.8  159.66  5016.7  157.89  5017.2  157.39  5024.3  157.89
  5032.7  160.23  5061.7  160.75  5090.3  164.18  5095.5  163.18  5131.3  165.41
  5136.5  163.31  5172.4  166.54  5379.9  170.26  5690.8  177.76  5860.9  182.17
#Mann=9,-1,0
  3980.4    0.05       0  4076.4    0.12       0  4396.5   0.013       0
  4451.1    0.12       0  5016.7    0.05       0  5024.3    0.12       0
  5032.7    0.05       0  5379.9    0.04       0  5690.8    0.05       0
Bank Sta=5016.7,5024.3
Exp/Cntr=0.3,0.1

Type RM Length L Ch R = 1,4271,346,346,346
BEGIN DESCRIPTION:
Mapping XS f7a92aa4
END DESCRIPTION:
XS GIS Cut Line= 4
      2530244.64     13525002.07      2529506.77     13525227.77
      2529285.42     13525353.64      2528769.43     13525583.45
#Sta/Elev= 30
  4097.7  191.30  4098.1  191.30  4230.3  187.65  4487.1  177.41  4557.4  174.46
  4682.9  168.99  4702.3  163.04  4707.5  164.54  4714.3  162.23  4724.8  160.96
  4735.1  163.58  4740.3  162.17  4745.7  166.27  4756.1  166.80  4897.1  165.46
  4905.9  163.66  4913.0  156.82  4914.9  156.36  4915.4  155.86  4922.5  156.36
  4940.4  159.84  4950.4  160.34  4963.4  160.61  4993.7  158.17  5043.9  160.83
  5126.9  161.62  5157.3  164.48  5224.9  166.36  5387.6  168.94  5688.8  175.83
#Mann=9,-1,0
  4097.7    0.04       0  4098.1    0.05       0  4230.3    0.12       0
  4487.1   0.013       0  4557.4    0.12       0  4914.9    0.05       0
  4922.5    0.12       0  5224.9    0.05       0  5387.6    0.04       0
Bank Sta=4914.9,4922.5
Exp/Cntr=0.3,0.1

Type RM Length L Ch R = 1,3925,229,229,229
BEGIN DESCRIPTION:
Mapping XS e5fd1aaa
END DESCRIPTION:
XS GIS Cut Line= 4
      2530075.34     13524902.25      2529341.84     13525028.12
      2528942.53     13525232.11      2528630.00     13525505.58
#Sta/Elev= 30
  3985.3  186.61  4050.5  184.57  4186.2  179.71  4286.4  177.09  4386.7  174.05
  4516.5  168.77  4554.3  167.58  4777.1  158.93  4843.7  159.67  4849.5  157.07
  4860.3  156.27  4871.0  159.76  4932.6  159.55  4961.8  157.37  4984.2  157.46
  4993.6  156.19  4995.4  152.38  4995.9  151.88  5003.2  152.38  5043.7  160.91
  5060.3  165.74  5220.7  169.89  5241.6  169.98  5255.2  168.37  5270.1  167.94
  5277.7  169.38  5284.3  168.10  5291.6  169.68  5441.2  172.00  5593.2  174.54
#Mann=13,-1,0
  3985.3    0.04       0  4050.5    0.12       0  4186.2   0.013       0
  4286.4    0.05       0  4386.7    0.12       0  4516.5    0.05       0
  4554.3    0.12       0  4871.0    0.05       0  4995.4    0.05       0
  5003.2    0.05       0  5255.2    0.04       0  5291.6    0.05       0
  5441.2    0.04       0
Bank Sta=4995.4,5003.2
Exp/Cntr=0.3,0.1

Type RM Length L Ch R = 1,3696,469,469,469
BEGIN DESCRIPTION:
Mapping XS a835bbea
END DESCRIPTION:
XS GIS Cut Line= 4
      2530075.35     13524806.76      2529402.60     13524949.99
      2529137.85     13524980.38      2528525.89     13524893.57
#Sta/Elev= 30
  3984.7  186.95  4000.3  187.34  4015.7  185.47  4177.0  179.86  4184.6  179.44
  4285.7  176.11  4386.9  173.35  4475.8  169.79  4560.3  167.35  4680.2  164.28
  4758.0  158.23  4801.0  157.29  4831.2  158.41  4871.4  157.23  4939.0  158.94
  4987.6  156.93  5010.2  154.79  5011.2  152.95  5011.7  152.45  5019.4  152.95
  5053.0  157.25  5063.1  161.95  5086.6  165.67  5185.5  166.94  5223.1  166.82
  5244.9  168.40  5265.1  167.90  5354.9  170.10  5483.2  172.96  5557.1  174.89
#Mann=14,-1,0
  3984.7    0.04       0  4177.0    0.12       0  4184.6   0.013       0
  4285.7    0.05       0  4386.9    0.12       0  4475.8    0.05       0
  4560.3    0.12       0  4987.6    0.04       0  5011.2    0.04       0
  5019.4    0.04       0  5086.6    0.05       0  5185.5    0.03       0
  5354.9    0.04       0  5483.2    0.03       0
Bank Sta=5011.2,5019.4
Exp/Cntr=0.3,0.1

Type RM Length L Ch R = 1,3227,294,294,294
BEGIN DESCRIPTION:
Mapping XS 4b114dfb
END DESCRIPTION:
XS GIS Cut Line= 3
      2529810.61     13524502.94      2529372.22     13524693.92
      2528673.45     13524763.36
#Sta/Elev= 30
  4525.3  181.94  4546.7  182.54  4575.1  180.67  4765.0  174.62  4807.8  173.02
  4859.9  171.41  4918.6  168.40  4947.5  165.71  4956.8  162.95  4965.5  155.46
  4978.6  152.09  4984.7  148.97  4985.2  148.47  4993.0  148.97  4994.3  149.04
  4999.2  153.48  5008.6  154.73  5060.5  157.76  5161.3  159.01  5211.7  162.50
  5251.9  162.66  5267.1  160.99  5292.1  162.05  5312.2  164.02  5411.9  165.06
  5447.7  165.67  5493.1  165.69  5513.2  167.29  5574.6  167.84  5705.7  171.18
#Mann=10,-1,0
  4525.3    0.04       0  4546.7    0.05       0  4765.0    0.04       0
  4807.8    0.05       0  4859.9    0.12       0  4984.7    0.05       0
  4993.0    0.12       0  5008.6    0.04       0  5411.9    0.03       0
  5447.7    0.04       0
Bank Sta=4984.7,4993
Exp/Cntr=0.3,0.1