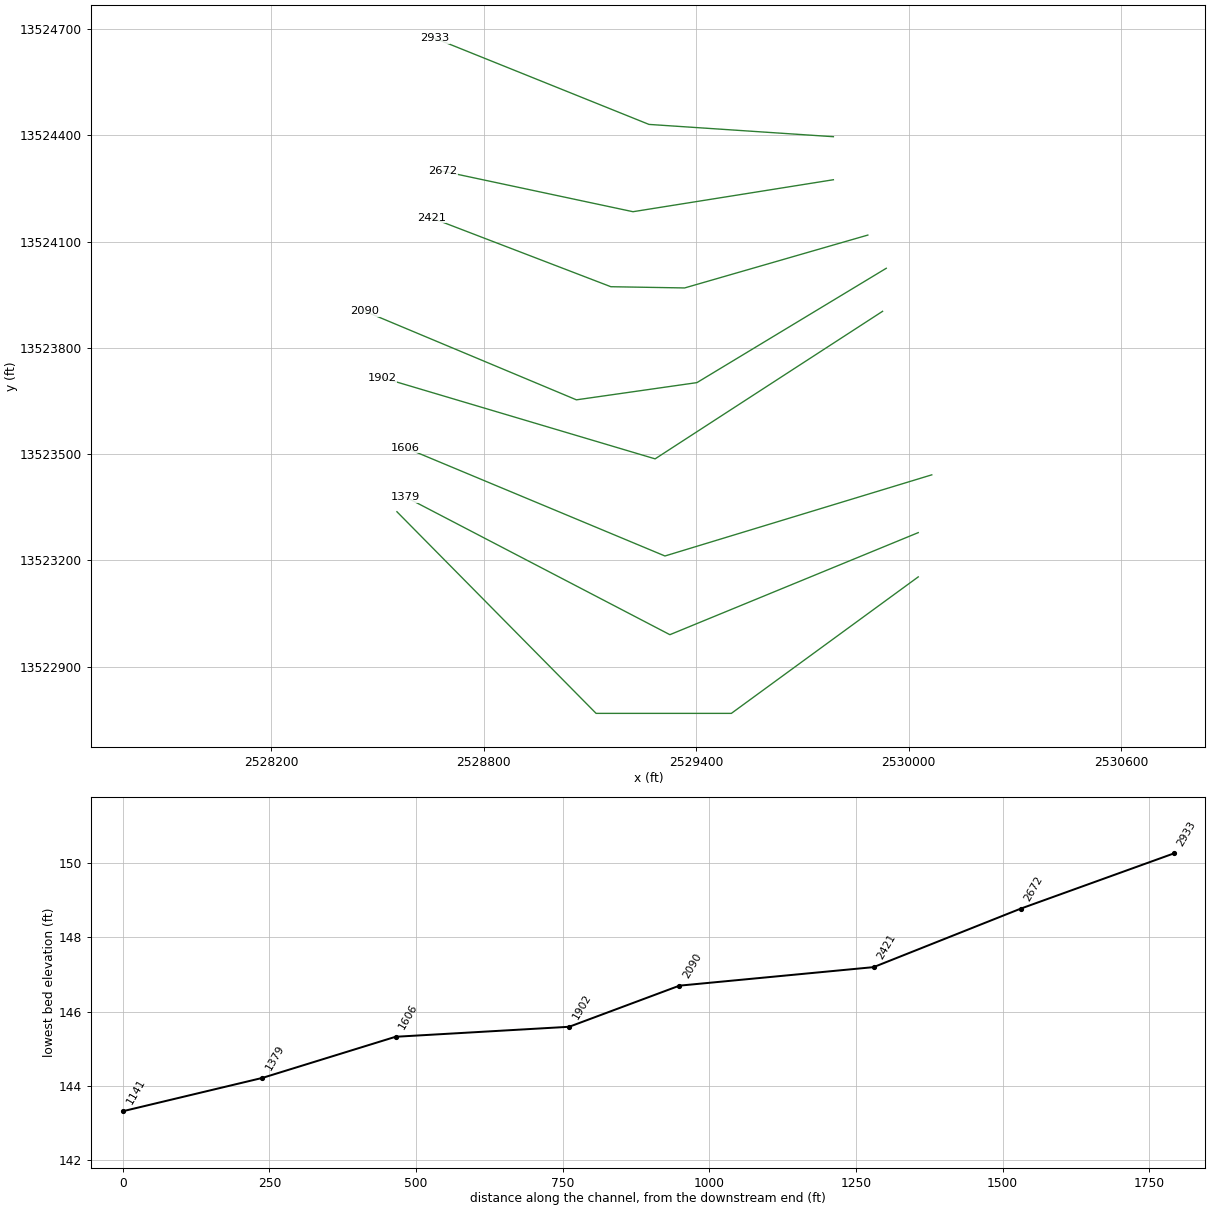
HEC-RAS study TRIB 4 TO TWELVEMILE CREEK.prj: TRIB 4 TO TWELVEMILE CREEK Base Level Engineering

--- TRIB 4 TO TWELVEMILE CREEK.g01 (geometry) --- (continued)

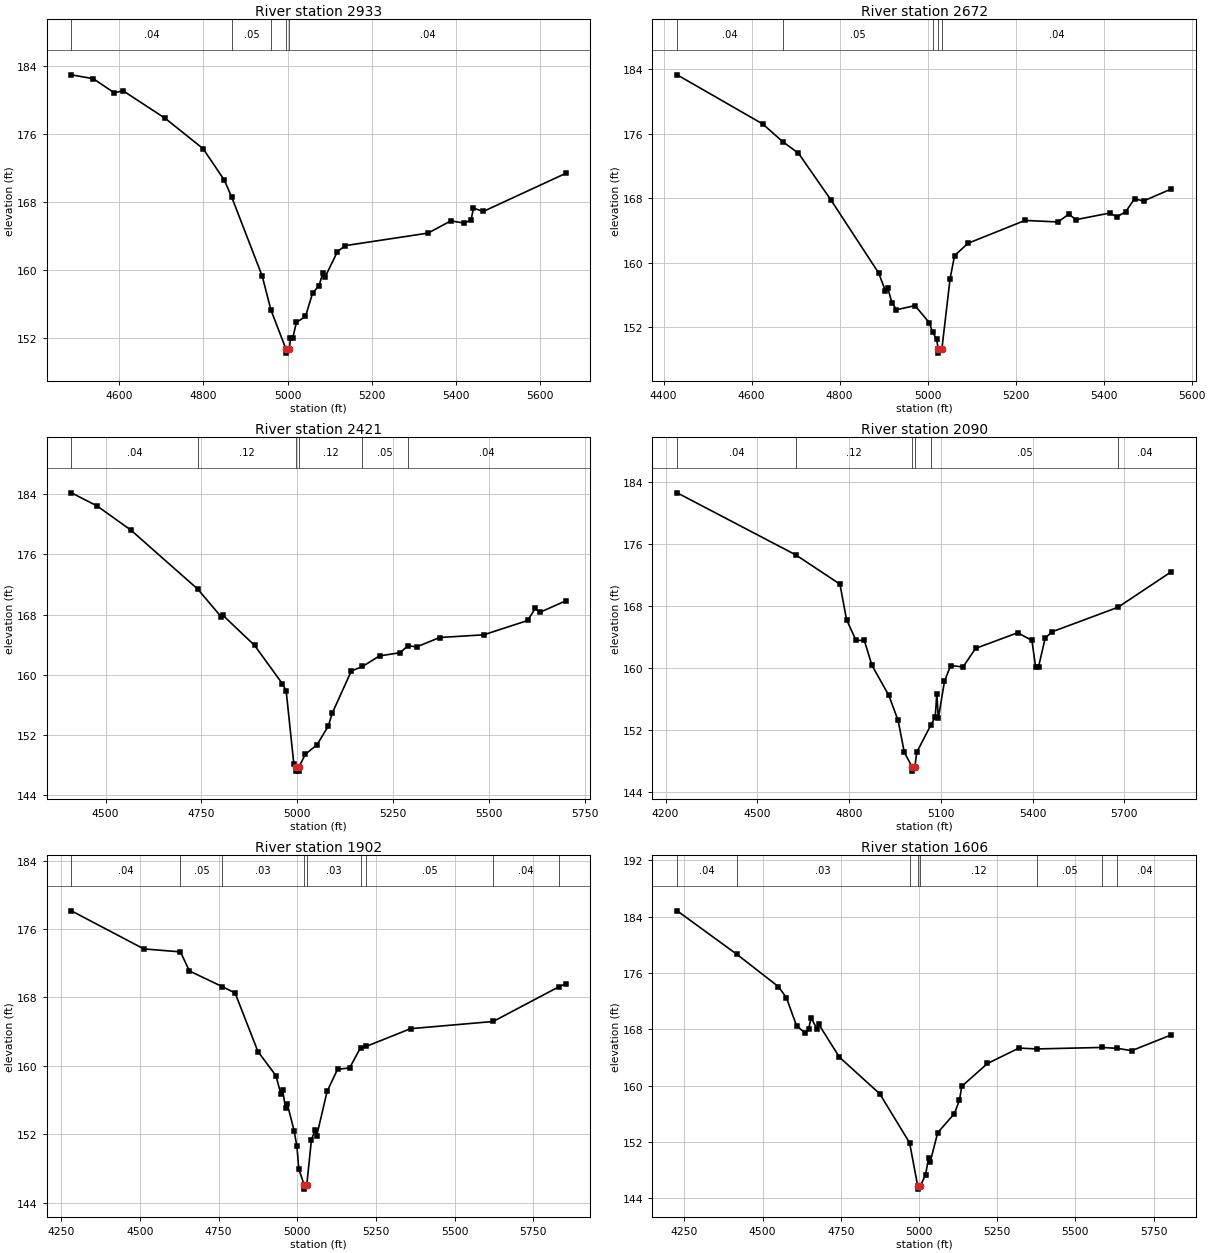
Type RM Length L Ch R = 1,2933,261,261,261
BEGIN DESCRIPTION:
Mapping XS 3a9db742
END DESCRIPTION:
XS GIS Cut Line= 3
      2529787.11     13524396.18      2529266.32     13524430.90
      2528662.12     13524673.96
#Sta/Elev= 30
  4486.7  182.96  4538.9  182.50  4589.0  180.83  4609.1  181.10  4709.3  177.85
  4799.5  174.28  4849.7  170.59  4867.5  168.57  4939.8  159.30  4960.4  155.33
  4995.9  150.77  4996.4  150.27  5004.2  150.77  5006.8  152.00  5012.0  152.00
  5020.8  153.88  5042.4  154.58  5059.2  157.31  5074.7  158.21  5083.4  159.66
  5088.8  159.19  5118.3  162.20  5137.1  162.90  5333.4  164.37  5387.3  165.80
  5419.7  165.54  5435.4  165.92  5441.2  167.29  5464.9  166.92  5659.9  171.38
#Mann=5,-1,0
  4486.7    0.04       0  4867.5    0.05       0  4960.4    0.04       0
  4995.9    0.04       0  5004.2    0.04       0
Bank Sta=4995.9,5004.2
Exp/Cntr=0.3,0.1

Type RM Length L Ch R = 1,2672,251,251,251
BEGIN DESCRIPTION:
Mapping XS b970a2af
END DESCRIPTION:
XS GIS Cut Line= 3
      2529787.11     13524274.64      2529221.18     13524184.37
      2528683.03     13524298.94
#Sta/Elev= 30
  4430.7  183.30  4625.2  177.20  4670.9  174.99  4706.3  173.58  4779.9  167.80
  4888.5  158.73  4904.1  156.49  4909.2  156.86  4918.9  155.04  4929.0  154.16
  4971.3  154.67  5003.8  152.55  5011.1  151.37  5020.3  150.53  5023.9  149.28
  5024.4  148.78  5032.3  149.28  5051.0  158.03  5061.2  160.88  5091.9  162.41
  5221.3  165.24  5296.4  165.05  5320.5  166.01  5337.3  165.34  5414.5  166.16
  5429.3  165.68  5449.7  166.29  5470.2  167.92  5490.6  167.65  5554.0  169.15
#Mann=5,-1,0
  4430.7    0.04       0  4670.9    0.05       0  5011.1    0.04       0
  5023.9    0.05       0  5032.3    0.04       0
Bank Sta=5023.9,5032.3
Exp/Cntr=0.3,0.1

Type RM Length L Ch R = 1,2421,331,331,331
BEGIN DESCRIPTION:
Mapping XS 2942f643
END DESCRIPTION:
XS GIS Cut Line= 4
      2529884.36     13524118.39      2529367.01     13523969.09
      2529158.68     13523972.56      2528651.72     13524167.02
#Sta/Elev= 30
  4410.9  184.17  4477.6  182.44  4566.4  179.21  4740.6  171.38  4801.2  167.74
  4806.4  167.90  4889.0  163.90  4961.4  158.82  4971.4  157.88  4991.4  148.15
  4995.9  147.70  4996.4  147.20  5003.8  147.20  5004.3  147.70  5021.4  149.44
  5051.4  150.67  5081.4  153.18  5091.4  154.87  5141.4  160.50  5170.5  161.10
  5215.2  162.51  5268.8  162.93  5289.3  163.87  5311.6  163.70  5372.2  164.95
  5487.0  165.31  5601.7  167.21  5621.1  168.81  5632.9  168.28  5700.7  169.81
#Mann=6,-1,0
  4410.9    0.04       0  4740.6    0.12       0  4995.9    0.05       0
  5004.3    0.12       0  5170.5    0.05       0  5289.3    0.04       0
Bank Sta=4995.9,5004.3
Exp/Cntr=0.3,0.1

Type RM Length L Ch R = 1,2090,188,188,188
BEGIN DESCRIPTION:
Mapping XS 90c78efe
END DESCRIPTION:
XS GIS Cut Line= 4
      2529936.43     13524024.63      2529401.74     13523701.73
      2529061.46     13523653.12      2528464.23     13523903.12
#Sta/Elev= 30
  4238.1  182.56  4626.0  174.56  4770.3  170.79  4791.7  166.23  4822.7  163.55
  4849.9  163.54  4874.8  160.34  4930.1  156.45  4960.4  153.23  4980.6  149.13
  5006.7  147.20  5007.2  146.70  5015.2  147.20  5021.2  149.13  5068.2  152.69
  5081.7  153.64  5086.9  156.67  5092.0  153.50  5112.0  158.27  5132.2  160.31
  5172.6  160.12  5213.5  162.51  5351.4  164.53  5397.8  163.54  5409.8  160.15
  5419.4  160.12  5441.1  163.83  5462.8  164.64  5679.1  167.81  5853.9  172.40
#Mann=6,-1,0
  4238.1    0.04       0  4626.0    0.12       0  5006.7    0.05       0
  5015.2    0.12       0  5068.2    0.05       0  5679.1    0.04       0
Bank Sta=5006.7,5015.2
Exp/Cntr=0.3,0.1

Type RM Length L Ch R = 1,1902,296,296,296
BEGIN DESCRIPTION:
Mapping XS c0651d89
END DESCRIPTION:
XS GIS Cut Line= 3
      2529926.01     13523903.10      2529283.68     13523486.45
      2528512.85     13523715.62
#Sta/Elev= 30
  4282.5  178.13  4512.4  173.68  4628.9  173.33  4657.4  171.10  4761.5  169.27
  4802.5  168.52  4875.0  161.68  4932.3  158.85  4947.5  156.75  4953.4  157.22
  4962.6  155.04  4968.6  155.51  4989.7  152.44  4998.9  150.59  5004.8  147.96
  5021.7  146.09  5022.2  145.59  5030.2  146.09  5044.9  151.34  5056.3  152.49
  5061.5  151.79  5094.7  157.01  5127.9  159.60  5166.3  159.76  5200.9  162.13
  5218.6  162.27  5359.7  164.35  5622.0  165.19  5831.4  169.26  5852.3  169.59
#Mann=9,-1,0
  4282.5    0.04       0  4628.9    0.05       0  4761.5    0.03       0
  5021.7    0.03       0  5030.2    0.03       0  5200.9    0.12       0
  5218.6    0.05       0  5622.0    0.04       0  5831.4   0.013       0
Bank Sta=5021.7,5030.2
Exp/Cntr=0.3,0.1

Type RM Length L Ch R = 1,1606,227,227,227
BEGIN DESCRIPTION:
Mapping XS 43db4691
END DESCRIPTION:
XS GIS Cut Line= 3
      2530064.93     13523441.31      2529311.46     13523212.15
      2528579.42     13523517.45
#Sta/Elev= 30
  4226.6  184.84  4417.7  178.66  4550.5  174.07  4575.7  172.53  4608.6  168.50
  4634.2  167.56  4646.7  168.02  4655.1  169.63  4674.3  168.02  4679.5  168.72
  4745.3  164.07  4874.6  158.85  4969.9  151.90  4995.7  145.82  4996.2  145.32
  5004.3  145.82  5021.1  147.36  5030.6  149.75  5036.0  149.21  5059.8  153.33
  5112.9  156.03  5129.5  157.95  5136.7  159.92  5219.0  163.16  5319.7  165.35
  5377.8  165.23  5585.1  165.44  5634.2  165.31  5680.3  164.98  5807.3  167.23
#Mann=8,-1,0
  4226.6    0.04       0  4417.7    0.03       0  4969.9    0.12       0
  4995.7    0.05       0  5004.3    0.12       0  5377.8    0.05       0
  5585.1    0.12       0  5634.2    0.04       0
Bank Sta=4995.7,5004.3
Exp/Cntr=0.3,0.1

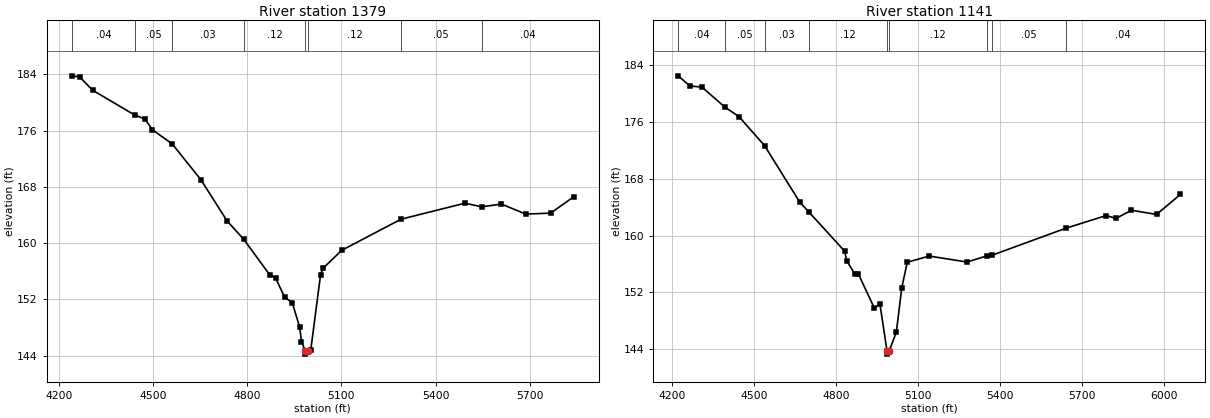
Type RM Length L Ch R = 1,1379,238,238,238
BEGIN DESCRIPTION:
Mapping XS 30d61daf
END DESCRIPTION:
XS GIS Cut Line= 3
      2530026.71     13523278.11      2529325.35     13522989.92
      2528579.44     13523378.49
#Sta/Elev= 30
  4241.3  183.79  4266.4  183.64  4308.0  181.73  4442.7  178.19  4474.4  177.65
  4498.3  176.12  4561.3  174.10  4652.9  169.00  4735.6  163.18  4789.3  160.53
  4871.7  155.49  4890.3  155.06  4919.6  152.29  4943.6  151.53  4967.5  148.01
  4973.0  145.99  4984.8  144.71  4985.3  144.21  4993.5  144.71  5002.7  144.83
  5033.8  155.50  5041.2  156.40  5101.4  158.98  5290.2  163.40  5494.0  165.68
  5546.6  165.16  5610.1  165.55  5687.2  164.13  5766.7  164.26  5840.6  166.60
#Mann=8,-1,0
  4241.3    0.04       0  4442.7    0.05       0  4561.3    0.03       0
  4789.3    0.12       0  4984.8    0.05       0  4993.5    0.12       0
  5290.2    0.05       0  5546.6    0.04       0
Bank Sta=4984.8,4993.5
Exp/Cntr=0.3,0.1

Type RM Length L Ch R = 1,1141,0,0,0
BEGIN DESCRIPTION:
Mapping XS 0bed628f
END DESCRIPTION:
XS GIS Cut Line= 4
      2530026.77     13523153.15      2529498.96     13522767.70
      2529117.01     13522767.70      2528554.54     13523337.12
#Sta/Elev= 30
  4222.4  182.50  4264.8  181.07  4308.8  180.92  4392.7  178.10  4444.7  176.75
  4538.4  172.65  4666.4  164.73  4700.9  163.29  4831.3  157.79  4837.8  156.49
  4867.2  154.66  4880.4  154.64  4939.9  149.77  4959.9  150.38  4985.6  143.81
  4986.1  143.31  4994.3  143.81  5019.9  146.40  5039.9  152.68  5059.9  156.25
  5139.9  157.12  5278.7  156.28  5351.2  157.15  5370.1  157.24  5639.2  161.03
  5787.8  162.83  5823.1  162.42  5879.7  163.57  5971.6  162.98  6058.3  165.79
#Mann=9,-1,0
  4222.4    0.04       0  4392.7    0.05       0  4538.4    0.03       0
  4700.9    0.12       0  4985.6    0.05       0  4994.3    0.12       0
  5351.2    0.04       0  5370.1    0.05       0  5639.2    0.04       0
Bank Sta=4985.6,4994.3
Exp/Cntr=0.3,0.1

Chan Stop Cuts=-1