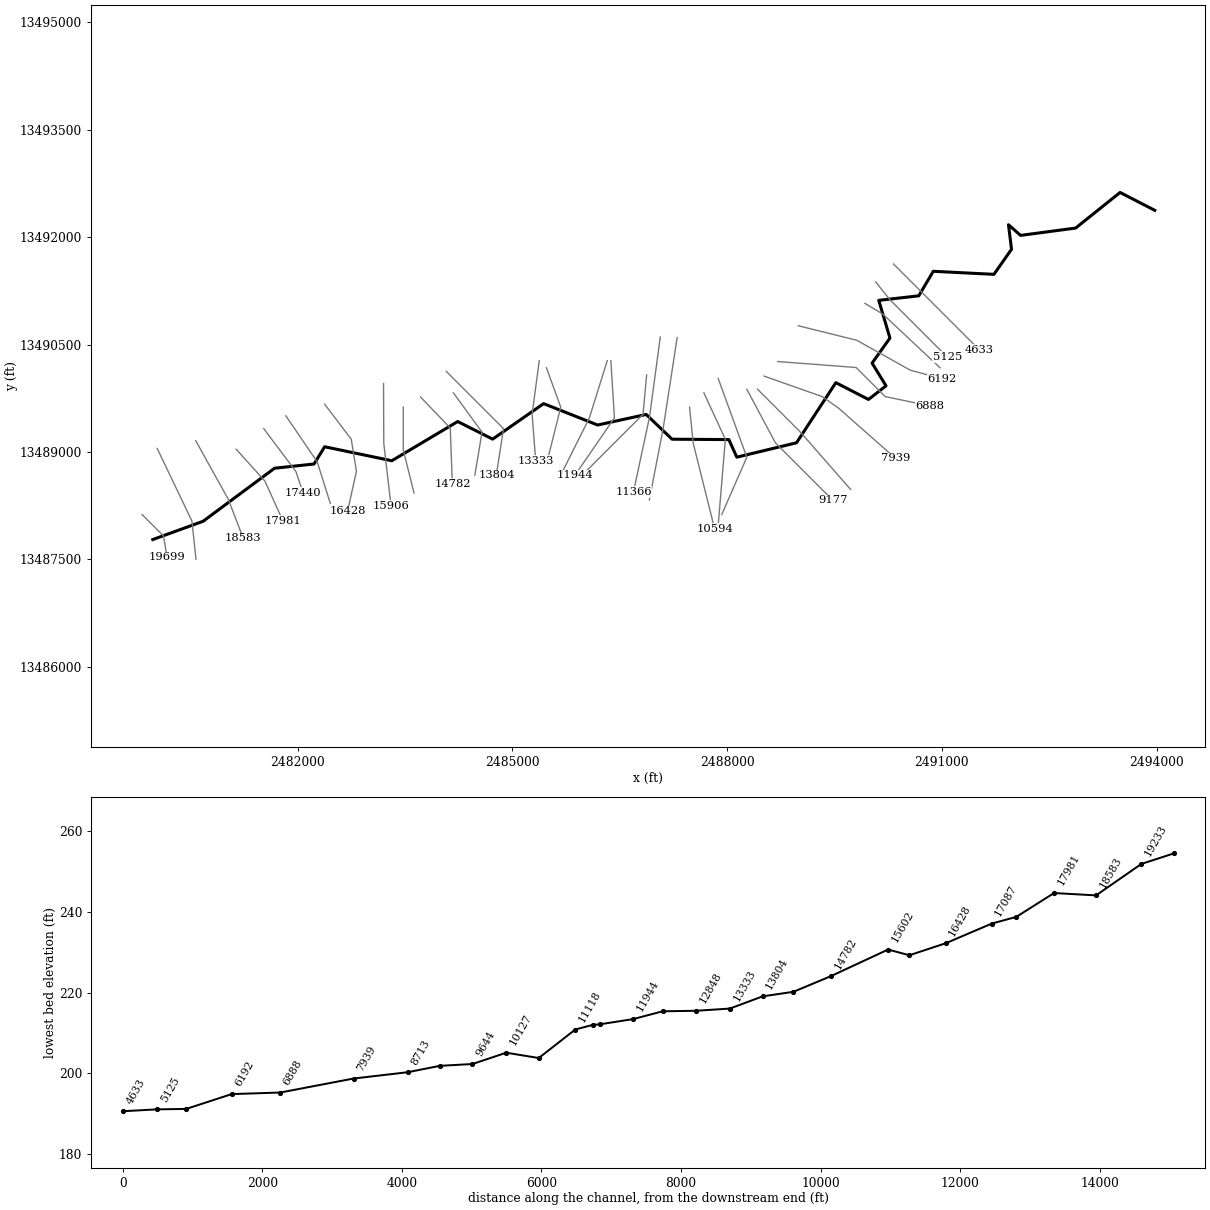
--- TRIB 4_1 TO EIGHTEENMILE CREEK.prj (project) ---

Proj Title=TRIB 4_1 TO EIGHTEENMILE CREEK Base Level Engineering
Current Plan=p01
Default Exp/Contr=0.3,0.1
English Units
Geom File=g01
Flow File=f01
Plan File=p01
Y Axis Title=Elevation
X Axis Title(PF)=Main Channel Distance
X Axis Title(XS)=Station
BEGIN DESCRIPTION:
XTRIB 4_1 TO EIGHTEENMILE CREEK
END DESCRIPTION:
DSS Export Rating Curves= 0
DSS Export Rating Curve Sorted= 0
DSS Export Volume Flow Curves= 0
DXF OffsetX= 0
DXF OffsetY= 0
DXF ScaleX= 1
DXF ScaleY= 10

--- TRIB 4_1 TO EIGHTEENMILE CREEK.p01 (plan) ---

Plan Title=Multiple Run
Short Identifier=Multiple
Geom File=g01
Flow File=f01
Subcritical Flow
K Sum by GR= 0
Std Step Tol= 0.01
Critical Tol= 0.01
Num of Std Step Trials= 20
Max Error Tol= 0.3
Flow Tol Ratio= 0.001
Split Flow NTrial= 30
Split Flow Tol= 0.02
Split Flow Ratio= 0.02
Log Output Level= 0
Friction Slope Method= 1
Unsteady Friction Slope Method= 2
Unsteady Bridges Friction Slope Method= 1
Parabolic Critical Depth
Global Vel Dist=  1 , 1 , 1
Global Log Level= 0
CheckData=True
Encroach Param= -1, 0, 0, 0
BEGIN DESCRIPTION:
Multiple Run
END DESCRIPTION:

--- TRIB 4_1 TO EIGHTEENMILE CREEK.f01 (steady flow) ---

Flow Title=Multiple
Number of Profiles=7
Profile Names=10-year,25-year,50-year,1pct_min,100-year,1pct_plu,500-year
River Rch & RM= TRIB 4_1 TO EIGH,Reach-1,19699
     512     812    1078     694    1384    2762    2256
River Rch & RM= TRIB 4_1 TO EIGH,Reach-1,15906
     932    1528    2074    1361    2715    5417    4604
River Rch & RM= TRIB 4_1 TO EIGH,Reach-1,10594
    1295    2157    2959    1960    3911    7803    6763
River Rch & RM= TRIB 4_1 TO EIGH,Reach-1,6888
    1534    2575    3550    2361    4712    9401    8222
River Rch & RM= TRIB 4_1 TO EIGH,Reach-1,5539
    1668    2802    3864    2569    5127   10229    8940
Boundary for River Rch & Prof#=TRIB 4_1 TO EIGH,Reach-1,1
Up Type=0
Dn Type=3
Dn Slope=0.005
Boundary for River Rch & Prof#=TRIB 4_1 TO EIGH,Reach-1,2
Up Type=0
Dn Type=3
Dn Slope=0.005
Boundary for River Rch & Prof#=TRIB 4_1 TO EIGH,Reach-1,3
Up Type=0
Dn Type=3
Dn Slope=0.005
Boundary for River Rch & Prof#=TRIB 4_1 TO EIGH,Reach-1,4
Up Type=0
Dn Type=3
Dn Slope=0.005
Boundary for River Rch & Prof#=TRIB 4_1 TO EIGH,Reach-1,5
Up Type=0
Dn Type=3
Dn Slope=0.005
Boundary for River Rch & Prof#=TRIB 4_1 TO EIGH,Reach-1,6
Up Type=0
Dn Type=3
Dn Slope=0.005
Boundary for River Rch & Prof#=TRIB 4_1 TO EIGH,Reach-1,7
Up Type=0
Dn Type=3
Dn Slope=0.005

--- TRIB 4_1 TO EIGHTEENMILE CREEK.g01 (geometry) ---

Geom Title=Existing Conditions
Program Version=4.10

River Reach=TRIB 4_1 TO EIGH,Reach-1
Reach XY= 30
        2479975.       13487775.       2480677.7     13488030.36
      2481676.45     13488771.47      2482227.71     13488830.41
      2482376.45     13489071.47      2483314.56     13488876.04
      2484235.44     13489423.96      2484723.54       13489178.
      2485435.43     13489673.95      2486190.22     13489375.24
      2486869.06     13489522.78      2487230.67     13489176.98
      2488023.78     13489171.57      2488135.27     13488925.96
      2488969.35     13489126.97      2489518.82     13489967.18
      2489974.91     13489732.28      2490219.94     13489922.71
      2490025.01     13490240.42      2490274.62     13490590.27
      2490118.57       13491117.      2490677.47     13491180.45
      2490880.46     13491522.94      2491727.46     13491480.45
      2491973.39     13491831.04      2491930.88     13492173.52
       2492099.8     13492024.64      2492869.07     13492127.24
      2493490.15     13492624.62        2493975.       13492375.

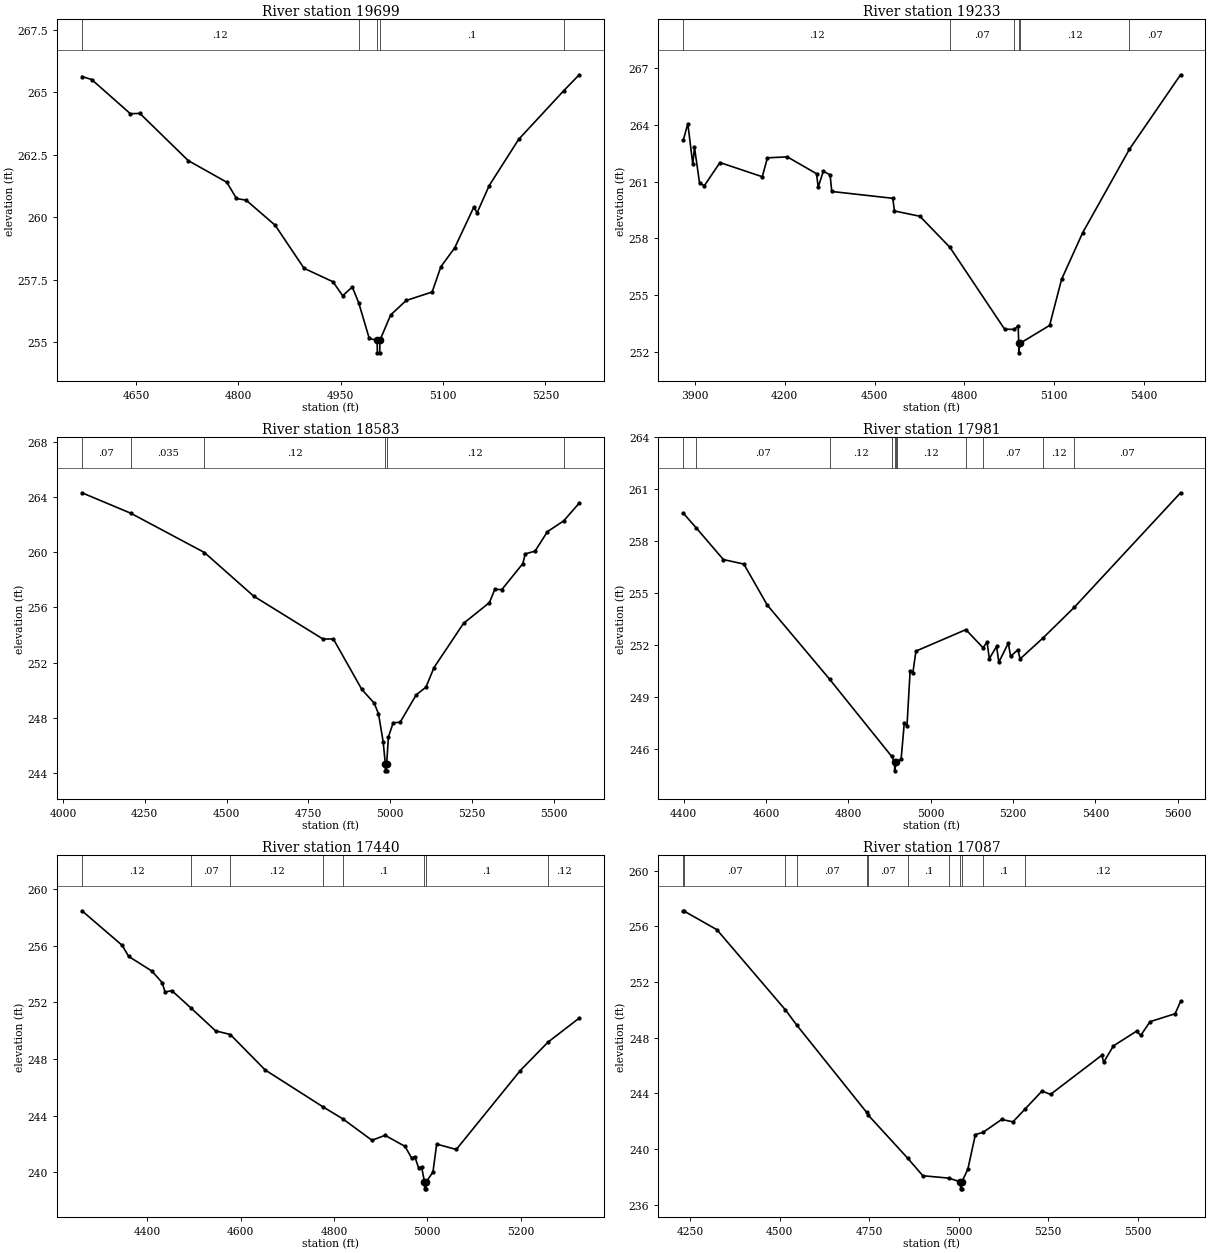
Type RM Length L Ch R = 1 ,19699   ,466,466,466
BEGIN DESCRIPTION:
TRIB TO TRIB 4 TO EIGHTEENMILE CREEK 40.0
END DESCRIPTION:
XS GIS Cut Line= 3
      2479824.97     13488125.03        2480125.       13487825.
      2480174.99     13487525.04
#Sta/Elev= 30
    4571  265.64  4585.2  265.52  4641.8  264.15  4655.9  264.16  4726.6  262.27
  4783.2   261.4  4797.3  260.75  4811.5  260.68  4853.9  259.68  4896.3  257.95
  4938.7  257.41  4952.9  256.85    4967   257.2  4976.5  256.56  4991.8  255.14
  5003.4  255.06  5003.7  254.56  5007.2  254.56  5007.4  255.06  5023.2  256.08
    5046  256.66    5084     257  5096.7  258.01    5117  258.77  5144.8  260.39
  5149.9  260.18  5167.6  261.27  5210.7  263.12  5276.7  265.07  5299.4  265.71
#Mann= 5 ,-1 , 0
    4571     .12       0  4976.5      .1       0  5003.4     .05       0
  5007.4      .1       0  5276.7     .07       0
Bank Sta=5003.4,5007.4
XS Rating Curve= 0 ,0
Exp/Cntr=0.3,0.1

Type RM Length L Ch R = 1 ,19233   ,650,650,650
BEGIN DESCRIPTION:
Mapping XS 415d9f0a
END DESCRIPTION:
XS GIS Cut Line= 3
      2480036.21      13489048.6       2480522.3     13488033.01
      2480578.68     13487499.61
#Sta/Elev= 30
  3860.8  263.19  3875.9  264.07  3892.6  261.91  3898.2  262.81  3915.3  260.91
  3931.3  260.79  3983.3  262.01  4124.8  261.26    4142  262.26  4208.5  262.31
  4306.2  261.42  4311.7  260.71  4328.9  261.55  4351.5  261.36  4357.1  260.48
  4561.1  260.12  4566.6  259.45  4651.8  259.17  4751.9  257.53  4934.9   253.2
  4967.6  253.19  4980.2  253.38  4982.1  252.45  4982.3  251.95  4986.1  252.45
  5085.3   253.4  5125.5  255.84  5195.9   258.3  5352.4  262.72  5523.1  266.65
#Mann= 6 ,-1 , 0
  3860.8     .12       0  4751.9     .07       0  4967.6     .12       0
  4982.1     .05       0  4986.1     .12       0  5352.4     .07       0
Bank Sta=4982.1,4986.1
XS Rating Curve= 0 ,0
Exp/Cntr=0.3,0.1

Type RM Length L Ch R = 1 ,18583   ,602,602,602
BEGIN DESCRIPTION:
Mapping XS eec6931e
END DESCRIPTION:
XS GIS Cut Line= 3
      2480574.39     13489157.14      2481030.11     13488336.83
      2481238.46     13487794.26
#Sta/Elev= 30
  4058.3  264.31  4207.2  262.83  4432.5  259.98  4582.9  256.82  4794.6  253.71
  4826.6  253.71  4913.6  250.05  4951.3  249.06  4964.5  248.29  4978.8  246.25
  4985.4  244.65  4985.6  244.15  4989.1  244.15  4989.4  244.65  4994.8  246.61
  5009.4  247.63  5030.8  247.68  5079.5  249.65  5109.6  250.22  5134.2  251.64
  5224.3  254.84  5303.6  256.35    5320  257.31  5341.4  257.29  5405.7  259.18
  5412.9  259.88    5443  260.08  5480.7  261.49  5530.3  262.27  5577.9  263.56
#Mann= 6 ,-1 , 0
  4058.3     .07       0  4207.2    .035       0  4432.5     .12       0
  4985.4     .05       0  4989.4     .12       0  5530.3     .07       0
Bank Sta=4985.4,4989.4
XS Rating Curve= 0 ,0
Exp/Cntr=0.3,0.1

Type RM Length L Ch R = 1 ,17981   ,541,541,541
BEGIN DESCRIPTION:
TRIB TO TRIB 4 TO EIGHTEENMILE CREEK 40.2
END DESCRIPTION:
XS GIS Cut Line= 3
      2481139.82     13489037.28      2481542.08     13488591.42
      2481792.02      13488038.6
#Sta/Elev= 30
  4399.5  259.62  4430.9  258.77  4496.8  256.94  4546.5  256.68  4603.3  254.31
  4754.5  250.03  4905.5  245.56  4912.4  245.23  4912.6  244.73  4916.4  245.23
  4918.1  245.23  4928.4  245.42  4935.9  247.48  4942.6  247.34  4950.1  250.49
  4956.8   250.4  4964.3  251.65  5085.5  252.89  5127.3  251.84  5136.9  252.18
  5142.4  251.21    5160  251.92  5165.5  251.01  5188.6  252.11  5194.1  251.34
  5211.7  251.73  5217.2   251.2  5273.3  252.42  5348.7  254.18  5606.7   260.8
#Mann= 11 ,-1 , 0
  4399.5     .05       0  4430.9     .07       0  4754.5     .12       0
  4905.5     .07       0  4912.4     .05       0  4916.4     .07       0
  4918.1     .12       0  5085.5      .1       0  5127.3     .07       0
  5273.3     .12       0  5348.7     .07       0
Bank Sta=4912.4,4916.4
XS Rating Curve= 0 ,0
Exp/Cntr=0.3,0.1

Type RM Length L Ch R = 1 ,17440   ,353,353,353
BEGIN DESCRIPTION:
TRIB TO TRIB 4 TO EIGHTEENMILE CREEK 35.0
END DESCRIPTION:
XS GIS Cut Line= 3
      2481524.98     13489325.03        2481975.       13488725.
      2482075.01     13488424.96
#Sta/Elev= 30
  4259.6  258.46  4346.1  256.01  4359.6  255.24  4409.6   254.2  4431.5  253.39
  4437.8  252.72  4452.3  252.82  4494.4  251.56  4546.1  249.98  4577.7  249.72
  4652.3  247.22  4776.5  244.61  4819.1  243.76  4881.5  242.25  4909.6   242.6
  4952.3  241.82  4966.9  240.98  4973.2   241.1  4981.5   240.3  4987.8  240.38
  4994.1  239.32  4994.3  238.82  4997.8  238.82  4998.1  239.32  5012.3  240.01
  5020.2  241.98  5062.3   241.6  5199.4  247.17  5258.9  249.18  5325.9  250.88
#Mann= 8 ,-1 , 0
  4259.6     .12       0  4494.4     .07       0  4577.7     .12       0
  4776.5     .07       0  4819.1      .1       0  4994.1     .05       0
  4998.1      .1       0  5258.9     .12       0
Bank Sta=4994.1,4998.1
XS Rating Curve= 0 ,0
Exp/Cntr=0.3,0.1

Type RM Length L Ch R = 1 ,17087   ,659,659,659
BEGIN DESCRIPTION:
Mapping XS e1bf9661
END DESCRIPTION:
XS GIS Cut Line= 3
      2481834.44     13489503.52      2482271.95     13488861.14
      2482455.62     13488278.94
#Sta/Elev= 30
  4231.4  257.11    4232  257.11  4325.2  255.75  4516.2     250  4548.1   248.9
    4743  242.64  4748.2  242.42  4858.3  239.33  4899.8  238.09  4972.2  237.92
  5004.9  237.65  5005.1  237.15  5008.6  237.15  5008.9  237.65  5025.5  238.56
  5046.5  241.05  5067.6   241.2  5119.9  242.13  5151.4  241.96  5184.5  242.86
  5232.4  244.17  5256.2  243.93  5399.4  246.74  5404.6  246.24  5431.7  247.41
  5496.4  248.47  5507.9  248.16    5534  249.15    5604  249.72  5619.1   250.6
#Mann= 12 ,-1 , 0
  4231.4     .05       0    4232     .07       0  4516.2     .12       0
  4548.1     .07       0    4743     .12       0  4748.2     .07       0
  4858.3      .1       0  4972.2     .12       0  5004.9     .05       0
  5008.9     .12       0  5067.6      .1       0  5184.5     .12       0
Bank Sta=5004.9,5008.9
XS Rating Curve= 0 ,0
Exp/Cntr=0.3,0.1

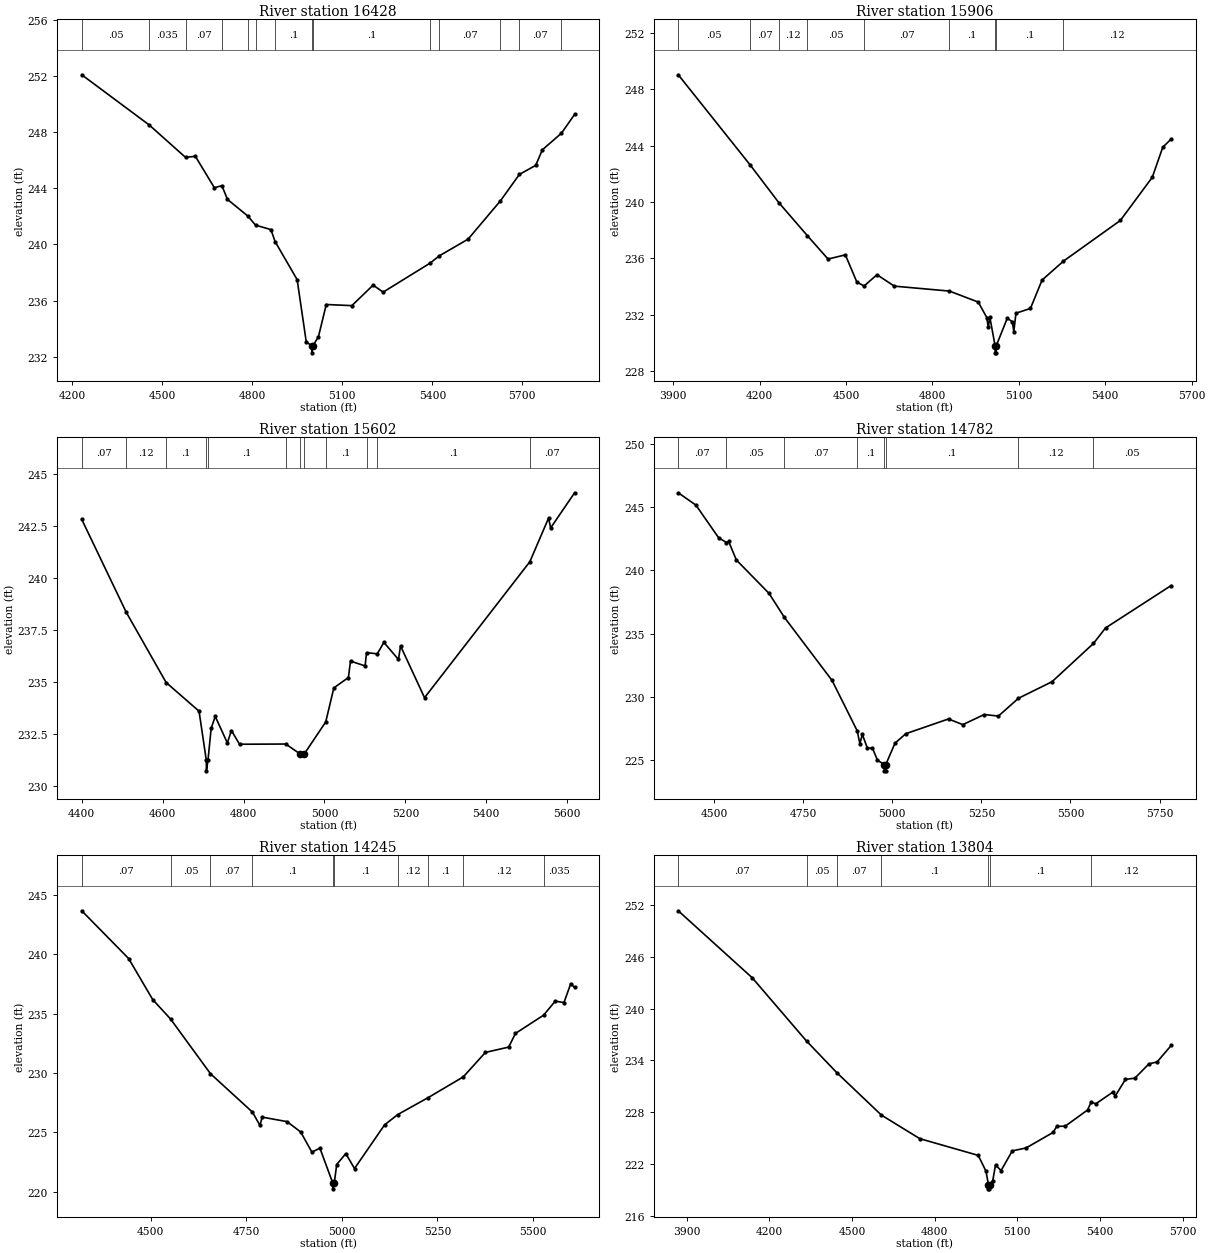
Type RM Length L Ch R = 1 ,16428   ,522,522,522
BEGIN DESCRIPTION:
Mapping XS 5195b5e2
END DESCRIPTION:
XS GIS Cut Line= 4
      2482376.12      13489666.7      2482747.65     13489177.11
      2482820.56     13488729.19      2482695.94     13488168.38
#Sta/Elev= 30
  4231.3  252.07  4456.1   248.5  4577.3  246.19    4610  246.27  4673.4  244.03
  4698.4  244.18  4717.1   243.2  4785.2  242.01  4810.5  241.37  4861.9  241.05
  4875.8   240.2  4949.3  237.49  4979.7  233.06    4998  232.78  4998.3  232.28
    5002  232.78  5020.3  233.43  5046.4  235.72  5131.7  235.64  5202.6   237.1
    5236   236.6  5392.1  238.66  5423.7  239.19  5519.1  240.37    5627   243.1
  5690.2  244.98  5744.5  245.62  5766.7  246.73  5830.3  247.91  5874.2  249.25
#Mann= 14 ,-1 , 0
  4231.3     .05       0  4456.1    .035       0  4577.3     .07       0
  4698.4     .12       0  4785.2     .07       0  4810.5     .12       0
  4875.8      .1       0    4998     .05       0    5002      .1       0
  5392.1     .12       0  5423.7     .07       0    5627      .1       0
  5690.2     .07       0  5830.3     .12       0
Bank Sta=4998,5002
XS Rating Curve= 0 ,0
Exp/Cntr=0.3,0.1

Type RM Length L Ch R = 1 ,15906   ,304,304,304
BEGIN DESCRIPTION:
Mapping XS 655ed977
END DESCRIPTION:
XS GIS Cut Line= 3
      2483199.04      13489954.9      2483202.51     13489118.08
       2483303.2     13488250.03
#Sta/Elev= 30
    3918  249.02  4168.5   242.6  4267.1  239.95  4365.7  237.62  4437.9  235.95
  4497.9  236.25  4537.9  234.32  4562.9  234.04  4607.9  234.84  4667.9  234.03
    4859  233.68  4959.3   232.9  4988.9   231.8    4994   231.1  4999.5  231.83
  5017.7   229.8  5017.9   229.3  5021.4   229.3  5021.7   229.8  5059.9  231.75
  5077.6  231.51  5082.7   230.8  5090.1  232.11  5140.5  232.45  5180.7  234.46
  5254.8   235.8  5452.6  238.69  5563.3  241.75  5599.7  243.88  5628.7  244.46
#Mann= 9 ,-1 , 0
    3918     .05       0  4168.5     .07       0  4267.1     .12       0
  4365.7     .05       0  4562.9     .07       0    4859      .1       0
  5017.7     .05       0  5021.7      .1       0  5254.8     .12       0
Bank Sta=5017.7,5021.7
XS Rating Curve= 0 ,0
Exp/Cntr=0.3,0.1

Type RM Length L Ch R = 1 ,15602   ,820,820,820
BEGIN DESCRIPTION:
TRIB TO TRIB 4 TO EIGHTEENMILE CREEK 31.0
END DESCRIPTION:
XS GIS Cut Line= 3
        2483475.     13489624.98        2483475.       13489025.
      2483624.99     13488425.04
#Sta/Elev= 30
  4400.1  242.82  4510.1  238.35  4608.7  234.97  4690.1  233.59  4708.1  231.22
  4708.3  230.72  4712.1  231.22  4720.1  232.77  4730.1  233.34  4760.1  232.06
  4770.1  232.66  4790.1     232  4904.5  232.01  4940.1  231.53  4950.1  231.53
  5003.2  233.07  5023.3  234.71  5059.3  235.21  5064.5     236  5100.6  235.77
  5104.1  236.41  5130.7  236.35    5147   236.9    5183  236.08  5188.2  236.73
  5247.5  234.24  5507.8  240.78  5554.1  242.88  5559.3  242.41  5618.5   244.1
#Mann= 12 ,-1 , 0
  4400.1     .07       0  4510.1     .12       0  4608.7      .1       0
  4708.1     .07       0  4712.1      .1       0  4904.5     .07       0
  4940.1     .05       0  4950.1     .07       0  5003.2      .1       0
  5104.1     .12       0  5130.7      .1       0  5507.8     .07       0
Bank Sta=4940.1,4950.1
XS Rating Curve= 0 ,0
Exp/Cntr=0.3,0.1

Type RM Length L Ch R = 1 ,14782   ,537,537,537
BEGIN DESCRIPTION:
TRIB TO TRIB 4 TO EIGHTEENMILE CREEK 40.4
END DESCRIPTION:
XS GIS Cut Line= 3
      2483716.27     13489766.38      2484131.18     13489332.83
      2484160.69     13488551.09
#Sta/Elev= 30
  4399.9  246.15  4449.5  245.17    4513  242.59  4535.1  242.21  4541.3  242.29
  4562.7  240.83  4654.5  238.18  4697.5  236.28  4831.3  231.28  4901.8  227.29
  4909.3  226.27  4916.2     227  4930.3  225.93  4944.5  225.93  4958.6  224.96
    4978  224.62  4978.3  224.12  4981.8  224.12    4982  224.62  5007.8  226.31
  5037.9  227.06  5157.9  228.23    5198  227.78    5258  228.58    5298  228.46
  5354.1  229.87  5448.2  231.18  5564.4  234.21  5598.3  235.44  5782.3   238.8
#Mann= 8 ,-1 , 0
  4399.9     .07       0  4535.1     .05       0  4697.5     .07       0
  4901.8      .1       0    4978     .05       0    4982      .1       0
  5354.1     .12       0  5564.4     .05       0
Bank Sta=4978,4982
XS Rating Curve= 0 ,0
Exp/Cntr=0.3,0.1

Type RM Length L Ch R = 1 ,14245   ,441,441,441
BEGIN DESCRIPTION:
TRIB TO TRIB 4 TO EIGHTEENMILE CREEK 28.0
END DESCRIPTION:
XS GIS Cut Line= 3
        2484175.       13489825.        2484575.       13489275.
      2484475.01     13488675.05
#Sta/Elev= 30
  4320.1  243.66  4442.6  239.64  4505.6  236.18  4552.1  234.55  4656.5  229.94
  4766.4   226.7  4785.7  225.59  4791.9  226.28  4856.8   225.9  4892.4  225.03
  4921.7  223.33  4942.6  223.67  4976.1  220.74  4976.3  220.24  4980.2  220.74
  4986.6  222.29  5010.3  223.21  5033.1  221.95  5111.7  225.63  5146.3   226.5
    5226  227.93  5317.4  229.67  5375.3  231.73  5436.1  232.18  5453.8  233.33
  5527.4  234.87  5557.8  236.05  5580.6  235.93  5598.3  237.52  5608.4   237.2
#Mann= 10 ,-1 , 0
  4320.1     .07       0  4552.1     .05       0  4656.5     .07       0
  4766.4      .1       0  4976.1     .05       0  4980.2      .1       0
  5146.3     .12       0    5226      .1       0  5317.4     .12       0
  5527.4    .035       0
Bank Sta=4976.1,4980.2
XS Rating Curve= 0 ,0
Exp/Cntr=0.3,0.1

Type RM Length L Ch R = 1 ,13804   ,471,471,471
BEGIN DESCRIPTION:
TRIB TO TRIB 4 TO EIGHTEENMILE CREEK 27.0
END DESCRIPTION:
XS GIS Cut Line= 3
        2484075.       13490125.        2484875.       13489325.
        2484775.     13488675.02
#Sta/Elev= 30
  3869.1  251.37  4137.8  243.59  4334.6  236.26  4444.9  232.58  4606.7  227.66
  4745.9  224.93    4958  222.99  4986.3  221.14  4994.8  219.61  4995.1  219.11
  4998.7  219.11    4999  219.61  5010.6  220.06  5020.7  221.88  5040.9  221.23
  5081.4  223.51    5132  223.86  5229.4  225.65  5243.3  226.36  5273.6  226.38
  5354.6  228.25  5367.7  229.17  5384.9  228.98  5445.6  230.31  5455.8  229.91
  5492.4  231.81  5526.6  231.95  5577.2   233.6  5607.5  233.84  5658.1  235.74
#Mann= 7 ,-1 , 0
  3869.1     .07       0  4334.6     .05       0  4444.9     .07       0
  4606.7      .1       0  4994.8     .05       0    4999      .1       0
  5367.7     .12       0
Bank Sta=4994.8,4999
XS Rating Curve= 0 ,0
Exp/Cntr=0.3,0.1

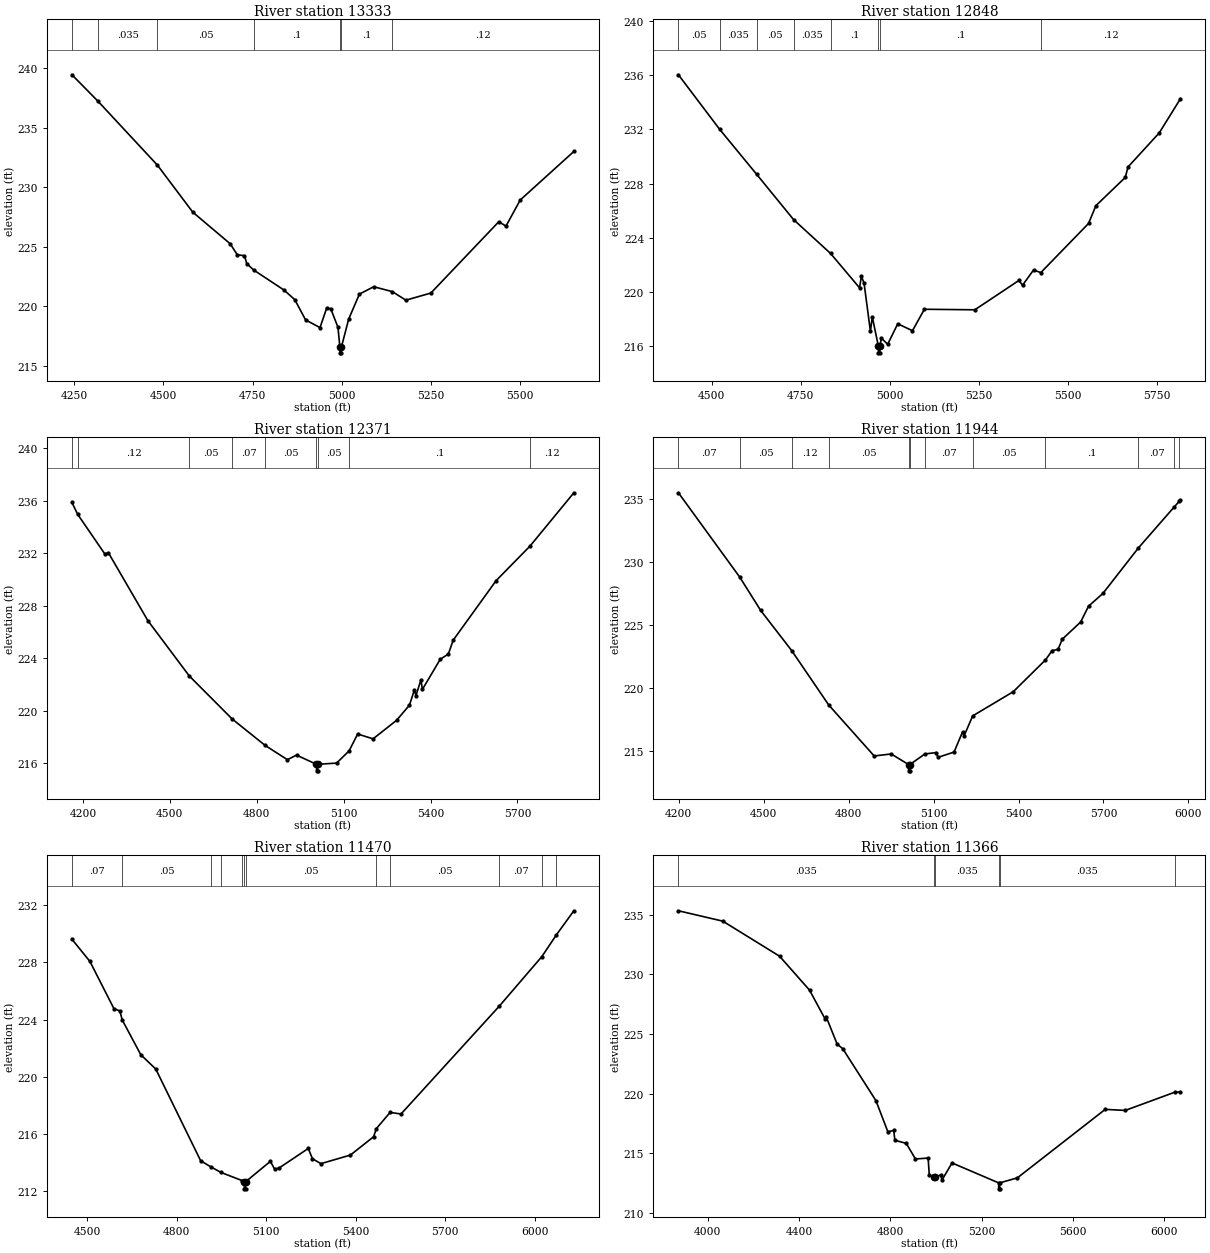
Type RM Length L Ch R = 1 ,13333   ,485,485,485
BEGIN DESCRIPTION:
TRIB TO TRIB 4 TO EIGHTEENMILE CREEK 26.0
END DESCRIPTION:
XS GIS Cut Line= 3
      2485374.99     13490274.96        2485275.       13489525.
        2485325.     13488875.02
#Sta/Elev= 30
  4243.1  239.47  4315.7  237.26  4482.9  231.87  4582.3  227.91    4687  225.26
  4707.1  224.33  4727.3  224.25  4733.6  223.59  4752.9  223.05  4838.3  221.36
  4868.5  220.55  4898.8  218.85  4939.2   218.2  4958.1  219.86  4969.4  219.79
  4989.6  218.23  4994.9  216.58  4995.2  216.08  4999.1  216.08  4999.4  216.58
  5019.8  218.93  5049.8  221.02    5090  221.64  5142.1  221.23  5180.2  220.51
  5250.4  221.11    5441  227.11  5461.1  226.74  5501.2  228.94  5651.6  233.02
#Mann= 7 ,-1 , 0
  4243.1     .05       0  4315.7    .035       0  4482.9     .05       0
  4752.9      .1       0  4994.9     .05       0  4999.4      .1       0
  5142.1     .12       0
Bank Sta=4994.9,4999.4
XS Rating Curve= 0 ,0
Exp/Cntr=0.3,0.1

Type RM Length L Ch R = 1 ,12848   ,477,477,477
BEGIN DESCRIPTION:
TRIB TO TRIB 4 TO EIGHTEENMILE CREEK 25.0
END DESCRIPTION:
XS GIS Cut Line= 3
      2485475.01     13490174.97        2485675.       13489625.
      2485475.01     13488825.02
#Sta/Elev= 30
  4406.5  236.01  4522.4  231.99  4626.2  228.68  4730.1  225.34  4833.9  222.85
  4915.2  220.32  4920.5  221.16  4927.9  220.67  4945.8  217.12  4951.1  218.17
  4968.1  216.03  4968.5  215.53  4972.4  215.53  4972.7  216.03  4976.4  216.61
  4994.3  216.16  5022.6  217.67  5063.9  217.16  5097.4  218.74  5239.1   218.7
  5362.8  220.86  5373.1  220.51    5404  221.63  5424.4  221.44  5558.6  225.06
  5579.2  226.37  5661.7  228.45  5669.4  229.22  5757.1  231.73  5816.3  234.23
#Mann= 8 ,-1 , 0
  4406.5     .05       0  4522.4    .035       0  4626.2     .05       0
  4730.1    .035       0  4833.9      .1       0  4968.1     .05       0
  4972.7      .1       0  5424.4     .12       0
Bank Sta=4968.1,4972.7
XS Rating Curve= 0 ,0
Exp/Cntr=0.3,0.1

Type RM Length L Ch R = 1 ,12371   ,427,427,427
BEGIN DESCRIPTION:
TRIB TO TRIB 4 TO EIGHTEENMILE CREEK 24.0
END DESCRIPTION:
XS GIS Cut Line= 3
      2486324.99     13490274.96        2486075.       13489475.
      2485675.01     13488675.03
#Sta/Elev= 30
  4162.2  235.88  4182.1  234.97  4275.8  231.95  4287.9  232.05  4424.1  226.87
  4567.1  222.65  4715.5  219.36    4829  217.35    4906  216.26  4937.4  216.61
  5006.3  215.91  5006.6  215.41  5010.7  215.41    5011  215.91  5075.8     216
  5119.1  216.94  5148.4  218.22  5201.6  217.85  5282.6  219.26  5327.3  220.42
  5344.1  221.58  5349.7  221.14  5366.5  222.33  5372.1  221.63  5433.5  223.92
  5461.5  224.32  5478.3  225.38  5626.4  229.92  5743.2  232.55  5894.7  236.62
#Mann= 9 ,-1 , 0
  4162.2     .07       0  4182.1     .12       0  4567.1     .05       0
  4715.5     .07       0    4829     .05       0  5006.3     .05       0
    5011     .05       0  5119.1      .1       0  5743.2     .12       0
Bank Sta=5006.3,5011
XS Rating Curve= 0 ,0
Exp/Cntr=0.3,0.1

Type RM Length L Ch R = 1 ,11944   ,474,474,474
BEGIN DESCRIPTION:
TRIB TO TRIB 4 TO EIGHTEENMILE CREEK 23.0
END DESCRIPTION:
XS GIS Cut Line= 3
        2486375.     13490274.98        2486425.       13489475.
      2485874.98     13488674.97
#Sta/Elev= 30
  4198.9  235.53  4415.3  228.84  4489.4  226.19  4598.7  223.01  4729.9  218.68
  4890.2  214.64  4950.3   214.8  5011.6  213.96  5011.9  213.46    5016  213.46
  5016.4  213.96  5069.2   214.8  5109.4  214.91  5115.5  214.53  5172.3  214.95
  5202.1  216.54  5208.1  216.26  5238.1  217.82  5381.3  219.74    5495  222.26
  5518.7     223  5539.6   223.1  5554.5  223.91  5619.3  225.27  5647.2  226.53
  5697.9  227.54  5823.5  231.16  5950.7  234.43  5967.4  234.85  5971.3  234.92
#Mann= 12 ,-1 , 0
  4198.9     .07       0  4415.3     .05       0  4598.7     .12       0
  4729.9     .05       0  5011.6     .05       0  5016.4     .05       0
  5069.2     .07       0  5238.1     .05       0    5495      .1       0
  5823.5     .07       0  5950.7     .12       0  5967.4     .07       0
Bank Sta=5011.6,5016.4
XS Rating Curve= 0 ,0
Exp/Cntr=0.3,0.1

Type RM Length L Ch R = 1 ,11470   ,104,104,104
BEGIN DESCRIPTION:
TRIB TO TRIB 4 TO EIGHTEENMILE CREEK 22.0
END DESCRIPTION:
XS GIS Cut Line= 3
        2486875.     13490075.05        2486825.       13489525.
      2486024.99     13488724.99
#Sta/Elev= 30
  4448.2  229.62  4508.5  228.07  4588.8  224.78  4608.9  224.61  4616.9  223.98
  4679.2  221.55  4729.4  220.55    4880  214.14  4914.7  213.71  4947.6  213.33
  5019.9  212.75  5026.4  212.68  5026.8  212.18  5030.9  212.18  5031.2  212.68
  5113.7   214.1  5127.8  213.57  5141.9  213.62  5240.9     215  5255.1  214.28
  5283.4  213.94  5382.4  214.54  5460.1  215.82  5469.4  216.39  5515.5  217.52
  5552.1  217.41  5881.1  224.93  6024.6  228.41  6073.4  229.93  6131.9  231.61
#Mann= 12 ,-1 , 0
  4448.2     .07       0  4616.9     .05       0  4914.7    .035       0
  4947.6     .12       0  5019.9     .05       0  5026.4     .05       0
  5031.2     .05       0  5469.4     .07       0  5515.5     .05       0
  5881.1     .07       0  6024.6     .05       0  6073.4     .07       0
Bank Sta=5026.4,5031.2
XS Rating Curve= 0 ,0
Exp/Cntr=0.3,0.1

Type RM Length L Ch R = 1 ,11366   ,248,248,248
BEGIN DESCRIPTION:
TRIB TO TRIB 4 TO EIGHTEENMILE CREEK 40.5
END DESCRIPTION:
XS GIS Cut Line= 3
      2487065.69     13490604.52      2486915.48     13489486.16
      2486690.91     13488438.86
#Sta/Elev= 30
  3871.6  235.33  4066.2  234.46  4315.1  231.52  4446.2  228.68  4513.6  226.29
  4518.6  226.47  4567.3  224.15  4591.5  223.78  4737.2  219.42  4789.3  216.82
  4815.2  216.92  4820.2   216.1    4870  215.84  4910.4  214.53  4965.9  214.61
    4971  213.18  4991.1     213  4998.1     213  5021.3  213.21  5026.4  212.76
  5070.7   214.2  5274.9  212.53  5275.3  212.03  5279.4  212.03  5279.7  212.53
    5357  212.95  5742.1  218.69  5829.6   218.6  6047.1  220.13  6071.1  220.14
#Mann= 6 ,-1 , 0
  3871.6    .035       0  4991.1    .035       0  4998.1    .035       0
  5274.9    .035       0  5279.7    .035       0  6047.1     .05       0
Bank Sta=4991.1,4998.1
XS Rating Curve= 0 ,0
Exp/Cntr=0.3,0.1

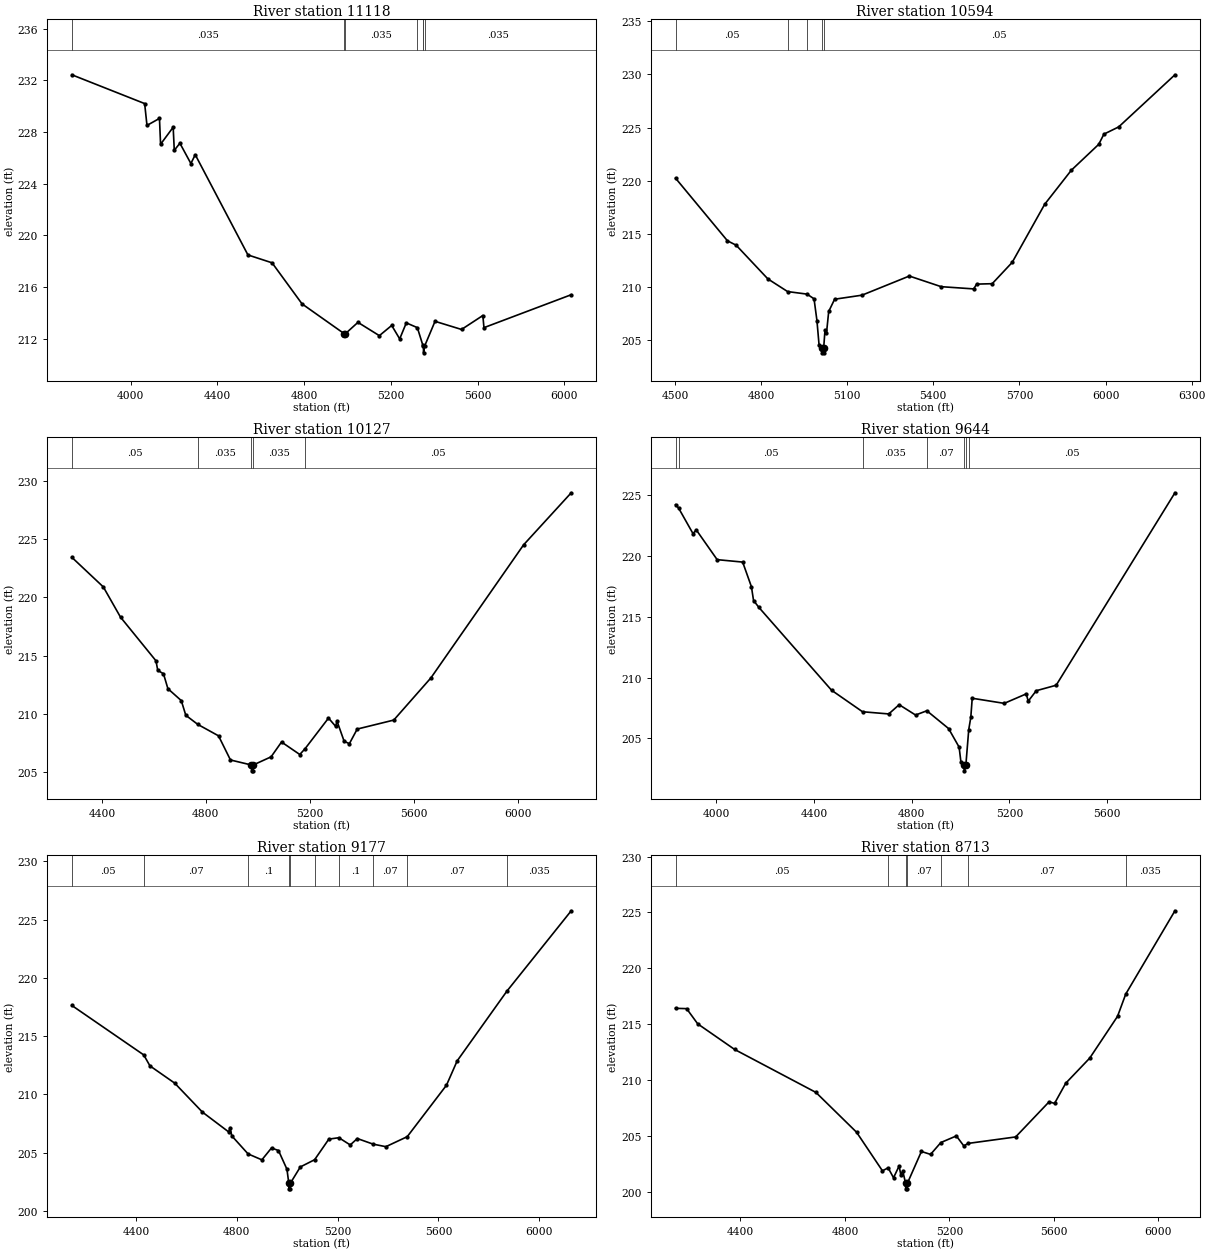
Type RM Length L Ch R = 1 ,11118   ,524,524,524
BEGIN DESCRIPTION:
TRIB TO TRIB 4 TO EIGHTEENMILE CREEK 40.6
END DESCRIPTION:
XS GIS Cut Line= 3
      2487301.79      13490597.5      2487108.42      13489341.7
      2486913.23     13488328.33
#Sta/Elev= 30
  3729.4  232.42  4065.2  230.19  4075.9   228.5  4133.5  229.04  4138.6  227.04
  4196.7  228.36  4201.8  226.57  4227.7  227.12  4278.3  225.55  4298.5  226.23
  4541.4  218.47  4652.7  217.86  4790.9  214.68  4985.6  212.37  4990.6  212.37
  5048.6  213.25  5147.3  212.22  5204.3  213.01  5241.1  211.97  5271.6  213.21
  5322.6  212.84  5347.2  211.51  5350.6  211.39    5351  210.89  5355.5  211.39
    5404  213.33  5526.2   212.7  5624.5  213.78  5629.6  212.84    6032  215.39
#Mann= 7 ,-1 , 0
  3729.4    .035       0  4985.6    .035       0  4990.6    .035       0
  5322.6     .07       0  5347.2    .035       0  5350.6    .035       0
  5355.5    .035       0
Bank Sta=4985.6,4990.6
XS Rating Curve= 0 ,0
Exp/Cntr=0.3,0.1

Type RM Length L Ch R = 1 ,10594   ,467,467,467
BEGIN DESCRIPTION:
TRIB TO TRIB 4 TO EIGHTEENMILE CREEK 20.0
END DESCRIPTION:
XS GIS Cut Line= 3
        2487475.     13489625.04        2487525.       13489125.
      2487825.01     13487924.97
#Sta/Elev= 30
  4502.3  220.24  4683.2  214.35  4713.4  213.94  4823.9  210.77  4892.6  209.58
  4960.3  209.34  4984.7   208.9  4994.8  206.86  5002.3  204.53  5011.8  204.32
  5012.3  203.82  5017.9  203.82  5018.4  204.32  5022.9  205.96    5028  205.65
  5035.8  207.71  5056.4  208.86  5151.7  209.24  5316.6  211.04  5427.5  210.04
  5540.8  209.83  5551.1  210.28  5605.3  210.32  5674.8  212.32  5788.2  217.79
    5881  220.99  5976.3  223.42  5994.4  224.38  6045.9  225.06  6241.8  229.96
#Mann= 5 ,-1 , 0
  4502.3     .05       0  4892.6    .035       0  4960.3     .05       0
  5011.8     .05       0  5018.4     .05       0
Bank Sta=5011.8,5018.4
XS Rating Curve= 0 ,0
Exp/Cntr=0.3,0.1

Type RM Length L Ch R = 1 ,10127   ,483,483,483
BEGIN DESCRIPTION:
TRIB TO TRIB 4 TO EIGHTEENMILE CREEK 19.0
END DESCRIPTION:
XS GIS Cut Line= 3
      2487675.01     13489824.99        2487975.       13489175.
        2487875.     13487975.04
#Sta/Elev= 30
  4284.7  223.43  4405.8  220.89  4471.9   218.3  4608.2  214.56  4615.1  213.74
  4637.1  213.45  4654.1  212.17  4705.5  211.15  4722.9  209.89    4769  209.11
  4848.7  208.13  4894.6  206.06  4975.3  205.63  4975.8  205.13  4981.4  205.13
  4981.9  205.63  5050.8  206.33  5090.9   207.6  5161.1  206.53  5181.9  207.04
  5271.5  209.65  5299.1  208.94  5304.1   209.4  5331.7  207.66  5351.8  207.46
  5381.9  208.71  5522.4  209.48  5665.4   213.1  6021.6   224.5  6204.7  228.96
#Mann= 5 ,-1 , 0
  4284.7     .05       0    4769    .035       0  4975.3    .035       0
  4981.9    .035       0  5181.9     .05       0
Bank Sta=4975.3,4981.9
XS Rating Curve= 0 ,0
Exp/Cntr=0.3,0.1

Type RM Length L Ch R = 1 ,9644    ,467,467,467
BEGIN DESCRIPTION:
TRIB TO TRIB 4 TO EIGHTEENMILE CREEK 18.0
END DESCRIPTION:
XS GIS Cut Line= 3
        2487875.       13490025.        2488275.       13488925.
      2487924.99     13488124.98
#Sta/Elev= 30
  3833.6  224.22  3845.9  223.95  3904.8  221.85  3918.7  222.14  4003.9   219.7
  4108.3   219.5  4144.2  217.47  4152.8  216.34  4174.8  215.77    4472  208.96
  4598.8  207.19  4706.1  207.01  4748.7  207.77  4815.9  206.92    4862  207.27
  4950.9  205.81  4994.1  204.28  5001.4  203.07  5015.1  202.83  5015.6  202.33
  5021.8  202.83  5033.5  205.73  5041.9  206.73  5047.7   208.3  5178.7  207.88
  5268.8  208.66  5276.9  208.06  5309.7  208.92  5391.2  209.37  5877.3   225.2
#Mann= 7 ,-1 , 0
  3833.6    .035       0  3845.9     .05       0  4598.8    .035       0
    4862     .07       0  5015.1     .05       0  5021.8     .07       0
  5033.5     .05       0
Bank Sta=5015.1,5021.8
XS Rating Curve= 0 ,0
Exp/Cntr=0.3,0.1

Type RM Length L Ch R = 1 ,9177    ,464,464,464
BEGIN DESCRIPTION:
TRIB TO TRIB 4 TO EIGHTEENMILE CREEK 17.0
END DESCRIPTION:
XS GIS Cut Line= 3
      2488275.02     13489874.97        2488675.       13489125.
      2489474.98     13488325.02
#Sta/Elev= 30
  4145.5  217.63  4430.9  213.38  4455.4  212.44  4553.5  210.96  4663.6  208.47
  4767.7  206.77  4773.4  207.14  4780.1  206.43  4844.7  204.88  4899.5  204.37
  4937.7  205.39  4965.4  205.17    4999  203.56  5006.2  202.38  5006.7  201.88
  5012.5  201.88    5013  202.38    5052  203.76  5108.7  204.38  5165.2  206.15
    5205  206.27    5250  205.65  5278.3   206.2  5340.6  205.72  5391.4   205.5
  5476.2  206.36  5631.9  210.78  5674.3  212.87  5871.3  218.85  6126.8  225.76
#Mann= 10 ,-1 , 0
  4145.5     .05       0  4430.9     .07       0  4844.7      .1       0
  5006.2     .05       0    5013      .1       0  5108.7     .07       0
    5205      .1       0  5340.6     .07       0  5476.2     .07       0
  5871.3    .035       0
Bank Sta=5006.2,5013
XS Rating Curve= 0 ,0
Exp/Cntr=0.3,0.1

Type RM Length L Ch R = 1 ,8713    ,774,774,774
BEGIN DESCRIPTION:
TRIB TO TRIB 4 TO EIGHTEENMILE CREEK 16.0
END DESCRIPTION:
XS GIS Cut Line= 3
      2488424.99     13489875.01        2489025.       13489275.
      2489725.03     13488474.97
#Sta/Elev= 30
  4151.5  216.43  4193.9   216.4  4236.4  215.04  4377.8  212.75  4688.9  208.91
  4844.5  205.35  4943.5   201.9  4965.2  202.17  4985.9  201.28  5007.2  202.33
  5013.8  201.56  5021.4  201.86  5032.2  200.79  5032.7  200.29  5038.5  200.29
    5039  200.79  5092.6  203.63  5127.7  203.37  5167.1  204.43  5226.4  205.02
  5254.9  204.13    5271  204.35  5453.3  204.93  5581.4  208.07  5602.3  207.93
    5645  209.73    5737  211.98  5843.3  215.71  5874.9  217.71  6063.1  225.15
#Mann= 7 ,-1 , 0
  4151.5     .05       0  4965.2     .07       0  5032.2     .05       0
    5039     .07       0  5167.1      .1       0    5271     .07       0
  5874.9    .035       0
Bank Sta=5032.2,5039
XS Rating Curve= 0 ,0
Exp/Cntr=0.3,0.1

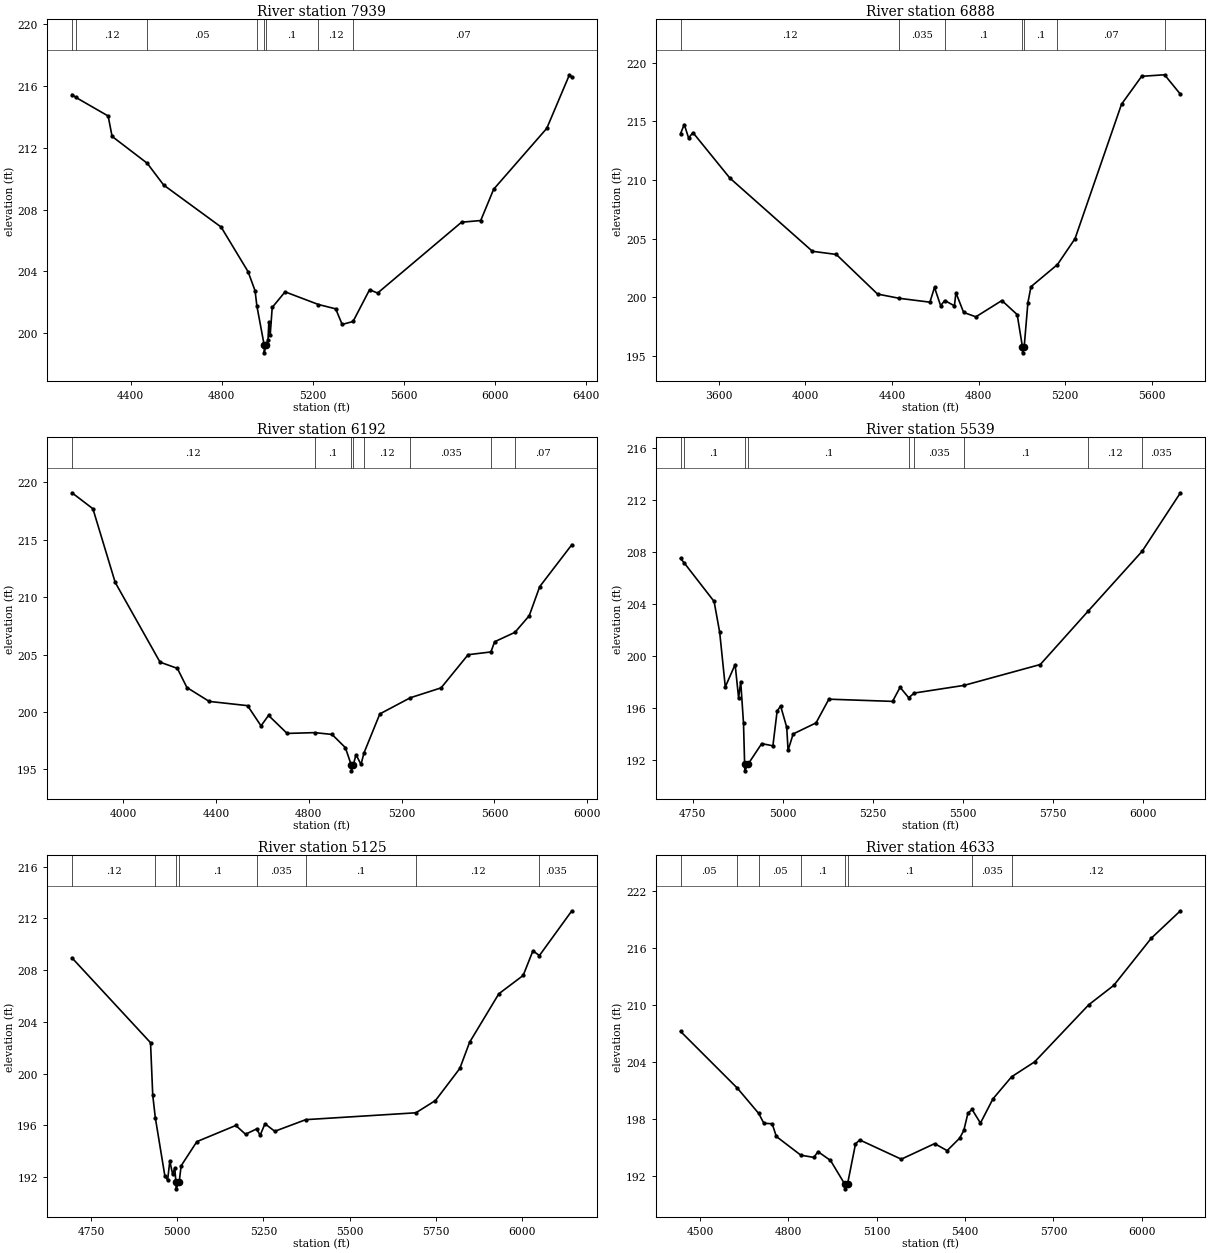
Type RM Length L Ch R = 1 ,7939    ,1051,1051,1051
BEGIN DESCRIPTION:
Mapping XS df717d77
END DESCRIPTION:
XS GIS Cut Line= 4
      2488515.02     13490059.05      2489327.51      13489772.6
      2489556.67     13489611.14      2490348.33     13488913.23
#Sta/Elev= 30
  4141.7  215.46  4159.3  215.27  4300.7  214.07    4318  212.75  4472.4  211.01
  4544.6   209.6  4797.1  206.88  4915.6  203.99  4946.5  202.75  4954.3  201.78
  4986.5  199.23    4987  198.73  4993.4  199.23  5003.2  199.54    5007  200.71
  5013.1  199.91  5021.8  201.67  5078.4  202.68  5225.1  201.86  5300.8  201.58
  5329.3  200.57  5377.1  200.76  5449.8  202.82  5484.9   202.6  5853.9  207.19
  5938.3   207.3  5995.3  209.33  6228.6  213.27  6328.2  216.74  6338.9  216.58
#Mann= 8 ,-1 , 0
  4141.7    .035       0  4159.3     .12       0  4472.4     .05       0
  4954.3      .1       0  4986.5     .05       0  4993.4      .1       0
  5225.1     .12       0  5377.1     .07       0
Bank Sta=4986.5,4993.4
XS Rating Curve= 0 ,0
Exp/Cntr=0.3,0.1

Type RM Length L Ch R = 1 ,6888    ,696,696,696
BEGIN DESCRIPTION:
Mapping XS 6e3963ff
END DESCRIPTION:
XS GIS Cut Line= 4
      2488707.76     13490262.18      2489801.47     13490178.85
      2490207.72      13489772.6      2490831.33     13489642.68
#Sta/Elev= 30
    3424  213.95  3441.3  214.73  3461.3  213.58  3481.4  214.04  3651.9  210.16
    4033  203.92  4143.3  203.65  4333.9  200.27  4434.2  199.91  4575.6  199.58
  4596.8  200.84  4625.1  199.28    4644  199.72  4688.7  199.27  4695.8  200.38
  4731.2  198.71  4787.7  198.33  4907.9  199.72  4978.6  198.52    5003  195.76
  5003.5  195.26  5010.9  195.76  5028.1  199.54  5042.3   200.9  5164.7  202.79
  5245.8     205  5460.4  216.46  5553.4  218.84  5659.2  218.97  5732.4  217.31
#Mann= 7 ,-1 , 0
    3424     .12       0  4434.2    .035       0    4644      .1       0
    5003     .05       0  5010.9      .1       0  5164.7     .07       0
  5659.2     .12       0
Bank Sta=5003,5010.9
XS Rating Curve= 0 ,0
Exp/Cntr=0.3,0.1

Type RM Length L Ch R = 1 ,6192    ,653,653,653
BEGIN DESCRIPTION:
Mapping XS febc4a23
END DESCRIPTION:
XS GIS Cut Line= 4
      2488994.19     13490762.17      2489811.88     13490559.05
      2490556.67     13490142.39      2490999.39     13490022.59
#Sta/Elev= 30
    3779   219.1  3869.2  217.71  3965.3  211.29  4158.6  204.34  4233.2   203.8
  4274.4  202.13  4370.5  200.92  4535.9  200.55  4593.8  198.79  4626.2   199.7
  4706.3  198.13    4826   198.2  4900.1  198.04  4957.4  196.89  4982.9  195.37
  4983.4  194.87  4991.4  195.37  5003.1  196.28  5024.8  195.43  5037.4  196.42
  5105.9  199.83  5237.5  201.24  5369.9   202.1  5486.4  204.99  5584.6  205.23
  5600.8  206.12  5688.4  206.94  5749.9  208.39    5795  210.92  5933.6  214.58
#Mann= 8 ,-1 , 0
    3779     .12       0    4826      .1       0  4982.9     .05       0
  4991.4      .1       0  5037.4     .12       0  5237.5    .035       0
  5584.6      .1       0  5688.4     .07       0
Bank Sta=4982.9,4991.4
XS Rating Curve= 0 ,0
Exp/Cntr=0.3,0.1

Type RM Length L Ch R = 1 ,5539    ,414,414,414
BEGIN DESCRIPTION:
TRIB TO TRIB 4 TO EIGHTEENMILE CREEK 10.0
END DESCRIPTION:
XS GIS Cut Line= 3
      2489925.04     13491074.98        2490175.       13490925.
      2490975.01     13490174.99
#Sta/Elev= 30
  4716.7  207.49  4726.3  207.17  4809.9  204.19  4825.5  201.81    4841  197.63
  4868.3  199.35    4878  196.78  4883.8  198.04  4891.6  194.83  4894.7  191.69
  4895.2  191.19    4904  191.69  4942.1  193.28  4973.2  193.11  4984.9  195.77
  4994.6  196.17  5011.6  194.53  5015.3  192.76  5029.4  194.02    5093  194.87
  5128.6  196.69  5305.4  196.52  5326.4   197.6  5350.3   196.8  5365.7  197.16
  5504.2  197.75  5715.7  199.35  5848.6  203.45  5998.7  208.05  6104.8  212.53
#Mann= 9 ,-1 , 0
  4716.7     .12       0  4726.3      .1       0  4894.7     .05       0
    4904      .1       0  5350.3     .12       0  5365.7    .035       0
  5504.2      .1       0  5848.6     .12       0  5998.7    .035       0
Bank Sta=4894.7,4904
XS Rating Curve= 0 ,0
Exp/Cntr=0.3,0.1

Type RM Length L Ch R = 1 ,5125    ,492,492,492
BEGIN DESCRIPTION:
TRIB TO TRIB 4 TO EIGHTEENMILE CREEK 9.0
END DESCRIPTION:
XS GIS Cut Line= 3
      2490075.02     13491374.98        2490275.       13491125.
        2491075.       13490325.
#Sta/Elev= 30
  4694.1  208.95  4922.2  202.39  4928.6  198.34  4936.1  196.59  4963.8  192.09
  4971.8  191.76  4978.2  193.25  4986.2  192.23  4992.6  192.69    4996  191.59
  4996.5  191.09  5005.3  191.59    5011  192.87  5056.7  194.74  5169.8  195.99
  5198.1  195.31    5230  195.72  5240.5  195.24  5254.6  196.12  5282.9  195.54
  5373.1  196.44  5692.7  196.97  5749.6  197.92  5820.3   200.4  5848.6  202.42
  5933.5  206.17  6004.2  207.59  6032.5  209.49  6051.4  209.13  6145.6  212.59
#Mann= 8 ,-1 , 0
  4694.1     .12       0  4936.1      .1       0    4996     .05       0
  5005.3      .1       0    5230    .035       0  5373.1      .1       0
  5692.7     .12       0  6051.4    .035       0
Bank Sta=4996,5005.3
XS Rating Curve= 0 ,0
Exp/Cntr=0.3,0.1

Type RM Length L Ch R = 1 ,4633    ,430,430,430
BEGIN DESCRIPTION:
TRIB TO TRIB 4 TO EIGHTEENMILE CREEK 8.0
END DESCRIPTION:
XS GIS Cut Line= 3
      2490324.99     13491625.01        2490725.       13491225.
      2491525.03     13490424.97
#Sta/Elev= 30
  4433.8  207.19  4626.9  201.21  4699.3  198.55  4716.7  197.52  4744.9  197.47
  4759.1  196.13  4842.3  194.16  4886.4  193.93  4900.5  194.53  4942.9  193.61
  4991.3  191.12  4991.8  190.62  5000.7  191.12  5027.8  195.34  5041.9  195.77
  5183.3  193.74  5296.5  195.38  5338.9  194.64  5381.3  195.95  5395.5  196.76
  5409.6  198.59  5423.6  198.97    5452  197.54  5494.5  200.09  5557.7  202.41
  5635.9  203.98  5819.7  209.99  5904.6  212.03  6031.9  216.99  6130.9  219.88
#Mann= 8 ,-1 , 0
  4433.8     .05       0  4626.9     .12       0  4699.3     .05       0
  4842.3      .1       0  4991.3     .05       0  5000.7      .1       0
  5423.6    .035       0  5557.7     .12       0
Bank Sta=4991.3,5000.7
XS Rating Curve= 0 ,0
Exp/Cntr=0.3,0.1