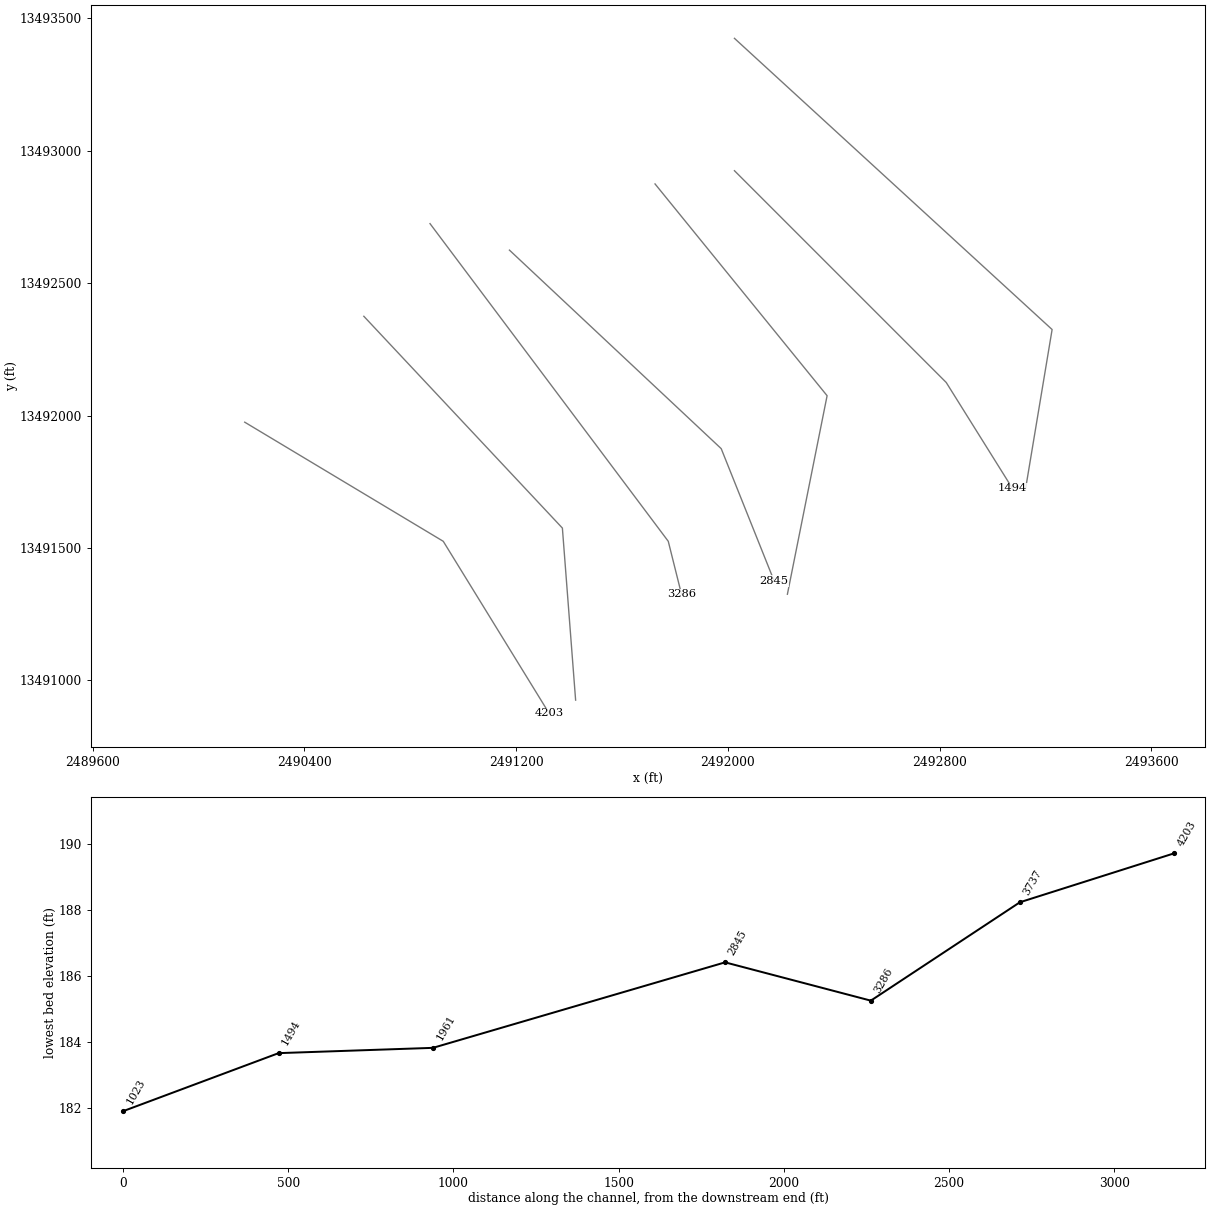
HEC-RAS study TRIB 4_1 TO EIGHTEENMILE CREEK.prj: TRIB 4_1 TO EIGHTEENMILE CREEK Base Level Engineering

--- TRIB 4_1 TO EIGHTEENMILE CREEK.g01 (geometry) --- (continued)

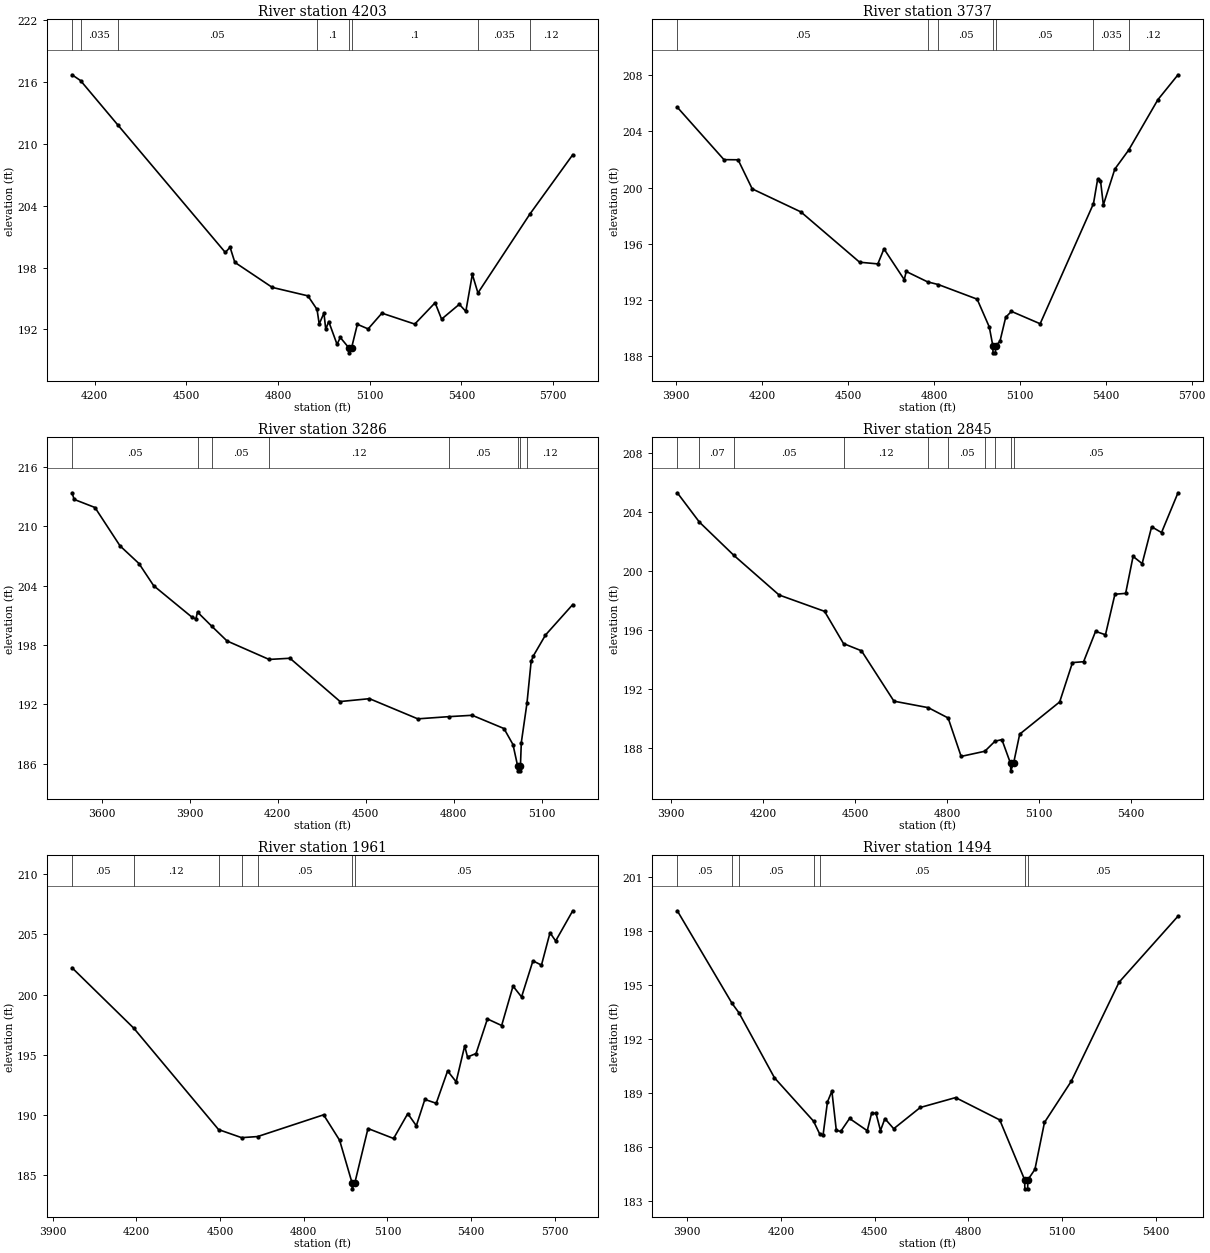
Type RM Length L Ch R = 1 ,4203    ,466,466,466
BEGIN DESCRIPTION:
TRIB TO TRIB 4 TO EIGHTEENMILE CREEK 7.0
END DESCRIPTION:
XS GIS Cut Line= 3
      2490174.99     13491975.01        2490925.       13491525.
      2491325.01     13490874.98
#Sta/Elev= 30
  4126.2   216.7    4154  216.14  4275.5  211.85  4627.7  199.46  4643.2  199.97
  4658.8   198.5  4781.2  196.07  4897.8  195.25  4927.7  193.93  4934.8  192.52
  4950.3  193.58  4956.2     192  4965.9  192.76  4993.1  190.55  5003.8  191.21
  5031.4  190.22  5031.9  189.72  5040.8  190.22  5059.6  192.49  5094.8  192.04
  5139.9  193.57  5247.4  192.51  5313.9  194.58  5335.1  192.99  5393.1  194.43
  5414.4  193.74  5435.7  197.33  5454.1  195.53  5623.6  203.17  5764.1  208.94
#Mann= 8 ,-1 , 0
  4126.2     .05       0    4154    .035       0  4275.5     .05       0
  4927.7      .1       0  5031.4     .05       0  5040.8      .1       0
  5454.1    .035       0  5623.6     .12       0
Bank Sta=5031.4,5040.8
XS Rating Curve= 0 ,0
Exp/Cntr=0.3,0.1

Type RM Length L Ch R = 1 ,3737    ,451,451,451
BEGIN DESCRIPTION:
TRIB TO TRIB 4 TO EIGHTEENMILE CREEK 6.0
END DESCRIPTION:
XS GIS Cut Line= 3
      2490624.97     13492375.03        2491375.       13491575.
        2491425.     13490925.05
#Sta/Elev= 30
  3903.9  205.72  4066.8  201.99  4116.2  201.98  4165.5  199.91  4335.5  198.27
  4540.6  194.69  4604.2  194.57  4625.6  195.64  4696.5  193.45  4703.3  194.03
    4778  193.29  4815.4   193.1    4951  192.06  4993.4  190.08  5005.8  188.74
  5006.3  188.24  5014.8  188.24  5015.3  188.74  5030.6  189.06  5050.7  190.77
  5070.7  191.19    5171  190.31  5357.2  198.86  5371.6  200.58  5381.7   200.5
  5391.7  198.77  5431.8  201.32  5480.1  202.67  5582.2  206.26  5652.4  208.03
#Mann= 7 ,-1 , 0
  3903.9     .05       0    4778     .12       0  4815.4     .05       0
  5005.8     .05       0  5015.3     .05       0  5357.2    .035       0
  5480.1     .12       0
Bank Sta=5005.8,5015.3
XS Rating Curve= 0 ,0
Exp/Cntr=0.3,0.1

Type RM Length L Ch R = 1 ,3286    ,441,441,441
BEGIN DESCRIPTION:
TRIB TO TRIB 4 TO EIGHTEENMILE CREEK 5.0
END DESCRIPTION:
XS GIS Cut Line= 3
      2490874.98     13492725.02        2491775.       13491525.
        2491825.     13491324.99
#Sta/Elev= 30
  3499.4  213.39  3506.7  212.72  3577.6   211.9    3663  208.02  3727.6  206.23
  3777.6  203.99  3906.7  200.84  3921.3  200.61    3927  201.32  3975.6  199.89
  4027.6   198.4  4170.9  196.53  4242.1  196.65    4413  192.27    4513  192.56
  4677.6  190.52  4782.5  190.74    4863  190.88  4971.3  189.54    5002  187.92
  5017.8  185.76  5018.3  185.26  5026.9  185.26  5027.4  185.76  5030.4  188.12
  5049.7  192.11  5063.9  196.34  5071.6   196.9  5112.8     199  5205.6  202.08
#Mann= 8 ,-1 , 0
  3499.4     .05       0    3927     .07       0  3975.6     .05       0
  4170.9     .12       0  4782.5     .05       0  5017.8     .05       0
  5027.4     .05       0  5049.7     .12       0
Bank Sta=5017.8,5027.4
XS Rating Curve= 0 ,0
Exp/Cntr=0.3,0.1

Type RM Length L Ch R = 1 ,2845    ,884,884,884
BEGIN DESCRIPTION:
TRIB TO TRIB 4 TO EIGHTEENMILE CREEK 4.0
END DESCRIPTION:
XS GIS Cut Line= 3
      2491174.99     13492625.01        2491975.       13491875.
      2492174.99     13491375.01
#Sta/Elev= 30
  3919.4   205.3  3991.5  203.31  4104.2  201.05  4251.8  198.36  4400.3  197.25
  4462.2  195.06  4520.9  194.57  4626.9  191.15    4739  190.71  4803.8  190.01
  4846.3   187.4  4923.7  187.75  4956.8  188.43  4979.4  188.54  5007.7  186.92
  5008.2  186.42  5017.4  186.92  5037.5  188.91  5168.1   191.1  5209.9  193.77
  5246.2  193.83  5285.3  195.89  5317.6  195.66  5348.5  198.41  5383.5  198.47
  5407.8  200.98  5437.4  200.49  5468.4  202.99  5500.7   202.6  5554.5   205.3
#Mann= 10 ,-1 , 0
  3919.4     .05       0  3991.5     .07       0  4104.2     .05       0
  4462.2     .12       0    4739    .035       0  4803.8     .05       0
  4923.7    .035       0  4956.8     .05       0  5007.7     .05       0
  5017.4     .05       0
Bank Sta=5007.7,5017.4
XS Rating Curve= 0 ,0
Exp/Cntr=0.3,0.1

Type RM Length L Ch R = 1 ,1961    ,467,467,467
BEGIN DESCRIPTION:
TRIB TO TRIB 4 TO EIGHTEENMILE CREEK 3.0
END DESCRIPTION:
XS GIS Cut Line= 3
        2491725.     13492875.01        2492375.       13492075.
      2492225.01     13491325.04
#Sta/Elev= 30
  3968.9  202.23  4190.4   197.2  4494.5  188.76    4577  188.09  4634.4  188.18
  4871.1  189.99  4928.6  187.87  4973.1  184.33  4973.6  183.83  4983.1  184.33
  5030.3  188.85  5122.1  188.02    5173  190.09  5203.6  189.08  5234.2  191.27
    5275  190.95  5315.8  193.64  5346.4  192.74    5377  195.72  5387.2   194.8
  5417.8  195.09  5458.6  197.97  5509.6  197.42  5550.4   200.7    5581   199.8
  5621.8   202.8  5652.4  202.45    5683  205.14  5703.3  204.46  5764.5  206.97
#Mann= 7 ,-1 , 0
  3968.9     .05       0  4190.4     .12       0  4494.5     .05       0
    4577     .12       0  4634.4     .05       0  4973.1     .05       0
  4983.1     .05       0
Bank Sta=4973.1,4983.1
XS Rating Curve= 0 ,0
Exp/Cntr=0.3,0.1

Type RM Length L Ch R = 1 ,1494    ,471,471,471
BEGIN DESCRIPTION:
TRIB TO TRIB 4 TO EIGHTEENMILE CREEK 2.0
END DESCRIPTION:
XS GIS Cut Line= 3
      2492025.03     13492924.97        2492825.       13492125.
      2493074.99     13491725.02
#Sta/Elev= 30
  3868.2  199.12  4043.7  193.97  4065.7  193.45  4179.3  189.84  4304.4  187.43
  4324.3  186.71  4334.8  186.65    4349   188.5  4363.1   189.1  4377.3  186.92
  4391.4  186.86  4419.7  187.58  4476.3   186.9  4490.4  187.88  4504.5  187.86
  4518.7  186.91  4532.8  187.57  4561.1  187.01    4646  188.19  4759.1  188.74
  4900.5   187.5  4980.3  184.17  4980.8  183.67  4989.9  183.67  4990.4  184.17
  5013.1  184.75  5043.7  187.36  5129.2  189.64  5282.5  195.15  5471.2  198.82
#Mann= 7 ,-1 , 0
  3868.2     .05       0  4043.7     .12       0  4065.7     .05       0
  4304.4    .035       0  4324.3     .05       0  4980.3     .05       0
  4990.4     .05       0
Bank Sta=4980.3,4990.4
XS Rating Curve= 0 ,0
Exp/Cntr=0.3,0.1

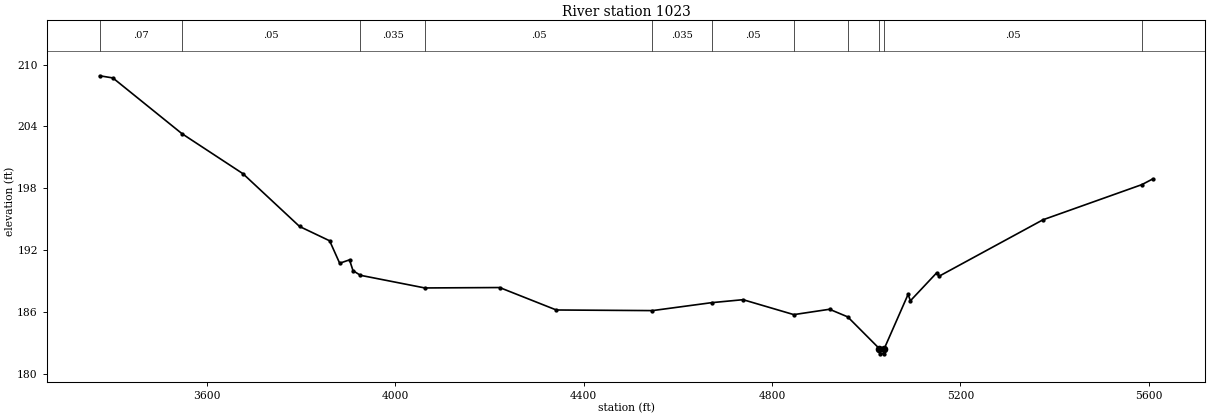
Type RM Length L Ch R = 1 ,1023    ,0,0,0
BEGIN DESCRIPTION:
TRIB TO TRIB 4 TO EIGHTEENMILE CREEK 1.0
END DESCRIPTION:
XS GIS Cut Line= 3
      2492024.98     13493425.02        2493225.       13492325.
        2493125.     13491724.99
#Sta/Elev= 30
  3372.3  208.92  3400.4  208.71    3547   203.3  3676.6  199.41  3796.9  194.28
  3860.7  192.89    3882  190.71  3902.9  191.04  3910.3  189.99    3926  189.54
  4062.9  188.31  4221.7  188.35    4342  186.17  4546.2  186.11  4671.6  186.88
  4738.5  187.17  4846.3  185.72  4922.2  186.24  4960.8   185.5  5028.1  182.41
  5028.6  181.91  5037.8  181.91  5038.3  182.41  5088.9  187.68    5094  187.07
  5149.7  189.78  5154.8  189.45  5375.3  194.93  5585.5  198.35  5608.5   198.9
#Mann= 11 ,-1 , 0
  3372.3     .07       0    3547     .05       0    3926    .035       0
  4062.9     .05       0  4546.2    .035       0  4671.6     .05       0
  4846.3    .035       0  4960.8     .05       0  5028.1     .05       0
  5038.3     .05       0  5585.5     .07       0
Bank Sta=5028.1,5038.3
XS Rating Curve= 0 ,0
Exp/Cntr=0.3,0.1

Chan Stop Cuts=-1
Use User Specified Reach Order=0
Composite Channel Slope=5