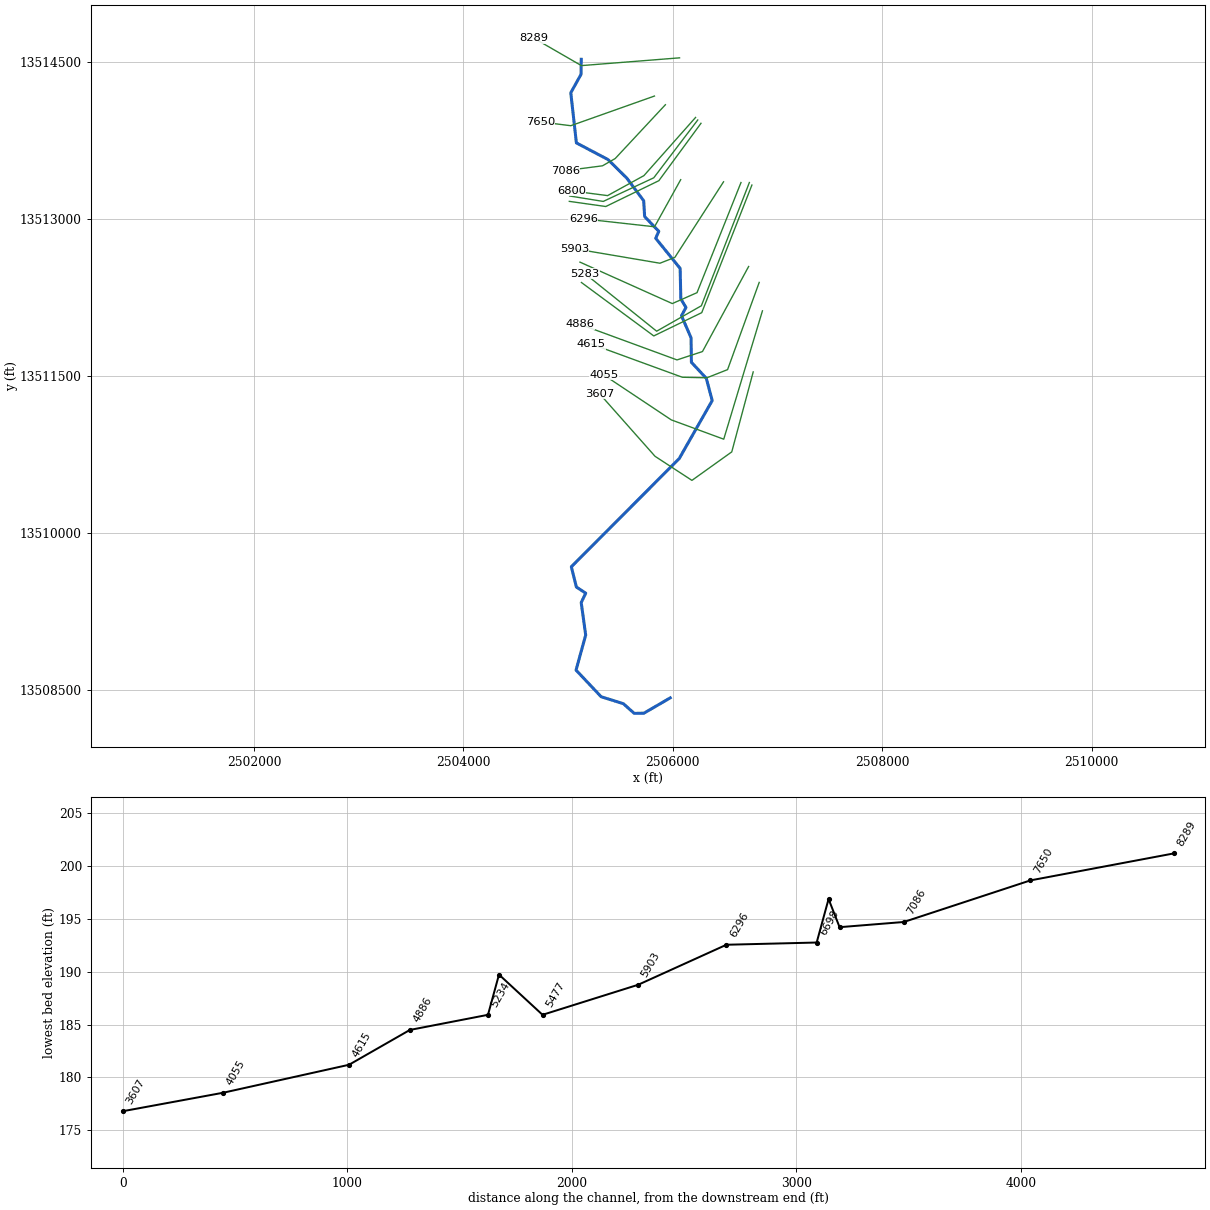
--- TRIB 4_1 TO FIFTEENMILE CREEK.prj (project) ---

Proj Title=TRIB 4_1 TO FIFTEENMILE CREEK Base Level Engineering
Current Plan=p01
Default Exp/Contr=0.3,0.1
English Units
Geom File=g01
Flow File=f01
Plan File=p01
BEGIN DESCRIPTION:
TRIB 4_1 TO FIFTEENMILE CREEK
END DESCRIPTION:

--- TRIB 4_1 TO FIFTEENMILE CREEK.p01 (plan) ---

Plan Title=Multiple Run
Short Identifier=Multiple
Geom File=g01
Flow File=f01
Subcritical Flow
K Sum by GR= 0
Std Step Tol= 0.01
Critical Tol= 0.01
Num of Std Step Trials= 20
Max Error Tol= 0.3
Flow Tol Ratio= 0.001
Split Flow NTrial= 30
Split Flow Tol= 0.02
Split Flow Ratio= 0.02
Log Output Level= 0
Friction Slope Method= 1
Unsteady Friction Slope Method= 2
Unsteady Bridges Friction Slope Method= 1
Parabolic Critical Depth
Global Vel Dist=  1 , 1 , 1
Global Log Level= 0
CheckData=True
Encroach Param= -1, 0, 0, 0
BEGIN DESCRIPTION:
Multiple Run
END DESCRIPTION:

--- TRIB 4_1 TO FIFTEENMILE CREEK.f01 (steady flow) ---

Flow Title=Multiple
Number of Profiles=7
Profile Names=10-year,25-year,50-year,1pct_min,100-year,1pct_plu,500-year
River Rch & RM= TRIB 4_1 TO FIFT,Reach-1,8289
     423     659     865     551    1099    2192    1750
River Rch & RM= TRIB 4_1 TO FIFT,Reach-1,3607
     494     776    1024     654    1306    2605    2097
Boundary for River Rch & Prof#=TRIB 4_1 TO FIFT,Reach-1,1
Up Type=0
Dn Type=3
Dn Slope=0.005
Boundary for River Rch & Prof#=TRIB 4_1 TO FIFT,Reach-1,2
Up Type=0
Dn Type=3
Dn Slope=0.005
Boundary for River Rch & Prof#=TRIB 4_1 TO FIFT,Reach-1,3
Up Type=0
Dn Type=3
Dn Slope=0.005
Boundary for River Rch & Prof#=TRIB 4_1 TO FIFT,Reach-1,4
Up Type=0
Dn Type=3
Dn Slope=0.005
Boundary for River Rch & Prof#=TRIB 4_1 TO FIFT,Reach-1,5
Up Type=0
Dn Type=3
Dn Slope=0.005
Boundary for River Rch & Prof#=TRIB 4_1 TO FIFT,Reach-1,6
Up Type=0
Dn Type=3
Dn Slope=0.005
Boundary for River Rch & Prof#=TRIB 4_1 TO FIFT,Reach-1,7
Up Type=0
Dn Type=3
Dn Slope=0.005

--- TRIB 4_1 TO FIFTEENMILE CREEK.g01 (geometry) ---

Geom Title=Existing Conditions

River Reach=TRIB 4_1 TO FIFT,Reach-1
Reach XY= 30
      2505125.00     13514525.00      2505122.80     13514380.91
      2505025.04     13514204.97      2505078.52     13513726.28
      2505381.06     13513566.86      2505561.37     13513388.21
      2505721.46     13513173.53      2505730.47     13513022.55
      2505865.70     13512881.67      2505836.24     13512815.00
      2506069.53     13512527.45      2506076.24     13512235.50
      2506125.21     13512154.79      2506082.59     13512075.01
      2506173.78     13511864.50      2506177.06     13511630.85
      2506319.48     13511477.43      2506375.82     13511264.93
      2506061.38     13510711.79      2505030.40     13509677.43
      2505078.56     13509483.48      2505167.74     13509425.30
      2505124.60     13509335.21      2505167.44     13509025.00
      2505075.24     13508690.22      2505315.32     13508435.76
      2505527.42     13508369.46      2505630.89     13508276.97
      2505723.41     13508278.67      2505975.00     13508425.00

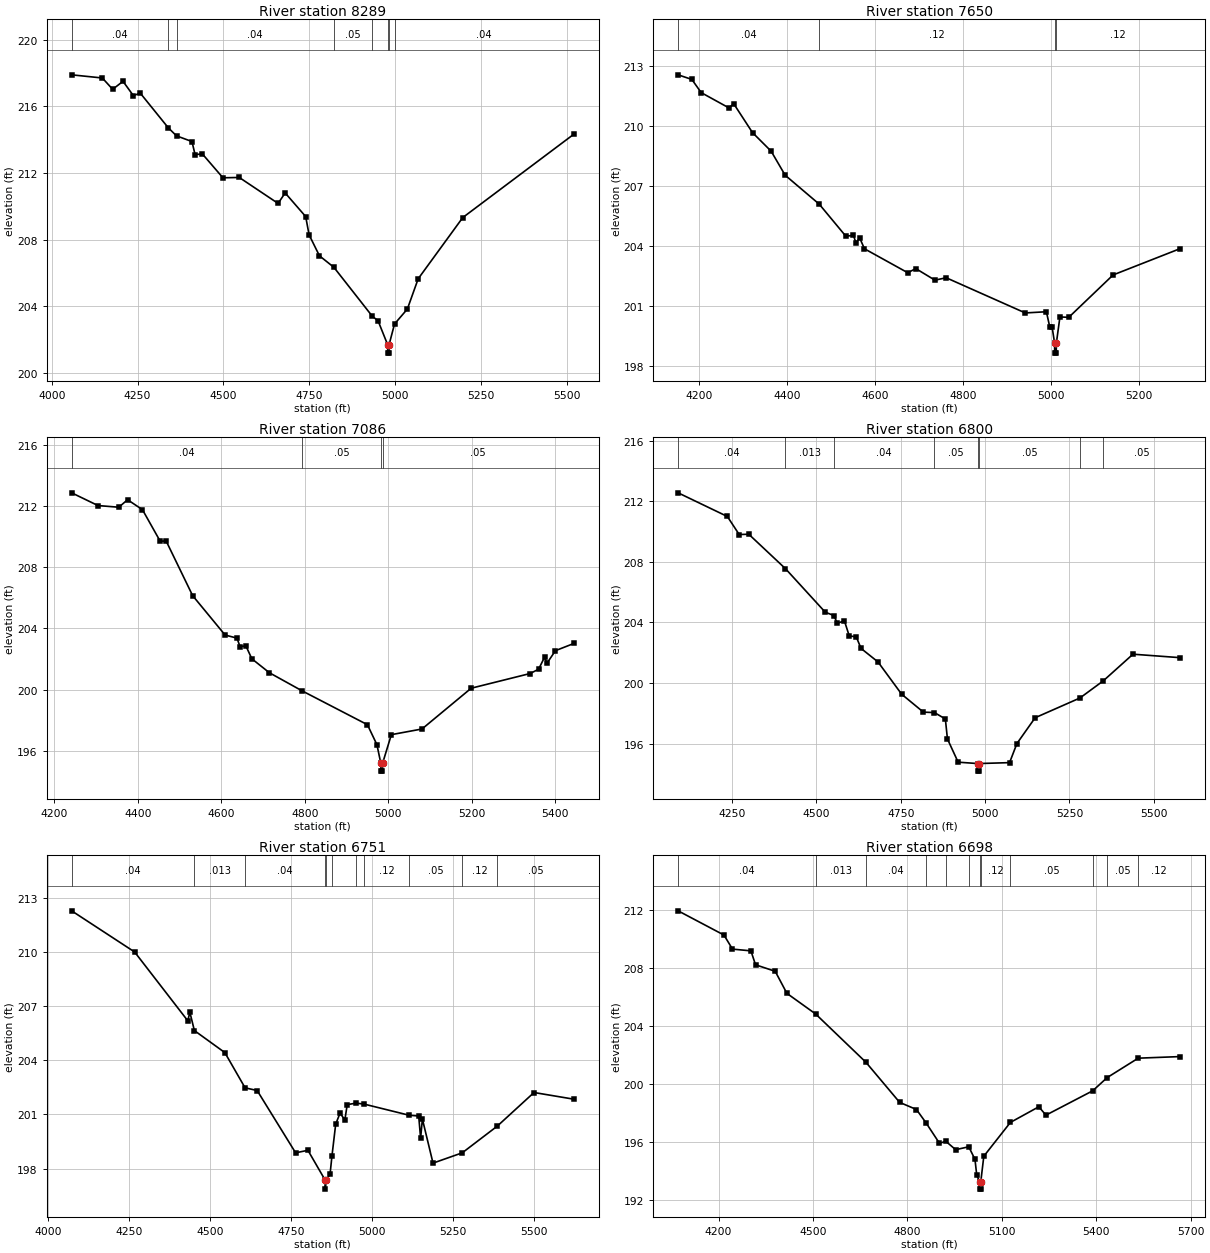
Type RM Length L Ch R = 1,8289,639,639,639
BEGIN DESCRIPTION:
TRIB 4_1 TO FIFTEENMILE CREEK 6.0
END DESCRIPTION:
XS GIS Cut Line= 3
      2506064.07     13514538.67      2505126.31     13514464.47
      2504675.00     13514725.00
#Sta/Elev= 30
  4058.0  217.90  4147.3  217.71  4177.4  217.03  4207.5  217.51  4237.6  216.65
  4257.7  216.80  4339.1  214.72  4363.3  214.23  4408.2  213.89  4417.3  213.10
  4438.3  213.15  4498.4  211.71  4545.9  211.73  4658.9  210.17  4679.5  210.80
  4739.2  209.38  4749.2  208.28  4779.3  207.02  4821.3  206.33  4933.4  203.38
  4949.8  203.12  4977.9  201.67  4978.2  201.17  4981.7  201.17  4981.9  201.67
  4997.8  202.92  5035.2  203.82  5066.7  205.64  5196.5  209.32  5519.8  214.33
#Mann=8,-1,0
  4058.0    0.04       0  4339.1   0.013       0  4363.3    0.04       0
  4821.3    0.05       0  4933.4    0.12       0  4977.9    0.04       0
  4981.9    0.12       0  4997.8    0.04       0
Bank Sta=4977.9,4981.9
Exp/Cntr=0.3,0.1

Type RM Length L Ch R = 1,7650,564,564,564
BEGIN DESCRIPTION:
TRIB 4_1 TO FIFTEENMILE CREEK 4.0
END DESCRIPTION:
XS GIS Cut Line= 3
      2505824.44     13514173.81      2505025.10     13513890.40
      2504733.27     13513926.87
#Sta/Elev= 30
  4151.9  212.54  4183.1  212.31  4204.4  211.65  4268.0  210.88  4278.2  211.10
  4321.1  209.65  4363.5  208.72  4395.3  207.52  4472.9  206.07  4533.3  204.47
  4550.7  204.51  4556.1  204.15  4565.1  204.37  4575.7  203.84  4674.3  202.64
  4692.4  202.85  4736.0  202.27  4761.6  202.39  4941.5  200.63  4989.5  200.69
  4997.4  199.91  5002.6  199.91  5008.2  199.12  5008.4  198.62  5011.9  198.62
  5012.2  199.12  5020.3  200.43  5040.4  200.41  5141.2  202.53  5294.1  203.85
#Mann=4,-1,0
  4151.9    0.04       0  4472.9    0.12       0  5008.2    0.05       0
  5012.2    0.12       0
Bank Sta=5008.2,5012.2
Exp/Cntr=0.3,0.1

Type RM Length L Ch R = 1,7086,286,286,286
BEGIN DESCRIPTION:
Mapping XS fab61aa3
END DESCRIPTION:
XS GIS Cut Line= 4
      2505928.66     13514090.73      2505449.53     13513576.87
      2505328.00     13513507.42      2504971.29     13513460.77
#Sta/Elev= 30
  4241.8  212.85  4304.8  212.02  4354.7  211.91  4375.7  212.40  4411.3  211.75
  4453.8  209.69  4468.0  209.71  4531.5  206.14  4609.2  203.57  4637.5  203.37
  4644.9  202.82  4659.0  202.86  4673.2  202.02  4715.2  201.11  4793.4  199.93
  4949.9  197.72  4972.6  196.42  4982.1  195.19  4982.4  194.69  4985.9  194.69
  4986.1  195.19  5007.2  197.07  5080.6  197.44  5198.3  200.10  5339.5  201.06
  5359.7  201.34  5373.9  202.12  5379.8  201.73  5400.0  202.55  5444.1  203.02
#Mann=4,-1,0
  4241.8    0.04       0  4793.4    0.05       0  4982.1    0.05       0
  4986.1    0.05       0
Bank Sta=4982.1,4986.1
Exp/Cntr=0.3,0.1

Type RM Length L Ch R = 1,6800,49,49,49
BEGIN DESCRIPTION:
Mapping XS 2e7e262e
END DESCRIPTION:
XS GIS Cut Line= 4
      2506216.86     13513969.20      2505723.83     13513413.67
      2505376.61     13513222.70      2505029.69     13513268.03
#Sta/Elev= 30
  4089.8  212.55  4235.8  210.99  4270.9  209.80  4299.3  209.82  4408.0  207.55
  4526.0  204.68  4551.5  204.46  4561.9  203.95  4582.8  204.11  4597.1  203.12
  4618.0  203.05  4632.2  202.29  4682.4  201.40  4752.6  199.27  4817.0  198.09
  4849.8  198.06  4882.1  197.64  4888.3  196.32  4920.0  194.79  4977.6  194.70
  4977.8  194.20  4981.3  194.20  4981.6  194.70  5072.5  194.76  5094.3  196.02
  5148.3  197.72  5281.0  199.02  5350.2  200.15  5438.4  201.91  5578.7  201.68
#Mann=8,-1,0
  4089.8    0.04       0  4408.0   0.013       0  4551.5    0.04       0
  4849.8    0.05       0  4977.6    0.05       0  4981.6    0.05       0
  5281.0    0.12       0  5350.2    0.05       0
Bank Sta=4977.6,4981.6
Exp/Cntr=0.3,0.1

Type RM Length L Ch R = 1,6751,53,53,53
BEGIN DESCRIPTION:
Mapping XS d9487bdd
END DESCRIPTION:
XS GIS Cut Line= 4
      2506237.74     13513944.96      2505817.58     13513392.84
      2505334.94     13513167.15      2505014.52     13513219.01
#Sta/Elev= 30
  4072.3  212.27  4266.9  209.99  4431.1  206.18  4437.4  206.66  4451.4  205.64
  4545.5  204.42  4608.0  202.47  4645.3  202.32  4764.1  198.87  4802.1  199.01
  4855.3  197.36  4855.5  196.86  4859.3  197.36  4870.5  197.69  4876.2  198.67
  4887.9  200.46  4901.4  201.07  4916.2  200.69  4923.5  201.54  4950.8  201.62
  4975.2  201.57  5115.0  200.95  5144.3  200.91  5150.2  199.68  5155.7  200.74
  5188.5  198.30  5278.8  198.87  5387.1  200.35  5500.5  202.21  5623.5  201.84
#Mann=11,-1,0
  4072.3    0.04       0  4451.4   0.013       0  4608.0    0.04       0
  4855.3    0.05       0  4859.3    0.04       0  4876.2    0.05       0
  4950.8    0.04       0  4975.2    0.12       0  5115.0    0.05       0
  5278.8    0.12       0  5387.1    0.05       0
Bank Sta=4855.3,4859.3
Exp/Cntr=0.3,0.1

Type RM Length L Ch R = 1,6698,402,402,402
BEGIN DESCRIPTION:
Mapping XS f6cce0af
END DESCRIPTION:
XS GIS Cut Line= 4
      2506268.98     13513913.69      2505866.19     13513365.06
      2505359.25     13513118.54      2505010.92     13513167.73
#Sta/Elev= 30
  4071.5  211.94  4217.2  210.27  4244.3  209.30  4302.9  209.18  4317.5  208.22
  4380.1  207.77  4417.2  206.25  4508.4  204.83  4668.3  201.50  4775.7  198.73
  4829.0  198.24  4859.8  197.31  4902.2  195.91  4922.3  196.05  4953.6  195.47
  4995.3  195.67  5015.0  194.80  5020.5  193.74  5029.4  193.25  5029.7  192.75
  5033.2  192.75  5033.4  193.25  5043.1  195.02  5127.6  197.35  5218.0  198.43
  5240.5  197.85  5389.2  199.53  5435.1  200.44  5533.8  201.78  5667.6  201.89
#Mann=12,-1,0
  4071.5    0.04       0  4508.4   0.013       0  4668.3    0.04       0
  4859.8    0.12       0  4922.3    0.04       0  4995.3    0.12       0
  5029.4    0.05       0  5033.4    0.12       0  5127.6    0.05       0
  5389.2    0.12       0  5435.1    0.05       0  5533.8    0.12       0
Bank Sta=5029.4,5033.4
Exp/Cntr=0.3,0.1

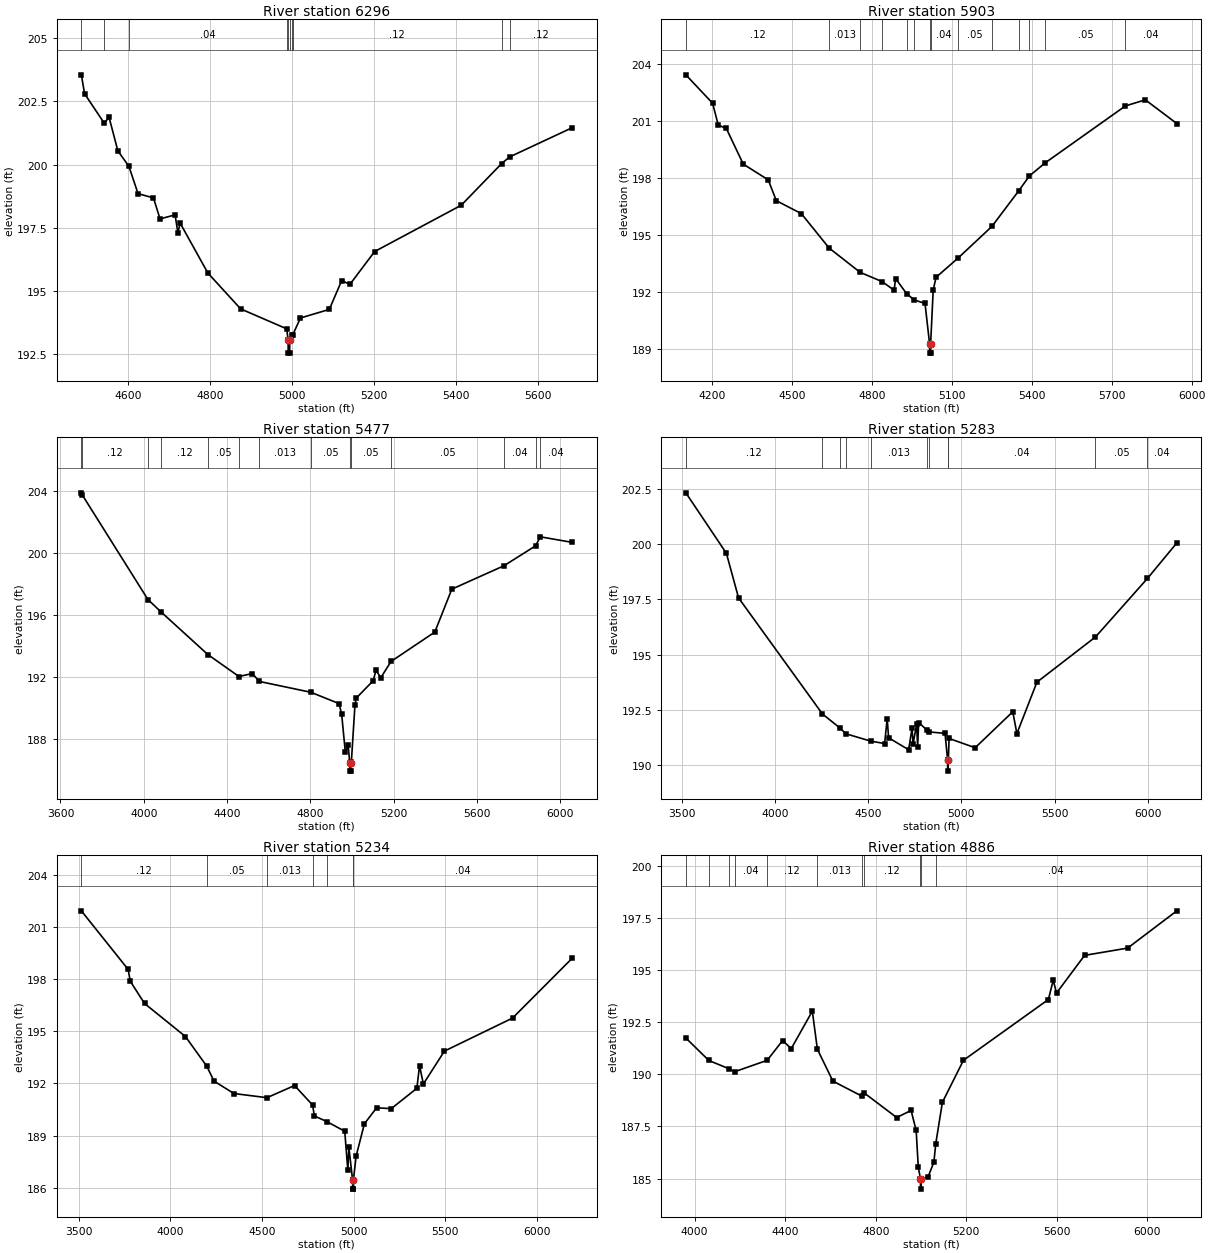
Type RM Length L Ch R = 1,6296,393,393,393
BEGIN DESCRIPTION:
TRIB 4_1 TO FIFTEENMILE CREEK 2.0
END DESCRIPTION:
XS GIS Cut Line= 3
      2506074.98     13513374.97      2505825.00     13512925.00
      2505145.42     13513000.51
#Sta/Elev= 30
  4485.6  203.55  4493.6  202.80  4541.8  201.63  4553.1  201.88  4574.8  200.54
  4601.7  199.93  4624.0  198.85  4661.7  198.68  4677.7  197.85  4714.4  198.01
  4721.2  197.31  4726.9  197.68  4794.4  195.71  4874.5  194.29  4987.1  193.50
  4990.3  193.04  4990.6  192.54  4994.1  192.54  4994.3  193.04  5000.1  193.27
  5001.8  193.27  5020.5  193.93  5090.9  194.27  5121.1  195.41  5141.2  195.26
  5201.6  196.56  5412.9  198.39  5511.6  200.04  5530.8  200.30  5684.1  201.46
#Mann=10,-1,0
  4485.6    0.04       0  4541.8   0.013       0  4601.7    0.04       0
  4987.1    0.12       0  4990.3    0.05       0  4994.3    0.12       0
  5000.1    0.04       0  5001.8    0.12       0  5511.6    0.05       0
  5530.8    0.12       0
Bank Sta=4990.3,4994.3
Exp/Cntr=0.3,0.1

Type RM Length L Ch R = 1,5903,426,426,426
BEGIN DESCRIPTION:
Mapping XS 34bdbcc5
END DESCRIPTION:
XS GIS Cut Line= 4
      2506484.23     13513354.62      2506018.97     13512632.42
      2505876.61     13512576.87      2505058.58     13512715.52
#Sta/Elev= 30
  4102.8  203.44  4203.2  201.94  4224.3  200.79  4254.7  200.61  4318.1  198.73
  4411.8  197.90  4442.2  196.80  4535.9  196.12  4640.4  194.30  4756.7  193.02
  4839.4  192.53  4883.8  192.08  4889.8  192.69  4930.6  191.90  4958.9  191.57
  4999.9  191.38  5017.0  189.26  5017.3  188.76  5020.8  188.76  5021.0  189.26
  5030.6  192.09  5041.3  192.76  5123.5  193.77  5250.6  195.44  5350.8  197.31
  5391.7  198.11  5451.0  198.80  5751.6  201.80  5826.3  202.12  5944.4  200.87
#Mann=14,-1,0
  4102.8    0.12       0  4640.4   0.013       0  4756.7    0.05       0
  4839.4    0.04       0  4930.6    0.05       0  4958.9    0.04       0
  5017.0    0.04       0  5021.0    0.04       0  5123.5    0.05       0
  5250.6    0.12       0  5350.8    0.05       0  5391.7    0.12       0
  5451.0    0.05       0  5751.6    0.04       0
Bank Sta=5017,5021
Exp/Cntr=0.3,0.1

Type RM Length L Ch R = 1,5477,194,194,194
BEGIN DESCRIPTION:
Mapping XS 84844d16
END DESCRIPTION:
XS GIS Cut Line= 4
      2506650.90     13513347.67      2506230.78     13512295.62
      2505994.67     13512191.45      2505112.72     13512587.29
#Sta/Elev= 30
  3700.4  203.89  3705.1  203.75  4020.2  197.00  4083.9  196.19  4307.7  193.45
  4457.2  192.03  4521.6  192.22  4555.3  191.71  4802.9  191.01  4937.9  190.28
  4950.3  189.61  4968.1  187.14  4981.6  187.58  4989.5  186.42  4989.7  185.92
  4993.2  185.92  4993.5  186.42  4996.9  186.49  5014.4  190.22  5020.2  190.63
  5101.9  191.76  5115.3  192.43  5138.4  191.95  5187.3  193.00  5397.8  194.90
  5479.3  197.67  5729.7  199.18  5882.0  200.47  5904.0  201.05  6058.0  200.69
#Mann=14,-1,0
  3700.4    0.04       0  3705.1    0.12       0  4020.2   0.013       0
  4083.9    0.12       0  4307.7    0.05       0  4457.2    0.12       0
  4555.3   0.013       0  4802.9    0.05       0  4989.5    0.04       0
  4993.5    0.05       0  5187.3    0.05       0  5729.7    0.04       0
  5882.0    0.05       0  5904.0    0.04       0
Bank Sta=4989.5,4993.5
Exp/Cntr=0.3,0.1

Type RM Length L Ch R = 1,5283,49,49,49
BEGIN DESCRIPTION:
Mapping XS d14b1056
END DESCRIPTION:
XS GIS Cut Line= 4
      2506730.76     13513347.66      2506272.44     13512170.62
      2505845.36     13511927.56      2505161.31     13512476.19
#Sta/Elev= 30
  3523.1  202.33  3740.4  199.59  3805.6  197.57  4255.1  192.31  4348.0  191.68
  4381.6  191.41  4513.7  191.08  4588.4  190.97  4602.2  192.09  4609.8  191.23
  4717.1  190.69  4735.5  191.67  4740.9  190.95  4760.0  191.84  4765.4  190.82
  4770.8  191.92  4815.8  191.58  4824.0  191.50  4912.2  191.43  4926.1  190.22
  4926.3  189.72  4930.1  190.22  4933.8  191.20  5073.6  190.78  5275.2  192.41
  5297.4  191.42  5404.6  193.75  5718.6  195.80  5997.0  198.45  6154.5  200.06
#Mann=11,-1,0
  3523.1    0.12       0  4255.1    0.05       0  4348.0    0.12       0
  4381.6    0.05       0  4513.7   0.013       0  4815.8    0.05       0
  4824.0    0.04       0  4926.1    0.04       0  4930.1    0.04       0
  5718.6    0.05       0  5997.0    0.04       0
Bank Sta=4926.1,4930.1
Exp/Cntr=0.3,0.1

Type RM Length L Ch R = 1,5234,348,348,348
BEGIN DESCRIPTION:
Mapping XS 8c6d1759
END DESCRIPTION:
XS GIS Cut Line= 4
      2506755.07     13513323.36      2506275.92     13512104.65
      2505817.58     13511882.42      2505126.64     13512392.82
#Sta/Elev= 30
  3515.4  201.93  3770.7  198.56  3782.3  197.88  3860.0  196.60  4083.1  194.70
  4199.5  192.99  4239.4  192.13  4347.8  191.42  4527.7  191.18  4678.3  191.88
  4776.5  190.76  4786.7  190.13  4855.3  189.80  4952.0  189.25  4969.0  187.01
  4974.5  188.33  4995.1  186.42  4995.4  185.92  4998.9  185.92  4999.1  186.42
  5014.1  187.82  5059.3  189.68  5126.0  190.60  5205.8  190.55  5345.4  191.72
  5360.0  193.02  5380.9  191.97  5495.7  193.86  5867.3  195.76  6193.3  199.21
#Mann=7,-1,0
  3515.4    0.12       0  4199.5    0.05       0  4527.7   0.013       0
  4776.5    0.05       0  4855.3    0.04       0  4995.1    0.04       0
  4999.1    0.04       0
Bank Sta=4995.1,4999.1
Exp/Cntr=0.3,0.1

Type RM Length L Ch R = 1,4886,271,271,271
BEGIN DESCRIPTION:
Mapping XS 8c9035bd
END DESCRIPTION:
XS GIS Cut Line= 4
      2506723.81     13512545.58      2506282.86     13511733.12
      2506039.80     13511653.26      2505112.73     13511993.53
#Sta/Elev= 30
  3961.8  191.75  4063.4  190.67  4150.7  190.28  4177.3  190.13  4321.1  190.68
  4389.1  191.63  4427.1  191.24  4520.3  193.04  4542.5  191.21  4611.0  189.68
  4738.5  188.96  4746.9  189.13  4892.7  187.93  4956.3  188.27  4978.7  187.31
  4988.1  185.54  4997.7  184.99  4998.0  184.49  5001.7  184.99  5031.3  185.08
  5057.0  185.79  5065.2  186.67  5094.5  188.66  5187.5  190.68  5562.6  193.60
  5583.9  194.53  5598.4  193.91  5722.4  195.72  5912.5  196.07  6129.6  197.86
#Mann=11,-1,0
  3961.8   0.013       0  4063.4    0.04       0  4150.7   0.013       0
  4177.3    0.04       0  4321.1    0.12       0  4542.5   0.013       0
  4738.5    0.05       0  4746.9    0.12       0  4997.7    0.05       0
  5001.7    0.12       0  5065.2    0.04       0
Bank Sta=4997.7,5001.7
Exp/Cntr=0.3,0.1

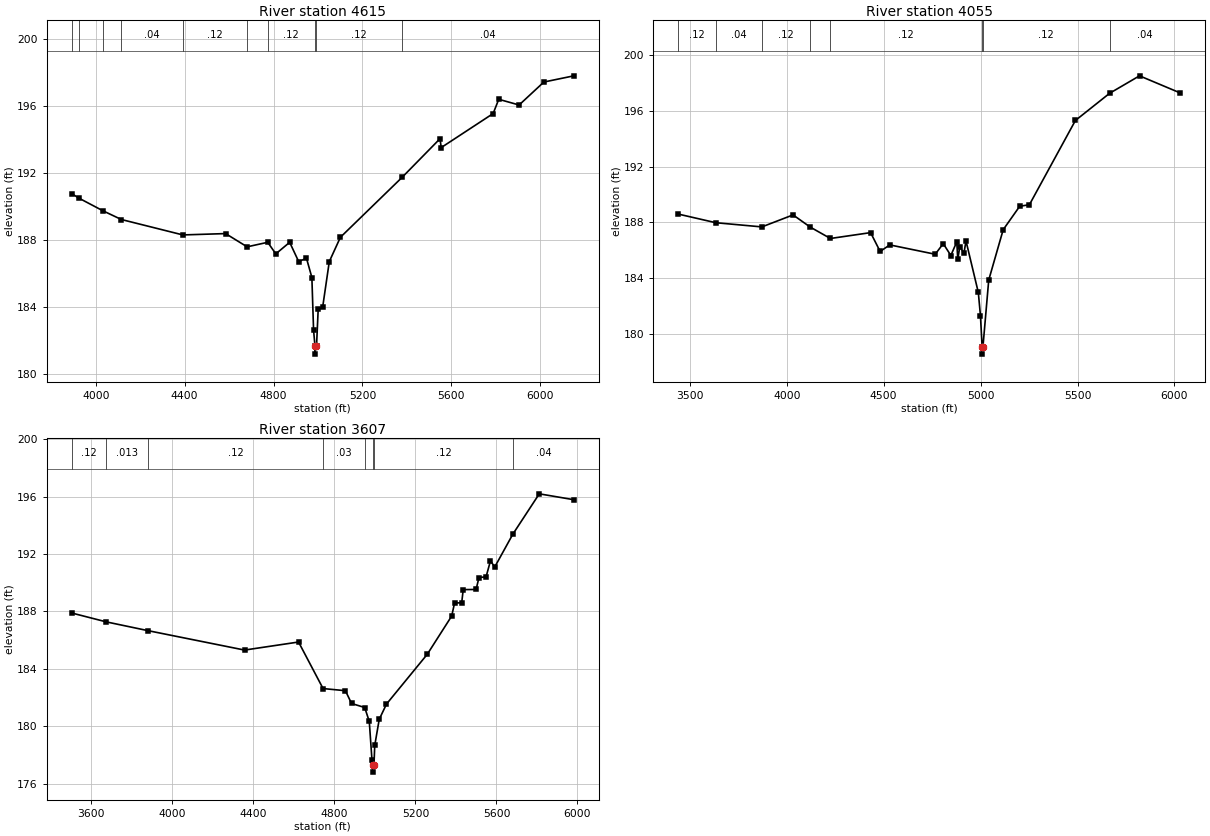
Type RM Length L Ch R = 1,4615,560,560,560
BEGIN DESCRIPTION:
Mapping XS 50873cbb
END DESCRIPTION:
XS GIS Cut Line= 5
      2506824.84     13512393.83      2506522.76     13511560.51
      2506324.85     13511482.39      2506090.47     13511487.60
      2505220.67     13511805.31
#Sta/Elev= 30
  3892.1  190.77  3926.3  190.49  4032.3  189.75  4115.3  189.23  4392.1  188.31
  4584.4  188.39  4681.2  187.60  4774.0  187.87  4810.4  187.18  4872.8  187.87
  4913.3  186.72  4948.4  186.92  4972.7  185.77  4980.3  182.64  4986.5  181.70
  4986.7  181.20  4990.5  181.70  4993.7  181.70  5001.1  183.87  5021.1  183.99
  5051.1  186.72  5101.1  188.17  5378.4  191.74  5549.4  194.05  5554.8  193.52
  5788.5  195.55  5813.7  196.40  5905.3  196.06  6016.8  197.43  6151.7  197.80
#Mann=10,-1,0
  3892.1    0.04       0  3926.3    0.05       0  4032.3    0.12       0
  4115.3    0.04       0  4392.1    0.12       0  4681.2   0.013       0
  4774.0    0.12       0  4986.5    0.05       0  4990.5    0.12       0
  5378.4    0.04       0
Bank Sta=4986.5,4990.5
Exp/Cntr=0.3,0.1

Type RM Length L Ch R = 1,4055,448,448,448
BEGIN DESCRIPTION:
Mapping XS 4269e45a
END DESCRIPTION:
XS GIS Cut Line= 4
      2506855.77     13512121.98      2506486.16     13510896.02
      2505984.86     13511080.48      2505339.88     13511509.93
#Sta/Elev= 30
  3440.6  188.60  3634.4  187.98  3872.0  187.68  4032.8  188.54  4121.0  187.67
  4225.5  186.85  4432.8  187.27  4481.9  185.92  4531.7  186.39  4765.9  185.72
  4807.5  186.48  4846.6  185.63  4877.1  186.61  4882.4  185.36  4892.8  186.26
  4914.1  185.80  4924.8  186.67  4988.3  182.98  4999.3  181.32  5008.0  179.06
  5008.3  178.56  5012.0  179.06  5042.0  183.87  5116.6  187.48  5201.8  189.16
  5251.8  189.27  5489.1  195.31  5665.7  197.26  5819.7  198.51  6030.1  197.28
#Mann=8,-1,0
  3440.6    0.12       0  3634.4    0.04       0  3872.0    0.12       0
  4121.0   0.013       0  4225.5    0.12       0  5008.0    0.05       0
  5012.0    0.12       0  5665.7    0.04       0
Bank Sta=5008,5012
Exp/Cntr=0.3,0.1

Type RM Length L Ch R = 1,3607,0,0,0
BEGIN DESCRIPTION:
Mapping XS 596f7f46
END DESCRIPTION:
XS GIS Cut Line= 5
      2506767.57     13511538.64      2506562.69     13510774.71
      2506182.35     13510502.63      2505830.06     13510732.39
      2505299.39     13511330.69
#Sta/Elev= 30
  3503.2  187.89  3674.5  187.27  3880.2  186.66  4356.3  185.31  4622.9  185.87
  4743.9  182.63  4854.3  182.48  4884.5  181.59  4949.5  181.31  4972.1  180.34
  4985.4  177.65  4991.2  177.31  4991.4  176.81  4995.2  177.31  4999.1  178.67
  5021.3  180.49  5057.1  181.55  5258.6  185.02  5379.0  187.68  5393.2  188.59
  5428.4  188.60  5435.9  189.52  5499.4  189.53  5513.7  190.36  5548.8  190.41
  5570.5  191.53  5591.4  191.09  5680.9  193.38  5811.4  196.19  5982.1  195.78
#Mann=8,-1,0
  3503.2    0.12       0  3674.5   0.013       0  3880.2    0.12       0
  4743.9    0.03       0  4949.5    0.12       0  4991.2    0.05       0
  4995.2    0.12       0  5680.9    0.04       0
Bank Sta=4991.2,4995.2
Exp/Cntr=0.3,0.1

Chan Stop Cuts=-1