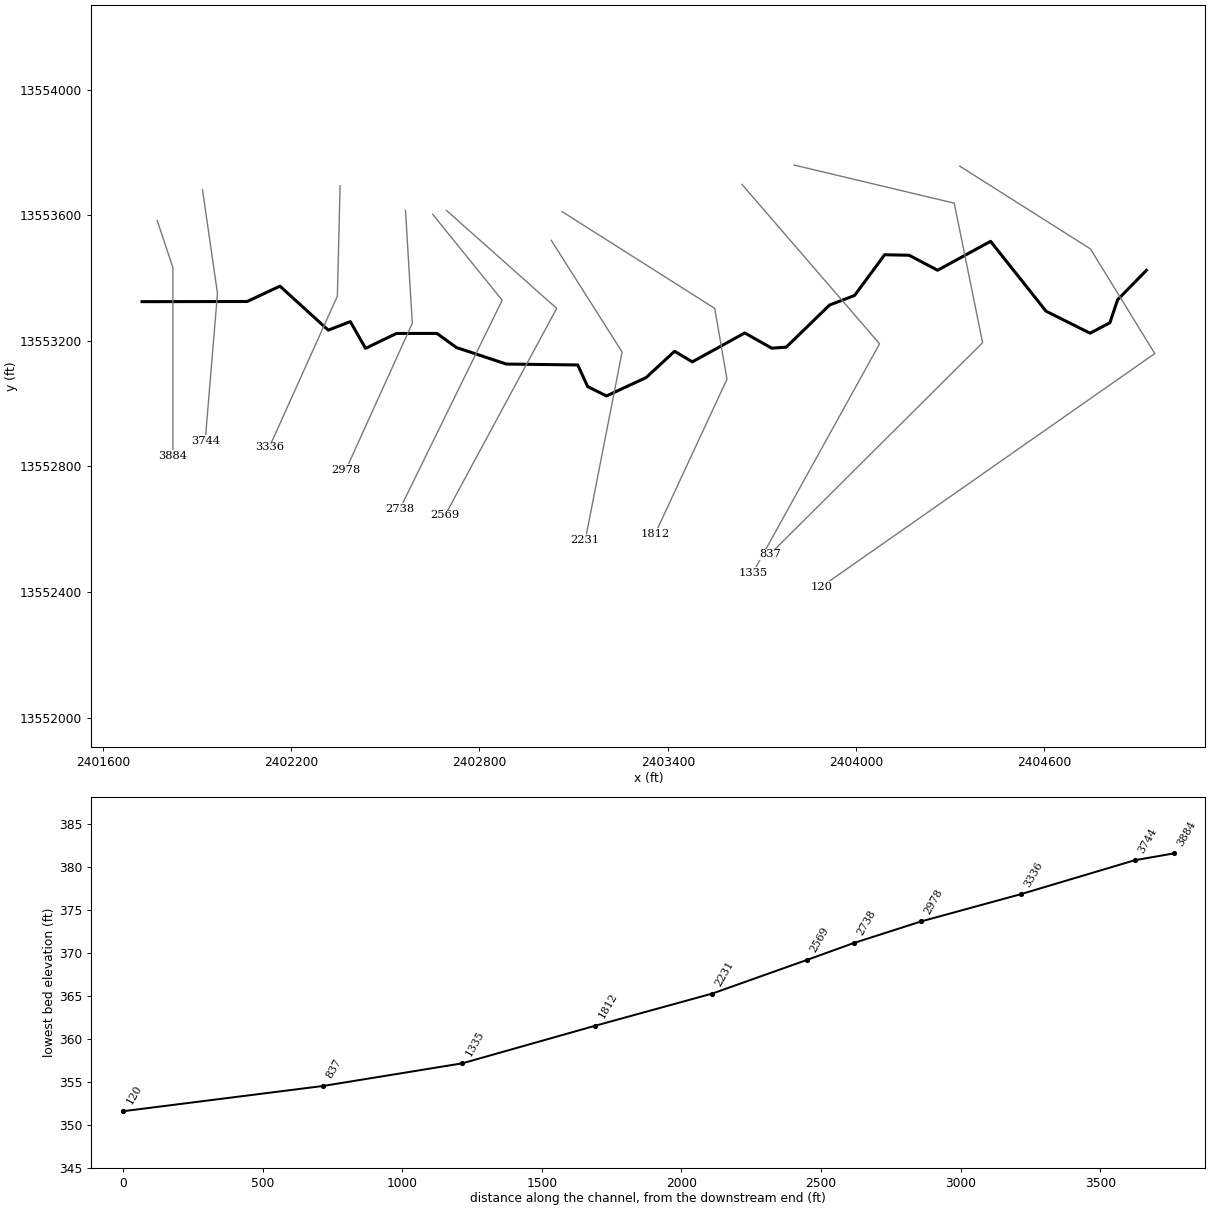
--- TRIB 4_1 TO THOMAS CREEK.prj (project) ---

Proj Title=TRIB 4_1 TO THOMAS CREEK Base Level Engineering
Current Plan=p01
Default Exp/Contr=0.3,0.1
English Units
Geom File=g01
Flow File=f01
Plan File=p01
BEGIN DESCRIPTION:
TRIB 4_1 TO THOMAS CREEK
END DESCRIPTION:

--- TRIB 4_1 TO THOMAS CREEK.p01 (plan) ---

Plan Title=Multiple Run
Short Identifier=Multiple
Geom File=g01
Flow File=f01
Subcritical Flow
K Sum by GR= 0
Std Step Tol= 0.01
Critical Tol= 0.01
Num of Std Step Trials= 20
Max Error Tol= 0.3
Flow Tol Ratio= 0.001
Split Flow NTrial= 30
Split Flow Tol= 0.02
Split Flow Ratio= 0.02
Log Output Level= 0
Friction Slope Method= 1
Unsteady Friction Slope Method= 2
Unsteady Bridges Friction Slope Method= 1
Parabolic Critical Depth
Global Vel Dist=  1 , 1 , 1
Global Log Level= 0
CheckData=True
Encroach Param= -1, 0, 0, 0
BEGIN DESCRIPTION:
Multiple Run
END DESCRIPTION:

--- TRIB 4_1 TO THOMAS CREEK.f01 (steady flow) ---

Flow Title=Multiple
Number of Profiles=7
Profile Names=10-year,25-year,50-year,1pct_min,100-year,1pct_plu,500-year
River Rch & RM= TRIB 4_1 TO THOM,Reach-1,3884
     383     610     812     525    1047    2089    1724
Boundary for River Rch & Prof#=TRIB 4_1 TO THOM,Reach-1,1
Up Type=0
Dn Type=3
Dn Slope=0.005
Boundary for River Rch & Prof#=TRIB 4_1 TO THOM,Reach-1,2
Up Type=0
Dn Type=3
Dn Slope=0.005
Boundary for River Rch & Prof#=TRIB 4_1 TO THOM,Reach-1,3
Up Type=0
Dn Type=3
Dn Slope=0.005
Boundary for River Rch & Prof#=TRIB 4_1 TO THOM,Reach-1,4
Up Type=0
Dn Type=3
Dn Slope=0.005
Boundary for River Rch & Prof#=TRIB 4_1 TO THOM,Reach-1,5
Up Type=0
Dn Type=3
Dn Slope=0.005
Boundary for River Rch & Prof#=TRIB 4_1 TO THOM,Reach-1,6
Up Type=0
Dn Type=3
Dn Slope=0.005
Boundary for River Rch & Prof#=TRIB 4_1 TO THOM,Reach-1,7
Up Type=0
Dn Type=3
Dn Slope=0.005

--- TRIB 4_1 TO THOMAS CREEK.g01 (geometry) ---

Geom Title=Existing Conditions

River Reach=TRIB 4_1 TO THOM,Reach-1
Reach XY= 30
      2401725.00     13553325.00      2402059.79     13553325.54
      2402164.38     13553374.40      2402318.34     13553234.31
      2402388.66     13553261.42      2402437.01     13553176.21
      2402535.48     13553223.77      2402664.49     13553223.80
      2402726.60     13553178.86      2402885.50     13553126.22
      2403113.17     13553123.35      2403144.71     13553054.50
      2403204.73     13553024.61      2403331.06     13553083.17
      2403421.67     13553166.99      2403478.23     13553133.25
      2403645.18     13553225.29      2403731.13     13553176.81
      2403777.30     13553180.09      2403915.32     13553314.22
      2403995.13     13553344.78      2404090.89     13553474.48
      2404168.95     13553472.85      2404259.61     13553425.08
      2404428.42     13553517.24      2404604.87     13553294.77
      2404745.27     13553224.60      2404808.51     13553257.77
      2404833.12     13553331.05      2404925.00     13553425.00

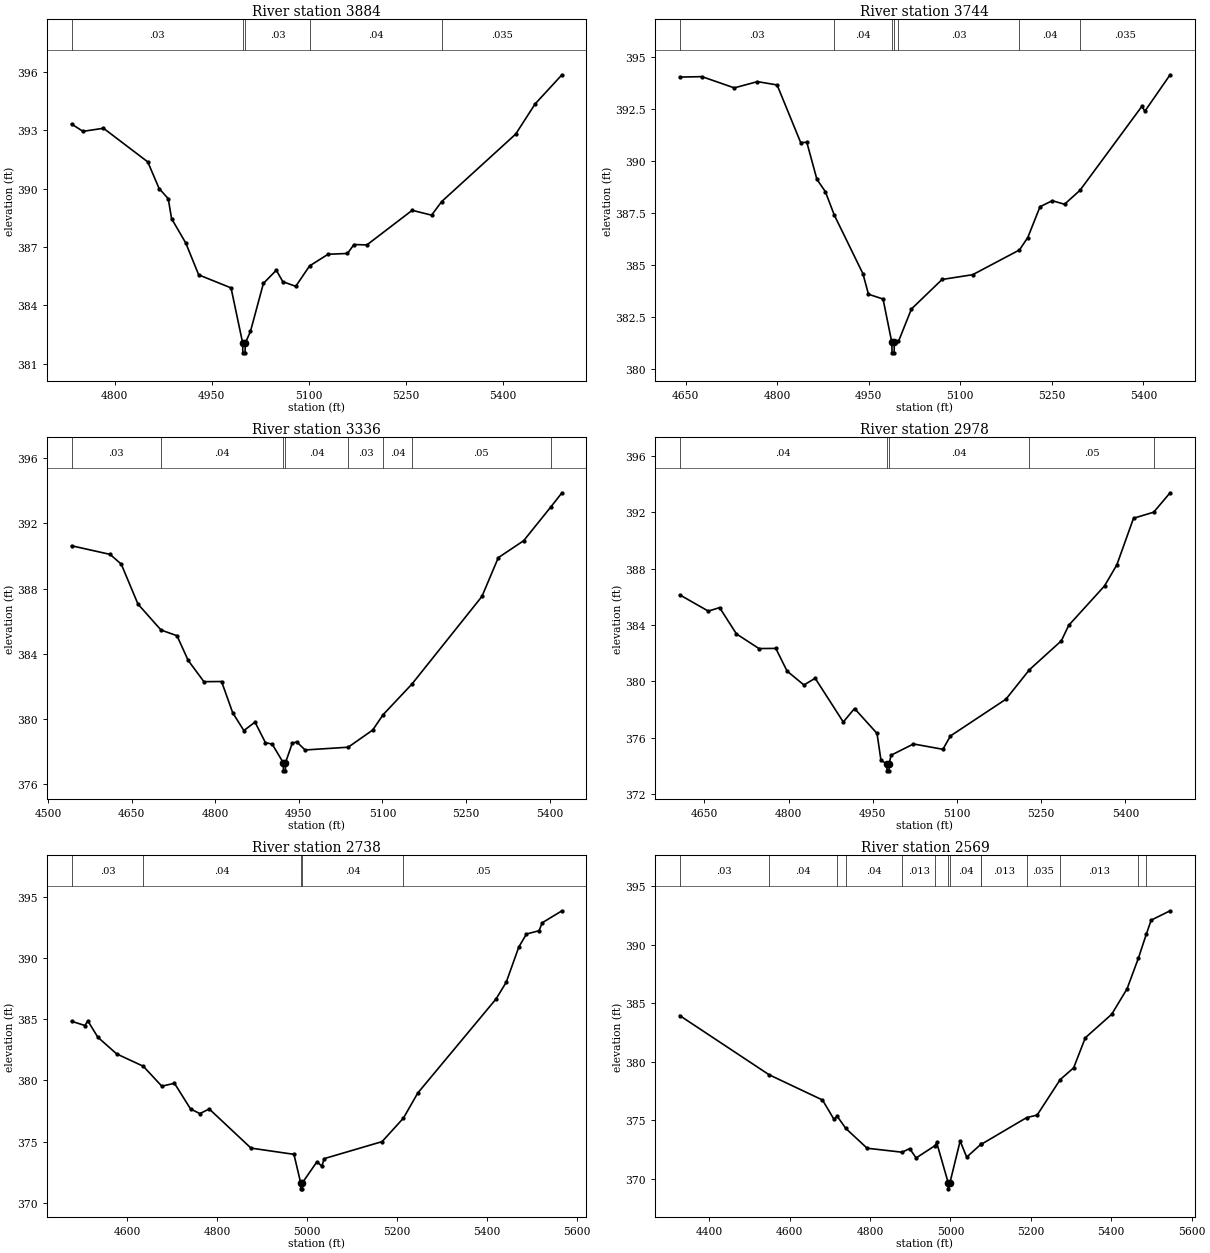
Type RM Length L Ch R = 1,3884,140,140,140
BEGIN DESCRIPTION:
TRIB 4_1 TO THOMAS CREEK 4.0
END DESCRIPTION:
XS GIS Cut Line= 3
      2401773.27     13553583.47      2401823.26     13553433.51
      2401823.26     13552833.49
#Sta/Elev= 30
  4733.4  393.33  4751.1  392.95  4782.8  393.11  4851.3  391.38  4868.8  390.01
  4882.9  389.49  4888.1  388.46  4910.0  387.21  4930.0  385.57  4980.0  384.90
  4998.0  382.06  4998.2  381.56  5001.7  381.56  5002.0  382.06  5010.0  382.66
  5030.0  385.13  5050.0  385.81  5060.0  385.22  5080.0  384.98  5101.4  386.03
  5130.0  386.63  5160.0  386.67  5170.0  387.13  5190.0  387.11  5260.0  388.89
  5290.0  388.64  5305.6  389.34  5420.0  392.81  5450.0  394.36  5491.5  395.86
#Mann=5,-1,0
  4733.4    0.03       0  4998.0    0.03       0  5002.0    0.03       0
  5101.4    0.04       0  5305.6   0.035       0
Bank Sta=4998,5002
Exp/Cntr=0.3,0.1

Type RM Length L Ch R = 1,3744,408,408,408
BEGIN DESCRIPTION:
Mapping XS 6ff86ecb
END DESCRIPTION:
XS GIS Cut Line= 3
      2401917.58     13553681.21      2401965.32     13553351.34
      2401926.26     13552882.58
#Sta/Elev= 30
  4640.2  394.04  4676.8  394.06  4729.7  393.52  4767.7  393.82  4799.9  393.66
  4838.5  390.89  4848.6  390.90  4865.1  389.12  4878.9  388.53  4893.6  387.40
  4940.5  384.58  4949.6  383.59  4973.5  383.36  4987.9  381.27  4988.2  380.77
  4991.7  380.77  4991.9  381.27  4998.8  381.32  5020.0  382.88  5070.2  384.30
  5120.4  384.53  5197.0  385.72  5210.7  386.32  5230.7  387.80  5250.8  388.09
  5270.9  387.92  5296.2  388.59  5397.6  392.63  5402.6  392.40  5443.9  394.15
#Mann=7,-1,0
  4640.2    0.03       0  4893.6    0.04       0  4987.9    0.03       0
  4991.9    0.04       0  4998.8    0.03       0  5197.0    0.04       0
  5296.2   0.035       0
Bank Sta=4987.9,4991.9
Exp/Cntr=0.3,0.1

Type RM Length L Ch R = 1,3336,358,358,358
BEGIN DESCRIPTION:
Mapping XS edf94b13
END DESCRIPTION:
XS GIS Cut Line= 3
      2402355.95     13553694.23      2402347.27     13553342.66
      2402130.24     13552860.86
#Sta/Elev= 30
  4542.0  390.63  4611.3  390.10  4631.3  389.50  4661.3  387.05  4702.6  385.46
  4731.3  385.11  4751.3  383.60  4779.6  382.29  4811.3  382.30  4831.3  380.38
  4851.3  379.29  4871.3  379.81  4890.0  378.55  4902.1  378.46  4922.0  377.32
  4922.3  376.82  4925.8  376.82  4926.0  377.32  4938.1  378.51  4946.0  378.60
  4961.2  378.10  5038.5  378.27  5082.4  379.32  5101.3  380.27  5152.8  382.14
  5278.5  387.52  5307.9  389.90  5353.4  390.94  5402.1  393.01  5422.1  393.88
#Mann=8,-1,0
  4542.0    0.03       0  4702.6    0.04       0  4922.0    0.04       0
  4926.0    0.04       0  5038.5    0.03       0  5101.3    0.04       0
  5152.8    0.05       0  5402.1   0.035       0
Bank Sta=4922,4926
Exp/Cntr=0.3,0.1

Type RM Length L Ch R = 1,2978,240,240,240
BEGIN DESCRIPTION:
Mapping XS 8d435d2a
END DESCRIPTION:
XS GIS Cut Line= 3
      2402564.28     13553616.06      2402585.98     13553255.85
      2402373.97     13552788.56
#Sta/Elev= 30
  4605.8  386.15  4656.9  384.99  4677.0  385.24  4707.0  383.37  4747.1  382.33
  4777.2  382.34  4797.2  380.73  4827.3  379.74  4847.3  380.22  4897.4  377.11
  4917.4  378.07  4957.5  376.30  4964.6  374.38  4975.1  374.14  4975.4  373.64
  4978.9  373.64  4979.1  374.14  4982.6  374.75  5022.5  375.55  5074.9  375.17
  5088.4  376.12  5187.2  378.73  5229.2  380.83  5286.0  382.88  5299.1  383.98
  5362.9  386.78  5384.9  388.28  5414.6  391.59  5450.5  392.02  5479.8  393.40
#Mann=5,-1,0
  4605.8    0.04       0  4975.1    0.04       0  4979.1    0.04       0
  5229.2    0.05       0  5450.5   0.035       0
Bank Sta=4975.1,4979.1
Exp/Cntr=0.3,0.1

Type RM Length L Ch R = 1,2738,169,169,169
BEGIN DESCRIPTION:
Mapping XS 9cd71026
END DESCRIPTION:
XS GIS Cut Line= 3
      2402651.06     13553603.10      2402872.44     13553329.64
      2402546.92     13552665.57
#Sta/Elev= 30
  4476.0  384.84  4505.9  384.49  4512.3  384.87  4534.7  383.53  4576.5  382.17
  4635.8  381.16  4677.0  379.53  4705.1  379.77  4740.9  377.67  4761.7  377.29
  4782.5  377.67  4875.4  374.47  4971.0  373.96  4985.9  371.64  4986.1  371.14
  4989.6  371.14  4989.9  371.64  5022.3  373.36  5032.9  372.99  5038.4  373.61
  5167.1  375.00  5214.6  376.92  5246.5  378.97  5420.9  386.67  5443.4  388.03
  5471.4  390.91  5488.4  391.97  5516.4  392.24  5523.5  392.89  5567.4  393.87
#Mann=5,-1,0
  4476.0    0.03       0  4635.8    0.04       0  4985.9    0.04       0
  4989.9    0.04       0  5214.6    0.05       0
Bank Sta=4985.9,4989.9
Exp/Cntr=0.3,0.1

Type RM Length L Ch R = 1,2569,338,338,338
BEGIN DESCRIPTION:
Mapping XS 095979f4
END DESCRIPTION:
XS GIS Cut Line= 3
      2402694.52     13553616.07      2403046.05     13553303.59
      2402690.16     13552643.90
#Sta/Elev= 30
  4326.5  383.97  4548.9  378.91  4681.8  376.75  4710.2  375.11  4718.2  375.37
  4739.8  374.32  4792.8  372.63  4879.9  372.29  4898.5  372.60  4914.7  371.80
  4962.1  372.86  4965.7  373.12  4994.6  369.66  4994.9  369.16  4998.6  369.66
  5024.2  373.25  5040.4  371.87  5075.9  372.97  5076.5  372.96  5189.7  375.25
  5215.6  375.46  5273.1  378.50  5306.5  379.50  5335.5  382.07  5401.2  384.08
  5439.3  386.25  5467.4  388.86  5487.5  390.95  5499.3  392.12  5546.4  392.92
#Mann=14,-1,0
  4326.5    0.03       0  4548.9    0.04       0  4718.2   0.013       0
  4739.8    0.04       0  4879.9   0.013       0  4962.1    0.04       0
  4994.6    0.04       0  4998.6    0.04       0  5075.9   0.035       0
  5076.5   0.013       0  5189.7   0.035       0  5273.1   0.013       0
  5467.4    0.04       0  5487.5   0.013       0
Bank Sta=4994.6,4998.6
Exp/Cntr=0.3,0.1

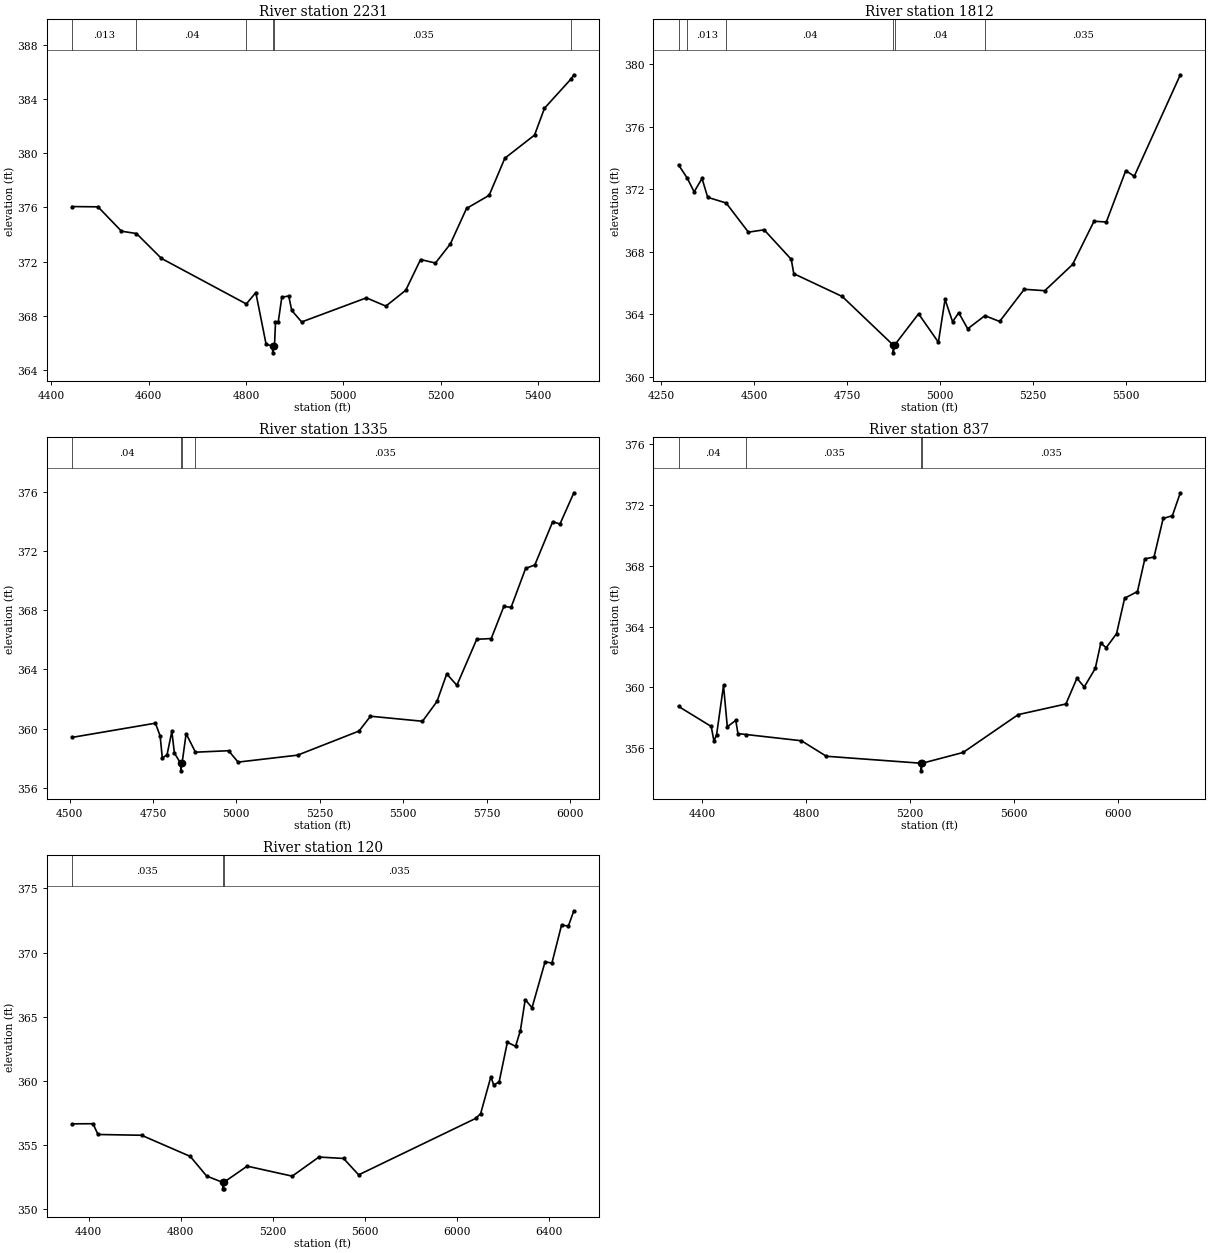
Type RM Length L Ch R = 1,2231,419,419,419
BEGIN DESCRIPTION:
Mapping XS 88a14425
END DESCRIPTION:
XS GIS Cut Line= 3
      2403028.68     13553520.62      2403254.38     13553164.71
      2403137.19     13552565.71
#Sta/Elev= 30
  4442.3  376.06  4495.6  376.04  4543.9  374.24  4574.7  374.07  4626.1  372.23
  4800.6  368.87  4820.1  369.71  4841.3  365.89  4854.5  365.76  4854.8  365.26
  4858.5  365.76  4860.6  367.51  4866.1  367.51  4873.6  369.36  4887.8  369.46
  4894.0  368.39  4914.4  367.54  5047.4  369.32  5087.6  368.71  5128.4  369.88
  5158.9  372.15  5189.5  371.89  5220.1  373.30  5253.4  375.92  5299.9  376.89
  5332.2  379.63  5393.3  381.34  5413.7  383.32  5468.0  385.47  5474.1  385.79
#Mann=6,-1,0
  4442.3   0.013       0  4574.7    0.04       0  4800.6   0.035       0
  4854.5   0.035       0  4858.5   0.035       0  5468.0    0.04       0
Bank Sta=4854.5,4858.5
Exp/Cntr=0.3,0.1

Type RM Length L Ch R = 1,1812,477,477,477
BEGIN DESCRIPTION:
Mapping XS ebf05470
END DESCRIPTION:
XS GIS Cut Line= 4
      2403063.44     13553611.73      2403549.52     13553303.59
      2403588.59     13553077.90      2403359.28     13552584.67
#Sta/Elev= 30
  4297.5  373.56  4320.7  372.72  4339.4  371.83  4360.6  372.69  4375.9  371.48
  4425.3  371.12  4485.2  369.25  4527.5  369.40  4600.4  367.51  4607.2  366.59
  4737.4  365.13  4874.2  362.02  4874.5  361.52  4878.2  362.02  4942.6  364.02
  4995.8  362.20  5013.7  364.94  5034.0  363.51  5050.5  364.09  5074.6  363.06
  5120.8  363.90  5160.4  363.53  5226.6  365.59  5281.7  365.50  5356.5  367.18
  5414.1  369.95  5447.1  369.90  5499.4  373.19  5522.2  372.83  5646.0  379.33
#Mann=6,-1,0
  4297.5    0.04       0  4320.7   0.013       0  4425.3    0.04       0
  4874.2    0.04       0  4878.2    0.04       0  5120.8   0.035       0
Bank Sta=4874.2,4878.2
Exp/Cntr=0.3,0.1

Type RM Length L Ch R = 1,1335,498,498,498
BEGIN DESCRIPTION:
Mapping XS 7608a582
END DESCRIPTION:
XS GIS Cut Line= 3
      2403636.34     13553698.54      2404074.70     13553190.75
      2403671.03     13552461.55
#Sta/Elev= 30
  4507.5  359.40  4757.3  360.36  4771.5  359.50  4778.1  358.00  4792.4  358.24
  4806.6  359.81  4814.3  358.34  4833.2  357.64  4833.4  357.14  4837.2  357.64
  4849.4  359.65  4877.4  358.40  4976.7  358.50  5005.2  357.73  5183.6  358.20
  5367.8  359.83  5402.1  360.83  5558.0  360.49  5601.5  361.83  5630.7  363.69
  5661.1  362.92  5720.6  366.03  5764.1  366.08  5801.9  368.25  5823.7  368.19
  5867.2  370.82  5894.7  371.05  5948.5  373.98  5970.2  373.82  6011.8  375.93
#Mann=4,-1,0
  4507.5    0.04       0  4833.2   0.035       0  4837.2    0.04       0
  4877.4   0.035       0
Bank Sta=4833.2,4837.2
Exp/Cntr=0.3,0.1

Type RM Length L Ch R = 1,837,717,717,717
BEGIN DESCRIPTION:
Mapping XS aeb598ac
END DESCRIPTION:
XS GIS Cut Line= 4
      2403802.25     13553760.32      2404312.64     13553638.79
      2404402.92     13553194.35      2403725.82     13552520.72
#Sta/Elev= 30
  4307.9  358.75  4433.9  357.43  4444.4  356.46  4454.6  356.89  4481.2  360.13
  4495.8  357.41  4528.4  357.83  4536.9  356.96  4568.8  356.90  4781.3  356.49
  4877.3  355.47  5242.6  355.01  5242.9  354.51  5246.6  355.01  5404.4  355.72
  5616.5  358.21  5800.3  358.91  5842.8  360.60  5871.1  360.03  5913.5  361.25
  5934.7  362.91  5955.9  362.62  5995.5  363.54  6026.6  365.87  6076.1  366.31
  6104.4  368.46  6139.8  368.58  6175.1  371.12  6210.5  371.30  6241.2  372.81
#Mann=4,-1,0
  4307.9    0.04       0  4568.8   0.035       0  5242.6   0.035       0
  5246.6   0.035       0
Bank Sta=5242.6,5246.6
Exp/Cntr=0.3,0.1

Type RM Length L Ch R = 1,120,0,0,0
BEGIN DESCRIPTION:
4827
END DESCRIPTION:
XS GIS Cut Line= 4
      2404329.99     13553756.86      2404746.67     13553492.96
      2404951.53     13553159.63      2403889.54     13552416.93
#Sta/Elev= 30
  4327.7  356.64  4418.8  356.65  4440.2  355.81  4629.5  355.75  4841.2  354.10
  4912.4  352.57  4982.4  352.07  4982.6  351.57  4986.1  351.57  4986.4  352.07
  5088.5  353.34  5284.3  352.56  5400.3  354.05  5507.5  353.94  5572.9  352.66
  6082.2  357.07  6103.1  357.44  6147.6  360.32  6159.8  359.67  6183.4  359.91
  6219.1  363.00  6254.9  362.69  6275.8  363.92  6296.7  366.33  6326.4  365.70
  6383.0  369.28  6412.7  369.18  6454.6  372.14  6484.2  372.07  6508.1  373.26
#Mann=3,-1,0
  4327.7   0.035       0  4982.4   0.035       0  4986.4   0.035       0
Bank Sta=4982.4,4986.4
Exp/Cntr=0.3,0.1

Chan Stop Cuts=-1