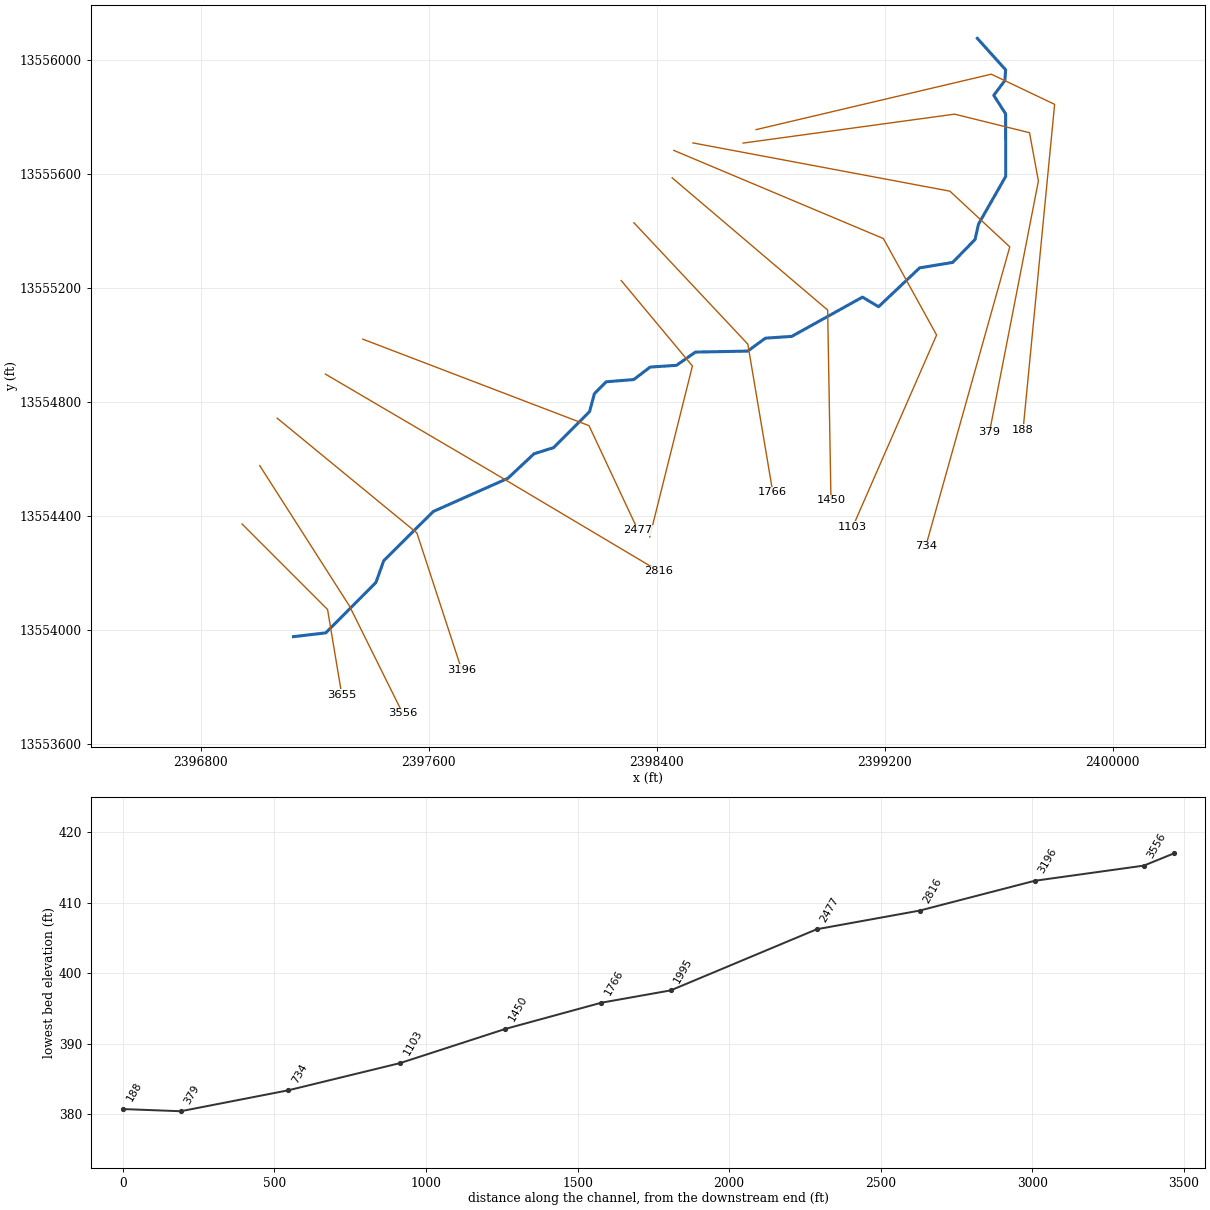
--- TRIB 4_2 TO THOMAS CREEK.prj (project) ---

Proj Title=TRIB 4_2 TO THOMAS CREEK Base Level Engineering
Current Plan=p01
Default Exp/Contr=0.3,0.1
English Units
Geom File=g01
Flow File=f01
Plan File=p01
BEGIN DESCRIPTION:
TRIB 4_2 TO THOMAS CREEK
END DESCRIPTION:

--- TRIB 4_2 TO THOMAS CREEK.p01 (plan) ---

Plan Title=Multiple Run
Short Identifier=Multiple
Geom File=g01
Flow File=f01
Subcritical Flow
K Sum by GR= 0
Std Step Tol= 0.01
Critical Tol= 0.01
Num of Std Step Trials= 20
Max Error Tol= 0.3
Flow Tol Ratio= 0.001
Split Flow NTrial= 30
Split Flow Tol= 0.02
Split Flow Ratio= 0.02
Log Output Level= 0
Friction Slope Method= 1
Unsteady Friction Slope Method= 2
Unsteady Bridges Friction Slope Method= 1
Parabolic Critical Depth
Global Vel Dist=  1 , 1 , 1
Global Log Level= 0
CheckData=True
Encroach Param= -1, 0, 0, 0
BEGIN DESCRIPTION:
Multiple Run
END DESCRIPTION:

--- TRIB 4_2 TO THOMAS CREEK.f01 (steady flow) ---

Flow Title=Multiple
Number of Profiles=7
Profile Names=10-year,25-year,50-year,1pct_min,100-year,1pct_plu,500-year
River Rch & RM= TRIB 4_2 TO THOM,Reach-1,3655
     309     486     643     413     824    1644    1340
Boundary for River Rch & Prof#=TRIB 4_2 TO THOM,Reach-1,1
Up Type=0
Dn Type=3
Dn Slope=0.005
Boundary for River Rch & Prof#=TRIB 4_2 TO THOM,Reach-1,2
Up Type=0
Dn Type=3
Dn Slope=0.005
Boundary for River Rch & Prof#=TRIB 4_2 TO THOM,Reach-1,3
Up Type=0
Dn Type=3
Dn Slope=0.005
Boundary for River Rch & Prof#=TRIB 4_2 TO THOM,Reach-1,4
Up Type=0
Dn Type=3
Dn Slope=0.005
Boundary for River Rch & Prof#=TRIB 4_2 TO THOM,Reach-1,5
Up Type=0
Dn Type=3
Dn Slope=0.005
Boundary for River Rch & Prof#=TRIB 4_2 TO THOM,Reach-1,6
Up Type=0
Dn Type=3
Dn Slope=0.005
Boundary for River Rch & Prof#=TRIB 4_2 TO THOM,Reach-1,7
Up Type=0
Dn Type=3
Dn Slope=0.005

--- TRIB 4_2 TO THOMAS CREEK.g01 (geometry) ---

Geom Title=Existing Conditions

River Reach=TRIB 4_2 TO THOM,Reach-1
Reach XY= 30
      2397125.00     13553975.00      2397238.33     13553988.35
      2397414.22     13554165.32      2397441.65     13554241.67
      2397615.32     13554414.24      2397877.29     13554530.85
      2397968.96     13554616.82      2398038.21     13554638.63
      2398164.21     13554765.34      2398180.74     13554827.57
      2398222.33     13554869.58      2398319.02     13554877.36
      2398376.60     13554921.15      2398469.02     13554927.36
      2398535.50     13554973.78      2398719.06     13554977.26
      2398780.98     13555022.64      2398873.42     13555028.83
      2399121.77     13555166.75      2399178.34     13555132.99
      2399322.57     13555269.47      2399438.33     13555288.39
      2399516.87     13555368.93      2399529.19     13555423.26
      2399624.49     13555590.21      2399624.34     13555809.84
      2399582.59     13555875.01      2399621.43     13555926.65
      2399624.40     13555964.36      2399525.00     13556075.00

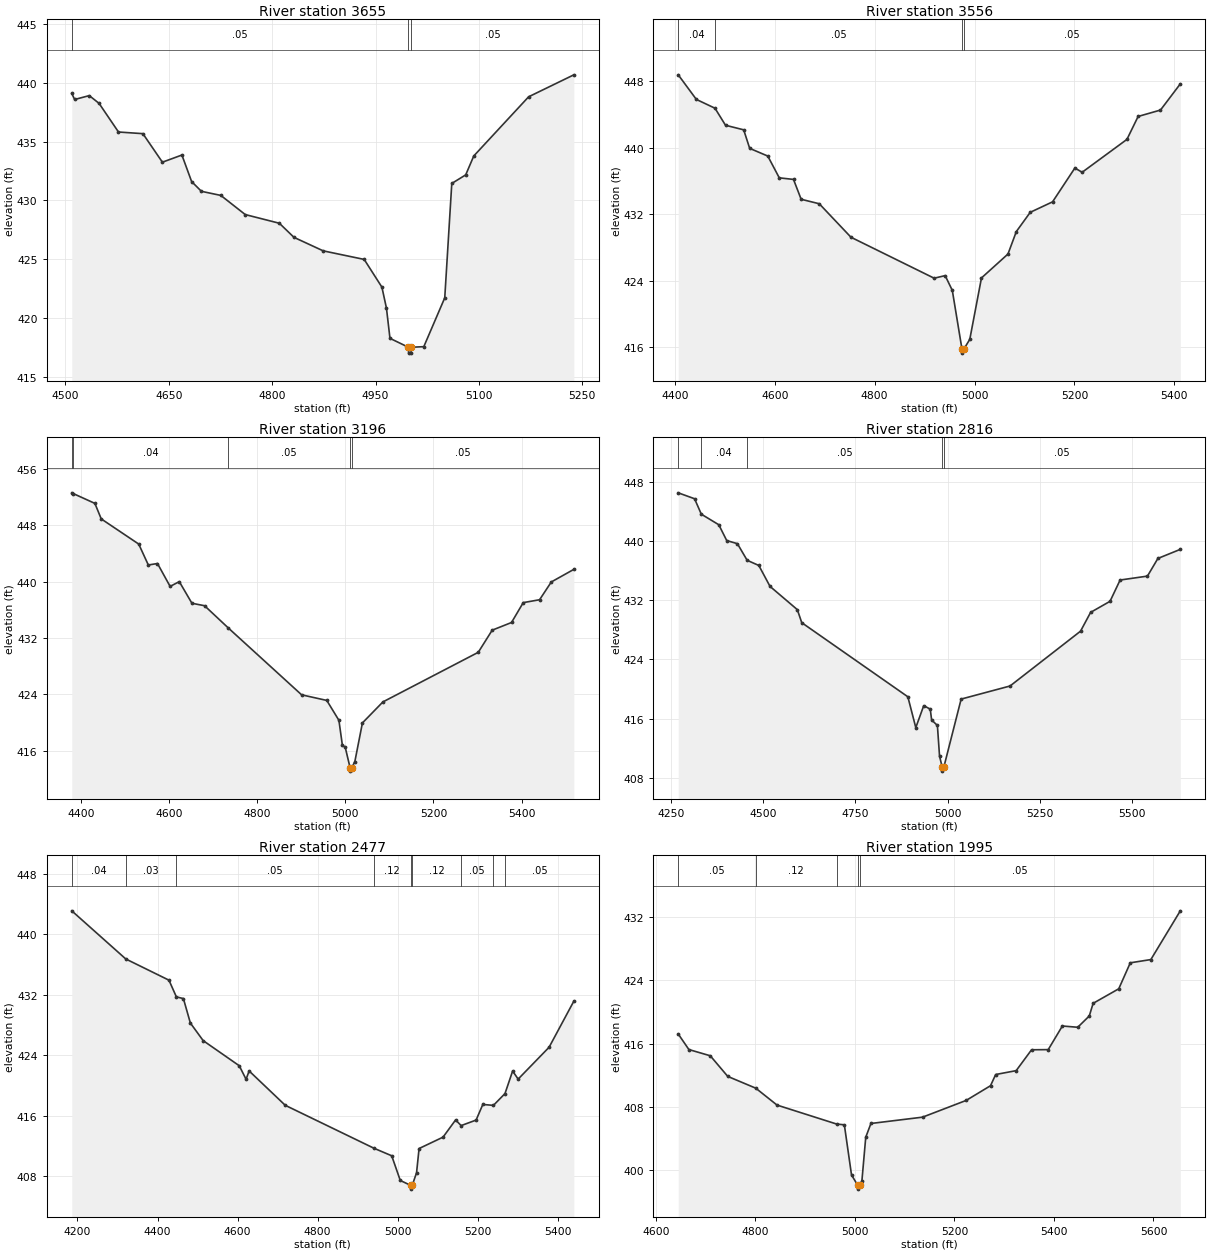
Type RM Length L Ch R = 1,3655,99,99,99
BEGIN DESCRIPTION:
TRIB 4_2 TO THOMAS CREEK 6.0
END DESCRIPTION:
XS GIS Cut Line= 3
      2396944.40     13554370.35      2397244.43     13554070.32
      2397294.44     13553770.27
#Sta/Elev= 30
  4509.2  439.11  4513.4  438.60  4534.6  438.93  4548.8  438.27  4577.0  435.83
  4612.4  435.69  4640.7  433.26  4669.0  433.87  4683.1  431.61  4697.3  430.78
  4725.5  430.43  4760.9  428.80  4810.4  428.06  4831.6  426.86  4874.0  425.71
  4933.5  424.98  4959.2  422.62  4965.8  420.83  4970.9  418.26  4997.7  417.50
  4998.0  417.00  5001.5  417.00  5001.7  417.50  5020.0  417.55  5050.4  421.71
  5060.6  431.45  5080.8  432.18  5092.5  433.79  5172.1  438.83  5237.7  440.70
#Mann=3,-1,0
  4509.2    0.05       0  4997.7    0.05       0  5001.7    0.05       0
Bank Sta=4997.7,5001.7
Exp/Cntr=0.3,0.1

Type RM Length L Ch R = 1,3556,360,360,360
BEGIN DESCRIPTION:
Mapping XS 15001e2e
END DESCRIPTION:
XS GIS Cut Line= 3
      2397006.25     13554575.55      2397321.47     13554082.28
      2397508.27     13553705.76
#Sta/Elev= 30
  4406.5  448.77  4442.8  445.81  4480.1  444.75  4501.2  442.70  4537.6  442.15
  4549.6  439.92  4585.9  438.99  4608.9  436.37  4637.4  436.18  4652.7  433.79
  4689.0  433.25  4752.5  429.22  4919.1  424.29  4941.2  424.60  4955.5  422.82
  4974.8  415.77  4975.0  415.27  4978.8  415.77  4990.5  416.93  5013.9  424.32
  5067.0  427.20  5083.7  429.90  5111.6  432.22  5156.3  433.48  5201.0  437.55
  5215.6  437.04  5305.3  441.00  5327.7  443.76  5372.5  444.53  5412.2  447.68
#Mann=4,-1,0
  4406.5    0.04       0  4480.1    0.05       0  4974.8    0.05       0
  4978.8    0.05       0
Bank Sta=4974.8,4978.8
Exp/Cntr=0.3,0.1

Type RM Length L Ch R = 1,3196,380,380,380
BEGIN DESCRIPTION:
Mapping XS e65207b8
END DESCRIPTION:
XS GIS Cut Line= 3
      2397067.58     13554741.85      2397557.88     13554339.11
      2397715.08     13553858.78
#Sta/Elev= 30
  4378.9  452.61  4382.4  452.50  4431.4  451.11  4445.8  448.91  4530.9  445.34
  4552.7  442.37  4573.5  442.58  4602.2  439.33  4623.0  440.01  4651.7  436.94
  4680.4  436.59  4734.7  433.41  4900.7  423.95  4957.9  423.15  4985.4  420.33
  4993.3  416.79  4999.7  416.52  5010.7  413.62  5011.0  413.12  5014.7  413.62
  5021.6  414.48  5038.8  419.96  5085.3  422.94  5301.8  429.98  5333.4  433.12
  5377.3  434.21  5403.9  437.03  5441.0  437.44  5467.6  439.96  5518.8  441.75
#Mann=5,-1,0
  4378.9    0.05       0  4382.4    0.04       0  4734.7    0.05       0
  5010.7    0.05       0  5014.7    0.05       0
Bank Sta=5010.7,5014.7
Exp/Cntr=0.3,0.1

Type RM Length L Ch R = 1,2816,339,339,339
BEGIN DESCRIPTION:
Mapping XS 6bdc28cb
END DESCRIPTION:
XS GIS Cut Line= 3
      2397236.87     13554896.54      2397823.47     13554552.17
      2398407.15     13554204.88
#Sta/Elev= 30
  4270.3  446.55  4314.5  445.75  4332.8  443.66  4380.1  442.23  4401.6  440.09
  4430.5  439.67  4456.9  437.42  4488.5  436.72  4518.8  433.89  4592.8  430.74
  4604.7  428.98  4892.0  418.95  4913.5  414.78  4935.0  417.75  4952.6  417.28
  4956.4  415.81  4972.0  415.07  4977.8  410.92  4985.2  409.39  4985.5  408.89
  4989.2  409.39  5036.3  418.64  5168.7  420.41  5359.6  427.83  5386.8  430.37
  5439.4  431.87  5466.7  434.75  5540.7  435.28  5569.0  437.67  5629.7  438.90
#Mann=5,-1,0
  4270.3    0.05       0  4332.8    0.04       0  4456.9    0.05       0
  4985.2    0.05       0  4989.2    0.05       0
Bank Sta=4985.2,4989.2
Exp/Cntr=0.3,0.1

Type RM Length L Ch R = 1,2477,482,482,482
BEGIN DESCRIPTION:
Mapping XS 14d0a47b
END DESCRIPTION:
XS GIS Cut Line= 3
      2397368.13     13555019.15      2398162.02     13554715.61
      2398333.71     13554348.95
#Sta/Elev= 30
  4185.7  443.13  4320.7  436.75  4428.6  433.94  4447.1  431.73  4464.7  431.50
  4482.1  428.26  4514.1  425.93  4604.3  422.60  4621.3  420.81  4629.0  421.91
  4719.2  417.36  4941.3  411.66  4985.3  410.67  5006.7  407.40  5032.6  406.75
  5032.8  406.25  5036.6  406.75  5047.4  408.42  5053.7  411.63  5113.6  413.14
  5145.0  415.42  5158.8  414.67  5196.2  415.40  5213.0  417.47  5239.5  417.35
  5268.4  418.91  5287.5  421.90  5301.3  420.83  5378.6  425.05  5440.5  431.16
#Mann=9,-1,0
  4185.7    0.04       0  4320.7    0.03       0  4447.1    0.05       0
  4941.3    0.12       0  5032.6    0.05       0  5036.6    0.12       0
  5158.8    0.05       0  5239.5    0.12       0  5268.4    0.05       0
Bank Sta=5032.6,5036.6
Exp/Cntr=0.3,0.1

Type RM Length L Ch R = 1,1995,229,229,229
BEGIN DESCRIPTION:
TRIB 4_2 TO THOMAS CREEK 3.0
END DESCRIPTION:
XS GIS Cut Line= 3
      2398275.03     13555224.97      2398525.00     13554925.00
      2398375.01     13554325.04
#Sta/Elev= 30
  4645.0  417.22  4666.4  415.25  4709.4  414.46  4744.5  411.85  4800.8  410.36
  4843.5  408.22  4963.2  405.82  4978.8  405.72  4993.2  399.38  5005.5  398.08
  5005.7  397.58  5009.5  398.08  5014.0  398.57  5021.8  404.15  5032.2  405.89
  5136.0  406.69  5223.6  408.81  5272.5  410.67  5282.9  412.09  5324.1  412.58
  5355.0  415.22  5388.5  415.24  5416.9  418.23  5447.8  418.07  5471.0  419.50
  5478.7  421.10  5530.2  422.94  5553.4  426.23  5594.7  426.64  5653.9  432.81
#Mann=5,-1,0
  4645.0    0.05       0  4800.8    0.12       0  4963.2    0.05       0
  5005.5    0.05       0  5009.5    0.05       0
Bank Sta=5005.5,5009.5
Exp/Cntr=0.3,0.1

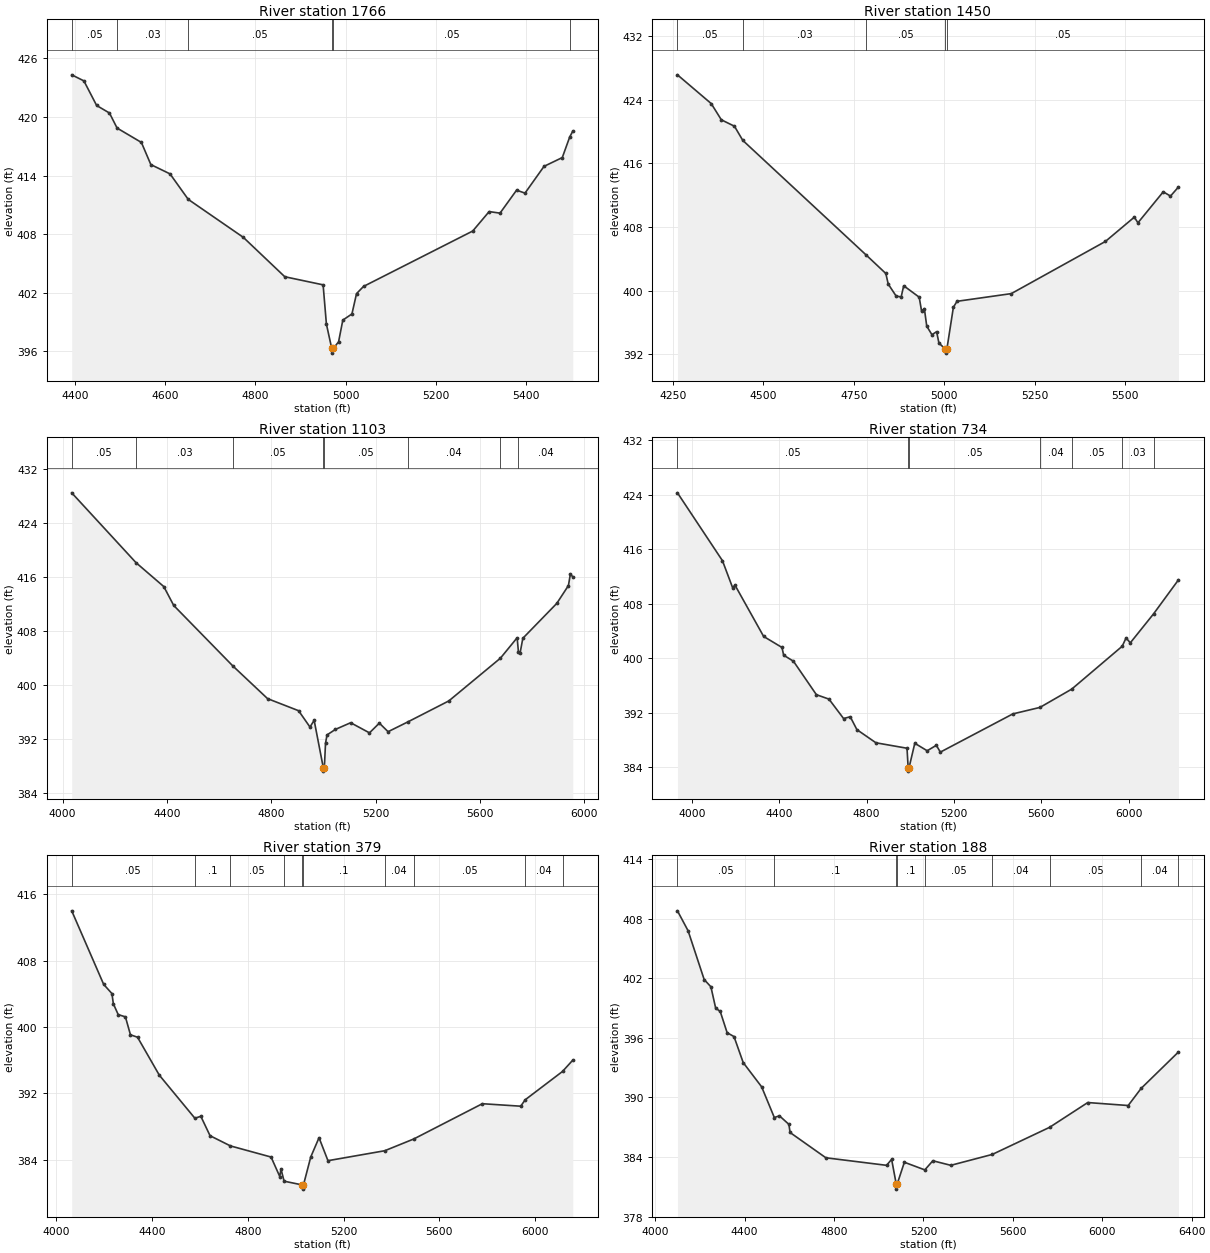
Type RM Length L Ch R = 1,1766,316,316,316
BEGIN DESCRIPTION:
Mapping XS 36f184a9
END DESCRIPTION:
XS GIS Cut Line= 3
      2398319.65     13555427.71      2398719.47     13555001.63
      2398807.02     13554482.14
#Sta/Elev= 30
  4392.5  424.32  4419.5  423.70  4447.8  421.18  4476.2  420.41  4493.1  418.87
  4547.0  417.40  4568.0  415.13  4610.5  414.18  4650.9  411.57  4773.1  407.68
  4865.0  403.65  4950.0  402.82  4957.3  398.80  4969.0  396.33  4969.3  395.83
  4973.0  396.33  4984.3  396.99  4993.7  399.21  5013.9  399.84  5024.1  401.92
  5039.7  402.66  5281.8  408.33  5318.2  410.32  5342.3  410.16  5379.0  412.51
  5397.7  412.21  5439.9  414.95  5480.4  415.85  5496.8  417.95  5503.6  418.55
#Mann=6,-1,0
  4392.5    0.05       0  4493.1    0.03       0  4650.9    0.05       0
  4969.0    0.05       0  4973.0    0.05       0  5496.8    0.03       0
Bank Sta=4969,4973
Exp/Cntr=0.3,0.1

Type RM Length L Ch R = 1,1450,347,347,347
BEGIN DESCRIPTION:
Mapping XS 83b8faf3
END DESCRIPTION:
XS GIS Cut Line= 3
      2398453.85     13555585.37      2398999.65     13555121.29
      2399011.33     13554452.92
#Sta/Elev= 30
  4262.3  427.14  4355.7  423.52  4383.6  421.48  4419.9  420.67  4442.9  418.89
  4784.8  404.43  4838.3  402.14  4844.9  400.81  4866.9  399.29  4880.7  399.20
  4887.7  400.60  4930.5  399.16  4937.1  397.41  4944.8  397.72  4951.4  395.51
  4965.7  394.44  4978.7  394.82  4985.0  393.39  5003.0  392.62  5003.3  392.12
  5007.0  392.62  5025.0  397.89  5035.0  398.64  5185.1  399.61  5445.1  406.17
  5525.1  409.23  5535.1  408.52  5605.1  412.42  5625.1  411.88  5647.2  413.03
#Mann=5,-1,0
  4262.3    0.05       0  4442.9    0.03       0  4784.8    0.05       0
  5003.0    0.05       0  5007.0    0.05       0
Bank Sta=5003,5007
Exp/Cntr=0.3,0.1

Type RM Length L Ch R = 1,1103,369,369,369
BEGIN DESCRIPTION:
Mapping XS 1b8783ff
END DESCRIPTION:
XS GIS Cut Line= 4
      2398459.67     13555681.67      2399195.20     13555372.29
      2399381.99     13555033.73      2399087.30     13554359.75
#Sta/Elev= 30
  4035.2  428.51  4281.7  418.16  4388.1  414.62  4426.2  411.82  4652.2  402.88
  4785.8  398.02  4904.7  396.23  4948.3  393.81  4964.3  394.81  4999.4  387.78
  4999.6  387.28  5003.4  387.78  5007.9  391.42  5013.6  392.64  5045.7  393.46
  5104.2  394.45  5176.3  392.95  5214.2  394.39  5247.7  393.12  5324.3  394.59
  5480.4  397.68  5678.1  404.01  5742.3  407.04  5747.3  404.90  5753.8  404.84
  5764.1  406.96  5894.2  412.13  5938.8  414.77  5946.4  416.51  5955.4  416.05
#Mann=8,-1,0
  4035.2    0.05       0  4281.7    0.03       0  4652.2    0.05       0
  4999.4    0.05       0  5003.4    0.05       0  5324.3    0.04       0
  5678.1    0.05       0  5747.3    0.04       0
Bank Sta=4999.4,5003.4
Exp/Cntr=0.3,0.1

Type RM Length L Ch R = 1,734,355,355,355
BEGIN DESCRIPTION:
Mapping XS ffda9b5c
END DESCRIPTION:
XS GIS Cut Line= 4
      2398526.80     13555707.93      2399428.68     13555538.64
      2399638.82     13555343.10      2399344.05     13554292.45
#Sta/Elev= 30
  3933.0  424.27  4139.2  414.31  4185.5  410.37  4196.8  410.71  4328.0  403.19
  4412.1  401.57  4419.6  400.44  4464.6  399.55  4569.7  394.64  4627.3  393.99
  4694.3  391.14  4724.8  391.40  4755.3  389.51  4842.5  387.58  4984.9  386.78
  4990.2  383.92  4990.5  383.42  4994.2  383.92  5020.6  387.51  5077.3  386.41
  5119.3  387.21  5137.7  386.21  5469.9  391.82  5593.9  392.77  5739.8  395.46
  5971.0  401.75  5988.7  402.97  6008.1  402.25  6114.6  406.50  6228.9  411.50
#Mann=7,-1,0
  3933.0    0.05       0  4990.2    0.05       0  4994.2    0.05       0
  5593.9    0.04       0  5739.8    0.05       0  5971.0    0.03       0
  6114.6    0.05       0
Bank Sta=4990.2,4994.2
Exp/Cntr=0.3,0.1

Type RM Length L Ch R = 1,379,191,191,191
BEGIN DESCRIPTION:
Mapping XS a1cfd670
END DESCRIPTION:
XS GIS Cut Line= 5
      2398702.84     13555707.34      2399445.05     13555808.91
      2399708.07     13555743.81      2399739.32     13555574.53
      2399567.45     13554691.73
#Sta/Elev= 30
  4065.2  414.01  4198.6  405.14  4233.1  404.03  4239.0  402.80  4259.2  401.50
  4289.4  401.22  4310.4  399.06  4339.9  398.77  4430.7  394.20  4579.3  389.00
  4604.2  389.23  4642.7  386.89  4727.9  385.66  4897.4  384.32  4933.7  381.97
  4938.8  382.88  4951.7  381.41  5028.6  380.95  5028.9  380.45  5032.6  380.95
  5063.1  384.33  5097.6  386.65  5134.9  383.88  5372.0  385.08  5493.3  386.50
  5779.4  390.75  5939.5  390.45  5958.5  391.23  6114.0  394.64  6156.8  396.00
#Mann=10,-1,0
  4065.2    0.05       0  4579.3     0.1       0  4727.9    0.05       0
  4951.7     0.1       0  5028.6    0.05       0  5032.6     0.1       0
  5372.0    0.04       0  5493.3    0.05       0  5958.5    0.04       0
  6114.0    0.05       0
Bank Sta=5028.6,5032.6
Exp/Cntr=0.3,0.1

Type RM Length L Ch R = 1,188,0,0,0
BEGIN DESCRIPTION:
Mapping XS 45aa90f3
END DESCRIPTION:
XS GIS Cut Line= 4
      2398748.64     13555754.62      2399574.05     13555949.19
      2399796.27     13555843.28      2399685.52     13554701.04
#Sta/Elev= 30
  4099.5  408.82  4147.1  406.81  4219.1  401.89  4249.2  401.16  4270.4  399.02
  4291.0  398.67  4321.8  396.53  4352.6  396.14  4393.7  393.52  4476.3  391.07
  4532.9  387.98  4555.9  388.15  4598.2  387.29  4603.4  386.47  4763.6  383.92
  5035.1  383.16  5057.8  383.76  5078.5  381.26  5078.8  380.76  5082.5  381.26
  5114.8  383.47  5206.3  382.70  5242.2  383.62  5322.6  383.16  5508.3  384.26
  5764.5  386.99  5935.4  389.49  6116.3  389.19  6173.9  390.91  6341.3  394.59
#Mann=9,-1,0
  4099.5    0.05       0  4532.9     0.1       0  5078.5    0.05       0
  5082.5     0.1       0  5206.3    0.05       0  5508.3    0.04       0
  5764.5    0.05       0  6173.9    0.04       0  6341.3    0.05       0
Bank Sta=5078.5,5082.5
Exp/Cntr=0.3,0.1

Chan Stop Cuts=-1