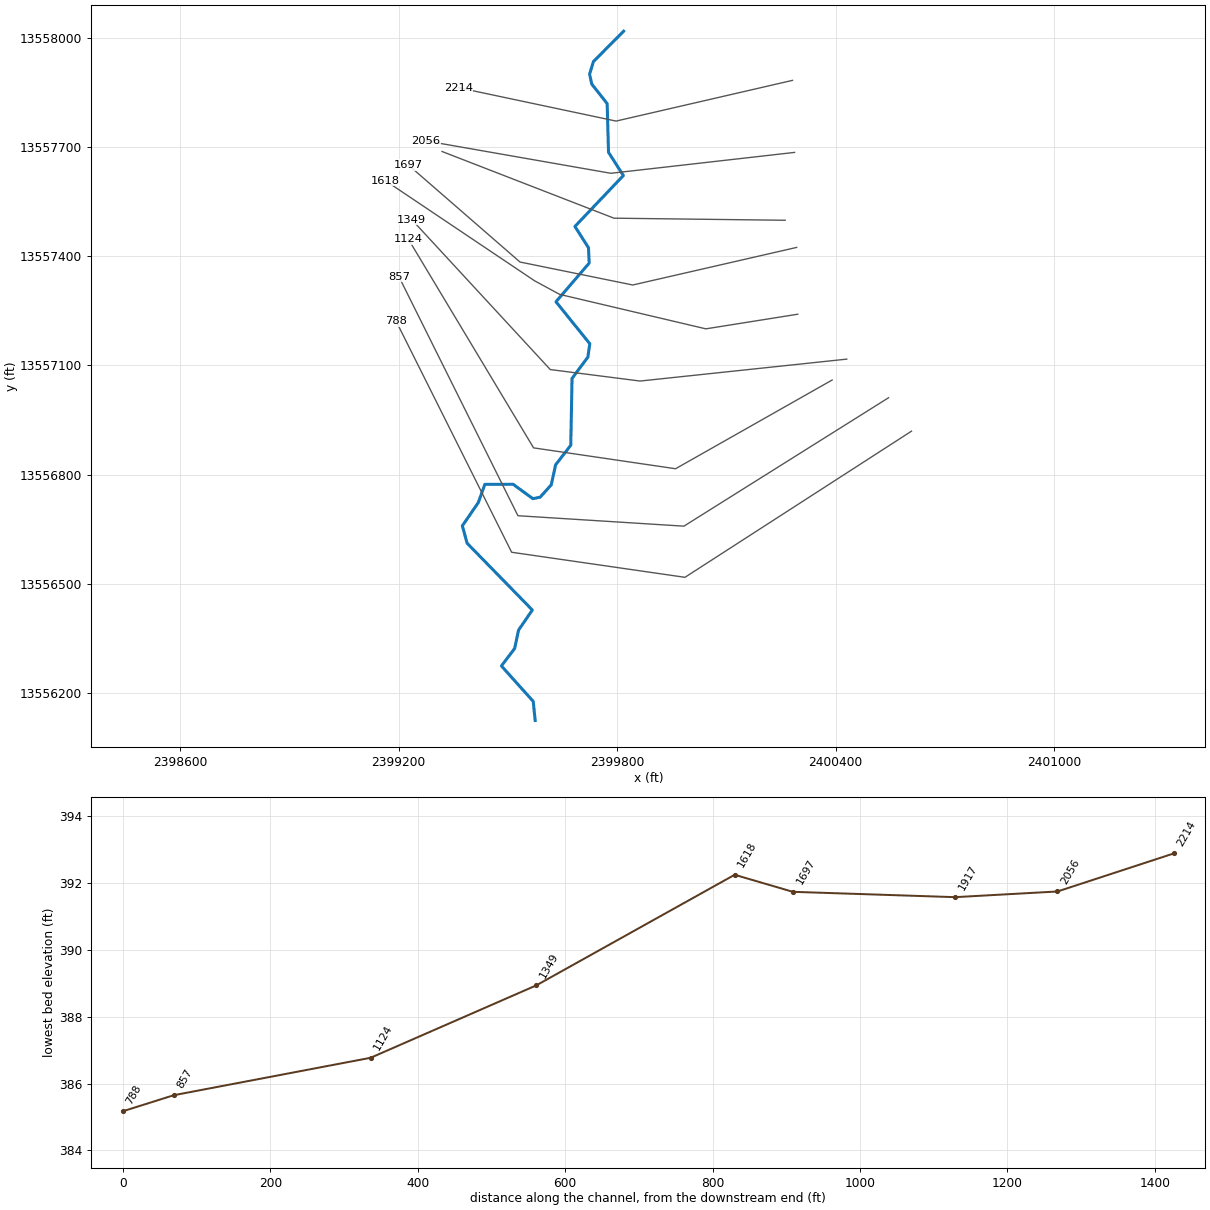
--- TRIB 4_3 TO THOMAS CREEK.prj (project) ---

Proj Title=TRIB 4_3 TO THOMAS CREEK Base Level Engineering
Current Plan=p01
Default Exp/Contr=0.3,0.1
English Units
Geom File=g01
Flow File=f01
Plan File=p01
BEGIN DESCRIPTION:
TRIB 4_3 TO THOMAS CREEK
END DESCRIPTION:

--- TRIB 4_3 TO THOMAS CREEK.p01 (plan) ---

Plan Title=Multiple Run
Short Identifier=Multiple
Geom File=g01
Flow File=f01
Subcritical Flow
K Sum by GR= 0
Std Step Tol= 0.01
Critical Tol= 0.01
Num of Std Step Trials= 20
Max Error Tol= 0.3
Flow Tol Ratio= 0.001
Split Flow NTrial= 30
Split Flow Tol= 0.02
Split Flow Ratio= 0.02
Log Output Level= 0
Friction Slope Method= 1
Unsteady Friction Slope Method= 2
Unsteady Bridges Friction Slope Method= 1
Parabolic Critical Depth
Global Vel Dist=  1 , 1 , 1
Global Log Level= 0
CheckData=True
Encroach Param= -1, 0, 0, 0
BEGIN DESCRIPTION:
Multiple Run
END DESCRIPTION:

--- TRIB 4_3 TO THOMAS CREEK.f01 (steady flow) ---

Flow Title=Multiple
Number of Profiles=7
Profile Names=10-year,25-year,50-year,1pct_min,100-year,1pct_plu,500-year
River Rch & RM= TRIB 4_3 TO THOM,Reach-1,2214
     444     705     937     604    1204    2403    1970
Boundary for River Rch & Prof#=TRIB 4_3 TO THOM,Reach-1,1
Up Type=0
Dn Type=3
Dn Slope=0.005
Boundary for River Rch & Prof#=TRIB 4_3 TO THOM,Reach-1,2
Up Type=0
Dn Type=3
Dn Slope=0.005
Boundary for River Rch & Prof#=TRIB 4_3 TO THOM,Reach-1,3
Up Type=0
Dn Type=3
Dn Slope=0.005
Boundary for River Rch & Prof#=TRIB 4_3 TO THOM,Reach-1,4
Up Type=0
Dn Type=3
Dn Slope=0.005
Boundary for River Rch & Prof#=TRIB 4_3 TO THOM,Reach-1,5
Up Type=0
Dn Type=3
Dn Slope=0.005
Boundary for River Rch & Prof#=TRIB 4_3 TO THOM,Reach-1,6
Up Type=0
Dn Type=3
Dn Slope=0.005
Boundary for River Rch & Prof#=TRIB 4_3 TO THOM,Reach-1,7
Up Type=0
Dn Type=3
Dn Slope=0.005

--- TRIB 4_3 TO THOMAS CREEK.g01 (geometry) ---

Geom Title=Existing Conditions

River Reach=TRIB 4_3 TO THOM,Reach-1
Reach XY= 30
      2399817.95     13558017.95      2399735.04     13557934.72
      2399724.47     13557900.03      2399730.35     13557872.83
      2399772.70     13557819.07      2399776.40     13557685.44
      2399817.20     13557621.58      2399684.15     13557481.73
      2399721.41     13557423.35      2399723.32     13557381.05
      2399632.10     13557275.00      2399725.04     13557159.66
      2399719.65     13557122.83      2399676.24     13557064.50
      2399672.76     13556880.93      2399631.14     13556827.12
      2399619.18     13556772.14      2399588.74     13556738.38
      2399568.62     13556734.23      2399514.42     13556773.77
      2399436.85     13556773.49      2399418.66     13556723.22
      2399375.01     13556659.60      2399388.12     13556611.79
      2399567.23     13556428.41      2399529.40     13556373.35
      2399518.62     13556322.71      2399482.28     13556274.91
      2399569.65     13556177.52      2399575.00     13556125.00

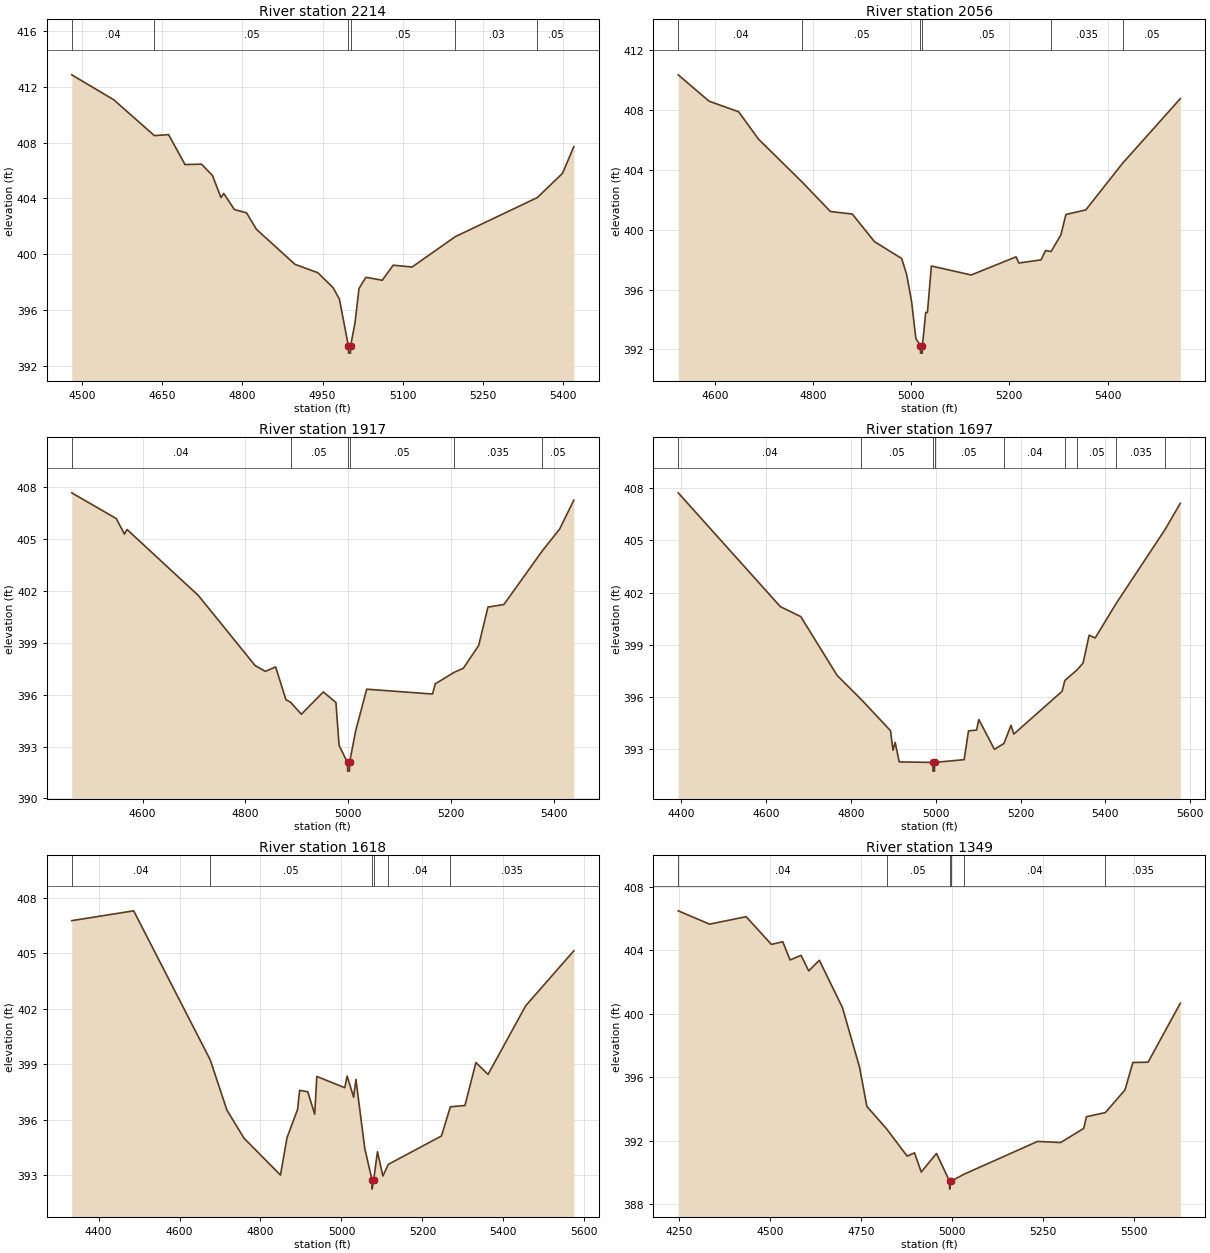
Type RM Length L Ch R = 1,2214,158,158,158
BEGIN DESCRIPTION:
Mapping XS 5c9a1eee
END DESCRIPTION:
XS GIS Cut Line= 3
      2400281.60     13557882.91      2399797.13     13557771.11
      2399364.25     13557862.84
#Sta/Elev= 30
  4480.5  412.86  4559.1  411.07  4635.1  408.50  4661.7  408.57  4692.5  406.42
  4723.3  406.45  4743.8  405.64  4759.8  404.05  4764.9  404.35  4784.9  403.19
  4807.6  402.96  4826.0  401.78  4898.3  399.26  4941.1  398.66  4969.6  397.59
  4981.4  396.77  4998.3  393.39  4998.6  392.89  5002.1  392.89  5002.3  393.39
  5010.6  395.06  5018.1  397.53  5031.0  398.33  5061.7  398.12  5082.1  399.20
  5117.5  399.07  5198.4  401.25  5351.8  404.05  5399.0  405.79  5420.2  407.71
#Mann=6,-1,0
  4480.5    0.04       0  4635.1    0.05       0  4998.3    0.05       0
  5002.3    0.05       0  5198.4    0.03       0  5351.8    0.05       0
Bank Sta=4998.3,5002.3
Exp/Cntr=0.3,0.1

Type RM Length L Ch R = 1,2056,139,139,139
BEGIN DESCRIPTION:
Mapping XS 8e117a18
END DESCRIPTION:
XS GIS Cut Line= 3
      2400287.39     13557685.10      2399782.79     13557627.76
      2399275.36     13557716.63
#Sta/Elev= 30
  4525.3  410.34  4588.1  408.58  4648.5  407.87  4688.7  406.05  4778.3  403.16
  4835.4  401.21  4880.0  401.04  4925.0  399.20  4980.6  398.07  4990.7  397.00
  5000.7  395.21  5009.5  392.72  5018.9  392.25  5019.1  391.75  5022.6  391.75
  5022.9  392.25  5029.5  394.47  5033.1  394.47  5041.1  397.57  5122.3  396.97
  5213.6  398.18  5219.4  397.77  5264.4  397.98  5273.8  398.60  5285.1  398.54
  5305.0  399.65  5315.2  401.01  5355.8  401.32  5430.9  404.44  5548.3  408.75
#Mann=6,-1,0
  4525.3    0.04       0  4778.3    0.05       0  5018.9    0.05       0
  5022.9    0.05       0  5285.1   0.035       0  5430.9    0.05       0
Bank Sta=5018.9,5022.9
Exp/Cntr=0.3,0.1

Type RM Length L Ch R = 1,1917,220,220,220
BEGIN DESCRIPTION:
Mapping XS 0e461085
END DESCRIPTION:
XS GIS Cut Line= 3
      2400261.58     13557498.74      2399791.39     13557504.47
      2399319.19     13557687.63
#Sta/Elev= 30
  4462.3  407.68  4548.9  406.19  4564.8  405.29  4569.8  405.56  4708.9  401.73
  4818.9  397.69  4838.9  397.35  4858.9  397.61  4878.9  395.71  4887.8  395.57
  4908.9  394.87  4951.6  396.16  4976.2  395.55  4982.3  393.07  4998.7  392.08
  4999.0  391.58  5002.5  391.58  5002.7  392.08  5014.5  393.90  5036.0  396.32
  5164.1  396.04  5169.5  396.63  5205.8  397.29  5224.0  397.53  5253.9  398.85
  5271.9  401.07  5303.0  401.22  5377.3  404.31  5411.3  405.58  5439.0  407.26
#Mann=6,-1,0
  4462.3    0.04       0  4887.8    0.05       0  4998.7    0.05       0
  5002.7    0.05       0  5205.8   0.035       0  5377.3    0.05       0
Bank Sta=4998.7,5002.7
Exp/Cntr=0.3,0.1

Type RM Length L Ch R = 1,1697,79,79,79
BEGIN DESCRIPTION:
Mapping XS 8d16dff5
END DESCRIPTION:
XS GIS Cut Line= 4
      2400293.11     13557424.19      2399843.00     13557320.98
      2399533.36     13557384.06      2399227.00     13557650.34
#Sta/Elev= 30
  4392.9  407.73  4633.7  401.19  4681.7  400.62  4767.5  397.24  4824.2  395.86
  4893.5  394.06  4899.2  392.94  4904.3  393.39  4913.9  392.27  4993.2  392.24
  4993.5  391.74  4997.0  391.74  4997.2  392.24  5067.0  392.40  5077.2  394.05
  5096.4  394.10  5101.5  394.71  5138.4  392.99  5160.9  393.33  5177.4  394.37
  5184.1  393.87  5298.0  396.33  5304.4  396.95  5332.9  397.55  5347.4  397.95
  5361.7  399.55  5375.9  399.39  5425.0  401.36  5541.1  405.64  5576.6  407.13
#Mann=9,-1,0
  4392.9    0.04       0  4824.2    0.05       0  4993.2    0.05       0
  4997.2    0.05       0  5160.9    0.04       0  5304.4   0.035       0
  5332.9    0.05       0  5425.0   0.035       0  5541.1    0.05       0
Bank Sta=4993.2,4997.2
Exp/Cntr=0.3,0.1

Type RM Length L Ch R = 1,1618,269,269,269
BEGIN DESCRIPTION:
Mapping XS 154f1d67
END DESCRIPTION:
XS GIS Cut Line= 5
      2400296.04     13557240.72      2400043.69     13557200.57
      2399642.31     13557295.18      2399573.50     13557332.45
      2399163.48     13557607.71
#Sta/Elev= 30
  4333.9  406.76  4486.8  407.29  4675.8  399.24  4717.1  396.52  4759.4  395.00
  4849.3  393.01  4865.5  395.03  4891.6  396.56  4896.7  397.59  4916.8  397.51
  4933.9  396.30  4939.1  398.34  5008.2  397.73  5013.9  398.36  5030.0  397.22
  5035.7  398.18  5057.6  394.44  5075.5  392.75  5075.7  392.25  5079.5  392.75
  5088.9  394.27  5102.3  392.96  5115.8  393.59  5246.9  395.12  5269.0  396.70
  5305.0  396.77  5332.0  399.09  5362.0  398.45  5455.0  402.16  5573.9  405.13
#Mann=6,-1,0
  4333.9    0.04       0  4675.8    0.05       0  5075.5    0.05       0
  5079.5    0.05       0  5115.8    0.04       0  5269.0   0.035       0
Bank Sta=5075.5,5079.5
Exp/Cntr=0.3,0.1

Type RM Length L Ch R = 1,1349,225,225,225
BEGIN DESCRIPTION:
Mapping XS 65d4d11c
END DESCRIPTION:
XS GIS Cut Line= 4
      2400430.73     13557117.42      2399863.07     13557057.22
      2399616.50     13557088.76      2399235.95     13557500.78
#Sta/Elev= 30
  4247.3  406.50  4333.5  405.66  4434.1  406.13  4503.4  404.38  4534.6  404.55
  4554.7  403.40  4584.9  403.69  4606.1  402.71  4635.2  403.38  4698.8  400.39
  4745.8  396.63  4765.9  394.16  4820.6  392.73  4876.7  391.02  4896.9  391.23
  4915.4  390.02  4957.3  391.19  4993.2  389.44  4993.4  388.94  4997.2  389.44
  5033.0  389.88  5235.1  391.95  5298.6  391.88  5362.1  392.77  5369.5  393.51
  5421.6  393.77  5475.5  395.20  5497.1  396.93  5539.0  396.95  5627.6  400.67
#Mann=6,-1,0
  4247.3    0.04       0  4820.6    0.05       0  4993.2    0.05       0
  4997.2    0.05       0  5033.0    0.04       0  5421.6   0.035       0
Bank Sta=4993.2,4997.2
Exp/Cntr=0.3,0.1

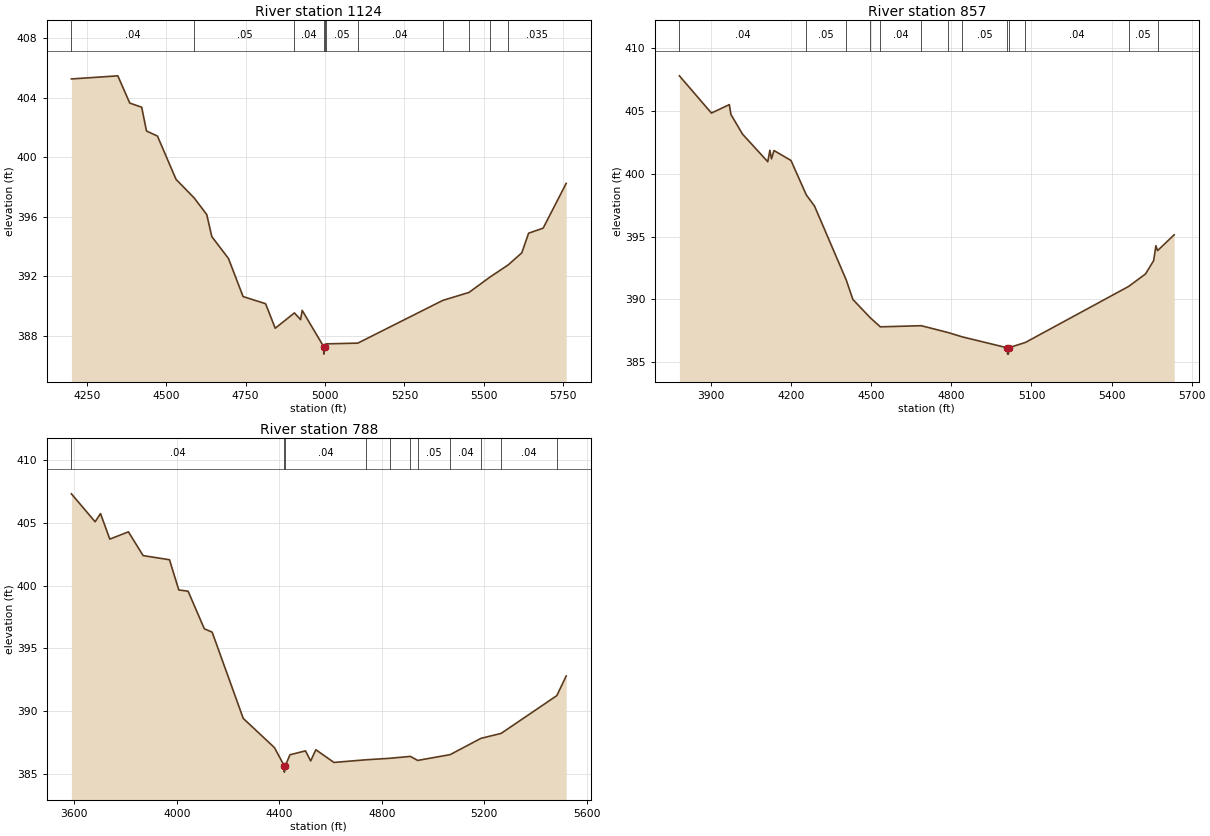
Type RM Length L Ch R = 1,1124,267,267,267
BEGIN DESCRIPTION:
Mapping XS 5d52ecee
END DESCRIPTION:
XS GIS Cut Line= 4
      2400390.58     13557060.07      2399960.55     13556816.39
      2399570.63     13556873.73      2399226.58     13557447.15
#Sta/Elev= 30
  4202.1  405.27  4348.2  405.48  4385.7  403.65  4423.3  403.37  4438.4  401.77
  4472.9  401.43  4531.4  398.52  4588.5  397.27  4628.1  396.15  4644.0  394.67
  4696.4  393.20  4742.4  390.64  4813.2  390.16  4843.5  388.51  4904.0  389.54
  4923.3  389.09  4928.4  389.71  4996.1  387.27  4996.4  386.77  5000.1  387.27
  5003.8  387.46  5103.6  387.51  5370.6  390.38  5453.5  390.92  5518.6  391.94
  5576.8  392.77  5619.5  393.58  5640.9  394.90  5686.7  395.24  5759.2  398.25
#Mann=11,-1,0
  4202.1    0.04       0  4588.5    0.05       0  4904.0    0.04       0
  4996.1    0.04       0  5000.1    0.04       0  5003.8    0.05       0
  5103.6    0.04       0  5370.6    0.05       0  5453.5    0.04       0
  5518.6    0.05       0  5576.8   0.035       0
Bank Sta=4996.1,5000.1
Exp/Cntr=0.3,0.1

Type RM Length L Ch R = 1,857,69,69,69
BEGIN DESCRIPTION:
Mapping XS 8bb15947
END DESCRIPTION:
XS GIS Cut Line= 4
      2400545.41     13557011.34      2399983.48     13556658.70
      2399527.63     13556687.37      2399200.77     13557343.95
#Sta/Elev= 30
  3781.0  407.78  3900.9  404.82  3968.1  405.49  3974.0  404.71  4017.6  403.14
  4112.0  400.95  4120.0  401.86  4126.0  401.18  4135.4  401.84  4199.0  401.05
  4256.5  398.31  4287.3  397.42  4406.2  391.54  4430.8  390.00  4496.6  388.53
  4533.7  387.82  4687.2  387.91  4787.0  387.37  4841.2  387.02  5009.9  386.15
  5010.2  385.65  5013.7  385.65  5013.9  386.15  5077.4  386.58  5463.7  391.03
  5526.9  392.02  5557.6  393.08  5566.1  394.27  5572.2  393.88  5634.6  395.14
#Mann=13,-1,0
  3781.0    0.04       0  4256.5    0.05       0  4406.2    0.04       0
  4496.6    0.05       0  4533.7    0.04       0  4687.2    0.05       0
  4787.0    0.04       0  4841.2    0.05       0  5009.9    0.05       0
  5013.9    0.05       0  5077.4    0.04       0  5463.7    0.05       0
  5572.2   0.035       0
Bank Sta=5009.9,5013.9
Exp/Cntr=0.3,0.1

Type RM Length L Ch R = 1,788,0,0,0
BEGIN DESCRIPTION:
Mapping XS e33ffd2a
END DESCRIPTION:
XS GIS Cut Line= 4
      2400608.51     13556919.61      2399986.35     13556518.22
      2399510.42     13556587.03      2399193.07     13557221.73
#Sta/Elev= 30
  3589.0  407.29  3681.5  405.07  3702.6  405.72  3738.9  403.69  3811.5  404.27
  3868.9  402.38  3971.8  402.05  4008.1  399.65  4044.4  399.55  4107.8  396.56
  4138.2  396.30  4259.6  389.44  4381.3  387.12  4419.7  385.67  4420.0  385.17
  4423.7  385.67  4441.9  386.55  4502.5  386.86  4522.7  386.06  4542.9  386.95
  4613.7  385.94  4738.0  386.15  4831.5  386.27  4911.9  386.42  4940.2  386.10
  5066.9  386.56  5186.7  387.85  5266.1  388.25  5483.3  391.25  5519.9  392.81
#Mann=11,-1,0
  3589.0    0.04       0  4419.7    0.05       0  4423.7    0.04       0
  4738.0    0.03       0  4831.5    0.05       0  4911.9    0.03       0
  4940.2    0.05       0  5066.9    0.04       0  5186.7    0.05       0
  5266.1    0.04       0  5483.3    0.05       0
Bank Sta=4419.7,4423.7
Exp/Cntr=0.3,0.1

Chan Stop Cuts=-1