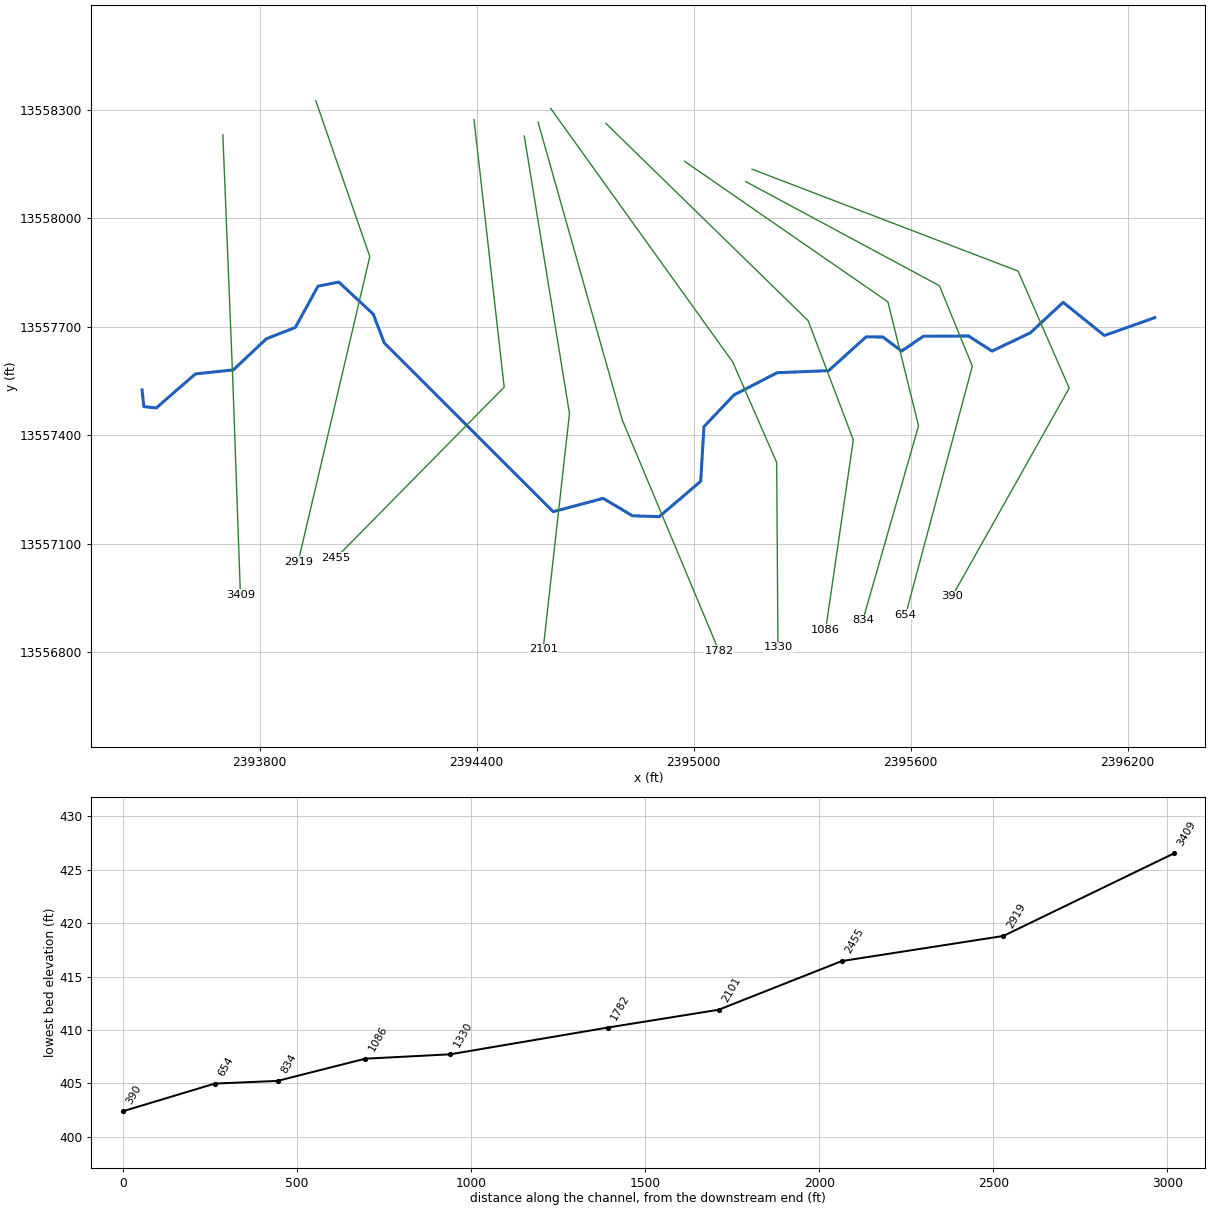
--- TRIB 4_4 TO THOMAS CREEK.prj (project) ---

Proj Title=TRIB 4_4 TO THOMAS CREEK Base Level Engineering
Current Plan=p01
Default Exp/Contr=0.3,0.1
English Units
Geom File=g01
Flow File=f01
Plan File=p01
BEGIN DESCRIPTION:
TRIB 4_4 TO THOMAS CREEK
END DESCRIPTION:

--- TRIB 4_4 TO THOMAS CREEK.p01 (plan) ---

Plan Title=Multiple Run
Short Identifier=Multiple
Geom File=g01
Flow File=f01
Subcritical Flow
K Sum by GR= 0
Std Step Tol= 0.01
Critical Tol= 0.01
Num of Std Step Trials= 20
Max Error Tol= 0.3
Flow Tol Ratio= 0.001
Split Flow NTrial= 30
Split Flow Tol= 0.02
Split Flow Ratio= 0.02
Log Output Level= 0
Friction Slope Method= 1
Unsteady Friction Slope Method= 2
Unsteady Bridges Friction Slope Method= 1
Parabolic Critical Depth
Global Vel Dist=  1 , 1 , 1
Global Log Level= 0
CheckData=True
Encroach Param= -1, 0, 0, 0
BEGIN DESCRIPTION:
Multiple Run
END DESCRIPTION:

--- TRIB 4_4 TO THOMAS CREEK.f01 (steady flow) ---

Flow Title=Multiple
Number of Profiles=7
Profile Names=10-year,25-year,50-year,1pct_min,100-year,1pct_plu,500-year
River Rch & RM= TRIB 4_4 TO THOM,Reach-1,3409
     489     795    1075     706    1408    2810    2394
River Rch & RM= TRIB 4_4 TO THOM,Reach-1,2919
     568     930    1261     830    1656    3305    2831
Boundary for River Rch & Prof#=TRIB 4_4 TO THOM,Reach-1,1
Up Type=0
Dn Type=3
Dn Slope=0.005
Boundary for River Rch & Prof#=TRIB 4_4 TO THOM,Reach-1,2
Up Type=0
Dn Type=3
Dn Slope=0.005
Boundary for River Rch & Prof#=TRIB 4_4 TO THOM,Reach-1,3
Up Type=0
Dn Type=3
Dn Slope=0.005
Boundary for River Rch & Prof#=TRIB 4_4 TO THOM,Reach-1,4
Up Type=0
Dn Type=3
Dn Slope=0.005
Boundary for River Rch & Prof#=TRIB 4_4 TO THOM,Reach-1,5
Up Type=0
Dn Type=3
Dn Slope=0.005
Boundary for River Rch & Prof#=TRIB 4_4 TO THOM,Reach-1,6
Up Type=0
Dn Type=3
Dn Slope=0.005
Boundary for River Rch & Prof#=TRIB 4_4 TO THOM,Reach-1,7
Up Type=0
Dn Type=3
Dn Slope=0.005

--- TRIB 4_4 TO THOMAS CREEK.g01 (geometry) ---

Geom Title=Existing Conditions

River Reach=TRIB 4_4 TO THOM,Reach-1
Reach XY= 30
      2393475.00     13557525.00      2393479.92     13557478.93
      2393514.21     13557475.37      2393622.58     13557569.46
      2393727.42     13557580.54      2393818.98     13557666.81
      2393898.83     13557697.87      2393961.44     13557812.03
      2394018.92     13557823.44      2394114.23     13557734.70
      2394144.79     13557654.91      2394611.62     13557188.53
      2394750.00     13557225.39      2394830.98     13557177.17
      2394904.95     13557174.79      2395019.54     13557272.53
      2395028.54     13557423.54      2395111.76     13557511.39
      2395230.93     13557572.75      2395373.53     13557578.56
      2395476.65     13557671.83      2395523.35     13557671.43
      2395574.99     13557632.59      2395635.44     13557673.63
      2395759.83     13557674.36      2395825.01     13557632.53
      2395931.05     13557683.16      2396021.67     13557767.39
      2396135.61     13557675.58      2396275.00     13557725.00

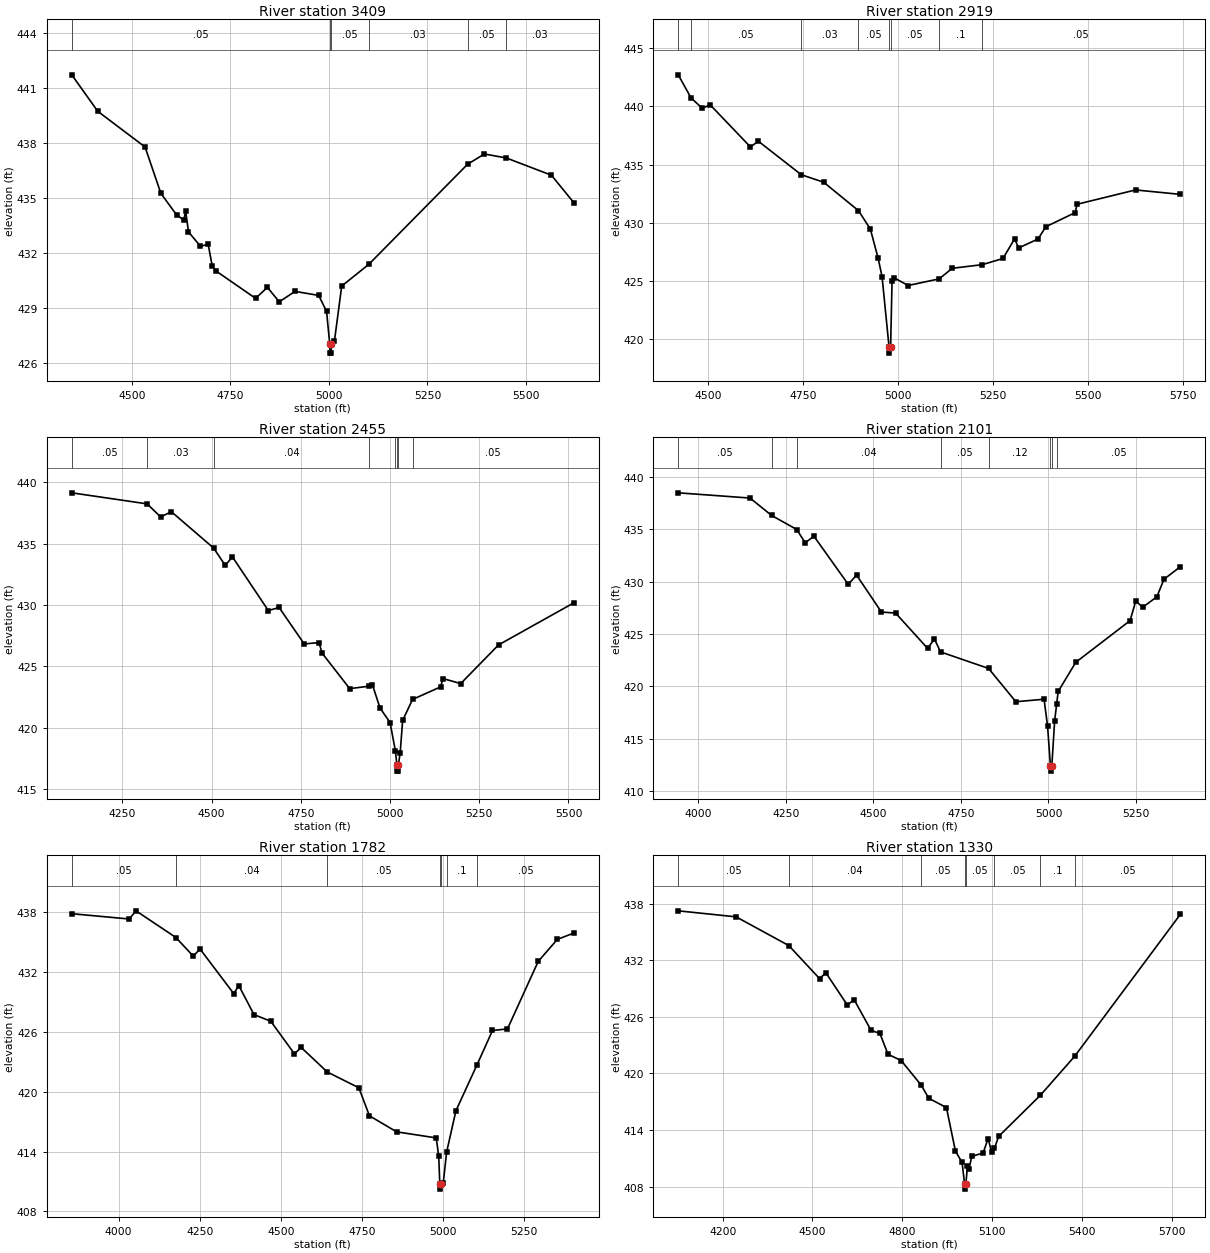
Type RM Length L Ch R = 1,3409,490,490,490
BEGIN DESCRIPTION:
Mapping XS 5b087995
END DESCRIPTION:
XS GIS Cut Line= 3
      2393698.41     13558230.80      2393726.19     13557543.27
      2393746.96     13556958.23
#Sta/Elev= 30
  4347.9  441.73  4413.8  439.74  4533.8  437.79  4573.9  435.26  4613.9  434.08
  4631.9  433.81  4636.9  434.28  4643.9  433.16  4674.0  432.38  4694.0  432.47
  4704.0  431.31  4714.0  431.02  4814.1  429.53  4844.1  430.13  4874.1  429.34
  4914.2  429.91  4974.2  429.69  4994.2  428.82  5002.2  427.04  5002.5  426.54
  5006.0  426.54  5006.2  427.04  5014.2  427.21  5032.6  430.20  5101.5  431.39
  5351.9  436.85  5394.5  437.41  5450.4  437.19  5564.6  436.25  5621.4  434.75
#Mann=6,-1,0
  4347.9    0.05       0  5002.2    0.05       0  5006.2    0.05       0
  5101.5    0.03       0  5351.9    0.05       0  5450.4    0.03       0
Bank Sta=5002.2,5006.2
Exp/Cntr=0.3,0.1

Type RM Length L Ch R = 1,2919,464,464,464
BEGIN DESCRIPTION:
Mapping XS 9795750e
END DESCRIPTION:
XS GIS Cut Line= 3
      2393955.36     13558324.51      2394104.66     13557893.97
      2393906.76     13557050.26
#Sta/Elev= 30
  4421.2  442.72  4454.9  440.74  4484.2  439.85  4505.4  440.14  4611.2  436.53
  4632.4  437.01  4745.2  434.14  4804.3  433.49  4895.9  431.05  4927.2  429.47
  4947.7  426.95  4958.0  425.39  4976.5  419.31  4976.8  418.81  4980.5  419.31
  4984.3  424.98  4989.4  425.29  5026.7  424.62  5108.5  425.19  5142.9  426.10
  5221.9  426.41  5276.4  426.94  5307.2  428.64  5317.5  427.84  5368.9  428.62
  5389.4  429.67  5466.5  430.88  5471.6  431.60  5625.6  432.83  5743.5  432.45
#Mann=8,-1,0
  4421.2    0.04       0  4454.9    0.05       0  4745.2    0.03       0
  4895.9    0.05       0  4976.5    0.05       0  4980.5    0.05       0
  5108.5     0.1       0  5221.9    0.05       0
Bank Sta=4976.5,4980.5
Exp/Cntr=0.3,0.1

Type RM Length L Ch R = 1,2455,354,354,354
BEGIN DESCRIPTION:
Mapping XS e0a09ee0
END DESCRIPTION:
XS GIS Cut Line= 3
      2394392.86     13558272.44      2394476.19     13557532.86
      2394010.91     13557060.63
#Sta/Elev= 30
  4107.9  439.13  4319.1  438.23  4356.9  437.17  4387.1  437.59  4505.5  434.63
  4538.0  433.22  4558.2  433.91  4658.8  429.54  4689.0  429.79  4759.4  426.82
  4800.8  426.93  4809.8  426.06  4886.9  423.18  4941.2  423.38  4950.5  423.50
  4971.7  421.61  5000.0  420.42  5014.8  418.13  5019.2  416.96  5019.4  416.46
  5022.9  416.46  5023.2  416.96  5028.3  417.94  5035.3  420.59  5063.0  422.30
  5141.4  423.32  5148.5  424.00  5198.0  423.59  5304.0  426.74  5515.1  430.17
#Mann=8,-1,0
  4107.9    0.05       0  4319.1    0.03       0  4505.5    0.04       0
  4941.2    0.05       0  5014.8    0.12       0  5019.2    0.05       0
  5023.2    0.12       0  5063.0    0.05       0
Bank Sta=5019.2,5023.2
Exp/Cntr=0.3,0.1

Type RM Length L Ch R = 1,2101,319,319,319
BEGIN DESCRIPTION:
Mapping XS 55dd3b75
END DESCRIPTION:
XS GIS Cut Line= 3
      2394531.74     13558227.32      2394656.75     13557459.94
      2394583.99     13556808.59
#Sta/Elev= 30
  3943.3  438.49  4148.3  437.99  4209.7  436.33  4281.8  434.98  4305.5  433.72
  4330.7  434.34  4428.5  429.74  4452.2  430.63  4523.2  427.10  4563.7  427.00
  4654.9  423.63  4674.5  424.53  4691.9  423.29  4829.0  421.71  4906.9  418.53
  4987.4  418.77  4997.4  416.19  5005.5  412.40  5005.8  411.90  5009.5  412.40
  5017.6  416.72  5023.4  418.34  5027.6  419.51  5077.9  422.30  5232.9  426.28
  5249.0  428.15  5269.1  427.56  5309.4  428.56  5329.5  430.23  5376.2  431.43
#Mann=8,-1,0
  3943.3    0.05       0  4209.7    0.03       0  4281.8    0.04       0
  4691.9    0.05       0  4829.0    0.12       0  5005.5    0.05       0
  5009.5    0.12       0  5023.4    0.05       0
Bank Sta=5005.5,5009.5
Exp/Cntr=0.3,0.1

Type RM Length L Ch R = 1,1782,452,452,452
BEGIN DESCRIPTION:
Mapping XS 21d28616
END DESCRIPTION:
XS GIS Cut Line= 3
      2394569.93     13558265.52      2394802.58     13557442.58
      2395069.95     13556803.66
#Sta/Elev= 30
  3855.7  437.87  4032.9  437.34  4053.7  438.16  4176.8  435.48  4230.3  433.61
  4251.1  434.33  4355.0  429.85  4370.6  430.66  4417.4  427.75  4469.4  427.07
  4542.1  423.81  4562.9  424.45  4643.6  421.98  4740.8  420.40  4773.3  417.59
  4857.1  415.98  4979.3  415.37  4986.9  413.54  4990.3  410.73  4990.6  410.23
  4994.3  410.73  5001.0  410.88  5011.4  413.96  5039.9  418.09  5104.8  422.69
  5152.7  426.15  5198.9  426.31  5293.6  433.08  5352.5  435.29  5403.5  435.93
#Mann=7,-1,0
  3855.7    0.05       0  4176.8    0.04       0  4643.6    0.05       0
  4990.3    0.05       0  4994.3    0.05       0  5011.4     0.1       0
  5104.8    0.05       0
Bank Sta=4990.3,4994.3
Exp/Cntr=0.3,0.1

Type RM Length L Ch R = 1,1330,244,244,244
BEGIN DESCRIPTION:
Mapping XS e58362a7
END DESCRIPTION:
XS GIS Cut Line= 4
      2394604.68     13558303.67      2395108.13     13557602.30
      2395229.66     13557324.52      2395233.13     13556814.09
#Sta/Elev= 30
  4051.6  437.26  4245.1  436.62  4421.1  433.57  4523.8  430.06  4544.7  430.69
  4616.2  427.27  4639.2  427.83  4695.7  424.57  4725.2  424.25  4752.2  422.04
  4796.4  421.37  4863.0  418.77  4888.5  417.37  4947.4  416.38  4977.5  411.76
  4999.6  410.57  5008.2  408.23  5008.5  407.73  5012.2  408.23  5017.6  410.18
  5023.0  409.91  5032.1  411.21  5069.8  411.56  5086.7  413.10  5098.6  411.62
  5107.7  412.07  5122.0  413.33  5260.9  417.68  5375.9  421.83  5728.6  436.88
#Mann=8,-1,0
  4051.6    0.05       0  4421.1    0.04       0  4863.0    0.05       0
  5008.2    0.05       0  5012.2    0.05       0  5107.7    0.05       0
  5260.9     0.1       0  5375.9    0.05       0
Bank Sta=5008.2,5012.2
Exp/Cntr=0.3,0.1

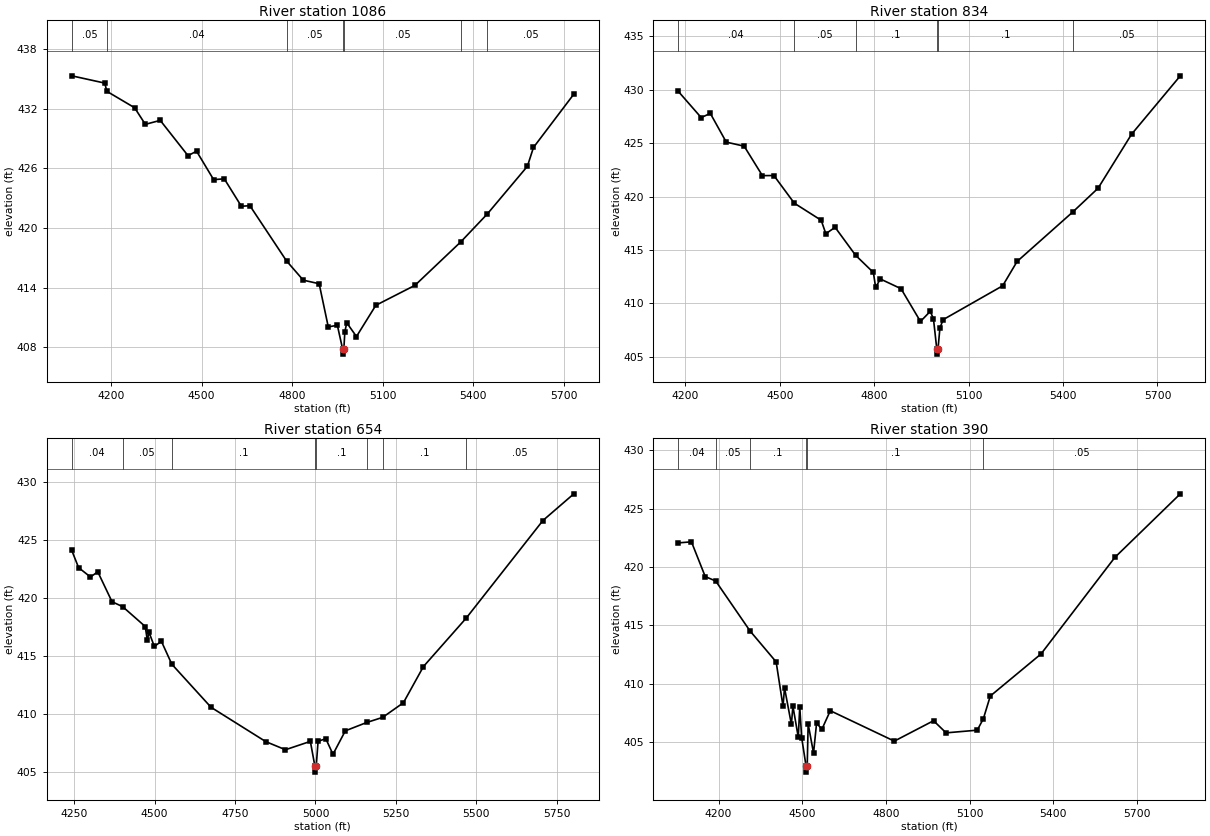
Type RM Length L Ch R = 1,1086,252,252,252
BEGIN DESCRIPTION:
Mapping XS 770afe3e
END DESCRIPTION:
XS GIS Cut Line= 4
      2394757.47     13558262.00      2395316.47     13557716.88
      2395441.47     13557387.02      2395365.08     13556862.70
#Sta/Elev= 30
  4069.8  435.31  4179.0  434.58  4186.1  433.75  4278.0  432.10  4313.5  430.43
  4362.9  430.83  4454.9  427.28  4483.2  427.73  4539.8  424.87  4575.1  424.95
  4631.7  422.19  4659.9  422.25  4781.4  416.69  4836.7  414.76  4889.4  414.40
  4919.6  410.06  4949.7  410.22  4967.2  407.82  4967.4  407.32  4971.2  407.82
  4974.5  409.57  4980.9  410.47  5013.0  409.09  5077.2  412.23  5206.9  414.24
  5359.0  418.62  5446.9  421.43  5579.3  426.21  5599.5  428.11  5733.2  433.47
#Mann=7,-1,0
  4069.8    0.05       0  4186.1    0.04       0  4781.4    0.05       0
  4967.2    0.05       0  4971.2    0.05       0  5359.0     0.1       0
  5446.9    0.05       0
Bank Sta=4967.2,4971.2
Exp/Cntr=0.3,0.1

Type RM Length L Ch R = 1,834,180,180,180
BEGIN DESCRIPTION:
Mapping XS e37bbb57
END DESCRIPTION:
XS GIS Cut Line= 4
      2394975.04     13558157.17      2395537.14     13557768.69
      2395621.77     13557425.81      2395468.04     13556888.84
#Sta/Elev= 30
  4177.6  429.86  4250.5  427.40  4279.5  427.79  4330.2  425.10  4387.0  424.72
  4445.0  421.96  4481.5  421.97  4546.3  419.38  4631.7  417.78  4646.5  416.52
  4675.9  417.12  4741.0  414.50  4797.5  412.89  4804.7  411.49  4819.6  412.28
  4885.3  411.37  4947.1  408.30  4978.0  409.24  4988.3  408.57  4998.9  405.74
  4999.1  405.24  5002.9  405.74  5008.9  407.69  5019.2  408.47  5208.2  411.64
  5254.1  413.92  5431.9  418.58  5511.3  420.78  5617.8  425.84  5772.6  431.31
#Mann=6,-1,0
  4177.6    0.04       0  4546.3    0.05       0  4741.0     0.1       0
  4998.9    0.05       0  5002.9     0.1       0  5431.9    0.05       0
Bank Sta=4998.9,5002.9
Exp/Cntr=0.3,0.1

Type RM Length L Ch R = 1,654,264,264,264
BEGIN DESCRIPTION:
Mapping XS 8e84383a
END DESCRIPTION:
XS GIS Cut Line= 4
      2395143.82     13558101.39      2395679.61     13557813.27
      2395770.59     13557590.88      2395586.09     13556903.44
#Sta/Elev= 30
  4242.7  424.10  4263.9  422.62  4300.8  421.81  4323.5  422.26  4367.8  419.68
  4401.0  419.25  4471.1  417.54  4477.3  416.38  4483.0  417.03  4499.3  415.82
  4521.2  416.27  4553.7  414.29  4675.5  410.58  4845.6  407.62  4906.8  406.92
  4984.2  407.64  4998.4  405.49  4998.7  404.99  5002.4  405.49  5008.2  407.65
  5032.2  407.87  5054.5  406.53  5092.9  408.55  5159.4  409.27  5208.9  409.71
  5273.4  410.97  5335.6  414.09  5468.7  418.27  5707.0  426.68  5803.1  428.98
#Mann=8,-1,0
  4242.7    0.04       0  4401.0    0.05       0  4553.7     0.1       0
  4998.4    0.05       0  5002.4     0.1       0  5159.4    0.05       0
  5208.9     0.1       0  5468.7    0.05       0
Bank Sta=4998.4,5002.4
Exp/Cntr=0.3,0.1

Type RM Length L Ch R = 1,390,0,0,0
BEGIN DESCRIPTION:
TRIB 4_4 TO THOMAS CREEK 1.0
END DESCRIPTION:
XS GIS Cut Line= 4
      2395161.70     13558135.45      2395896.95     13557853.71
      2396038.48     13557530.22      2395715.07     13556954.86
#Sta/Elev= 30
  4055.4  422.07  4102.8  422.16  4152.2  419.18  4189.7  418.80  4312.7  414.52
  4406.5  411.86  4431.2  408.04  4436.5  409.64  4461.2  406.50  4466.6  408.07
  4485.9  405.39  4491.2  408.01  4498.0  405.37  4513.9  402.90  4514.2  402.40
  4517.9  402.90  4521.3  406.54  4540.6  404.03  4551.5  406.60  4570.6  406.08
  4600.7  407.67  4830.3  405.06  4971.0  406.81  5016.0  405.77  5127.7  406.00
  5149.6  406.98  5174.5  408.93  5356.4  412.54  5621.0  420.82  5855.9  426.28
#Mann=6,-1,0
  4055.4    0.04       0  4189.7    0.05       0  4312.7     0.1       0
  4513.9    0.05       0  4517.9     0.1       0  5149.6    0.05       0
Bank Sta=4513.9,4517.9
Exp/Cntr=0.3,0.1

Chan Stop Cuts=-1