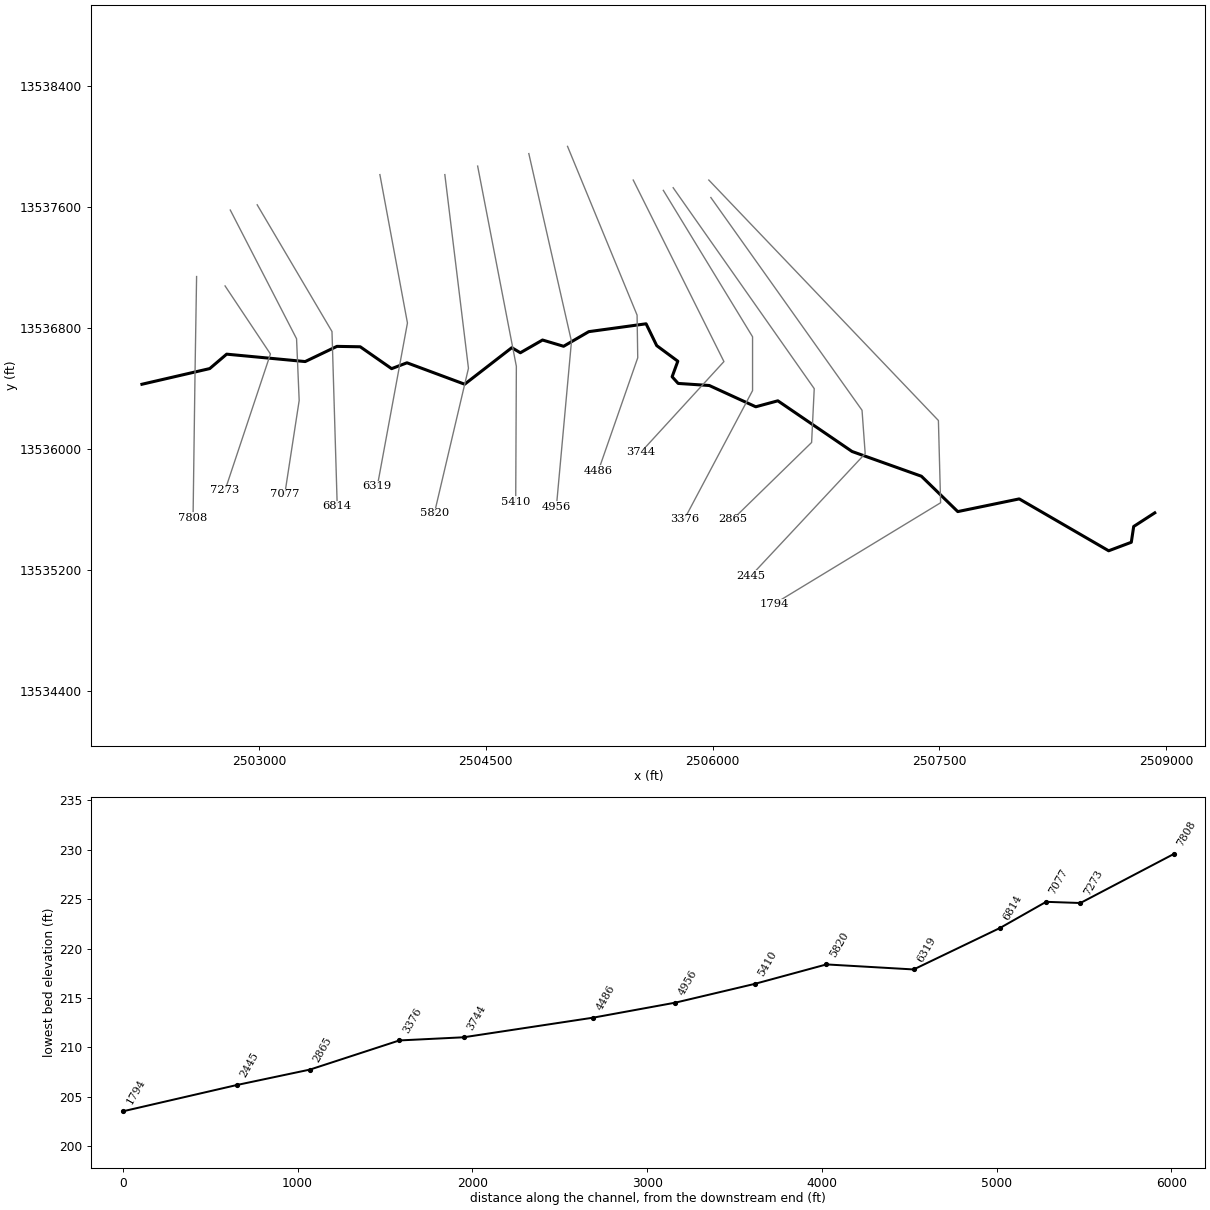
--- TRIB 5 TO BOGGY BRANCH.prj (project) ---

Proj Title=TRIB 5 TO BOGGY BRANCH Base Level Engineering
Current Plan=p01
Default Exp/Contr=0.3,0.1
English Units
Geom File=g01
Flow File=f01
Plan File=p01
BEGIN DESCRIPTION:
TRIB 5 TO BOGGY BRANCH
END DESCRIPTION:

--- TRIB 5 TO BOGGY BRANCH.p01 (plan) ---

Plan Title=Multiple Run
Short Identifier=Multiple
Geom File=g01
Flow File=f01
Subcritical Flow
K Sum by GR= 0
Std Step Tol= 0.01
Critical Tol= 0.01
Num of Std Step Trials= 20
Max Error Tol= 0.3
Flow Tol Ratio= 0.001
Split Flow NTrial= 30
Split Flow Tol= 0.02
Split Flow Ratio= 0.02
Log Output Level= 0
Friction Slope Method= 1
Unsteady Friction Slope Method= 2
Unsteady Bridges Friction Slope Method= 1
Parabolic Critical Depth
Global Vel Dist=  1 , 1 , 1
Global Log Level= 0
CheckData=True
Encroach Param= -1, 0, 0, 0
BEGIN DESCRIPTION:
Multiple Run
END DESCRIPTION:

--- TRIB 5 TO BOGGY BRANCH.f01 (steady flow) ---

Flow Title=Multiple
Number of Profiles=7
Profile Names=10-year,25-year,50-year,1pct_min,100-year,1pct_plu,500-year
River Rch & RM= TRIB 5 TO BOGGY ,Reach-1,7808
     862    1421    1936    1278    2549    5087    4372
River Rch & RM= TRIB 5 TO BOGGY ,Reach-1,5820
    1004    1662    2270    1500    2993    5972    5149
River Rch & RM= TRIB 5 TO BOGGY ,Reach-1,1794
    1152    1918    2631    1744    3480    6944    6029
Boundary for River Rch & Prof#=TRIB 5 TO BOGGY ,Reach-1,1
Up Type=0
Dn Type=3
Dn Slope=0.005
Boundary for River Rch & Prof#=TRIB 5 TO BOGGY ,Reach-1,2
Up Type=0
Dn Type=3
Dn Slope=0.005
Boundary for River Rch & Prof#=TRIB 5 TO BOGGY ,Reach-1,3
Up Type=0
Dn Type=3
Dn Slope=0.005
Boundary for River Rch & Prof#=TRIB 5 TO BOGGY ,Reach-1,4
Up Type=0
Dn Type=3
Dn Slope=0.005
Boundary for River Rch & Prof#=TRIB 5 TO BOGGY ,Reach-1,5
Up Type=0
Dn Type=3
Dn Slope=0.005
Boundary for River Rch & Prof#=TRIB 5 TO BOGGY ,Reach-1,6
Up Type=0
Dn Type=3
Dn Slope=0.005
Boundary for River Rch & Prof#=TRIB 5 TO BOGGY ,Reach-1,7
Up Type=0
Dn Type=3
Dn Slope=0.005

--- TRIB 5 TO BOGGY BRANCH.g01 (geometry) ---

Geom Title=Existing Conditions

River Reach=TRIB 5 TO BOGGY ,Reach-1
Reach XY= 30
      2502225.00     13536425.00      2502673.50     13536528.62
      2502785.44     13536623.94      2503304.97     13536575.06
      2503514.81     13536675.46      2503669.07     13536672.76
      2503876.65     13536528.17      2503978.29     13536566.89
      2504359.78     13536425.24      2504671.77     13536666.76
      2504728.23     13536633.24      2504874.99     13536717.47
      2505014.45     13536676.09      2505180.93     13536772.76
      2505559.97     13536824.69      2505630.26     13536680.48
      2505769.89     13536577.30      2505732.25     13536474.67
      2505772.02     13536430.51      2505978.23     13536416.76
      2506285.55     13536276.11      2506431.62     13536315.59
      2506922.58     13535980.54      2507381.34     13535816.98
      2507621.77     13535583.24      2508028.40     13535667.17
      2508619.97     13535324.19      2508769.75     13535380.44
      2508785.51     13535484.77      2508925.00     13535575.00

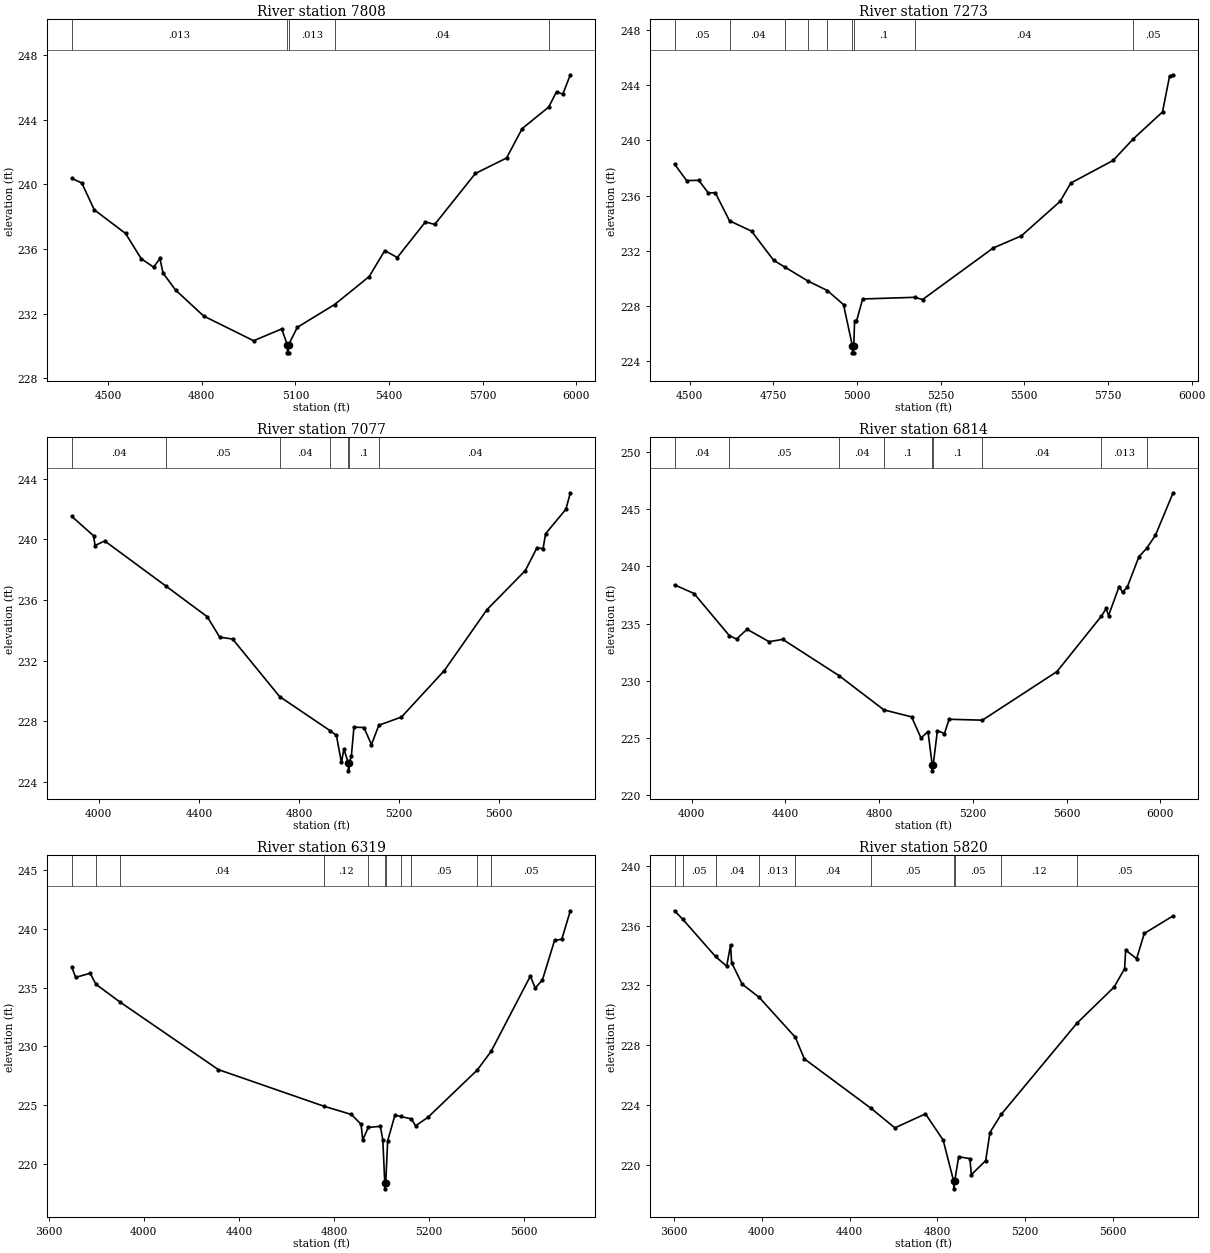
Type RM Length L Ch R = 1,7808,535,535,535
BEGIN DESCRIPTION:
TRIB 5 TO BOGGY BRANCH 11.0
END DESCRIPTION:
XS GIS Cut Line= 3
      2502586.59     13537137.14      2502576.56     13536521.24
      2502563.16     13535540.81
#Sta/Elev= 30
  4383.9  240.38  4416.0  240.09  4456.0  238.43  4556.1  236.97  4606.1  235.41
  4646.1  234.88  4666.1  235.42  4676.1  234.52  4716.1  233.47  4806.1  231.86
  4966.1  230.33  5056.1  231.06  5074.1  230.08  5074.4  229.58  5077.9  229.58
  5078.1  230.08  5106.1  231.16  5225.6  232.57  5336.2  234.30  5386.2  235.91
  5426.2  235.48  5516.2  237.68  5546.2  237.53  5676.2  240.68  5776.2  241.64
  5826.2  243.46  5911.0  244.79  5936.2  245.74  5956.2  245.59  5980.4  246.79
#Mann=5,-1,0
  4383.9   0.013       0  5074.1    0.03       0  5078.1   0.013       0
  5225.6    0.04       0  5911.0    0.05       0
Bank Sta=5074.1,5078.1
Exp/Cntr=0.3,0.1

Type RM Length L Ch R = 1,7273,196,196,196
BEGIN DESCRIPTION:
TRIB 5 TO BOGGY BRANCH 10.0
END DESCRIPTION:
XS GIS Cut Line= 3
      2502774.98     13537075.04      2503075.00     13536625.00
      2502774.99     13535724.96
#Sta/Elev= 30
  4455.0  238.27  4491.1  237.08  4527.2  237.10  4555.7  236.19  4576.7  236.20
  4619.2  234.17  4684.9  233.42  4751.0  231.31  4786.3  230.79  4853.6  229.81
  4911.5  229.12  4959.8  228.10  4986.4  225.11  4986.6  224.61  4990.1  224.61
  4990.4  225.11  4992.9  226.89  4998.5  226.89  5017.0  228.51  5172.0  228.63
  5196.2  228.47  5407.0  232.20  5491.3  233.08  5607.2  235.58  5638.9  236.90
  5765.4  238.54  5825.2  240.09  5912.9  242.05  5934.0  244.64  5944.6  244.74
#Mann=9,-1,0
  4455.0    0.05       0  4619.2    0.04       0  4786.3    0.05       0
  4853.6    0.04       0  4911.5     0.1       0  4986.4    0.05       0
  4990.4     0.1       0  5172.0    0.04       0  5825.2    0.05       0
Bank Sta=4986.4,4990.4
Exp/Cntr=0.3,0.1

Type RM Length L Ch R = 1,7077,263,263,263
BEGIN DESCRIPTION:
Mapping XS 880781d5
END DESCRIPTION:
XS GIS Cut Line= 4
      2502809.46     13537576.60      2503247.84     13536725.89
      2503265.20     13536317.90      2503169.72     13535697.27
#Sta/Elev= 30
  3891.7  241.52  3979.0  240.24  3984.7  239.60  4023.4  239.90  4267.6  236.93
  4433.3  234.90  4483.2  233.55  4534.7  233.43  4722.7  229.63  4924.5  227.38
  4949.7  227.07  4969.7  225.29  4979.7  226.16  4997.7  225.23  4998.0  224.73
  5001.7  225.23  5009.7  225.74  5019.8  227.61  5059.8  227.59  5089.8  226.46
  5119.3  227.74  5209.9  228.28  5381.4  231.35  5551.3  235.36  5705.2  237.95
  5751.2  239.44  5776.0  239.40  5786.1  240.38  5867.1  241.99  5885.0  243.08
#Mann=7,-1,0
  3891.7    0.04       0  4267.6    0.05       0  4722.7    0.04       0
  4924.5     0.1       0  4997.7    0.05       0  5001.7     0.1       0
  5119.3    0.04       0
Bank Sta=4997.7,5001.7
Exp/Cntr=0.3,0.1

Type RM Length L Ch R = 1,6814,495,495,495
BEGIN DESCRIPTION:
Mapping XS 02abee27
END DESCRIPTION:
XS GIS Cut Line= 3
      2502987.43     13537611.28      2503482.21     13536773.63
      2503516.92     13535619.51
#Sta/Elev= 30
  3927.2  238.39  4010.4  237.63  4160.5  233.95  4191.8  233.64  4236.5  234.50
  4330.3  233.41  4388.9  233.61  4628.5  230.44  4820.8  227.43  4938.7  226.82
  4978.7  224.97  5008.7  225.53  5026.8  222.59  5027.0  222.09  5030.8  222.59
  5048.8  225.61  5078.8  225.36  5098.8  226.61  5240.8  226.53  5559.0  230.79
  5748.6  235.65  5769.1  236.32  5779.1  235.70  5824.3  238.24  5839.1  237.74
  5859.1  238.20  5909.1  240.87  5941.4  241.58  5979.2  242.73  6054.7  246.46
#Mann=9,-1,0
  3927.2    0.04       0  4160.5    0.05       0  4628.5    0.04       0
  4820.8     0.1       0  5026.8    0.05       0  5030.8     0.1       0
  5240.8    0.04       0  5748.6   0.013       0  5941.4    0.04       0
Bank Sta=5026.8,5030.8
Exp/Cntr=0.3,0.1

Type RM Length L Ch R = 1,6319,499,499,499
BEGIN DESCRIPTION:
Mapping XS aaf3b191
END DESCRIPTION:
XS GIS Cut Line= 3
      2503799.06     13537810.93      2503981.34     13536830.06
      2503781.76     13535749.70
#Sta/Elev= 30
  3697.1  236.76  3713.3  235.88  3774.3  236.23  3798.9  235.29  3898.6  233.80
  4313.4  228.03  4757.7  224.91  4872.8  224.21  4913.5  223.38  4920.4  222.05
  4944.0  223.11  4994.8  223.20  5005.0  222.03  5013.2  218.38  5013.4  217.88
  5017.2  218.38  5025.3  221.96  5055.8  224.15  5080.2  224.04  5125.4  223.83
  5142.4  223.24  5195.3  223.98  5401.9  227.99  5460.2  229.58  5625.3  235.99
  5645.6  234.97  5676.1  235.67  5727.0  239.02  5757.5  239.13  5793.4  241.55
#Mann=11,-1,0
  3697.1    0.12       0  3798.9   0.013       0  3898.6    0.04       0
  4757.7    0.12       0  4944.0    0.05       0  5013.2    0.05       0
  5017.2    0.05       0  5080.2    0.12       0  5125.4    0.05       0
  5401.9    0.12       0  5460.2    0.05       0
Bank Sta=5013.2,5017.2
Exp/Cntr=0.3,0.1

Type RM Length L Ch R = 1,5820,410,410,410
BEGIN DESCRIPTION:
Mapping XS df10e3fb
END DESCRIPTION:
XS GIS Cut Line= 3
      2504228.74     13537810.93      2504384.99     13536530.58
      2504159.65     13535572.88
#Sta/Elev= 30
  3602.0  237.00  3639.4  236.43  3788.7  233.94  3839.7  233.29  3857.4  234.72
  3862.4  233.52  3910.2  232.09  3987.7  231.21  4152.9  228.53  4193.8  227.09
  4498.0  223.78  4606.7  222.47  4746.4  223.41  4826.9  221.65  4875.2  218.89
  4875.5  218.39  4879.5  218.89  4897.6  220.54  4948.9  220.41  4955.7  219.34
  5020.9  220.28  5040.4  222.16  5091.5  223.37  5437.9  229.49  5606.4  231.89
  5654.3  233.12  5659.4  234.37  5709.2  233.79  5744.1  235.48  5875.7  236.66
#Mann=10,-1,0
  3602.0    0.04       0  3639.4    0.05       0  3788.7    0.04       0
  3987.7   0.013       0  4152.9    0.04       0  4498.0    0.05       0
  4875.2    0.05       0  4879.5    0.05       0  5091.5    0.12       0
  5437.9    0.05       0
Bank Sta=4875.2,4879.5
Exp/Cntr=0.3,0.1

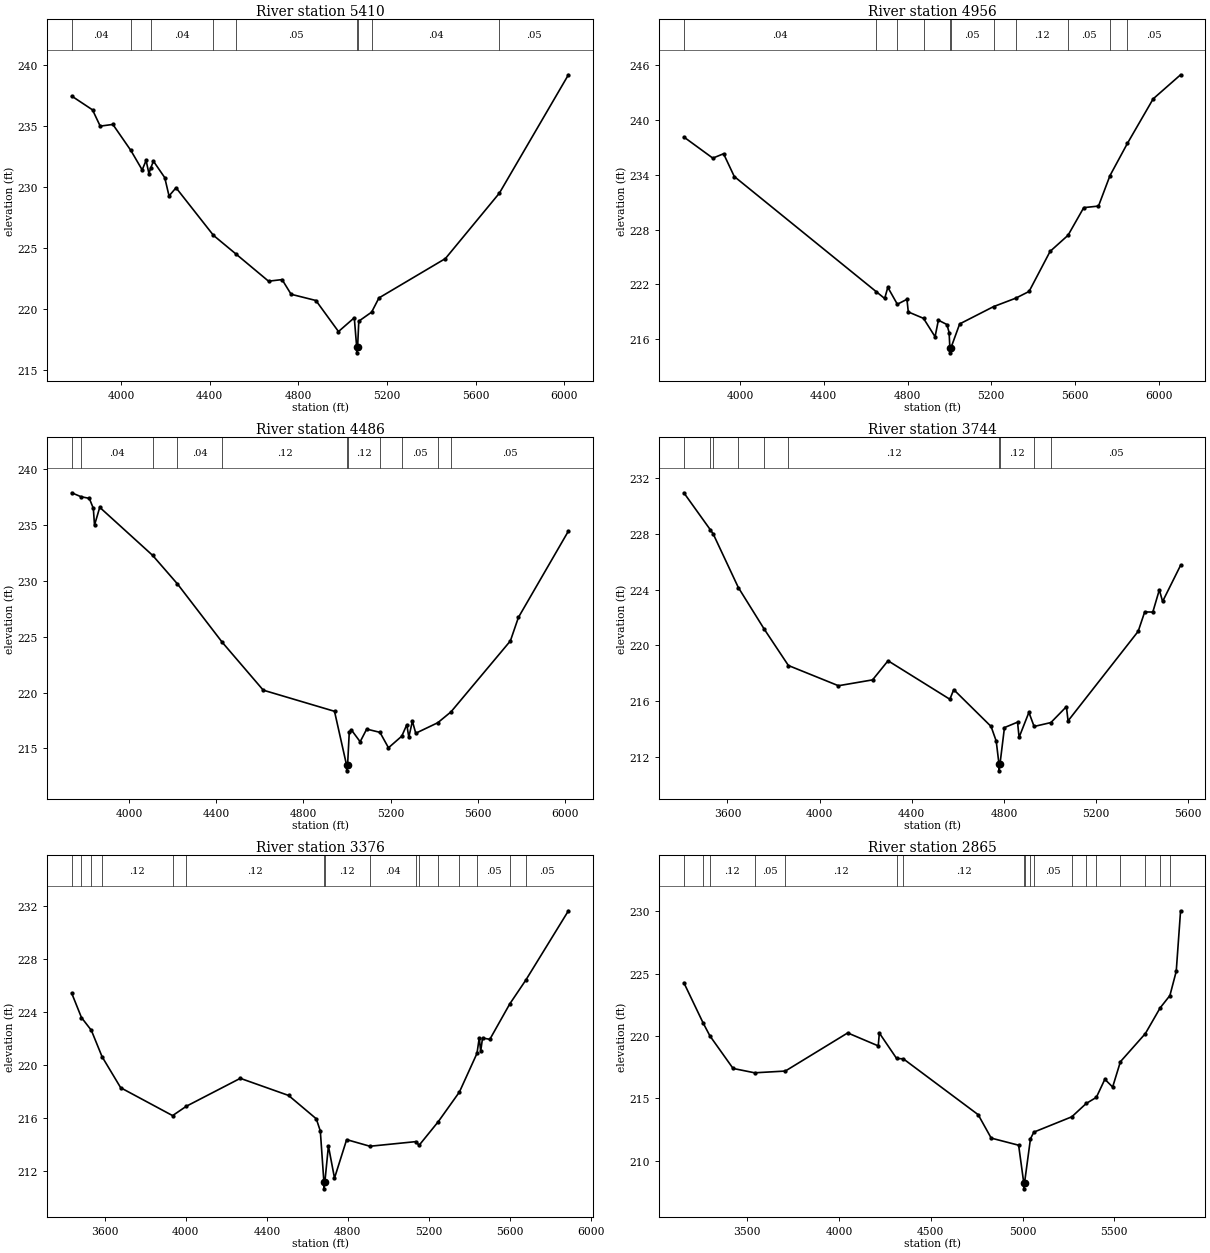
Type RM Length L Ch R = 1,5410,454,454,454
BEGIN DESCRIPTION:
Mapping XS 9f02fd53
END DESCRIPTION:
XS GIS Cut Line= 3
      2504445.75     13537867.38      2504701.83     13536543.60
      2504697.49     13535649.73
#Sta/Elev= 30
  3777.1  237.42  3871.2  236.29  3905.8  234.96  3962.9  235.10  4044.2  232.97
  4095.3  231.38  4113.0  232.16  4125.8  231.07  4133.4  231.52  4146.2  232.09
  4197.1  230.75  4216.5  229.25  4248.1  229.92  4416.9  226.03  4516.8  224.53
  4665.7  222.28  4726.8  222.41  4767.5  221.21  4879.5  220.70  4981.4  218.16
  5052.7  219.29  5063.4  216.92  5063.7  216.42  5067.7  216.92  5073.1  219.01
  5131.0  219.75  5164.0  220.91  5464.0  224.13  5707.6  229.48  6019.3  239.16
#Mann=9,-1,0
  3777.1    0.04       0  4044.2   0.013       0  4133.4    0.04       0
  4416.9   0.013       0  4516.8    0.05       0  5063.4    0.05       0
  5067.7    0.05       0  5131.0    0.04       0  5707.6    0.05       0
Bank Sta=5063.4,5067.7
Exp/Cntr=0.3,0.1

Type RM Length L Ch R = 1,4956,470,470,470
BEGIN DESCRIPTION:
Mapping XS 2cbdae5b
END DESCRIPTION:
XS GIS Cut Line= 3
      2504784.29     13537949.84      2505066.41     13536708.53
      2504966.58     13535614.74
#Sta/Elev= 30
  3732.3  238.11  3870.6  235.80  3921.9  236.28  3973.1  233.79  4651.0  221.20
  4691.0  220.46  4706.0  221.68  4751.5  219.83  4797.3  220.37  4803.8  218.99
  4876.4  218.29  4931.6  216.28  4947.4  218.09  4988.4  217.61  4998.6  216.74
  5002.3  215.02  5002.6  214.52  5006.7  215.02  5049.0  217.68  5210.6  219.57
  5317.3  220.50  5380.4  221.23  5480.8  225.61  5566.4  227.37  5641.4  230.39
  5711.7  230.56  5766.6  233.89  5849.5  237.40  5972.8  242.28  6103.6  244.91
#Mann=11,-1,0
  3732.3    0.04       0  4651.0   0.013       0  4751.5    0.04       0
  4876.4    0.05       0  5002.3    0.05       0  5006.7    0.05       0
  5210.6    0.04       0  5317.3    0.12       0  5566.4    0.05       0
  5766.6    0.04       0  5849.5    0.05       0
Bank Sta=5002.3,5006.7
Exp/Cntr=0.3,0.1

Type RM Length L Ch R = 1,4486,742,742,742
BEGIN DESCRIPTION:
Mapping XS 5f5bb940
END DESCRIPTION:
XS GIS Cut Line= 4
      2505040.38     13537997.56      2505500.44     13536882.14
      2505504.78     13536600.02      2505244.35     13535853.47
#Sta/Elev= 30
  3736.7  237.85  3779.2  237.50  3817.5  237.35  3836.0  236.46  3841.4  234.96
  3865.4  236.55  4107.9  232.26  4222.2  229.70  4427.9  224.48  4615.7  220.21
  4942.7  218.32  4998.2  213.50  4998.5  213.00  5002.7  213.50  5010.4  216.44
  5020.4  216.65  5060.4  215.60  5090.4  216.73  5151.2  216.44  5190.4  215.06
  5251.4  216.10  5274.4  217.12  5283.7  216.01  5300.1  217.44  5315.5  216.36
  5416.6  217.30  5477.2  218.27  5749.7  224.61  5786.6  226.71  6016.1  234.43
#Mann=11,-1,0
  3736.7    0.05       0  3779.2    0.04       0  4107.9    0.12       0
  4222.2    0.04       0  4427.9    0.12       0  4998.2    0.05       0
  5002.7    0.12       0  5151.2   0.013       0  5251.4    0.05       0
  5416.6    0.12       0  5477.2    0.05       0
Bank Sta=4998.2,5002.7
Exp/Cntr=0.3,0.1

Type RM Length L Ch R = 1,3744,368,368,368
BEGIN DESCRIPTION:
TRIB 5 TO BOGGY BRANCH 3.0
END DESCRIPTION:
XS GIS Cut Line= 3
      2505474.98     13537775.04      2506075.00     13536575.00
      2505525.02     13535975.02
#Sta/Elev= 30
  3410.8  230.94  3526.1  228.28  3538.5  227.98  3647.2  224.15  3759.1  221.18
  3864.5  218.56  4081.7  217.11  4229.8  217.53  4296.9  218.90  4565.2  216.14
  4582.0  216.83  4744.1  214.19  4766.4  213.14  4778.2  211.51  4778.6  211.01
  4782.8  211.51  4802.1  214.11  4858.9  214.50  4865.6  213.41  4908.2  215.20
  4930.8  214.19  5003.6  214.47  5071.0  215.61  5078.1  214.59  5382.4  221.01
  5410.7  222.40  5445.9  222.39  5474.2  223.98  5488.4  223.15  5566.4  225.74
#Mann=10,-1,0
  3410.8    0.04       0  3526.1    0.05       0  3538.5    0.12       0
  3647.2    0.04       0  3759.1    0.05       0  3864.5    0.12       0
  4778.2    0.03       0  4782.8    0.12       0  4930.8   0.013       0
  5003.6    0.05       0
Bank Sta=4778.2,4782.8
Exp/Cntr=0.3,0.1

Type RM Length L Ch R = 1,3376,511,511,511
BEGIN DESCRIPTION:
Mapping XS f2e774e3
END DESCRIPTION:
XS GIS Cut Line= 4
      2505674.07     13537706.76      2506264.33     13536738.91
      2506264.33     13536383.01      2505812.93     13535532.29
#Sta/Elev= 30
  3436.5  225.44  3484.8  223.60  3533.5  222.64  3586.5  220.65  3678.5  218.31
  3934.7  216.21  4003.1  216.92  4269.0  219.02  4507.3  217.73  4644.1  215.97
  4664.1  215.05  4681.8  211.19  4682.1  210.69  4686.4  211.19  4704.1  213.92
  4734.1  211.50  4794.1  214.40  4909.0  213.90  5136.4  214.25  5151.7  213.97
  5246.3  215.75  5350.9  217.99  5437.6  220.90  5448.8  222.07  5455.9  221.06
  5465.1  222.06  5501.1  221.96  5599.5  224.63  5678.9  226.43  5889.1  231.65
#Mann=16,-1,0
  3436.5    0.05       0  3484.8    0.12       0  3533.5    0.05       0
  3586.5    0.12       0  3934.7    0.05       0  4003.1    0.12       0
  4681.8    0.04       0  4686.4    0.12       0  4909.0    0.04       0
  5136.4   0.013       0  5151.7    0.04       0  5246.3    0.05       0
  5350.9    0.04       0  5437.6    0.05       0  5599.5    0.12       0
  5678.9    0.05       0
Bank Sta=4681.8,4686.4
Exp/Cntr=0.3,0.1

Type RM Length L Ch R = 1,2865,420,420,420
BEGIN DESCRIPTION:
Mapping XS 315a43ea
END DESCRIPTION:
XS GIS Cut Line= 4
      2505739.16     13537724.15      2506672.31     13536396.03
      2506654.95     13536040.13      2506134.13     13535532.32
#Sta/Elev= 30
  3154.4  224.28  3258.4  221.08  3296.5  220.01  3422.6  217.40  3540.0  217.05
  3707.2  217.19  4047.3  220.25  4213.7  219.21  4219.8  220.24  4313.9  218.20
  4350.5  218.17  4758.3  213.69  4829.4  211.81  4978.8  211.24  5006.5  208.24
  5006.9  207.74  5011.2  208.24  5043.2  211.75  5061.6  212.29  5268.5  213.52
  5347.1  214.59  5402.3  215.08  5448.6  216.53  5491.1  215.91  5533.4  217.94
  5669.5  220.20  5750.0  222.26  5803.1  223.25  5837.6  225.19  5861.3  230.05
#Mann=18,-1,0
  3154.4    0.12       0  3258.4    0.05       0  3296.5    0.12       0
  3540.0    0.05       0  3707.2    0.12       0  4313.9    0.05       0
  4350.5    0.12       0  5006.5    0.05       0  5011.2    0.12       0
  5043.2     0.1       0  5061.6    0.05       0  5268.5    0.04       0
  5347.1    0.05       0  5402.3    0.04       0  5533.4    0.05       0
  5669.5    0.04       0  5750.0    0.12       0  5803.1    0.05       0
Bank Sta=5006.5,5011.2
Exp/Cntr=0.3,0.1

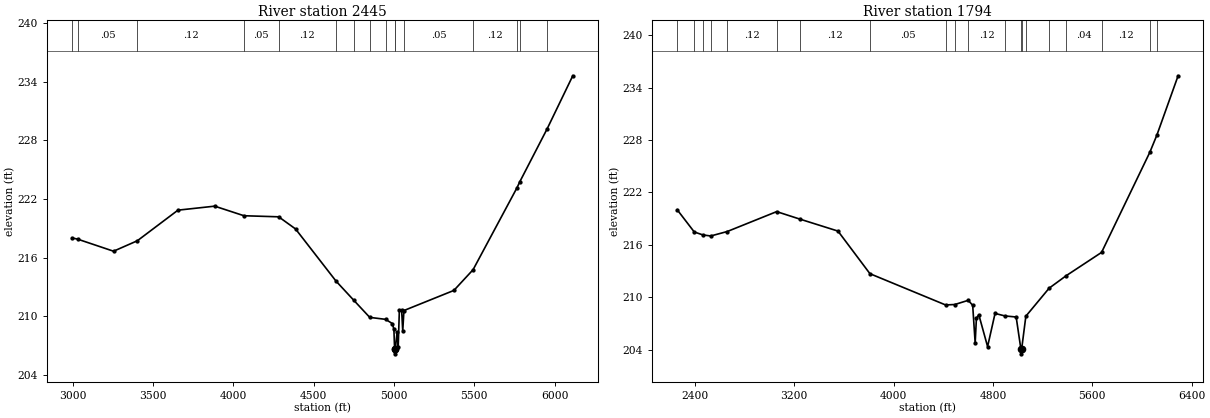
Type RM Length L Ch R = 1,2445,651,651,651
BEGIN DESCRIPTION:
Mapping XS 78210aa9
END DESCRIPTION:
XS GIS Cut Line= 4
      2505988.49     13537659.40      2506988.51     13536253.13
      2507009.34     13535966.67      2506254.46     13535159.72
#Sta/Elev= 30
  2995.1  218.03  3030.0  217.91  3254.3  216.67  3402.5  217.74  3655.2  220.87
  3884.0  221.28  4066.1  220.30  4282.2  220.19  4387.1  218.95  4639.3  213.61
  4750.4  211.64  4849.1  209.90  4947.7  209.70  4989.5  209.27  4999.5  208.69
  5003.8  206.67  5004.2  206.17  5008.6  206.67  5019.3  208.41  5026.2  206.83
  5033.5  210.66  5047.6  210.64  5054.5  208.50  5061.9  210.60  5373.0  212.66
  5492.4  214.78  5765.3  223.15  5783.9  223.80  5953.9  229.21  6112.9  234.62
#Mann=16,-1,0
  2995.1    0.12       0  3030.0    0.05       0  3402.5    0.12       0
  4066.1    0.05       0  4282.2    0.12       0  4639.3     0.1       0
  4750.4    0.12       0  4849.1     0.1       0  4947.7    0.12       0
  5003.8    0.05       0  5008.6    0.12       0  5061.9    0.05       0
  5492.4    0.12       0  5765.3    0.05       0  5783.9    0.12       0
  5953.9    0.05       0
Bank Sta=5003.8,5008.6
Exp/Cntr=0.3,0.1

Type RM Length L Ch R = 1,1794,0,0,0
BEGIN DESCRIPTION:
TRIB 5 TO BOGGY BRANCH 1.0
END DESCRIPTION:
XS GIS Cut Line= 4
      2505974.98     13537775.02      2507493.72     13536185.42
      2507508.29     13535641.62      2506405.19     13534971.88
#Sta/Elev= 30
  2257.5  220.01  2394.5  217.47  2464.3  217.13  2527.2  217.01  2659.9  217.52
  3058.2  219.80  3245.5  218.94  3551.9  217.57  3809.2  212.69  4418.4  209.11
  4492.3  209.16  4600.8  209.64  4636.5  209.07  4656.5  204.75  4666.5  207.59
  4686.0  207.98  4756.5  204.34  4816.6  208.14  4896.4  207.85  4986.6  207.73
  5025.1  204.01  5025.5  203.51  5030.4  204.01  5064.6  207.82  5252.0  211.03
  5388.3  212.45  5674.3  215.13  6063.3  226.61  6119.5  228.56  6290.5  235.36
#Mann=20,-1,0
  2257.5   0.013       0  2394.5    0.05       0  2464.3   0.013       0
  2527.2    0.05       0  2659.9    0.12       0  3058.2    0.05       0
  3245.5    0.12       0  3809.2    0.05       0  4418.4    0.12       0
  4492.3    0.05       0  4600.8    0.12       0  4896.4     0.1       0
  5025.1    0.05       0  5030.4     0.1       0  5064.6    0.05       0
  5252.0    0.12       0  5388.3    0.04       0  5674.3    0.12       0
  6063.3    0.05       0  6119.5    0.12       0
Bank Sta=5025.1,5030.4
Exp/Cntr=0.3,0.1

Chan Stop Cuts=-1