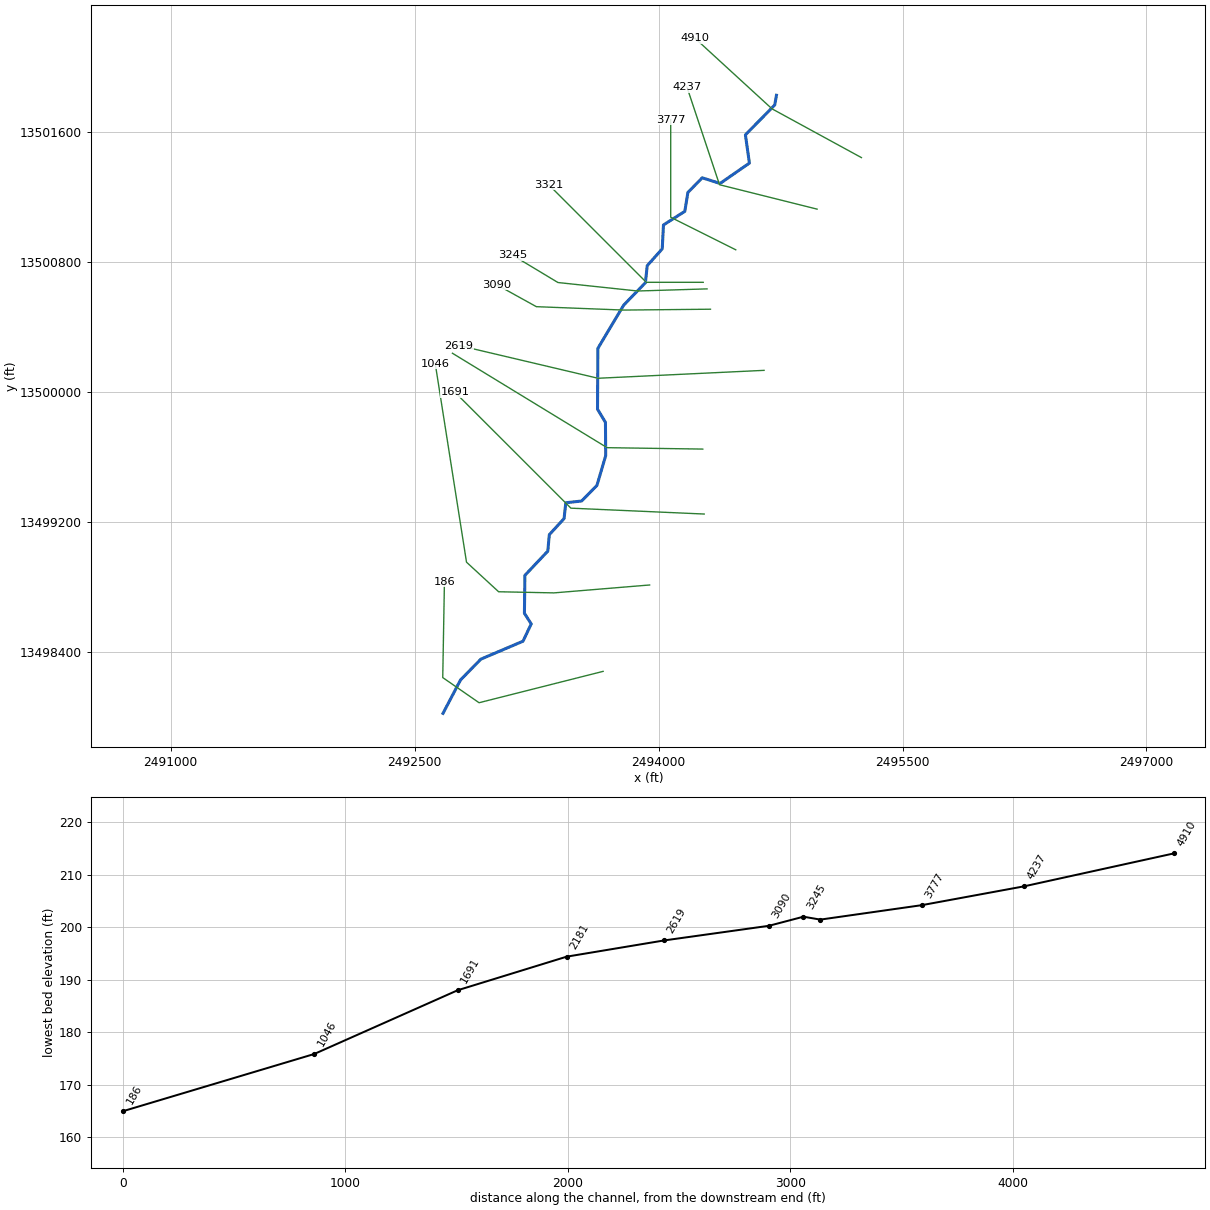
--- TRIB 5 TO EIGHTEENMILE CREEK.prj (project) ---

Proj Title=TRIB 5 TO EIGHTEENMILE CREEK Base Level Engineering
Current Plan=p01
Default Exp/Contr=0.3,0.1
English Units
Geom File=g01
Flow File=f01
Plan File=p01
Y Axis Title=Elevation
X Axis Title(PF)=Main Channel Distance
X Axis Title(XS)=Station
BEGIN DESCRIPTION:
TRIB 5 TO EIGHTEENMILE CREEK
END DESCRIPTION:
DSS Export Rating Curves= 0
DSS Export Rating Curve Sorted= 0
DSS Export Volume Flow Curves= 0
DXF OffsetX= 0
DXF OffsetY= 0
DXF ScaleX= 1
DXF ScaleY= 10

--- TRIB 5 TO EIGHTEENMILE CREEK.p01 (plan) ---

Plan Title=Multiple Run
Short Identifier=Multiple
Geom File=g01
Flow File=f01
Subcritical Flow
K Sum by GR= 0
Std Step Tol= 0.01
Critical Tol= 0.01
Num of Std Step Trials= 20
Max Error Tol= 0.3
Flow Tol Ratio= 0.001
Split Flow NTrial= 30
Split Flow Tol= 0.02
Split Flow Ratio= 0.02
Log Output Level= 0
Friction Slope Method= 1
Unsteady Friction Slope Method= 2
Unsteady Bridges Friction Slope Method= 1
Parabolic Critical Depth
Global Vel Dist=  1 , 1 , 1
Global Log Level= 0
CheckData=True
Encroach Param= -1, 0, 0, 0
BEGIN DESCRIPTION:
Multiple Run
END DESCRIPTION:

--- TRIB 5 TO EIGHTEENMILE CREEK.f01 (steady flow) ---

Flow Title=Multiple
Number of Profiles=7
Profile Names=10-year,25-year,50-year,1pct_min,100-year,1pct_plu,500-year
River Rch & RM= TRIB 5 TO EIGHTE,Reach-1,4910
     426     673     891     573    1144    2283    1861
Boundary for River Rch & Prof#=TRIB 5 TO EIGHTE,Reach-1,1
Up Type=0
Dn Type=3
Dn Slope=0.005
Boundary for River Rch & Prof#=TRIB 5 TO EIGHTE,Reach-1,2
Up Type=0
Dn Type=3
Dn Slope=0.005
Boundary for River Rch & Prof#=TRIB 5 TO EIGHTE,Reach-1,3
Up Type=0
Dn Type=3
Dn Slope=0.005
Boundary for River Rch & Prof#=TRIB 5 TO EIGHTE,Reach-1,4
Up Type=0
Dn Type=3
Dn Slope=0.005
Boundary for River Rch & Prof#=TRIB 5 TO EIGHTE,Reach-1,5
Up Type=0
Dn Type=3
Dn Slope=0.005
Boundary for River Rch & Prof#=TRIB 5 TO EIGHTE,Reach-1,6
Up Type=0
Dn Type=3
Dn Slope=0.005
Boundary for River Rch & Prof#=TRIB 5 TO EIGHTE,Reach-1,7
Up Type=0
Dn Type=3
Dn Slope=0.005

--- TRIB 5 TO EIGHTEENMILE CREEK.g01 (geometry) ---

Geom Title=Existing Conditions
Program Version=4.10

River Reach=TRIB 5 TO EIGHTE,Reach-1
Reach XY= 30
        2494725.       13501825.      2494714.48     13501765.21
      2494534.29     13501581.67      2494558.77     13501407.96
       2494378.4     13501282.83      2494268.93     13501317.51
      2494180.52     13501227.44      2494161.74     13501111.35
      2494030.37      13501027.7      2494022.92     13500880.86
      2493930.54     13500777.42      2493919.48     13500672.57
      2493785.78     13500534.68      2493627.24     13500269.07
      2493625.07     13499895.03      2493673.78      13499814.5
      2493675.43     13499609.82      2493621.39     13499426.48
      2493527.38     13499330.54      2493430.11     13499319.89
      2493419.43     13499222.64      2493328.63      13499123.5
      2493319.48     13499022.57      2493178.54     13498873.54
      2493175.66     13498640.16      2493217.47     13498574.99
        2493167.     13498468.67      2492908.25     13498358.54
      2492783.14     13498231.06        2492675.       13498025.

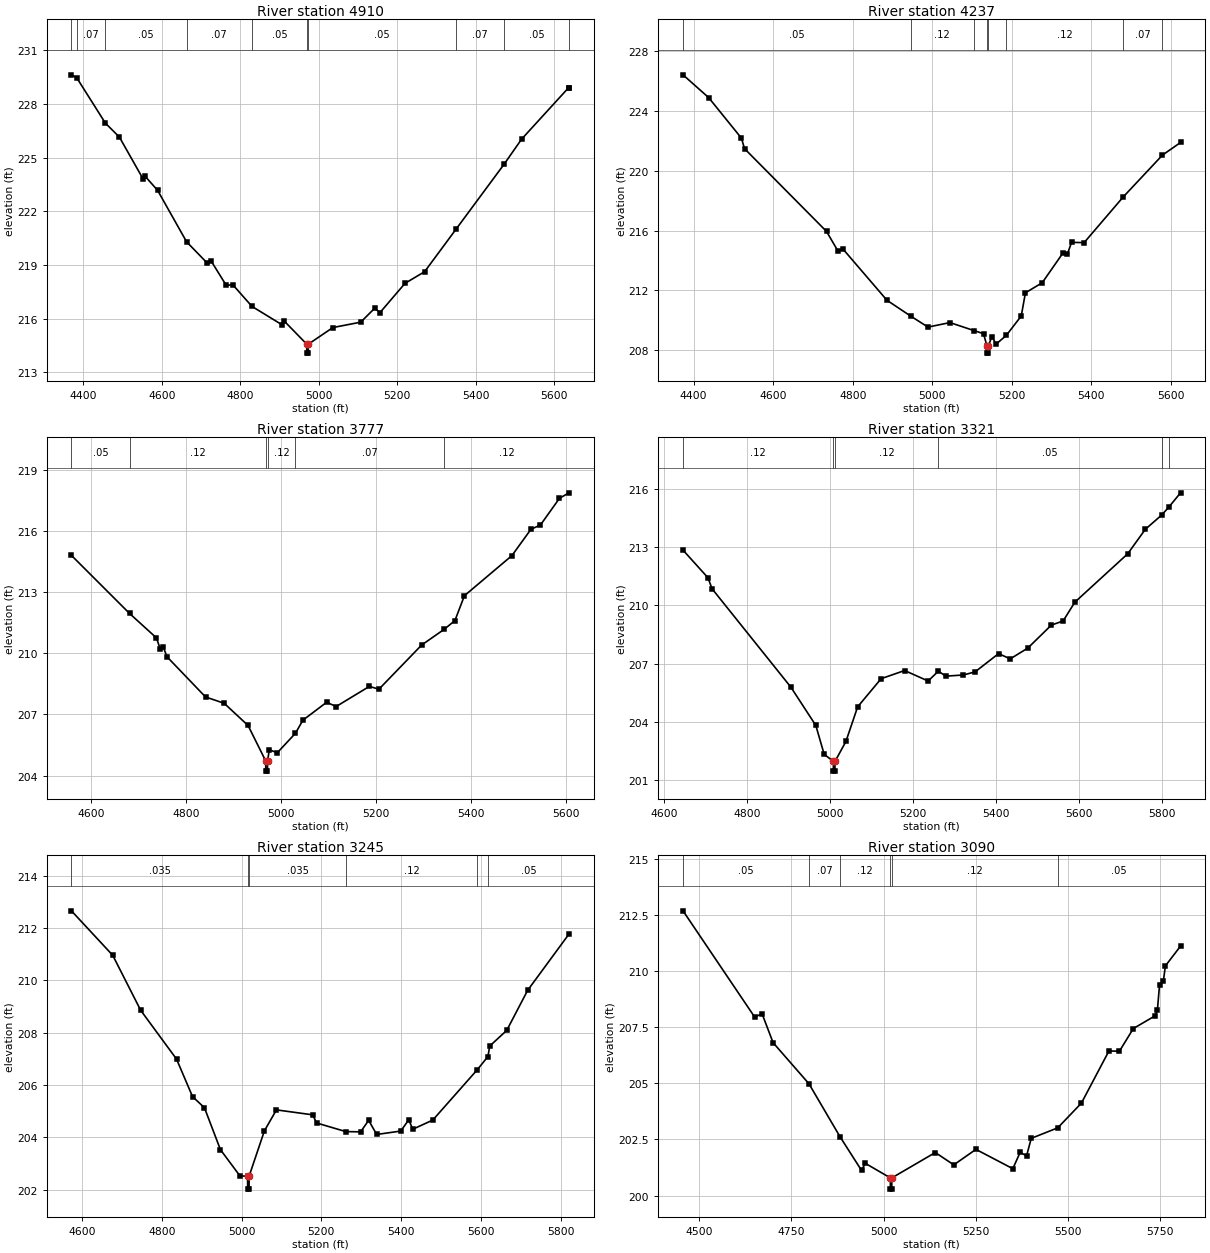
Type RM Length L Ch R = 1 ,4910    ,673,673,673
BEGIN DESCRIPTION:
TRIB 5 TO EIGHTEENMILE CREEK 7.0
END DESCRIPTION:
XS GIS Cut Line= 3
      2495247.72     13501441.63       2494697.7     13501741.64
      2494225.01     13502174.99
#Sta/Elev= 30
  4369.5  229.63  4382.9  229.47  4456.1  226.93  4491.8  226.15  4551.6  223.83
  4557.3  223.96    4589  223.18    4663   220.3  4714.3  219.14  4726.3   219.2
  4764.2  217.86  4780.4  217.91  4829.6  216.69  4905.7  215.67  4911.4  215.88
  4969.2  214.58  4969.4  214.08  4972.9  214.08  4973.2  214.58  5035.8  215.51
  5106.7  215.81  5141.9  216.58    5156  216.35  5219.6  217.98  5269.5  218.63
  5350.1  221.02  5472.2  224.64  5516.8  226.04  5636.8  228.92  5637.3  228.92
#Mann= 10 ,-1 , 0
  4369.5     .05       0  4382.9     .07       0  4456.1     .05       0
    4663     .07       0  4829.6     .05       0  4969.2     .05       0
  4973.2     .05       0  5350.1     .07       0  5472.2     .05       0
  5636.8     .12       0
Bank Sta=4969.2,4973.2
XS Rating Curve= 0 ,0
Exp/Cntr=0.3,0.1

Type RM Length L Ch R = 1 ,4237    ,460,460,460
BEGIN DESCRIPTION:
TRIB 5 TO EIGHTEENMILE CREEK 6.0
END DESCRIPTION:
XS GIS Cut Line= 3
        2494975.       13501125.        2494375.       13501275.
      2494175.01     13501874.98
#Sta/Elev= 30
  4373.3   226.4  4437.7  224.88  4520.2  222.17  4527.9  221.47  4734.1  215.94
  4762.4  214.65  4775.3  214.77  4886.1  211.34  4945.4  210.29  4989.2  209.55
  5044.5  209.85  5104.4  209.32  5128.8  209.11  5137.3  208.31  5137.6  207.81
  5141.1  207.81  5141.3  208.31  5149.9  208.92  5160.4  208.41    5186  208.99
  5223.7  210.29  5234.2  211.84  5276.4  212.51  5329.1  214.52  5339.6  214.42
  5350.2  215.21  5381.8  215.19    5480  218.24  5578.8  221.04  5624.2  221.88
#Mann= 8 ,-1 , 0
  4373.3     .05       0  4945.4     .12       0  5104.4     .07       0
  5137.3     .05       0  5141.3     .07       0    5186     .12       0
    5480     .07       0  5578.8     .12       0
Bank Sta=5137.3,5141.3
XS Rating Curve= 0 ,0
Exp/Cntr=0.3,0.1

Type RM Length L Ch R = 1 ,3777    ,456,456,456
BEGIN DESCRIPTION:
TRIB 5 TO EIGHTEENMILE CREEK 5.0
END DESCRIPTION:
XS GIS Cut Line= 3
      2494475.01     13500874.99        2494075.       13501075.
        2494075.     13501674.97
#Sta/Elev= 30
  4558.7  214.81    4681  211.96  4737.6  210.76    4746  210.19  4751.6  210.33
    4760  209.83    4841  207.86  4880.2  207.55  4930.5  206.46  4967.6  204.72
  4967.8  204.22  4971.3  204.22  4971.6  204.72  4975.2  205.27    4992  205.12
  5030.3  206.08  5045.9  206.72  5095.9   207.6  5115.9  207.39  5185.9  208.38
  5205.9  208.24  5295.9  210.41  5343.3  211.18  5365.9  211.61  5385.9  212.83
  5485.9   214.8  5525.9  216.09  5545.9   216.3  5585.9  217.61  5605.9  217.88
#Mann= 6 ,-1 , 0
  4558.7     .05       0    4681     .12       0  4967.6     .05       0
  4971.6     .12       0  5030.3     .07       0  5343.3     .12       0
Bank Sta=4967.6,4971.6
XS Rating Curve= 0 ,0
Exp/Cntr=0.3,0.1

Type RM Length L Ch R = 1 ,3321    ,76,76,76
BEGIN DESCRIPTION:
TRIB 5 TO EIGHTEENMILE CREEK 4.0
END DESCRIPTION:
XS GIS Cut Line= 3
      2494275.04       13500675.        2493925.       13500675.
      2493324.97     13501275.03
#Sta/Elev= 30
  4645.6  212.85  4705.6  211.43  4715.6  210.86  4905.6  205.79  4965.6  203.82
  4985.6  202.34  5007.8  201.97    5008  201.47  5011.5  201.47  5011.8  201.97
  5038.1     203  5066.3  204.78  5122.9  206.23  5179.5  206.65  5236.1  206.11
  5260.9  206.62  5278.5  206.36  5320.9  206.42  5349.2  206.58  5405.8  207.52
    5434  207.25  5476.5  207.81    5533  208.99  5561.3   209.2  5589.6  210.17
  5716.9  212.66  5759.3  213.92  5798.4  214.65  5815.8  215.06  5844.2   215.8
#Mann= 6 ,-1 , 0
  4645.6     .12       0  5007.8     .05       0  5011.8     .12       0
  5260.9     .05       0  5798.4    .035       0  5815.8     .05       0
Bank Sta=5007.8,5011.8
XS Rating Curve= 0 ,0
Exp/Cntr=0.3,0.1

Type RM Length L Ch R = 1 ,3245    ,155,155,155
BEGIN DESCRIPTION:
Mapping XS e588b034
END DESCRIPTION:
XS GIS Cut Line= 4
      2494298.55     13500634.67       2493871.5     13500621.65
      2493381.92     13500673.73      2493100.63     13500843.02
#Sta/Elev= 30
  4573.2  212.66  4676.8  210.96  4746.8  208.86  4836.9  206.99  4876.9  205.56
  4906.9  205.13  4946.9  203.53  4996.2  202.52    5015  202.52  5015.3  202.02
  5018.8  202.02    5019  202.52  5057.3  204.25  5087.4  205.05  5178.5  204.86
    5188  204.55  5261.3  204.22  5298.6  204.21  5318.7  204.65  5338.9  204.11
  5399.2  204.24  5419.3  204.67  5429.4  204.31  5479.6  204.66  5591.5  206.59
  5617.9  207.09  5622.4  207.49  5665.1  208.09  5717.5  209.62  5821.1  211.77
#Mann= 6 ,-1 , 0
  4573.2    .035       0    5015    .035       0    5019    .035       0
  5261.3     .12       0  5591.5    .035       0  5617.9     .05       0
Bank Sta=5015,5019
XS Rating Curve= 0 ,0
Exp/Cntr=0.3,0.1

Type RM Length L Ch R = 1 ,3090    ,471,471,471
BEGIN DESCRIPTION:
Mapping XS 22eb157f
END DESCRIPTION:
XS GIS Cut Line= 4
       2494319.4     13500509.67      2493785.56     13500504.46
       2493249.1     13500525.29      2493004.99     13500660.33
#Sta/Elev= 30
    4456  212.68  4650.4  207.95  4670.4   208.1  4700.4  206.81  4797.7  204.98
    4882  202.62  4940.4  201.12  4950.4  201.44  5018.5  200.79  5018.7  200.29
  5022.2  200.29  5022.5  200.79  5140.5  201.92  5190.6  201.37  5250.6  202.06
  5350.7   201.2  5370.7  201.93    5388  201.77  5400.7  202.55  5472.7  203.02
  5536.8  204.12  5611.4  206.44  5639.9  206.43  5677.7  207.44  5737.1  208.01
  5742.9  208.26  5748.7  209.37    5759  209.55  5764.7  210.23  5805.7  211.11
#Mann= 6 ,-1 , 0
    4456     .05       0  4797.7     .07       0    4882     .12       0
  5018.5     .05       0  5022.5     .12       0  5472.7     .05       0
Bank Sta=5018.5,5022.5
XS Rating Curve= 0 ,0
Exp/Cntr=0.3,0.1

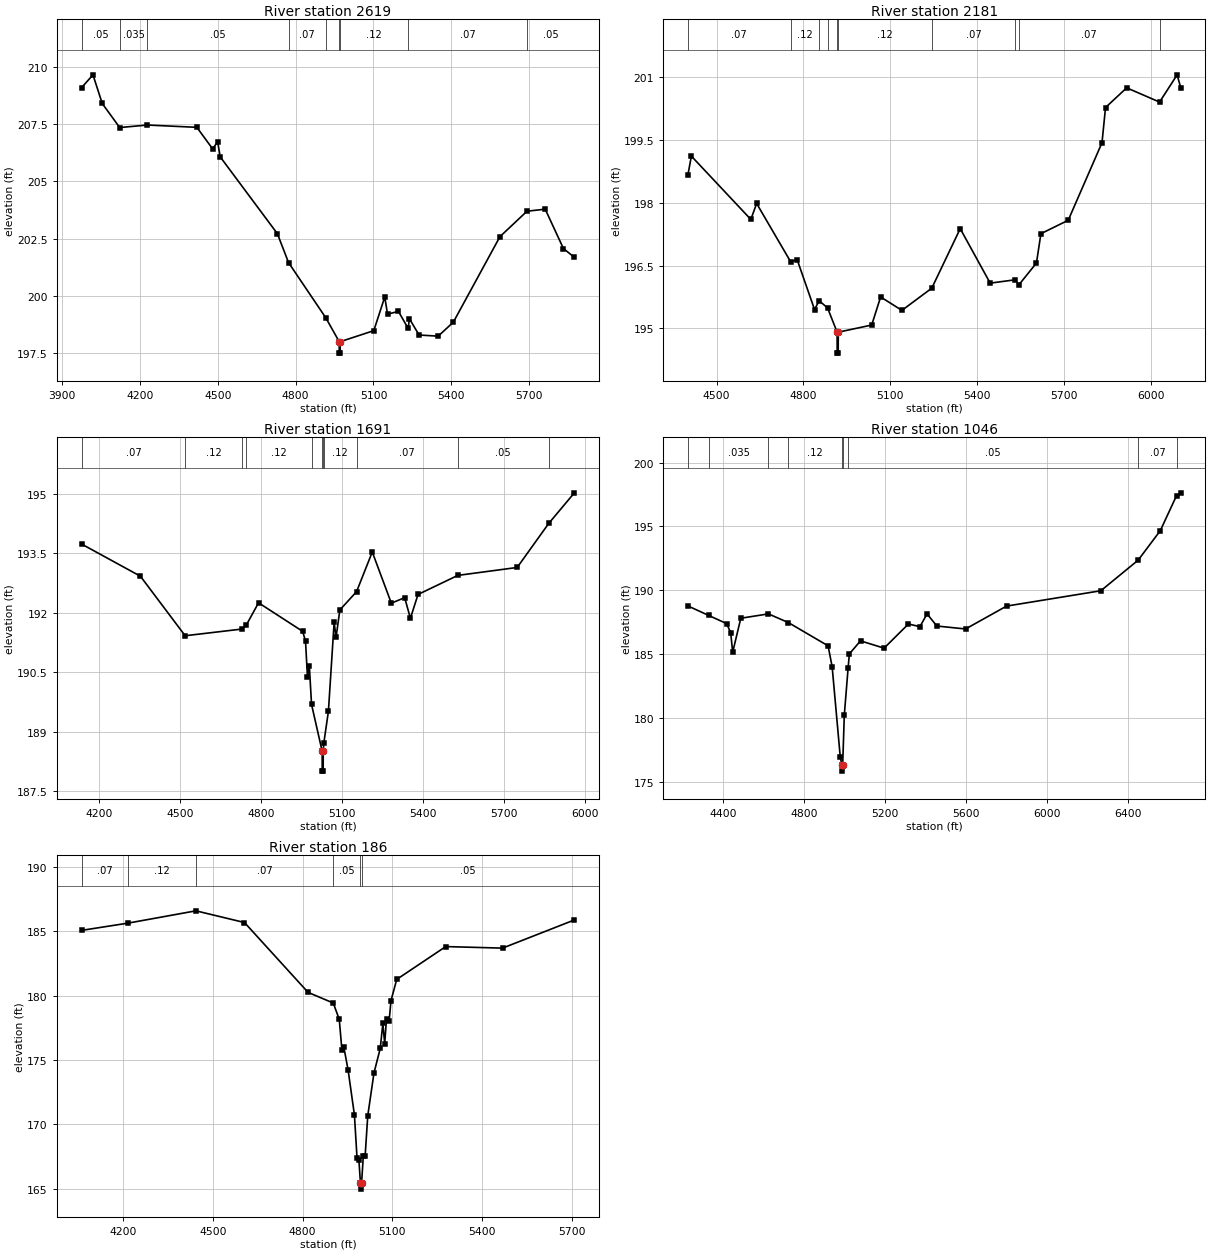
Type RM Length L Ch R = 1 ,2619    ,438,438,438
BEGIN DESCRIPTION:
Mapping XS 8a8a4d27
END DESCRIPTION:
XS GIS Cut Line= 3
      2494648.94     13500133.82      2493628.14     13500085.21
      2492774.02     13500286.59
#Sta/Elev= 30
  3974.8  209.08  4018.8  209.64  4054.5  208.39  4121.9  207.34  4228.2  207.45
  4419.2  207.35    4480  206.41  4499.3  206.72  4509.3  206.06  4729.6  202.71
  4772.6  201.45  4916.2  199.04  4967.9     198  4968.1   197.5  4971.6   197.5
  4971.9     198  5101.2  198.48  5143.5  199.95  5154.1   199.2  5196.1  199.32
  5233.6  198.58  5238.5     199  5275.7  198.29  5349.3  198.24  5407.8  198.85
  5587.4  202.58  5691.6  203.69  5761.9  203.78  5832.2  202.06  5874.3  201.68
#Mann= 9 ,-1 , 0
  3974.8     .05       0  4121.9    .035       0  4228.2     .05       0
  4772.6     .07       0  4916.2     .12       0  4967.9     .05       0
  4971.9     .12       0  5233.6     .07       0  5691.6     .05       0
Bank Sta=4967.9,4971.9
XS Rating Curve= 0 ,0
Exp/Cntr=0.3,0.1

Type RM Length L Ch R = 1 ,2181    ,490,490,490
BEGIN DESCRIPTION:
Mapping XS 89534600
END DESCRIPTION:
XS GIS Cut Line= 3
      2494272.13     13499649.83      2493684.04     13499658.51
      2492733.14     13500238.92
#Sta/Elev= 30
  4401.4  198.67  4413.2  199.11  4618.6   197.6  4638.6  197.98  4756.1  196.59
  4778.6  196.64  4838.6  195.45  4854.4  195.66  4883.5  195.49  4916.6  194.91
  4916.8  194.41  4920.3  194.41  4920.6  194.91    5036  195.08  5066.9  195.75
  5140.4  195.43  5243.6  195.96  5341.8  197.38  5445.3  196.08  5531.8  196.16
  5544.5  196.04  5605.1  196.56  5620.5  197.26  5714.8  197.58  5831.5  199.43
  5843.7  200.27  5916.8  200.74  6030.4   200.4    6091  201.05  6103.6  200.74
#Mann= 10 ,-1 , 0
  4401.4     .07       0  4756.1     .12       0  4854.4     .07       0
  4883.5     .12       0  4916.6     .05       0  4920.6     .12       0
  5243.6     .07       0  5531.8     .12       0  5544.5     .07       0
  6030.4     .05       0
Bank Sta=4916.6,4920.6
XS Rating Curve= 0 ,0
Exp/Cntr=0.3,0.1

Type RM Length L Ch R = 1 ,1691    ,645,645,645
BEGIN DESCRIPTION:
Mapping XS 353d055a
END DESCRIPTION:
XS GIS Cut Line= 3
      2494280.79     13499250.53      2493461.47      13499286.6
      2492748.93     13499998.86
#Sta/Elev= 30
  4134.4  193.73  4352.6  192.92  4518.6  191.42  4730.7  191.59  4745.4  191.69
  4790.8  192.25  4954.5  191.53    4965  191.28  4972.1  190.39  4979.2  190.65
  4987.3  189.69  5026.7  188.51  5026.9  188.01  5030.4  188.01  5030.7  188.51
  5032.9  188.72  5049.9  189.52  5071.1  191.76  5078.2  191.38  5092.3  192.07
  5154.2  192.53  5212.5  193.53  5283.2  192.24  5332.7  192.38  5353.9  191.86
  5382.2  192.46  5529.7  192.94  5749.9  193.14    5867  194.25    5962  195.02
#Mann= 11 ,-1 , 0
  4134.4     .07       0  4518.6     .12       0  4730.7     .05       0
  4745.4     .12       0  4987.3     .07       0  5026.7     .05       0
  5030.7     .07       0  5032.9     .12       0  5154.2     .07       0
  5529.7     .05       0    5867     .07       0
Bank Sta=5026.7,5030.7
XS Rating Curve= 0 ,0
Exp/Cntr=0.3,0.1

Type RM Length L Ch R = 1 ,1046    ,860,860,860
BEGIN DESCRIPTION:
Mapping XS 86c740fa
END DESCRIPTION:
XS GIS Cut Line= 5
      2493945.16     13498814.32       2493357.3     13498765.77
      2493017.03     13498772.71      2492819.63     13498954.53
       2492627.4       13500175.
#Sta/Elev= 30
  4227.7  188.78    4330  188.04  4418.5   187.4  4438.6   186.7  4448.6  185.16
  4488.7  187.82  4625.2  188.16  4723.7  187.48  4919.9  185.66  4939.9  184.02
  4979.9  176.97  4987.9  176.36  4988.1  175.86  4991.9  176.36  4999.9  180.24
  5018.8  183.95  5024.9  185.03  5079.9  186.05  5196.4  185.48  5316.6  187.37
  5373.4  187.16  5408.5  188.16  5457.1  187.21  5598.9  186.98  5801.3  188.77
    6267  189.97  6451.1  192.36  6560.6  194.67  6640.9  197.41  6661.8  197.63
#Mann= 9 ,-1 , 0
  4227.7     .05       0    4330    .035       0  4625.2     .05       0
  4723.7     .12       0  4987.9     .05       0  4991.9     .12       0
  5018.8     .05       0  6451.1     .07       0  6640.9     .05       0
Bank Sta=4987.9,4991.9
XS Rating Curve= 0 ,0
Exp/Cntr=0.3,0.1

Type RM Length L Ch R = 1 ,186     ,0,0,0
BEGIN DESCRIPTION:
TRIB 5 TO EIGHTEENMILE CREEK 1.0
END DESCRIPTION:
XS GIS Cut Line= 4
      2493659.66     13498283.31      2492896.76     13498090.44
      2492673.53     13498245.11      2492683.95     13498835.35
#Sta/Elev= 30
  4060.2  185.08  4214.8  185.64  4442.8   186.6  4605.3  185.69    4818  180.26
  4902.3  179.43  4922.4  178.16  4931.2  175.79  4937.3  176.05  4952.2  174.19
  4973.1  170.73  4981.9  167.36    4988  167.25  4993.2  165.46  4993.5  164.96
  4997.2  165.46  5002.8  167.53  5008.9   167.5  5017.7  170.66  5038.6     174
  5059.6  175.91  5068.2  177.85  5074.4  176.28  5080.5  178.22  5089.3  178.05
  5095.4  179.61  5114.7  181.27  5278.6  183.82  5468.6   183.7    5709  185.89
#Mann= 6 ,-1 , 0
  4060.2     .07       0  4214.8     .12       0  4442.8     .07       0
  4902.3     .05       0  4993.2     .05       0  4997.2     .05       0
Bank Sta=4993.2,4997.2
XS Rating Curve= 0 ,0
Exp/Cntr=0.3,0.1

Chan Stop Cuts=-1
Use User Specified Reach Order=0
Composite Channel Slope=5