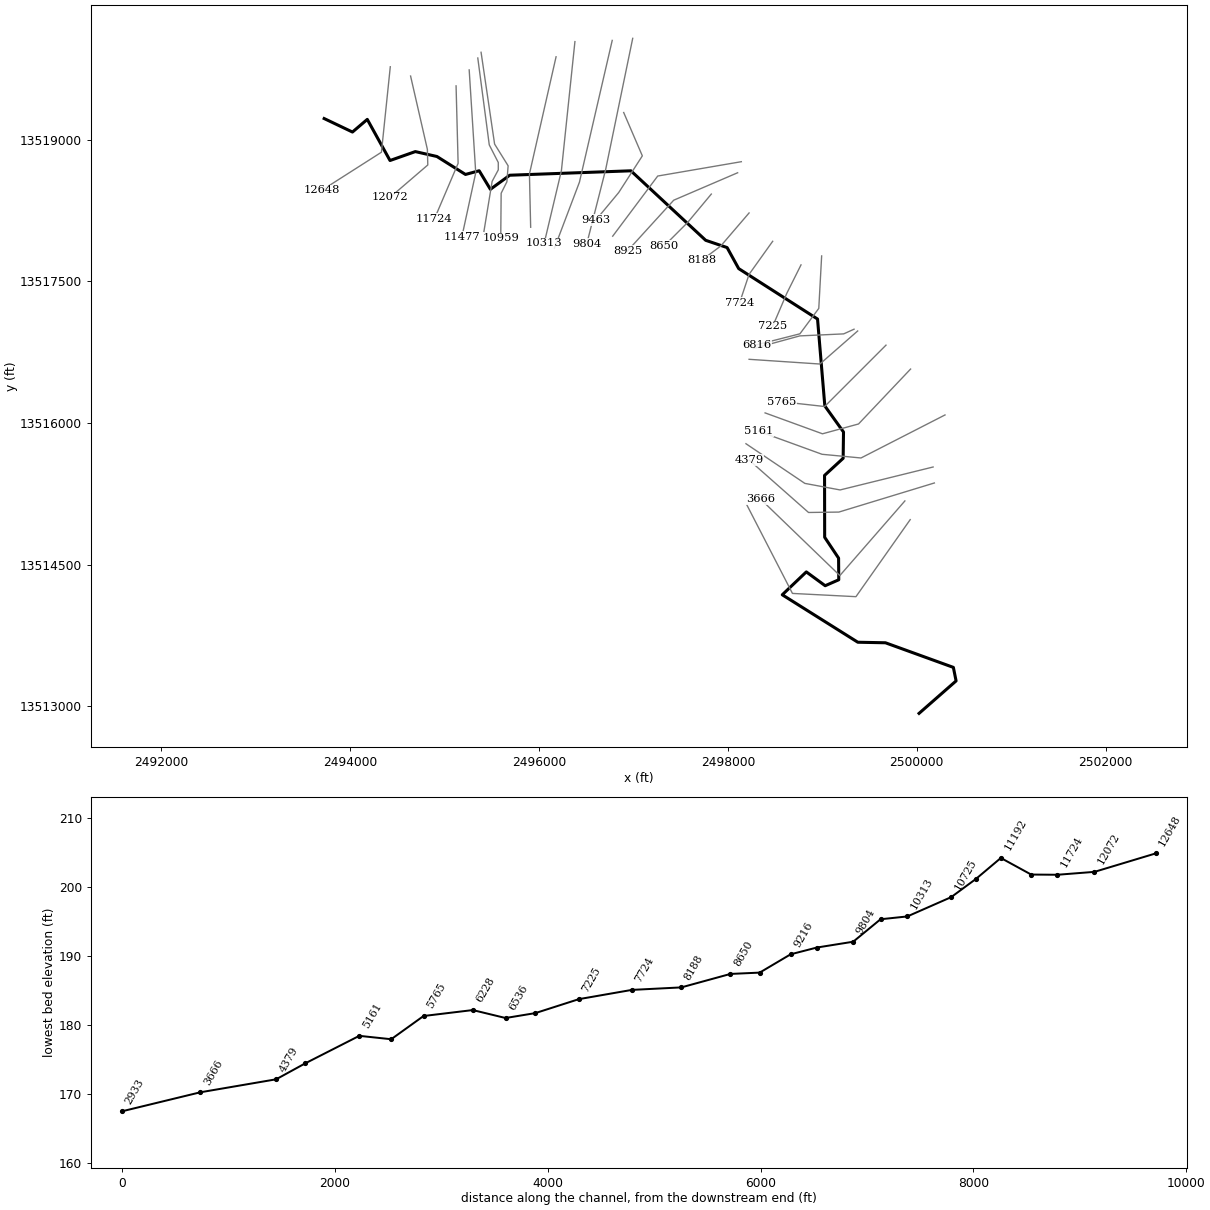
--- TRIB 5 TO FIFTEENMILE CREEK.prj (project) ---

Proj Title=TRIB 5 TO FIFTEENMILE CREEK Base Level Engineering
Current Plan=p01
Default Exp/Contr=0.3,0.1
English Units
Geom File=g01
Flow File=f01
Plan File=p01
BEGIN DESCRIPTION:
TRIB 5 TO FIFTEENMILE CREEK
END DESCRIPTION:

--- TRIB 5 TO FIFTEENMILE CREEK.p01 (plan) ---

Plan Title=Multiple Run
Short Identifier=Multiple
Geom File=g01
Flow File=f01
Subcritical Flow
K Sum by GR= 0
Std Step Tol= 0.01
Critical Tol= 0.01
Num of Std Step Trials= 20
Max Error Tol= 0.3
Flow Tol Ratio= 0.001
Split Flow NTrial= 30
Split Flow Tol= 0.02
Split Flow Ratio= 0.02
Log Output Level= 0
Friction Slope Method= 1
Unsteady Friction Slope Method= 2
Unsteady Bridges Friction Slope Method= 1
Parabolic Critical Depth
Global Vel Dist=  1 , 1 , 1
Global Log Level= 0
CheckData=True
Encroach Param= -1, 0, 0, 0
BEGIN DESCRIPTION:
Multiple Run
END DESCRIPTION:

--- TRIB 5 TO FIFTEENMILE CREEK.f01 (steady flow) ---

Flow Title=Multiple
Number of Profiles=7
Profile Names=10-year,25-year,50-year,1pct_min,100-year,1pct_plu,500-year
River Rch & RM= TRIB 5 TO FIFTEE,Reach-1,12648
     788    1277    1721    1121    2236    4462    3738
River Rch & RM= TRIB 5 TO FIFTEE,Reach-1,8925
     948    1551    2102    1376    2746    5479    4638
River Rch & RM= TRIB 5 TO FIFTEE,Reach-1,6536
    1125    1856    2528    1663    3319    6622    5663
Boundary for River Rch & Prof#=TRIB 5 TO FIFTEE,Reach-1,1
Up Type=0
Dn Type=3
Dn Slope=0.005
Boundary for River Rch & Prof#=TRIB 5 TO FIFTEE,Reach-1,2
Up Type=0
Dn Type=3
Dn Slope=0.005
Boundary for River Rch & Prof#=TRIB 5 TO FIFTEE,Reach-1,3
Up Type=0
Dn Type=3
Dn Slope=0.005
Boundary for River Rch & Prof#=TRIB 5 TO FIFTEE,Reach-1,4
Up Type=0
Dn Type=3
Dn Slope=0.005
Boundary for River Rch & Prof#=TRIB 5 TO FIFTEE,Reach-1,5
Up Type=0
Dn Type=3
Dn Slope=0.005
Boundary for River Rch & Prof#=TRIB 5 TO FIFTEE,Reach-1,6
Up Type=0
Dn Type=3
Dn Slope=0.005
Boundary for River Rch & Prof#=TRIB 5 TO FIFTEE,Reach-1,7
Up Type=0
Dn Type=3
Dn Slope=0.005

--- TRIB 5 TO FIFTEENMILE CREEK.g01 (geometry) ---

Geom Title=Existing Conditions

River Reach=TRIB 5 TO FIFTEE,Reach-1
Reach XY= 30
      2493725.00     13519225.00      2494024.80     13519082.01
      2494181.69     13519216.05      2494422.56     13518780.39
      2494690.39     13518874.92      2494919.14     13518822.92
      2495221.59     13518632.81      2495366.68     13518672.03
      2495485.49     13518475.48      2495690.16     13518624.62
      2496973.50     13518671.39      2497765.19     13517935.51
      2497992.06     13517858.52      2498115.00     13517635.65
      2498949.94     13517101.52      2499027.24     13516180.93
      2499225.04     13515905.02      2499221.25     13515626.55
      2499024.33     13515445.23      2499025.51     13514790.21
      2499172.94     13514569.14      2499174.68     13514340.02
      2499030.90     13514276.96      2498831.05     13514423.41
      2498576.57     13514181.04      2499376.74     13513678.37
      2499669.07     13513672.75      2500388.48     13513412.03
      2500417.26     13513268.78      2500025.00     13512925.00

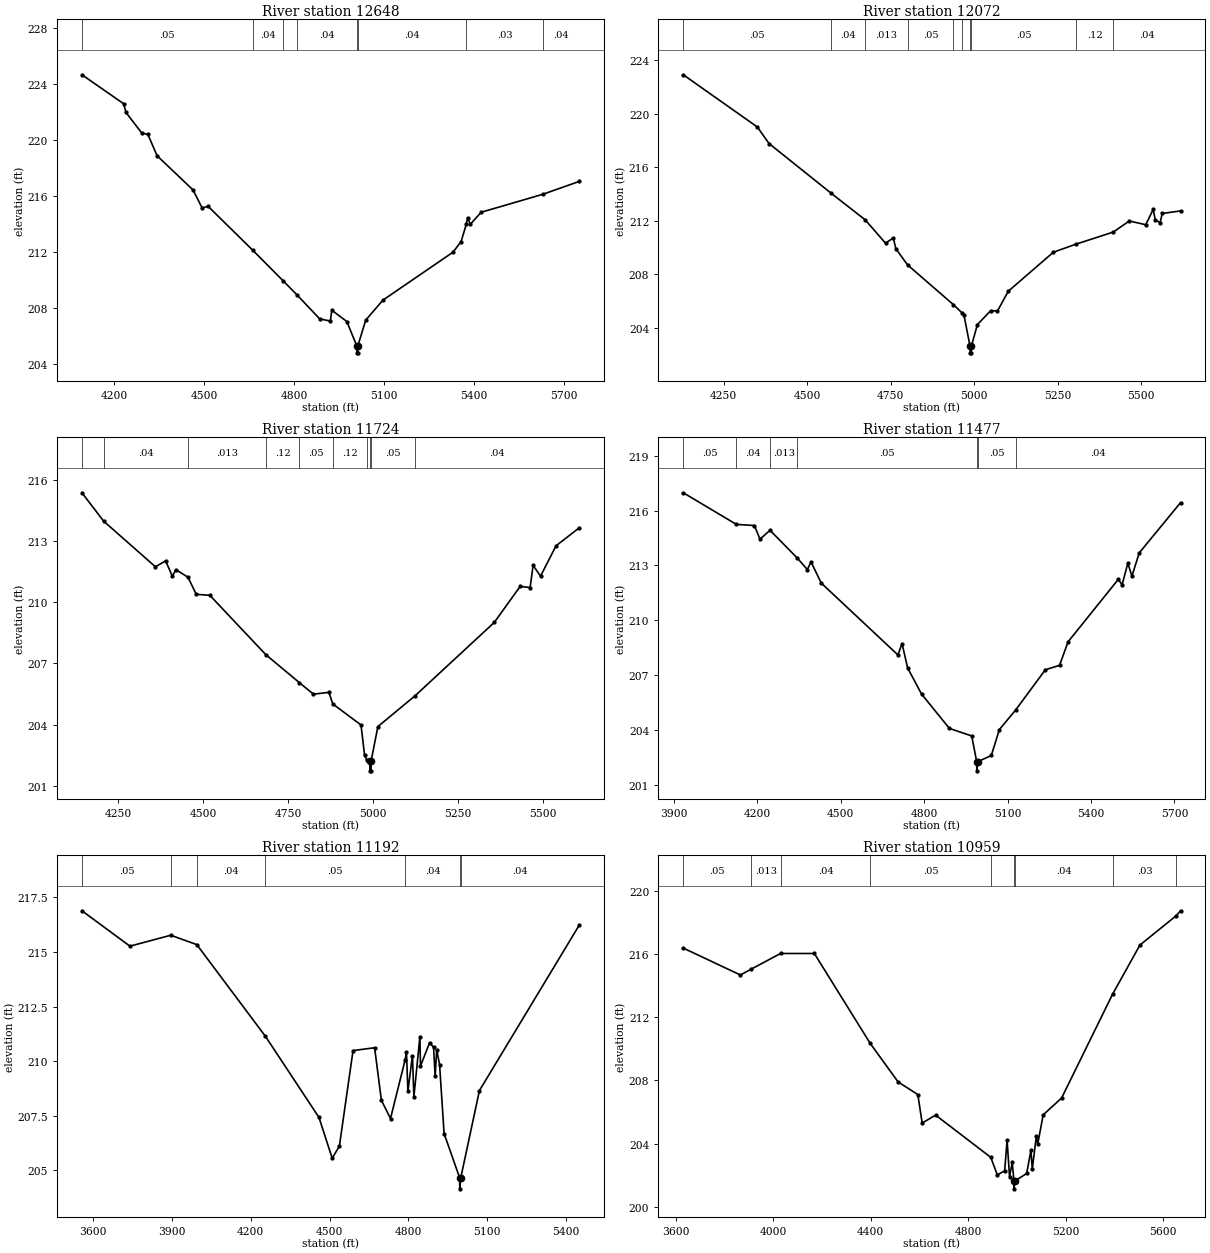
Type RM Length L Ch R = 1,12648,576,576,576
BEGIN DESCRIPTION:
TRIB 5 TO FIFTEENMILE CREEK 20.0
END DESCRIPTION:
XS GIS Cut Line= 3
      2494425.39     13519773.41      2494331.54     13518868.26
      2493701.44     13518466.10
#Sta/Elev= 30
  4092.8  224.66  4232.0  222.59  4239.5  221.97  4292.3  220.50  4312.4  220.41
  4343.3  218.88  4463.2  216.44  4493.3  215.16  4513.5  215.27  4662.1  212.14
  4762.4  209.98  4808.9  208.97  4885.4  207.24  4920.7  207.09  4925.7  207.86
  4975.9  207.05  5008.6  205.32  5008.8  204.82  5012.3  204.82  5012.6  205.32
  5038.5  207.15  5096.0  208.58  5329.5  212.00  5356.6  212.76  5373.8  213.99
  5378.3  214.47  5387.1  213.99  5423.5  214.85  5628.5  216.13  5750.3  217.05
#Mann=8,-1,0
  4092.8    0.05       0  4662.1    0.04       0  4762.4   0.013       0
  4808.9    0.04       0  5008.6    0.04       0  5012.6    0.04       0
  5373.8    0.03       0  5628.5    0.04       0
Bank Sta=5008.6,5012.6
Exp/Cntr=0.3,0.1

Type RM Length L Ch R = 1,12072,348,348,348
BEGIN DESCRIPTION:
Mapping XS b0fb9e67
END DESCRIPTION:
XS GIS Cut Line= 4
      2494640.23     13519675.11      2494818.18     13518898.17
      2494822.53     13518733.24      2494423.19     13518390.34
#Sta/Elev= 30
  4129.4  222.90  4351.2  219.00  4386.0  217.77  4572.5  214.05  4674.1  212.07
  4734.8  210.33  4757.9  210.73  4765.6  209.92  4800.8  208.71  4937.7  205.75
  4964.3  205.12  4969.6  204.94  4987.7  202.65  4987.9  202.15  4991.4  202.15
  4991.7  202.65  5009.7  204.26  5049.7  205.30  5069.7  205.27  5102.2  206.75
  5237.2  209.66  5306.0  210.27  5416.2  211.16  5464.3  211.99  5513.7  211.71
  5535.7  212.85  5542.2  212.07  5556.5  211.86  5563.1  212.55  5617.8  212.74
#Mann=10,-1,0
  4129.4    0.05       0  4572.5    0.04       0  4674.1   0.013       0
  4800.8    0.05       0  4937.7    0.12       0  4964.3    0.05       0
  4987.7    0.05       0  4991.7    0.05       0  5306.0    0.12       0
  5416.2    0.04       0
Bank Sta=4987.7,4991.7
Exp/Cntr=0.3,0.1

Type RM Length L Ch R = 1,11724,247,247,247
BEGIN DESCRIPTION:
Mapping XS 0e1c24f9
END DESCRIPTION:
XS GIS Cut Line= 3
      2495122.00     13519570.94      2495143.71     13518750.60
      2494891.98     13518160.36
#Sta/Elev= 30
  4143.9  215.37  4207.5  213.98  4359.9  211.74  4389.9  212.03  4409.9  211.27
  4419.9  211.60  4455.5  211.23  4480.0  210.39  4520.0  210.34  4684.5  207.43
  4783.0  206.06  4824.7  205.49  4870.1  205.58  4881.6  205.01  4964.5  203.98
  4975.0  202.50  4981.7  202.25  4990.4  202.23  4990.6  201.73  4994.1  201.73
  4994.4  202.23  5014.1  203.90  5124.0  205.42  5356.4  209.01  5432.7  210.78
  5461.8  210.72  5470.7  211.81  5492.4  211.28  5538.1  212.77  5606.2  213.65
#Mann=10,-1,0
  4143.9    0.05       0  4207.5    0.04       0  4455.5   0.013       0
  4684.5    0.12       0  4783.0    0.05       0  4881.6    0.12       0
  4981.7    0.05       0  4990.4    0.05       0  4994.4    0.05       0
  5124.0    0.04       0
Bank Sta=4990.4,4994.4
Exp/Cntr=0.3,0.1

Type RM Length L Ch R = 1,11477,285,285,285
BEGIN DESCRIPTION:
Mapping XS 0dbdea62
END DESCRIPTION:
XS GIS Cut Line= 3
      2495260.89     13519740.21      2495330.34     13518650.78
      2495182.84     13517969.70
#Sta/Elev= 30
  3933.6  216.97  4124.5  215.24  4189.3  215.18  4209.4  214.43  4245.5  214.92
  4344.1  213.39  4379.7  212.77  4392.9  213.19  4429.8  212.03  4705.5  208.10
  4720.4  208.72  4740.4  207.39  4790.5  205.96  4890.7  204.08  4970.9  203.67
  4988.9  202.26  4989.2  201.76  4992.9  202.26  5041.4  202.60  5070.5  204.02
  5128.6  205.08  5235.8  207.29  5286.9  207.53  5317.6  208.82  5498.0  212.23
  5512.0  211.94  5532.5  213.12  5547.2  212.41  5573.4  213.68  5722.1  216.43
#Mann=7,-1,0
  3933.6    0.05       0  4124.5    0.04       0  4245.5   0.013       0
  4344.1    0.05       0  4988.9    0.05       0  4992.9    0.05       0
  5128.6    0.04       0
Bank Sta=4988.9,4992.9
Exp/Cntr=0.3,0.1

Type RM Length L Ch R = 1,11192,233,233,233
BEGIN DESCRIPTION:
Mapping XS 0009efcb
END DESCRIPTION:
XS GIS Cut Line= 6
      2495352.03     13519866.09      2495473.57     13518945.92
      2495569.05     13518759.28      2495569.05     13518681.16
      2495503.95     13518559.63      2495417.14     13518030.10
#Sta/Elev= 30
  3557.4  216.89  3740.1  215.27  3895.6  215.77  3994.7  215.34  4256.1  211.14
  4459.8  207.43  4510.2  205.56  4537.6  206.12  4589.5  210.49  4671.7  210.62
  4697.5  208.21  4732.2  207.38  4788.0  210.07  4792.9  210.43  4798.4  208.62
  4815.7  210.26  4821.2  208.37  4844.1  211.13  4846.3  209.78  4881.0  210.85
  4896.1  210.64  4902.2  209.31  4908.1  210.53  4919.0  209.85  4936.3  206.69
  4995.6  204.66  4995.8  204.16  4999.6  204.66  5070.8  208.66  5450.7  216.23
#Mann=7,-1,0
  3557.4    0.05       0  3895.6   0.013       0  3994.7    0.04       0
  4256.1    0.05       0  4788.0    0.04       0  4995.6    0.04       0
  4999.6    0.04       0
Bank Sta=4995.6,4999.6
Exp/Cntr=0.3,0.1

Type RM Length L Ch R = 1,10959,234,234,234
BEGIN DESCRIPTION:
Mapping XS ba919f4e
END DESCRIPTION:
XS GIS Cut Line= 6
      2495386.76     13519926.84      2495529.99     13518954.60
      2495673.22     13518724.56      2495660.20     13518555.29
      2495599.43     13518433.76      2495595.11     13517958.21
#Sta/Elev= 30
  3632.0  216.36  3866.3  214.66  3910.4  215.03  4030.9  216.02  4169.6  216.02
  4399.0  210.33  4513.2  207.90  4594.1  207.10  4612.0  205.30  4667.2  205.80
  4893.5  203.13  4920.3  202.02  4950.3  202.28  4960.4  204.20  4970.4  201.91
  4981.5  202.81  4988.5  201.64  4988.7  201.14  4992.5  201.64  5040.7  202.11
  5058.2  203.58  5063.7  202.40  5080.5  204.49  5086.1  203.98  5108.5  205.82
  5183.9  206.88  5393.3  213.45  5505.2  216.55  5654.3  218.41  5672.0  218.72
#Mann=9,-1,0
  3632.0    0.05       0  3910.4   0.013       0  4030.9    0.04       0
  4399.0    0.05       0  4893.5    0.04       0  4988.5    0.04       0
  4992.5    0.04       0  5393.3    0.03       0  5654.3    0.04       0
Bank Sta=4988.5,4992.5
Exp/Cntr=0.3,0.1

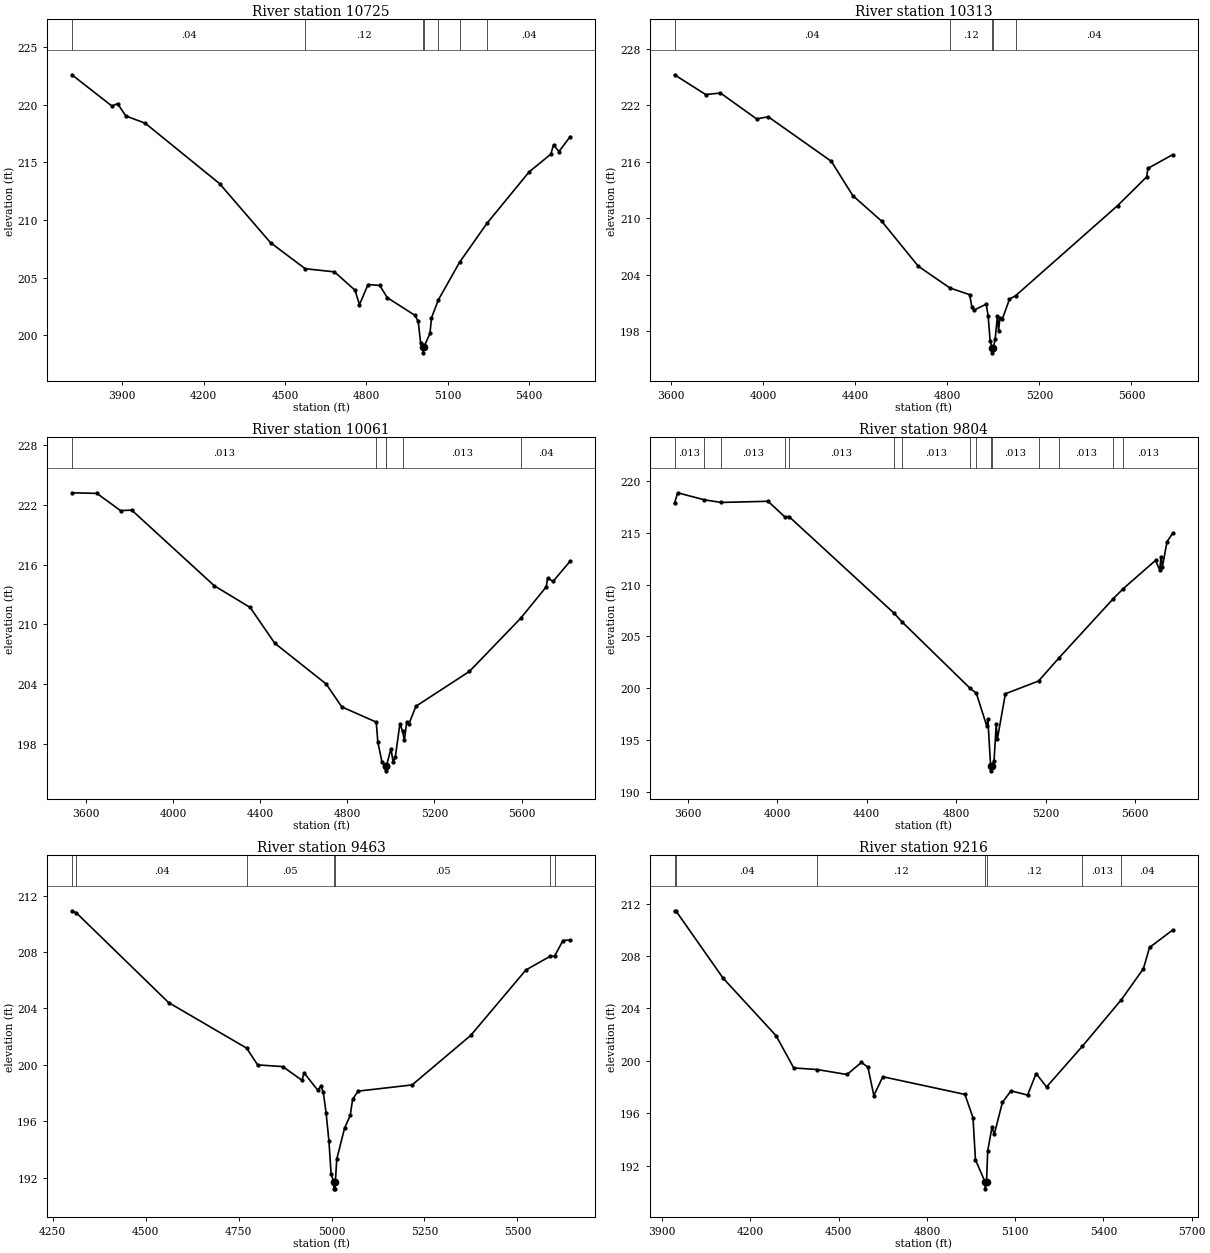
Type RM Length L Ch R = 1,10725,412,412,412
BEGIN DESCRIPTION:
Mapping XS 08cd562b
END DESCRIPTION:
XS GIS Cut Line= 3
      2496181.03     13519879.06      2495898.91     13518637.76
      2495911.93     13518073.57
#Sta/Elev= 30
  3714.5  222.59  3862.2  219.88  3882.7  220.09  3913.5  219.02  3985.0  218.39
  4258.8  213.16  4446.8  208.04  4574.7  205.78  4682.6  205.51  4758.2  203.92
  4774.9  202.67  4806.4  204.41  4849.5  204.33  4877.5  203.27  4978.7  201.75
  4991.3  201.23  5000.2  199.37  5008.2  198.99  5008.5  198.49  5012.2  198.99
  5034.9  200.17  5040.2  201.51  5066.0  203.09  5143.7  206.33  5244.7  209.71
  5400.3  214.17  5480.3  215.71  5490.3  216.51  5510.4  215.94  5551.8  217.23
#Mann=7,-1,0
  3714.5    0.04       0  4574.7    0.12       0  5008.2    0.05       0
  5012.2    0.12       0  5066.0    0.04       0  5143.7    0.12       0
  5244.7    0.04       0
Bank Sta=5008.2,5012.2
Exp/Cntr=0.3,0.1

Type RM Length L Ch R = 1,10313,252,252,252
BEGIN DESCRIPTION:
Mapping XS a5dfe3fd
END DESCRIPTION:
XS GIS Cut Line= 3
      2496380.68     13520039.65      2496237.46     13518672.48
      2496055.17     13517904.26
#Sta/Elev= 30
  3615.5  225.24  3750.9  223.14  3815.1  223.30  3972.1  220.55  4022.4  220.78
  4296.4  216.05  4389.6  212.41  4515.0  209.69  4674.3  204.90  4811.6  202.59
  4897.1  201.88  4907.2  200.55  4917.2  200.25  4969.1  200.87  4977.6  199.60
  4986.4  196.91  4995.8  196.20  4996.1  195.70  4999.8  196.20  5008.1  197.15
  5017.9  199.64  5023.0  198.03  5028.7  199.44  5038.9  199.27  5070.3  201.40
  5097.4  201.78  5539.8  211.34  5665.9  214.39  5671.6  215.30  5779.7  216.76
#Mann=5,-1,0
  3615.5    0.04       0  4811.6    0.12       0  4995.8    0.05       0
  4999.8    0.12       0  5097.4    0.04       0
Bank Sta=4995.8,4999.8
Exp/Cntr=0.3,0.1

Type RM Length L Ch R = 1,10061,257,257,257
BEGIN DESCRIPTION:
Mapping XS 18fee6d5
END DESCRIPTION:
XS GIS Cut Line= 3
      2496775.65     13520052.69      2496428.43     13518550.95
      2496163.68     13517852.18
#Sta/Elev= 30
  3534.7  223.20  3649.5  223.14  3758.1  221.41  3809.5  221.46  4189.2  213.86
  4353.4  211.69  4466.3  208.10  4702.4  204.01  4774.3  201.71  4932.5  200.18
  4939.8  198.18  4959.0  196.16  4975.2  195.79  4975.5  195.29  4979.5  195.79
  5000.1  197.52  5010.3  196.13  5020.1  196.67  5041.1  200.00  5053.7  199.26
  5061.6  198.35  5072.6  200.20  5082.4  199.98  5114.5  201.77  5360.5  205.27
  5595.7  210.60  5713.4  213.76  5719.7  214.65  5744.5  214.30  5823.3  216.34
#Mann=6,-1,0
  3534.7   0.013       0  4932.5    0.05       0  4975.2    0.05       0
  4979.5    0.05       0  5053.7   0.013       0  5595.7    0.04       0
Bank Sta=4975.2,4979.5
Exp/Cntr=0.3,0.1

Type RM Length L Ch R = 1,9804,341,341,341
BEGIN DESCRIPTION:
Mapping XS aa40f659
END DESCRIPTION:
XS GIS Cut Line= 3
      2496992.67     13520074.44      2496706.21     13518685.50
      2496506.56     13517899.94
#Sta/Elev= 30
  3540.6  217.83  3554.6  218.85  3674.1  218.17  3748.7  217.92  3958.7  218.03
  4034.3  216.52  4052.4  216.56  4522.4  207.24  4558.7  206.39  4862.4  200.00
  4890.5  199.52  4936.9  196.37  4942.0  197.02  4954.3  192.54  4954.6  192.04
  4958.6  192.54  4969.6  192.98  4979.4  196.51  4984.5  195.10  5020.3  199.47
  5168.7  200.70  5260.6  202.94  5503.0  208.64  5546.7  209.59  5691.9  212.33
  5711.0  211.40  5716.2  212.65  5722.8  211.74  5743.4  214.14  5769.3  214.96
#Mann=15,-1,0
  3540.6   0.013       0  3674.1    0.05       0  3748.7   0.013       0
  4034.3    0.05       0  4052.4   0.013       0  4522.4    0.05       0
  4558.7   0.013       0  4862.4    0.05       0  4890.5   0.013       0
  4954.3    0.03       0  4958.6   0.013       0  5168.7    0.12       0
  5260.6   0.013       0  5503.0    0.12       0  5546.7   0.013       0
Bank Sta=4954.3,4958.6
Exp/Cntr=0.3,0.1

Type RM Length L Ch R = 1,9463,247,247,247
BEGIN DESCRIPTION:
Mapping XS a7932ced
END DESCRIPTION:
XS GIS Cut Line= 4
      2496897.18     13519288.80      2497094.65     13518829.67
      2496844.65     13518441.65      2496602.46     13518149.98
#Sta/Elev= 30
  4301.5  210.92  4313.2  210.78  4561.6  204.41  4771.5  201.18  4801.1  199.99
  4868.8  199.87  4920.3  198.90  4926.2  199.42  4962.5  198.21  4971.8  198.48
  4977.7  198.07  4985.3  196.59  4992.9  194.61  4998.8  192.25  5005.9  191.70
  5006.2  191.20  5010.0  191.20  5010.3  191.70  5014.0  193.31  5035.1  195.51
  5050.3  196.41  5056.7  197.55  5071.4  198.13  5216.7  198.57  5374.4  202.08
  5522.8  206.72  5587.1  207.68  5600.1  207.71  5622.5  208.81  5642.0  208.85
#Mann=7,-1,0
  4301.5   0.013       0  4313.2    0.04       0  4771.5    0.05       0
  5005.9    0.05       0  5010.3    0.05       0  5587.1   0.013       0
  5600.1    0.12       0
Bank Sta=5005.9,5010.3
Exp/Cntr=0.3,0.1

Type RM Length L Ch R = 1,9216,291,291,291
BEGIN DESCRIPTION:
Mapping XS 92ad12af
END DESCRIPTION:
XS GIS Cut Line= 3
      2498142.85     13518767.97      2497257.42     13518616.06
      2496780.73     13517979.03
#Sta/Elev= 30
  3942.0  211.44  3946.5  211.45  4107.3  206.30  4287.3  201.91  4347.3  199.45
  4426.6  199.33  4528.3  198.95  4577.2  199.87  4599.3  199.52  4619.6  197.34
  4650.0  198.78  4929.1  197.43  4956.6  195.66  4965.0  192.44  4998.2  190.72
  4998.5  190.22  5002.6  190.72  5006.6  193.11  5021.2  194.93  5029.0  194.38
  5056.6  196.82  5085.8  197.70  5142.1  197.38  5171.3  199.02  5206.7  198.00
  5327.8  201.09  5461.3  204.67  5536.0  207.03  5556.8  208.65  5636.0  209.99
#Mann=7,-1,0
  3942.0   0.013       0  3946.5    0.04       0  4426.6    0.12       0
  4998.2    0.05       0  5002.6    0.12       0  5327.8   0.013       0
  5461.3    0.04       0
Bank Sta=4998.2,5002.6
Exp/Cntr=0.3,0.1

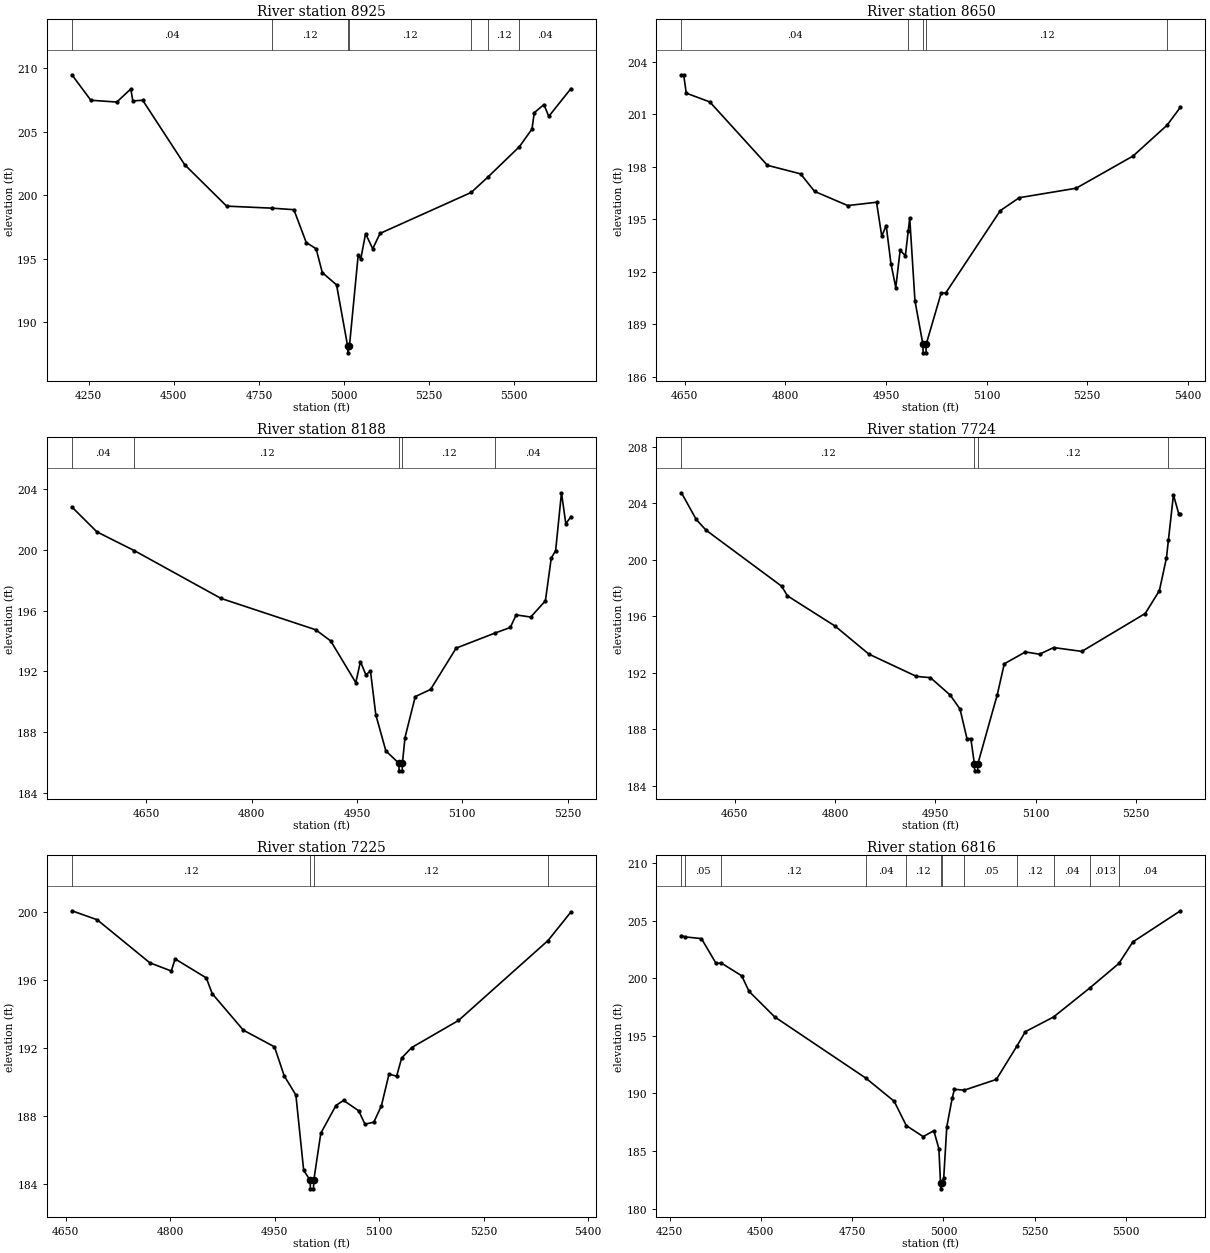
Type RM Length L Ch R = 1,8925,275,275,275
BEGIN DESCRIPTION:
Mapping XS 038aa708
END DESCRIPTION:
XS GIS Cut Line= 3
      2498103.74     13518650.76      2497426.69     13518359.98
      2496936.24     13517821.78
#Sta/Elev= 30
  4201.1  209.50  4256.6  207.49  4332.8  207.35  4373.9  208.38  4379.9  207.44
  4408.9  207.49  4532.1  202.41  4655.3  199.14  4788.8  198.98  4852.7  198.86
  4889.0  196.27  4918.0  195.78  4936.1  193.90  4978.0  192.93  5010.7  188.07
  5011.1  187.57  5015.7  188.07  5041.6  195.31  5049.0  194.97  5063.2  196.97
  5084.1  195.78  5105.7  196.99  5373.3  200.22  5422.6  201.44  5514.8  203.83
  5551.7  205.22  5558.4  206.51  5586.8  207.15  5601.0  206.22  5666.1  208.41
#Mann=7,-1,0
  4201.1    0.04       0  4788.8    0.12       0  5010.7    0.05       0
  5015.7    0.12       0  5373.3   0.013       0  5422.6    0.12       0
  5514.8    0.04       0
Bank Sta=5010.7,5015.7
Exp/Cntr=0.3,0.1

Type RM Length L Ch R = 1,8650,462,462,462
BEGIN DESCRIPTION:
TRIB 5 TO FIFTEENMILE CREEK 12.0
END DESCRIPTION:
XS GIS Cut Line= 3
      2497825.00     13518425.00      2497575.00     13518125.00
      2497324.98     13517874.98
#Sta/Elev= 30
  4645.1  203.26  4648.4  203.26  4652.3  202.21  4687.4  201.71  4773.3  198.09
  4822.8  197.60  4843.6  196.60  4893.1  195.79  4936.0  195.98  4943.8  194.04
  4950.4  194.65  4957.5  192.47  4964.7  191.11  4971.2  193.23  4979.0  192.93
  4983.3  194.35  4985.5  195.08  4993.3  190.35  5005.1  187.88  5005.5  187.38
  5009.8  187.38  5010.1  187.88  5032.4  190.80  5039.2  190.80  5120.5  195.50
  5148.8  196.24  5233.6  196.78  5318.5  198.62  5369.2  200.38  5389.2  201.41
#Mann=5,-1,0
  4645.1    0.04       0  4983.3    0.12       0  5005.1    0.05       0
  5010.1    0.12       0  5369.2   0.013       0
Bank Sta=5005.1,5010.1
Exp/Cntr=0.3,0.1

Type RM Length L Ch R = 1,8188,464,464,464
BEGIN DESCRIPTION:
TRIB 5 TO FIFTEENMILE CREEK 11.0
END DESCRIPTION:
XS GIS Cut Line= 3
      2498224.97     13518224.97      2497925.00     13517875.00
      2497725.03     13517725.02
#Sta/Elev= 30
  4544.0  202.84  4579.6  201.20  4633.0  199.96  4756.3  196.81  4891.3  194.74
  4912.7  194.00  4948.4  191.25  4955.0  192.64  4962.7  191.77  4969.3  192.01
  4976.9  189.13  4991.2  186.75  5009.7  185.93  5010.1  185.43  5014.4  185.43
  5014.8  185.93  5018.5  187.63  5033.1  190.33  5054.9  190.80  5091.4  193.53
  5147.1  194.53  5168.5  194.89  5176.8  195.72  5197.6  195.58  5218.5  196.65
  5226.8  199.46  5233.1  199.97  5241.4  203.78  5247.6  201.73  5254.9  202.21
#Mann=5,-1,0
  4544.0    0.04       0  4633.0    0.12       0  5009.7    0.05       0
  5014.8    0.12       0  5147.1    0.04       0
Bank Sta=5009.7,5014.8
Exp/Cntr=0.3,0.1

Type RM Length L Ch R = 1,7724,499,499,499
BEGIN DESCRIPTION:
TRIB 5 TO FIFTEENMILE CREEK 10.0
END DESCRIPTION:
XS GIS Cut Line= 3
      2498475.00     13517925.00      2498225.00     13517575.00
      2498125.02     13517275.05
#Sta/Elev= 30
  4570.1  204.74  4592.2  202.85  4607.0  202.09  4720.0  198.13  4728.6  197.45
  4799.9  195.31  4850.3  193.33  4921.6  191.75  4942.5  191.66  4972.0  190.43
  4986.7  189.44  4997.1  187.35  5002.9  187.35  5008.2  185.57  5008.6  185.07
  5013.0  185.07  5013.4  185.57  5042.4  190.45  5052.9  192.64  5084.5  193.48
  5105.6  193.32  5126.7  193.79  5168.9  193.52  5263.7  196.20  5284.8  197.81
  5295.4  200.12  5298.4  201.40  5305.9  204.59  5313.8  203.26  5316.4  203.26
#Mann=4,-1,0
  4570.1    0.12       0  5008.2    0.05       0  5013.4    0.12       0
  5298.4   0.013       0
Bank Sta=5008.2,5013.4
Exp/Cntr=0.3,0.1

Type RM Length L Ch R = 1,7225,409,409,409
BEGIN DESCRIPTION:
TRIB 5 TO FIFTEENMILE CREEK 9.0
END DESCRIPTION:
XS GIS Cut Line= 3
      2498775.00     13517675.00      2498625.00     13517375.00
      2498475.00     13517025.00
#Sta/Elev= 30
  4658.9  200.08  4695.2  199.55  4770.7  197.02  4801.5  196.54  4807.0  197.25
  4851.8  196.13  4860.2  195.21  4904.9  193.06  4949.6  192.08  4963.6  190.37
  4980.3  189.25  4991.5  184.82  5000.8  184.23  5001.2  183.73  5005.6  183.73
  5006.0  184.23  5016.1  187.00  5037.8  188.63  5048.7  188.93  5070.5  188.32
  5079.5  187.53  5092.2  187.65  5103.1  188.62  5114.0  190.48  5124.9  190.35
  5132.1  191.42  5146.6  192.04  5213.7  193.63  5342.2  198.33  5375.1  200.01
#Mann=4,-1,0
  4658.9    0.12       0  5000.8    0.05       0  5006.0    0.12       0
  5342.2    0.04       0
Bank Sta=5000.8,5006
Exp/Cntr=0.3,0.1

Type RM Length L Ch R = 1,6816,280,280,280
BEGIN DESCRIPTION:
Mapping XS 713df5e6
END DESCRIPTION:
XS GIS Cut Line= 4
      2498993.53     13517769.72      2498963.15     13517214.15
      2498763.50     13516945.05      2498303.47     13516827.87
#Sta/Elev= 30
  4282.6  203.73  4292.7  203.61  4337.4  203.46  4377.5  201.30  4391.5  201.34
  4447.6  200.23  4467.6  198.88  4537.7  196.66  4787.1  191.34  4865.1  189.32
  4898.1  187.21  4944.4  186.25  4973.6  186.76  4987.4  185.20  4991.9  182.21
  4992.3  181.71  4997.1  182.21  5000.7  182.69  5009.1  187.11  5023.7  189.57
  5029.9  190.36  5057.1  190.29  5144.7  191.22  5200.7  194.10  5224.1  195.37
  5301.4  196.65  5402.1  199.21  5480.2  201.30  5518.4  203.17  5648.8  205.88
#Mann=12,-1,0
  4282.6    0.04       0  4292.7    0.05       0  4391.5    0.12       0
  4787.1    0.04       0  4898.1    0.12       0  4991.9    0.05       0
  4997.1    0.12       0  5057.1    0.05       0  5200.7    0.12       0
  5301.4    0.04       0  5402.1   0.013       0  5480.2    0.04       0
Bank Sta=4991.9,4997.1
Exp/Cntr=0.3,0.1

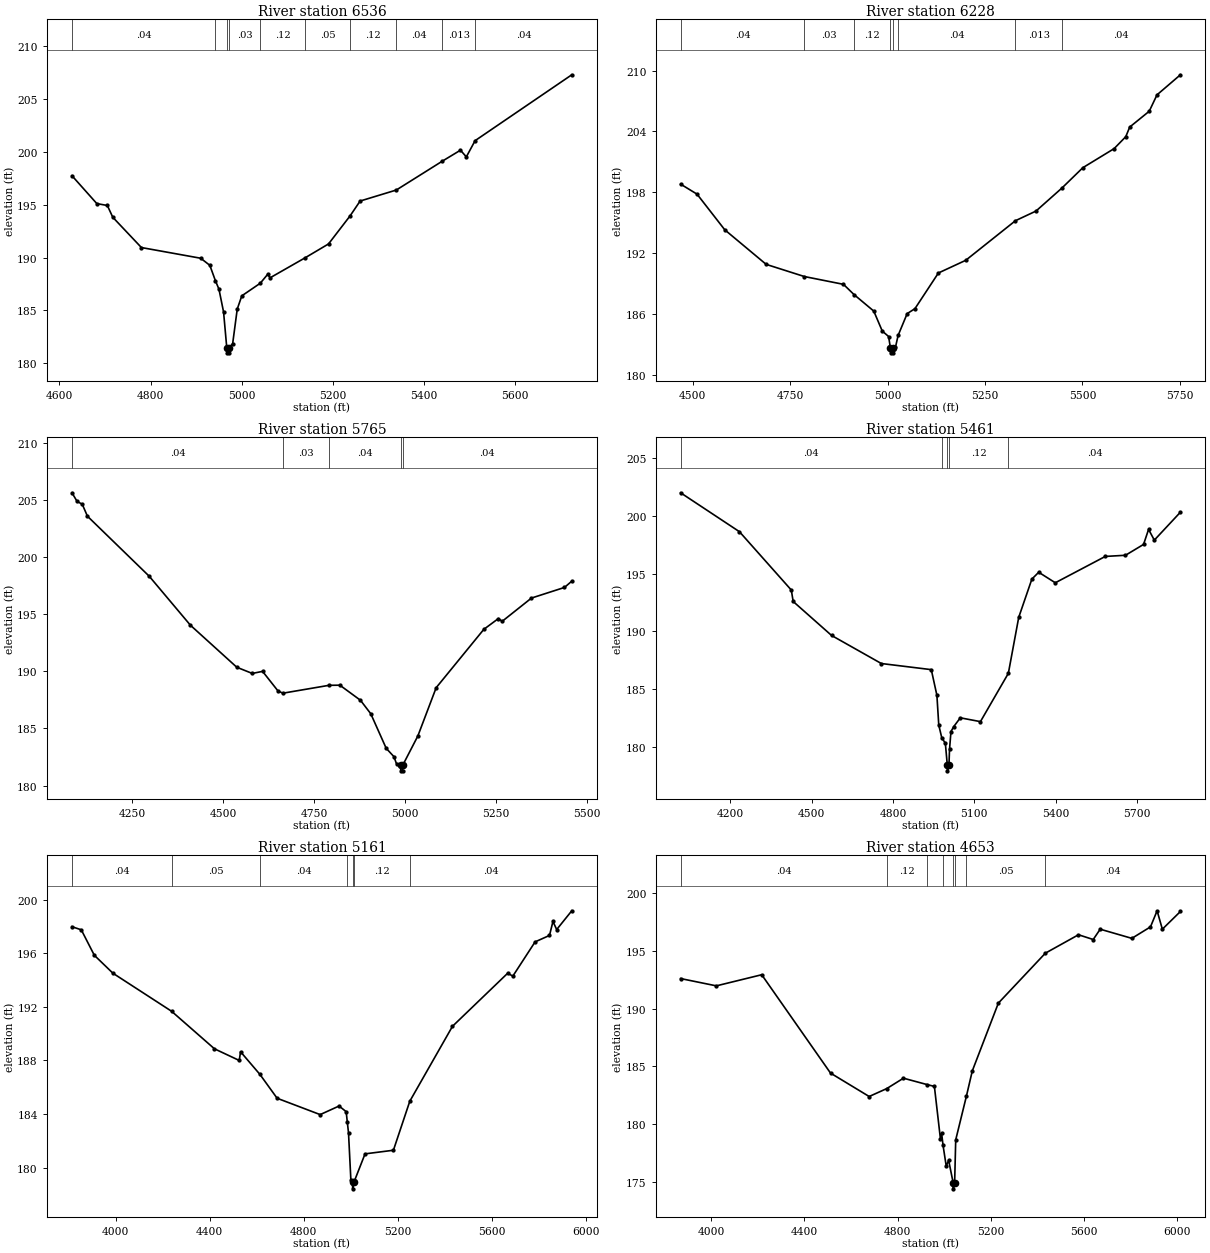
Type RM Length L Ch R = 1,6536,308,308,308
BEGIN DESCRIPTION:
4843
END DESCRIPTION:
XS GIS Cut Line= 4
      2499336.54     13516993.86      2499226.59     13516944.21
      2498761.97     13516922.93      2498269.49     13516788.29
#Sta/Elev= 30
  4627.5  197.72  4682.0  195.09  4705.1  194.91  4717.0  193.80  4779.8  190.94
  4909.9  189.93  4929.9  189.26  4942.2  187.80  4949.9  187.01  4960.0  184.86
  4967.0  181.50  4967.5  181.00  4972.5  181.00  4972.9  181.50  4980.0  181.88
  4990.0  185.13  5000.0  186.38  5040.5  187.57  5056.9  188.42  5061.9  188.08
  5138.8  189.97  5190.2  191.28  5237.7  193.94  5259.5  195.33  5338.9  196.37
  5440.0  199.10  5479.6  200.13  5492.5  199.50  5511.7  201.03  5723.8  207.25
#Mann=10,-1,0
  4627.5    0.04       0  4942.2    0.03       0  4967.0    0.03       0
  4972.9    0.03       0  5040.5    0.12       0  5138.8    0.05       0
  5237.7    0.12       0  5338.9    0.04       0  5440.0   0.013       0
  5511.7    0.04       0
Bank Sta=4967,4972.9
Exp/Cntr=0.3,0.1

Type RM Length L Ch R = 1,6228,463,463,463
BEGIN DESCRIPTION:
TRIB 5 TO FIFTEENMILE CREEK 7.0
END DESCRIPTION:
XS GIS Cut Line= 3
      2499374.98     13516974.99      2498975.00     13516625.00
      2498225.05     13516675.00
#Sta/Elev= 30
  4468.5  198.80  4510.7  197.81  4581.9  194.29  4688.2  190.88  4786.2  189.68
  4886.6  188.91  4913.7  187.90  4964.4  186.27  4986.2  184.30  5002.5  183.76
  5007.0  182.65  5007.5  182.15  5012.5  182.15  5013.0  182.65  5020.0  182.69
  5026.9  183.87  5050.1  186.02  5070.1  186.51  5130.3  190.03  5200.4  191.28
  5328.1  195.19  5380.8  196.14  5447.6  198.42  5501.1  200.42  5581.3  202.30
  5611.3  203.48  5621.4  204.43  5671.5  205.99  5691.5  207.61  5751.6  209.59
#Mann=8,-1,0
  4468.5    0.04       0  4786.2    0.03       0  4913.7    0.12       0
  5007.0    0.05       0  5013.0    0.12       0  5026.9    0.04       0
  5328.1   0.013       0  5447.6    0.04       0
Bank Sta=5007,5013
Exp/Cntr=0.3,0.1

Type RM Length L Ch R = 1,5765,304,304,304
BEGIN DESCRIPTION:
TRIB 5 TO FIFTEENMILE CREEK 6.0
END DESCRIPTION:
XS GIS Cut Line= 3
      2499674.98     13516824.98      2499025.00     13516175.00
      2498574.97     13516225.00
#Sta/Elev= 30
  4085.3  205.64  4099.4  204.88  4113.5  204.64  4127.7  203.59  4297.4  198.33
  4410.5  194.04  4537.8  190.36  4580.2  189.82  4608.5  190.00  4651.0  188.28
  4664.4  188.09  4791.0  188.78  4820.7  188.79  4877.2  187.47  4905.5  186.29
  4947.9  183.26  4969.1  182.53  4976.2  181.90  4987.4  181.79  4987.9  181.29
  4992.9  181.29  4993.4  181.79  5034.7  184.34  5085.0  188.57  5215.8  193.68
  5256.0  194.63  5266.1  194.38  5346.6  196.42  5437.2  197.35  5457.3  197.90
#Mann=5,-1,0
  4085.3    0.04       0  4664.4    0.03       0  4791.0    0.04       0
  4987.4    0.04       0  4993.4    0.04       0
Bank Sta=4987.4,4993.4
Exp/Cntr=0.3,0.1

Type RM Length L Ch R = 1,5461,300,300,300
BEGIN DESCRIPTION:
Mapping XS ec9d7945
END DESCRIPTION:
XS GIS Cut Line= 4
      2499935.36     13516571.77      2499384.16     13515990.19
      2499002.21     13515886.02      2498394.56     13516107.38
#Sta/Elev= 30
  4016.3  202.00  4233.4  198.63  4424.7  193.58  4431.6  192.59  4573.2  189.65
  4756.8  187.22  4941.1  186.69  4961.8  184.47  4968.7  181.89  4980.0  180.77
  4992.9  180.33  5000.2  178.43  5000.7  177.93  5006.3  178.43  5008.4  179.79
  5013.7  181.33  5024.0  181.76  5048.1  182.52  5122.4  182.19  5225.4  186.37
  5263.7  191.22  5312.2  194.53  5337.4  195.12  5398.6  194.21  5583.0  196.49
  5657.5  196.59  5724.2  197.53  5742.7  198.83  5763.9  197.90  5860.2  200.32
#Mann=5,-1,0
  4016.3    0.04       0  4980.0    0.12       0  5000.2    0.05       0
  5006.3    0.12       0  5225.4    0.04       0
Bank Sta=5000.2,5006.3
Exp/Cntr=0.3,0.1

Type RM Length L Ch R = 1,5161,508,508,508
BEGIN DESCRIPTION:
Mapping XS 3ac7361c
END DESCRIPTION:
XS GIS Cut Line= 4
      2500299.93     13516085.66      2499410.20     13515629.94
      2498997.87     13515669.01      2498329.70     13515911.98
#Sta/Elev= 30
  3814.4  197.98  3854.0  197.75  3909.4  195.85  3988.5  194.51  4238.0  191.67
  4420.1  188.87  4525.5  188.00  4531.1  188.65  4613.4  186.96  4686.5  185.18
  4869.5  183.96  4949.9  184.60  4980.0  184.18  4984.7  183.44  4990.0  182.60
  5000.1  179.06  5007.1  178.92  5007.6  178.42  5013.2  178.92  5060.3  181.03
  5180.9  181.30  5250.6  184.96  5432.0  190.55  5666.1  194.50  5688.8  194.30
  5783.2  196.85  5844.4  197.33  5859.1  198.37  5875.0  197.77  5939.2  199.17
#Mann=7,-1,0
  3814.4    0.04       0  4238.0    0.05       0  4613.4    0.04       0
  4984.7    0.12       0  5007.1    0.05       0  5013.2    0.12       0
  5250.6    0.04       0
Bank Sta=5007.1,5013.2
Exp/Cntr=0.3,0.1

Type RM Length L Ch R = 1,4653,274,274,274
BEGIN DESCRIPTION:
Mapping XS e683353e
END DESCRIPTION:
XS GIS Cut Line= 4
      2500174.04     13515534.45      2499188.84     13515291.40
      2498815.58     13515360.85      2498191.97     13515780.92
#Sta/Elev= 30
  3868.5  192.59  4022.0  191.96  4216.8  192.92  4512.3  184.43  4678.2  182.41
  4753.5  183.09  4825.4  183.99  4926.7  183.44  4958.3  183.28  4984.3  178.74
  4989.4  179.23  4995.3  178.22  5009.2  176.39  5019.4  176.91  5039.1  174.94
  5039.6  174.44  5045.2  174.94  5049.9  178.67  5095.8  182.44  5121.1  184.62
  5233.0  190.47  5434.8  194.78  5577.1  196.37  5640.3  195.96  5670.3  196.85
  5806.2  196.06  5886.2  197.05  5914.7  198.44  5937.2  196.85  6014.8  198.38
#Mann=8,-1,0
  3868.5    0.04       0  4753.5    0.12       0  4926.7    0.05       0
  4995.3    0.12       0  5039.1    0.05       0  5045.2    0.12       0
  5095.8    0.05       0  5434.8    0.04       0
Bank Sta=5039.1,5045.2
Exp/Cntr=0.3,0.1

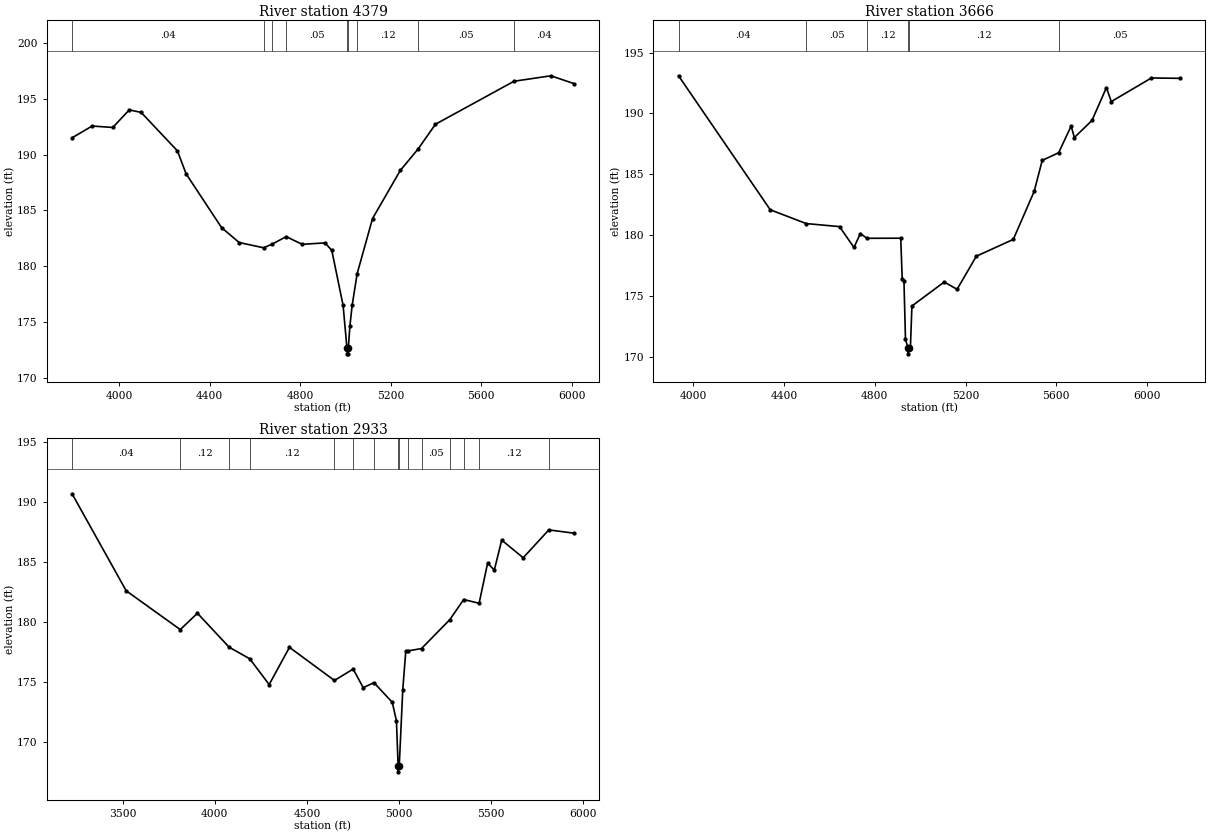
Type RM Length L Ch R = 1,4379,713,713,713
BEGIN DESCRIPTION:
Mapping XS e92a2f3c
END DESCRIPTION:
XS GIS Cut Line= 4
      2500187.11     13515365.19      2499175.82     13515057.03
      2498854.64     13515052.69      2498225.29     13515608.26
#Sta/Elev= 30
  3791.7  191.52  3880.4  192.58  3971.6  192.45  4044.6  194.03  4097.1  193.80
  4257.3  190.35  4295.7  188.29  4452.5  183.46  4530.4  182.12  4638.4  181.65
  4675.0  181.97  4738.3  182.65  4808.8  181.96  4909.7  182.09  4939.7  181.42
  4989.7  176.47  5006.7  172.63  5007.2  172.13  5012.3  172.13  5012.8  172.63
  5019.7  174.64  5029.7  176.48  5051.8  179.33  5119.7  184.27  5242.3  188.59
  5320.9  190.51  5397.9  192.74  5745.3  196.60  5908.2  197.09  6009.6  196.39
#Mann=9,-1,0
  3791.7    0.04       0  4638.4    0.12       0  4675.0    0.04       0
  4738.3    0.05       0  5006.7    0.05       0  5012.8    0.05       0
  5051.8    0.12       0  5320.9    0.05       0  5745.3    0.04       0
Bank Sta=5006.7,5012.8
Exp/Cntr=0.3,0.1

Type RM Length L Ch R = 1,3666,733,733,733
BEGIN DESCRIPTION:
TRIB 5 TO FIFTEENMILE CREEK 2.0
END DESCRIPTION:
XS GIS Cut Line= 3
      2499875.02     13515175.03      2499186.22     13514384.53
      2498350.70     13515190.66
#Sta/Elev= 30
  3936.3  193.09  4340.3  182.08  4498.7  180.95  4645.1  180.70  4708.7  178.99
  4737.1  180.13  4766.3  179.74  4914.7  179.75  4921.3  176.36  4928.9  176.23
  4935.6  171.44  4946.7  170.75  4947.2  170.25  4952.9  170.75  4957.4  170.84
  4964.0  174.18  5106.2  176.15  5162.8  175.55  5247.7  178.27  5410.3  179.65
  5502.2  183.59  5537.7  186.14  5610.0  186.77  5665.0  188.96  5679.2  188.02
  5756.8  189.42  5820.4  192.12  5841.7  190.97  6018.5  192.91  6145.8  192.88
#Mann=6,-1,0
  3936.3    0.04       0  4498.7    0.05       0  4766.3    0.12       0
  4946.7    0.05       0  4952.9    0.12       0  5610.0    0.05       0
Bank Sta=4946.7,4952.9
Exp/Cntr=0.3,0.1

Type RM Length L Ch R = 1,2933,0,0,0
BEGIN DESCRIPTION:
TRIB 5 TO FIFTEENMILE CREEK 1.0
END DESCRIPTION:
XS GIS Cut Line= 4
      2499931.44     13514977.03      2499356.75     13514160.96
      2498684.36     13514195.44      2498202.17     13515131.11
#Sta/Elev= 30
  3225.0  190.67  3518.8  182.59  3812.3  179.36  3905.6  180.72  4077.8  177.89
  4189.3  176.93  4295.0  174.78  4405.1  177.88  4649.3  175.12  4750.9  176.07
  4805.6  174.52  4863.7  174.94  4963.4  173.30  4985.9  171.75  4994.9  168.01
  4995.4  167.51  5001.1  168.01  5020.2  174.35  5036.7  177.59  5048.2  177.58
  5122.0  177.78  5275.3  180.18  5350.9  181.86  5434.7  181.55  5480.9  184.90
  5517.1  184.31  5557.4  186.81  5673.9  185.34  5813.0  187.66  5949.0  187.39
#Mann=15,-1,0
  3225.0    0.04       0  3812.3    0.12       0  4077.8    0.03       0
  4189.3    0.12       0  4649.3    0.05       0  4750.9    0.12       0
  4863.7    0.05       0  4994.9    0.05       0  5001.1    0.05       0
  5048.2    0.12       0  5122.0    0.05       0  5275.3    0.12       0
  5350.9    0.05       0  5434.7    0.12       0  5813.0    0.05       0
Bank Sta=4994.9,5001.1
Exp/Cntr=0.3,0.1

Chan Stop Cuts=-1