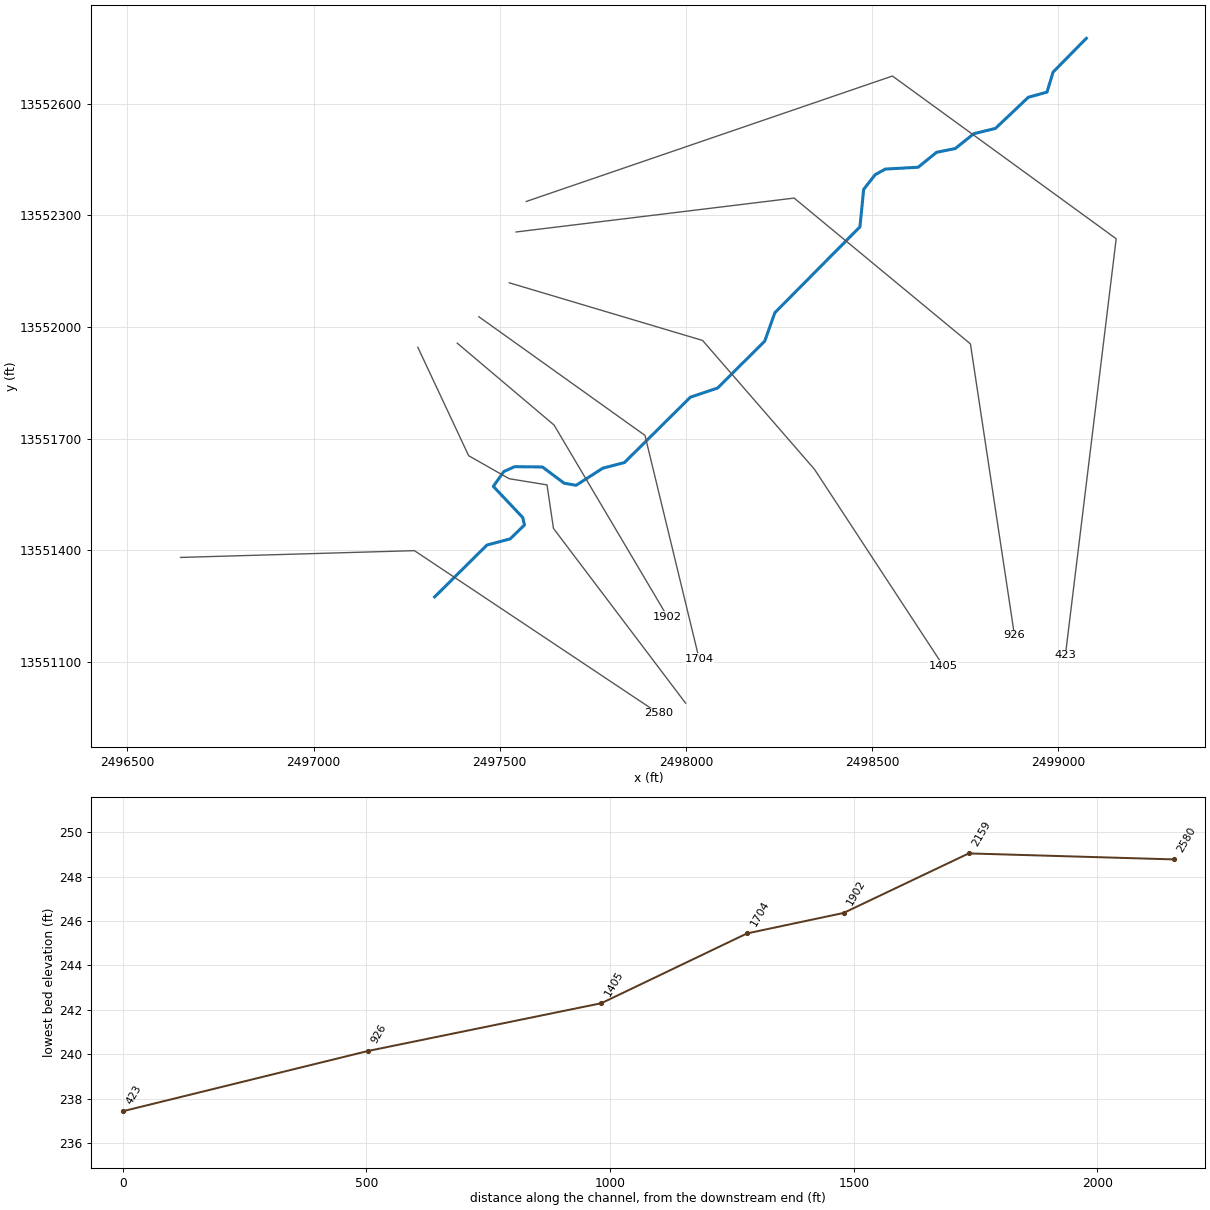
--- TRIB 5 TO FIVEMILE CREEK.prj (project) ---

Proj Title=TRIB 5 TO FIVEMILE CREEK Base Level Engineering
Current Plan=p01
Default Exp/Contr=0.3,0.1
English Units
Geom File=g01
Flow File=f01
Plan File=p01
BEGIN DESCRIPTION:
TRIB 5 TO FIVEMILE CREEK
END DESCRIPTION:

--- TRIB 5 TO FIVEMILE CREEK.p01 (plan) ---

Plan Title=Multiple Run
Short Identifier=Multiple
Geom File=g01
Flow File=f01
Subcritical Flow
K Sum by GR= 0
Std Step Tol= 0.01
Critical Tol= 0.01
Num of Std Step Trials= 20
Max Error Tol= 0.3
Flow Tol Ratio= 0.001
Split Flow NTrial= 30
Split Flow Tol= 0.02
Split Flow Ratio= 0.02
Log Output Level= 0
Friction Slope Method= 1
Unsteady Friction Slope Method= 2
Unsteady Bridges Friction Slope Method= 1
Parabolic Critical Depth
Global Vel Dist=  1 , 1 , 1
Global Log Level= 0
CheckData=True
Encroach Param= -1, 0, 0, 0
BEGIN DESCRIPTION:
Multiple Run
END DESCRIPTION:

--- TRIB 5 TO FIVEMILE CREEK.f01 (steady flow) ---

Flow Title=Multiple
Number of Profiles=7
Profile Names=10-year,25-year,50-year,1pct_min,100-year,1pct_plu,500-year
River Rch & RM= TRIB 5 TO FIVEMI,Reach-1,2580
     351     543     709     450     897    1790    1419
Boundary for River Rch & Prof#=TRIB 5 TO FIVEMI,Reach-1,1
Up Type=0
Dn Type=3
Dn Slope=0.005
Boundary for River Rch & Prof#=TRIB 5 TO FIVEMI,Reach-1,2
Up Type=0
Dn Type=3
Dn Slope=0.005
Boundary for River Rch & Prof#=TRIB 5 TO FIVEMI,Reach-1,3
Up Type=0
Dn Type=3
Dn Slope=0.005
Boundary for River Rch & Prof#=TRIB 5 TO FIVEMI,Reach-1,4
Up Type=0
Dn Type=3
Dn Slope=0.005
Boundary for River Rch & Prof#=TRIB 5 TO FIVEMI,Reach-1,5
Up Type=0
Dn Type=3
Dn Slope=0.005
Boundary for River Rch & Prof#=TRIB 5 TO FIVEMI,Reach-1,6
Up Type=0
Dn Type=3
Dn Slope=0.005
Boundary for River Rch & Prof#=TRIB 5 TO FIVEMI,Reach-1,7
Up Type=0
Dn Type=3
Dn Slope=0.005

--- TRIB 5 TO FIVEMILE CREEK.g01 (geometry) ---

Geom Title=Existing Conditions

River Reach=TRIB 5 TO FIVEMI,Reach-1
Reach XY= 30
      2497325.00     13551275.00      2497465.35     13551414.23
      2497527.86     13551430.86      2497566.15     13551468.05
      2497561.58     13551488.23      2497482.53     13551571.88
      2497510.85     13551611.66      2497539.93     13551624.76
      2497614.44     13551623.88      2497672.82     13551580.38
      2497704.83     13551574.71      2497776.74     13551620.75
      2497834.68     13551635.76      2498011.79     13551811.37
      2498084.68     13551835.78      2498211.37     13551961.79
      2498238.63     13552038.21      2498467.14     13552268.83
      2498477.07     13552369.31      2498507.79     13552408.73
      2498535.31     13552423.91      2498623.41     13552428.83
      2498672.82     13552468.88      2498723.28     13552479.16
      2498772.81     13552518.90      2498831.05     13552533.16
      2498919.26     13552616.70      2498969.39     13552630.61
      2498985.83     13552684.42      2499075.00     13552775.00

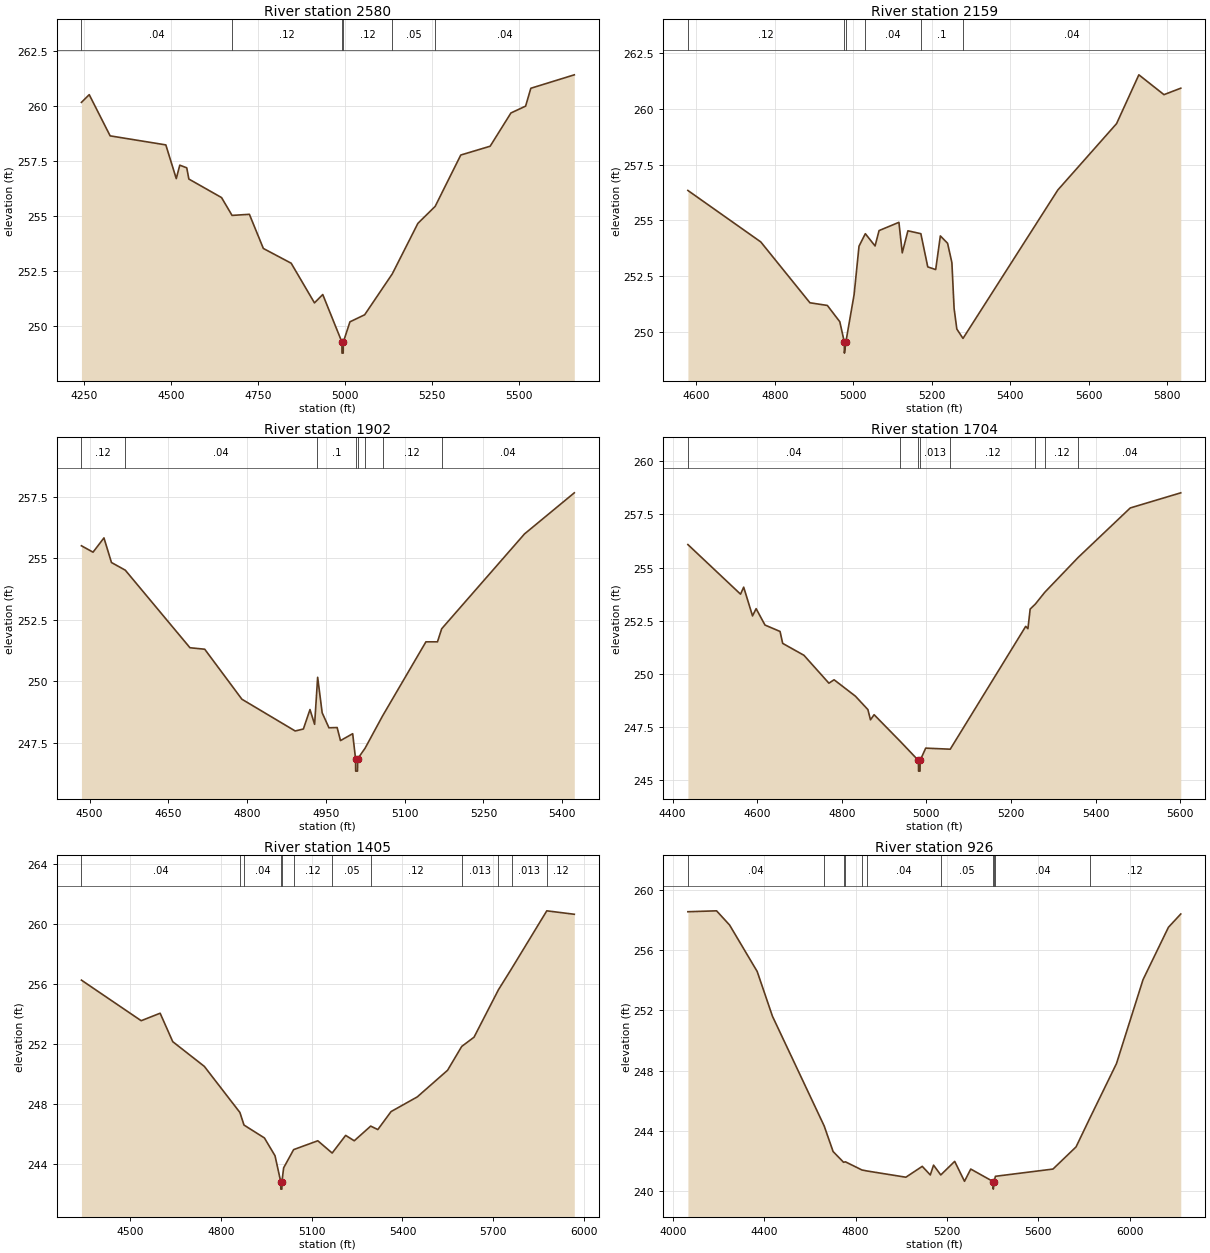
Type RM Length L Ch R = 1,2580,421,421,421
BEGIN DESCRIPTION:
LGII4526
END DESCRIPTION:
XS GIS Cut Line= 3
      2496642.56     13551381.02      2497270.70     13551399.23
      2497926.19     13550962.24
#Sta/Elev= 30
  4242.9  260.15  4265.3  260.50  4325.4  258.63  4485.4  258.22  4515.4  256.69
  4525.5  257.30  4545.5  257.18  4551.6  256.67  4645.5  255.83  4675.7  255.02
  4725.5  255.07  4765.6  253.52  4845.6  252.85  4912.5  251.05  4936.3  251.43
  4991.4  249.27  4991.6  248.77  4995.1  248.77  4995.4  249.27  5014.4  250.19
  5056.7  250.51  5136.2  252.37  5209.7  254.66  5259.3  255.43  5332.9  257.76
  5417.3  258.16  5477.1  259.67  5519.2  259.98  5534.2  260.79  5659.1  261.40
#Mann=6,-1,0
  4242.9    0.04       0  4675.7    0.12       0  4991.4    0.05       0
  4995.4    0.12       0  5136.2    0.05       0  5259.3    0.04       0
Bank Sta=4991.4,4995.4
Exp/Cntr=0.3,0.1

Type RM Length L Ch R = 1,2159,257,257,257
BEGIN DESCRIPTION:
LGII4525
END DESCRIPTION:
XS GIS Cut Line= 6
      2497279.83     13551945.43      2497416.37     13551654.14
      2497525.11     13551592.41      2497626.76     13551575.86
      2497644.08     13551458.96      2497998.84     13550989.79
#Sta/Elev= 30
  4578.4  256.34  4764.2  254.03  4889.4  251.30  4933.8  251.18  4965.5  250.45
  4977.0  249.54  4977.3  249.04  4981.0  249.54  5002.0  251.67  5014.5  253.84
  5030.6  254.40  5055.4  253.85  5065.6  254.54  5116.2  254.91  5124.7  253.54
  5139.1  254.53  5172.1  254.40  5189.7  252.91  5209.9  252.79  5221.8  254.30
  5240.2  253.97  5251.2  253.10  5256.8  251.05  5263.8  250.12  5279.5  249.70
  5521.1  256.36  5670.9  259.34  5727.7  261.53  5791.7  260.64  5834.5  260.93
#Mann=6,-1,0
  4578.4    0.12       0  4977.0    0.05       0  4981.0    0.12       0
  5030.6    0.04       0  5172.1     0.1       0  5279.5    0.04       0
Bank Sta=4977,4981
Exp/Cntr=0.3,0.1

Type RM Length L Ch R = 1,1902,198,198,198
BEGIN DESCRIPTION:
4829
END DESCRIPTION:
XS GIS Cut Line= 3
      2497385.66     13551956.42      2497645.67     13551736.60
      2497950.32     13551221.76
#Sta/Elev= 30
  4484.3  255.51  4506.4  255.25  4527.2  255.83  4541.5  254.83  4567.8  254.52
  4691.0  251.37  4719.1  251.31  4789.9  249.28  4891.4  247.99  4907.0  248.07
  4919.6  248.86  4928.4  248.26  4932.9  249.74  4934.2  250.17  4942.8  248.73
  4955.7  248.12  4971.3  248.13  4977.7  247.60  5000.9  247.88  5006.4  246.86
  5006.6  246.36  5010.1  246.36  5010.4  246.86  5024.5  247.29  5057.8  248.60
  5140.4  251.61  5162.4  251.61  5170.4  252.14  5328.1  255.99  5423.0  257.66
#Mann=8,-1,0
  4484.3    0.12       0  4567.8    0.04       0  4932.9     0.1       0
  5006.4    0.05       0  5010.4     0.1       0  5024.5    0.04       0
  5057.8    0.12       0  5170.4    0.04       0
Bank Sta=5006.4,5010.4
Exp/Cntr=0.3,0.1

Type RM Length L Ch R = 1,1704,299,299,299
BEGIN DESCRIPTION:
LGII4524
END DESCRIPTION:
XS GIS Cut Line= 3
      2497443.71     13552027.39      2497889.78     13551708.77
      2498035.20     13551108.92
#Sta/Elev= 30
  4436.0  256.08  4560.5  253.75  4567.9  254.08  4588.8  252.73  4597.3  253.07
  4618.3  252.30  4653.9  252.00  4660.1  251.44  4710.4  250.88  4769.4  249.57
  4781.7  249.73  4832.1  248.96  4861.6  248.33  4867.7  247.85  4876.3  248.09
  4938.0  246.84  4981.1  245.94  4981.4  245.44  4984.9  245.44  4985.1  245.94
  4998.3  246.52  5056.3  246.47  5234.8  252.24  5240.0  252.13  5245.3  253.05
  5257.7  253.29  5279.9  253.84  5358.5  255.47  5482.0  257.80  5601.4  258.51
#Mann=8,-1,0
  4436.0    0.04       0  4938.0   0.013       0  4981.1    0.03       0
  4985.1   0.013       0  5056.3    0.12       0  5257.7    0.04       0
  5279.9    0.12       0  5358.5    0.04       0
Bank Sta=4981.1,4985.1
Exp/Cntr=0.3,0.1

Type RM Length L Ch R = 1,1405,479,479,479
BEGIN DESCRIPTION:
LGII4523
END DESCRIPTION:
XS GIS Cut Line= 4
      2497525.60     13552118.45      2498044.55     13551963.68
      2498344.98     13551617.73      2498690.38     13551090.53
#Sta/Elev= 30
  4338.3  256.26  4535.9  253.55  4598.6  254.05  4640.3  252.15  4744.7  250.50
  4862.4  247.42  4875.9  246.58  4943.4  245.72  4978.5  244.53  4997.4  242.80
  4997.7  242.30  5001.2  242.30  5001.4  242.80  5007.0  243.72  5040.1  244.94
  5120.0  245.53  5167.5  244.71  5212.1  245.89  5240.6  245.53  5294.9  246.51
  5318.5  246.28  5362.3  247.48  5448.9  248.46  5549.2  250.24  5595.9  251.83
  5636.7  252.45  5717.5  255.62  5761.6  257.05  5877.3  260.89  5968.3  260.66
#Mann=12,-1,0
  4338.3    0.04       0  4862.4    0.05       0  4875.9    0.04       0
  4997.4    0.04       0  5001.4    0.04       0  5040.1    0.12       0
  5167.5    0.05       0  5294.9    0.12       0  5595.9   0.013       0
  5717.5    0.12       0  5761.6   0.013       0  5877.3    0.12       0
Bank Sta=4997.4,5001.4
Exp/Cntr=0.3,0.1

Type RM Length L Ch R = 1,926,503,503,503
BEGIN DESCRIPTION:
LGII4522
END DESCRIPTION:
XS GIS Cut Line= 4
      2497543.82     13552255.01      2498290.35     13552346.05
      2498763.76     13551954.58      2498882.11     13551171.64
#Sta/Elev= 30
  4066.0  258.54  4191.5  258.60  4248.5  257.66  4369.4  254.58  4436.3  251.61
  4662.7  244.34  4701.9  242.64  4747.7  241.93  4755.8  241.96  4828.0  241.42
  4851.6  241.35  5020.5  240.94  5092.2  241.66  5127.4  241.09  5141.7  241.74
  5173.3  241.09  5234.2  241.99  5277.2  240.67  5304.5  241.48  5402.9  240.65
  5403.1  240.15  5406.9  240.65  5412.5  241.00  5664.6  241.48  5765.7  242.95
  5825.3  244.83  5942.6  248.47  6059.0  254.04  6170.2  257.51  6224.2  258.39
#Mann=11,-1,0
  4066.0    0.04       0  4662.7    0.05       0  4747.7    0.12       0
  4755.8    0.04       0  4828.0    0.05       0  4851.6    0.04       0
  5173.3    0.05       0  5402.9    0.04       0  5406.9    0.05       0
  5412.5    0.04       0  5825.3    0.12       0
Bank Sta=5402.9,5406.9
Exp/Cntr=0.3,0.1

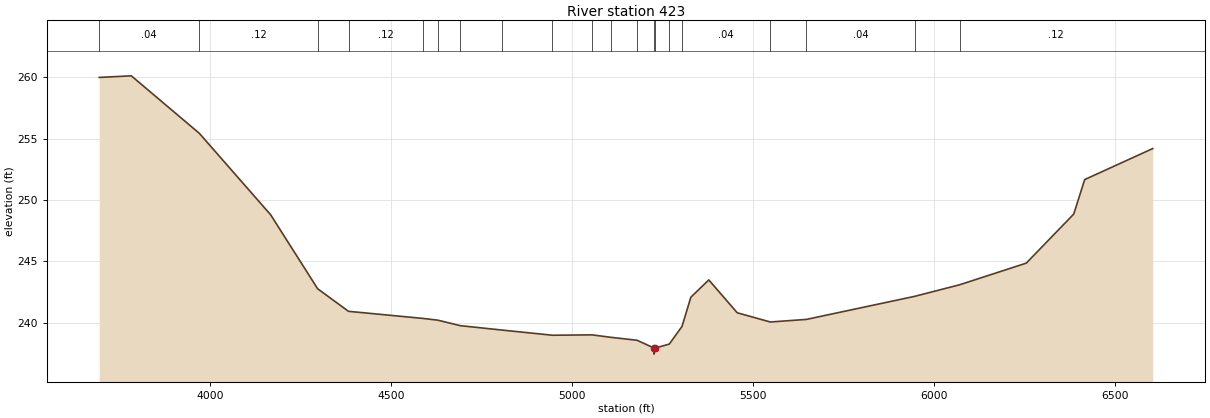
Type RM Length L Ch R = 1,423,0,0,0
BEGIN DESCRIPTION:
LGII4521
END DESCRIPTION:
XS GIS Cut Line= 4
      2497571.15     13552336.95      2498554.37     13552673.79
      2499155.24     13552236.80      2499018.86     13551118.48
#Sta/Elev= 30
  3694.2  260.00  3782.8  260.13  3970.7  255.44  4167.6  248.80  4297.3  242.77
  4382.5  240.93  4588.4  240.35  4628.9  240.21  4691.4  239.76  4806.8  239.40
  4945.7  238.98  5055.1  239.01  5107.0  238.81  5179.3  238.57  5225.9  237.94
  5226.1  237.44  5229.9  237.94  5268.3  238.26  5303.4  239.70  5327.8  242.08
  5377.3  243.49  5455.9  240.81  5547.2  240.06  5646.8  240.27  5945.7  242.15
  6070.5  243.10  6254.0  244.86  6385.0  248.86  6415.2  251.67  6603.1  254.20
#Mann=20,-1,0
  3694.2    0.04       0  3970.7    0.12       0  4297.3    0.03       0
  4382.5    0.12       0  4588.4    0.05       0  4628.9    0.12       0
  4691.4   0.013       0  4806.8   0.013       0  4945.7   0.013       0
  5055.1    0.04       0  5107.0   0.013       0  5179.3    0.04       0
  5225.9    0.03       0  5229.9    0.04       0  5268.3   0.013       0
  5303.4    0.04       0  5547.2   0.013       0  5646.8    0.04       0
  5945.7    0.05       0  6070.5    0.12       0
Bank Sta=5225.9,5229.9
Exp/Cntr=0.3,0.1

Chan Stop Cuts=-1