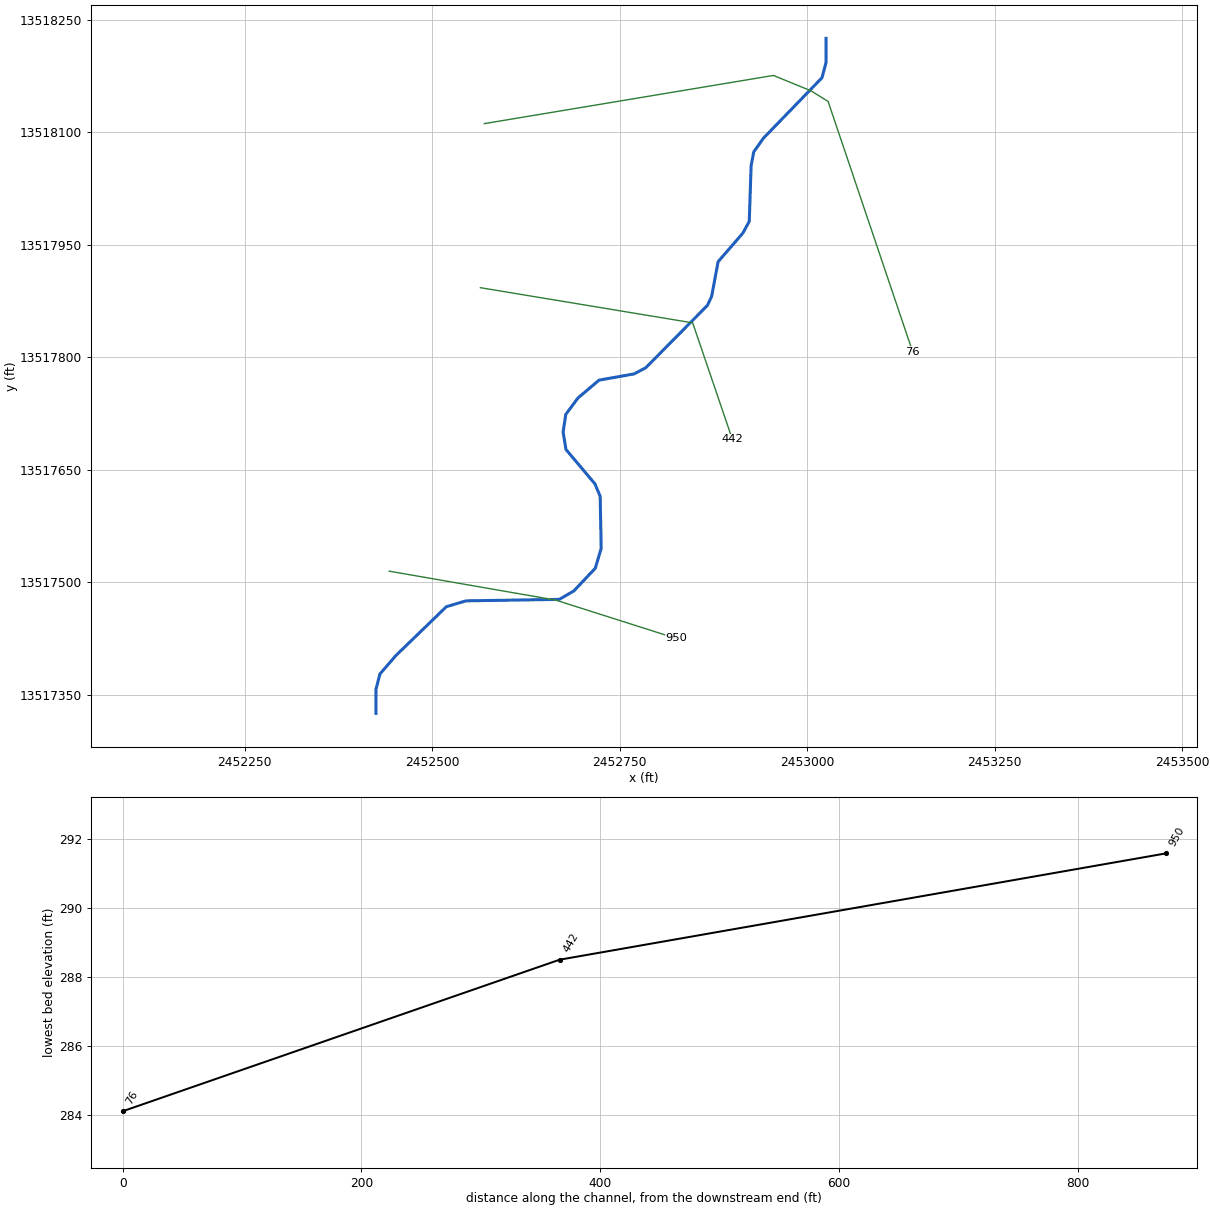
--- TRIB 5 TO HOOSIER CREEK.prj (project) ---

Proj Title=TRIB 5 TO HOOSIER CREEK Base Level Engineering
Current Plan=p01
Default Exp/Contr=0.3,0.1
English Units
Geom File=g01
Flow File=f01
Plan File=p01
Y Axis Title=Elevation
X Axis Title(PF)=Main Channel Distance
X Axis Title(XS)=Station
BEGIN DESCRIPTION:
TRIB 5 TO HOOSIER CREEK
END DESCRIPTION:
DSS Export Rating Curves= 0
DSS Export Rating Curve Sorted= 0
DSS Export Volume Flow Curves= 0
DXF OffsetX= 0
DXF OffsetY= 0
DXF ScaleX= 1
DXF ScaleY= 10

--- TRIB 5 TO HOOSIER CREEK.p01 (plan) ---

Plan Title=Multiple Run
Short Identifier=Multiple
Geom File=g01
Flow File=f01
Subcritical Flow
K Sum by GR= 0
Std Step Tol= 0.01
Critical Tol= 0.01
Num of Std Step Trials= 20
Max Error Tol= 0.3
Flow Tol Ratio= 0.001
Split Flow NTrial= 30
Split Flow Tol= 0.02
Split Flow Ratio= 0.02
Log Output Level= 0
Friction Slope Method= 1
Unsteady Friction Slope Method= 2
Unsteady Bridges Friction Slope Method= 1
Parabolic Critical Depth
Global Vel Dist=  1 , 1 , 1
Global Log Level= 0
CheckData=True
Encroach Param= -1, 0, 0, 0
BEGIN DESCRIPTION:
Multiple Run
END DESCRIPTION:

--- TRIB 5 TO HOOSIER CREEK.f01 (steady flow) ---

Flow Title=Multiple
Number of Profiles=7
Profile Names=10-year,25-year,50-year,1pct_min,100-year,1pct_plu,500-year
River Rch & RM= TRIB 5 TO HOOSIE,Reach-1,950
     373     584     770     492     982    1959    1579
Boundary for River Rch & Prof#=TRIB 5 TO HOOSIE,Reach-1,1
Up Type=0
Dn Type=3
Dn Slope=0.005
Boundary for River Rch & Prof#=TRIB 5 TO HOOSIE,Reach-1,2
Up Type=0
Dn Type=3
Dn Slope=0.005
Boundary for River Rch & Prof#=TRIB 5 TO HOOSIE,Reach-1,3
Up Type=0
Dn Type=3
Dn Slope=0.005
Boundary for River Rch & Prof#=TRIB 5 TO HOOSIE,Reach-1,4
Up Type=0
Dn Type=3
Dn Slope=0.005
Boundary for River Rch & Prof#=TRIB 5 TO HOOSIE,Reach-1,5
Up Type=0
Dn Type=3
Dn Slope=0.005
Boundary for River Rch & Prof#=TRIB 5 TO HOOSIE,Reach-1,6
Up Type=0
Dn Type=3
Dn Slope=0.005
Boundary for River Rch & Prof#=TRIB 5 TO HOOSIE,Reach-1,7
Up Type=0
Dn Type=3
Dn Slope=0.005

--- TRIB 5 TO HOOSIER CREEK.g01 (geometry) ---

Geom Title=Existing Conditions
Program Version=4.10

River Reach=TRIB 5 TO HOOSIE,Reach-1
Reach XY= 30
        2452425.       13517325.      2452424.92     13517356.89
       2452430.3     13517377.54      2452451.32     13517401.88
      2452518.79      13517467.2      2452544.99     13517475.02
      2452669.35     13517476.98      2452688.75      13517488.2
      2452717.38      13517518.5      2452725.26     13517544.94
      2452723.88     13517614.45      2452716.86     13517631.05
      2452678.33     13517676.78      2452674.47     13517700.12
      2452678.04     13517723.58      2452694.27     13517745.47
      2452722.39     13517769.25      2452768.92     13517777.55
      2452784.68     13517785.78      2452866.87     13517868.93
      2452872.51     13517881.02      2452881.14     13517927.17
      2452914.16     13517965.35      2452922.67     13517980.97
      2452925.13     13518054.95      2452928.61      13518073.5
      2452941.46     13518091.75      2453019.67     13518172.49
      2453025.07     13518193.12        2453025.       13518225.

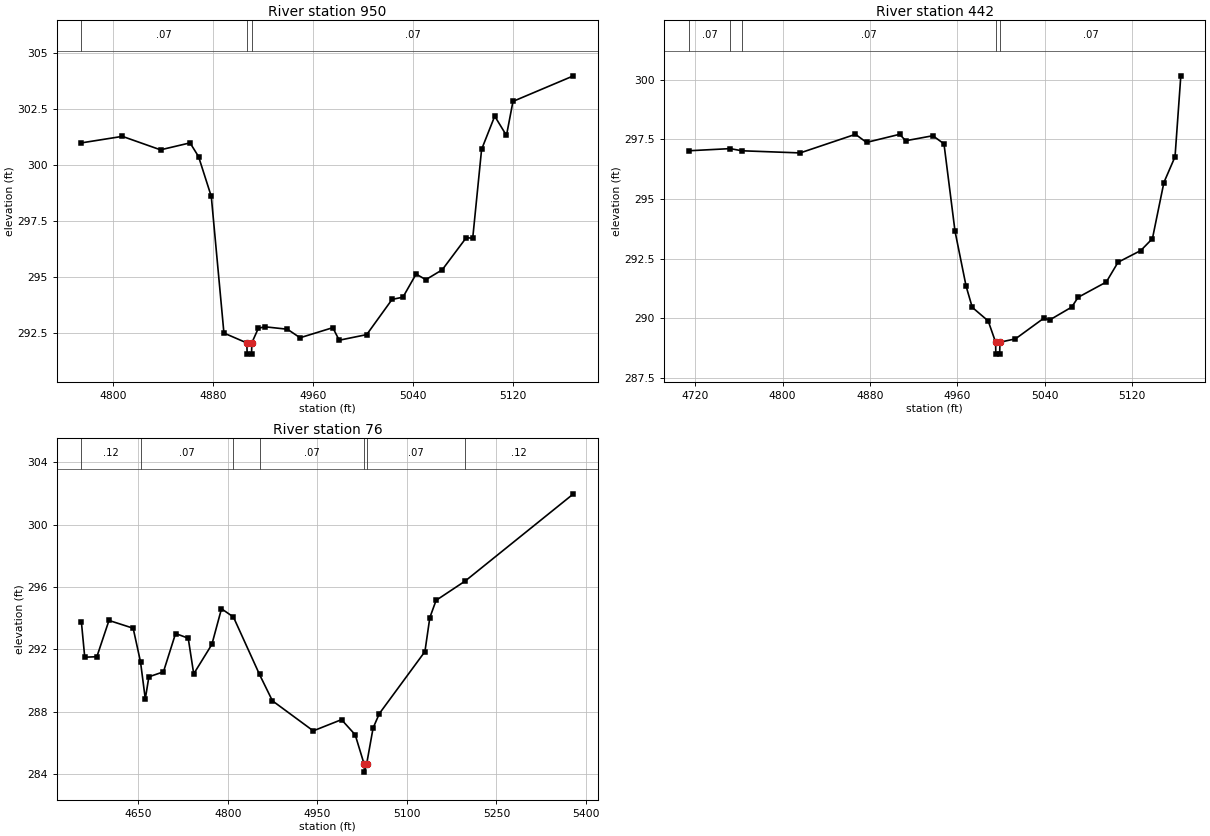
Type RM Length L Ch R = 1 ,950     ,508,508,508
BEGIN DESCRIPTION:
TRIB 5 TO HOOSIER CREEK 2.0
END DESCRIPTION:
XS GIS Cut Line= 3
      2452442.66     13517514.59      2452664.73     13517475.99
      2452825.02     13517424.99
#Sta/Elev= 30
  4774.6     301  4807.4  301.29  4837.9  300.69  4861.5     301  4868.3  300.39
  4878.5  298.61  4888.6  292.52  4906.9  292.08  4907.2  291.58  4910.7  291.58
  4910.9  292.08  4916.1  292.73  4921.2   292.8  4939.4  292.69  4949.5  292.31
  4975.7  292.76  4980.8   292.2  5002.8  292.45  5023.1  294.02  5031.8  294.12
  5042.3  295.15  5050.1   294.9  5063.2  295.34  5082.4  296.77  5087.6  296.75
  5094.7  300.71  5105.2  302.19  5114.6  301.33  5119.8  302.85  5168.2  303.99
#Mann= 3 ,-1 , 0
  4774.6     .07       0  4906.9     .05       0  4910.9     .07       0
Bank Sta=4906.9,4910.9
XS Rating Curve= 0 ,0
Exp/Cntr=0.3,0.1

Type RM Length L Ch R = 1 ,442     ,366,366,366
BEGIN DESCRIPTION:
Mapping XS 4fc3418b
END DESCRIPTION:
XS GIS Cut Line= 3
      2452564.26     13517892.54      2452847.24     13517845.67
      2452900.15     13517690.37
#Sta/Elev= 30
    4714  297.02    4752  297.11  4762.7  297.02  4816.1  296.93  4866.8  297.71
  4876.9  297.37  4907.3  297.71  4912.8  297.44  4937.7  297.65  4947.9  297.31
    4958  293.65  4968.2  291.34  4973.8  290.46  4988.4  289.89  4995.2     289
  4995.4   288.5  4998.9   288.5  4999.2     289  5013.4  289.14  5039.5  290.01
  5044.7  289.93  5064.9  290.47  5070.8  290.88  5096.6  291.52  5107.4  292.35
  5128.2  292.84  5138.9  293.34  5149.4  295.69  5159.6  296.77  5164.9  300.16
#Mann= 5 ,-1 , 0
    4714     .07       0    4752     .12       0  4762.7     .07       0
  4995.2     .05       0  4999.2     .07       0
Bank Sta=4995.2,4999.2
XS Rating Curve= 0 ,0
Exp/Cntr=0.3,0.1

Type RM Length L Ch R = 1 ,76      ,0,0,0
BEGIN DESCRIPTION:
TRIB 5 TO HOOSIER CREEK 1.0
END DESCRIPTION:
XS GIS Cut Line= 5
      2452569.44     13518111.29      2452954.88     13518175.53
      2453005.17     13518154.93       2453027.8     13518140.81
      2453140.54     13517807.01
#Sta/Elev= 30
  4554.9  293.75  4560.5  291.49  4580.8  291.52  4601.1  293.85  4641.6  293.35
  4653.9  291.19  4661.9  288.81  4667.9  290.23  4692.3  290.55  4712.6  293.01
  4733.8  292.71    4743  290.42  4773.4  292.31  4789.5   294.6  4809.5  294.07
  4853.2  290.38  4874.8  288.69  4943.2  286.76  4990.5  287.48  5013.4  286.51
  5028.5  284.61  5028.8  284.11  5032.5  284.61  5043.4  286.94  5053.9  287.87
  5130.2  291.85  5138.4  294.03  5148.9  295.14  5197.6  296.38    5379  301.98
#Mann= 7 ,-1 , 0
  4554.9     .12       0  4653.9     .07       0  4809.5     .12       0
  4853.2     .07       0  5028.5     .05       0  5032.5     .07       0
  5197.6     .12       0
Bank Sta=5028.5,5032.5
XS Rating Curve= 0 ,0
Exp/Cntr=0.3,0.1

Chan Stop Cuts=-1
Use User Specified Reach Order=0
Composite Channel Slope=5