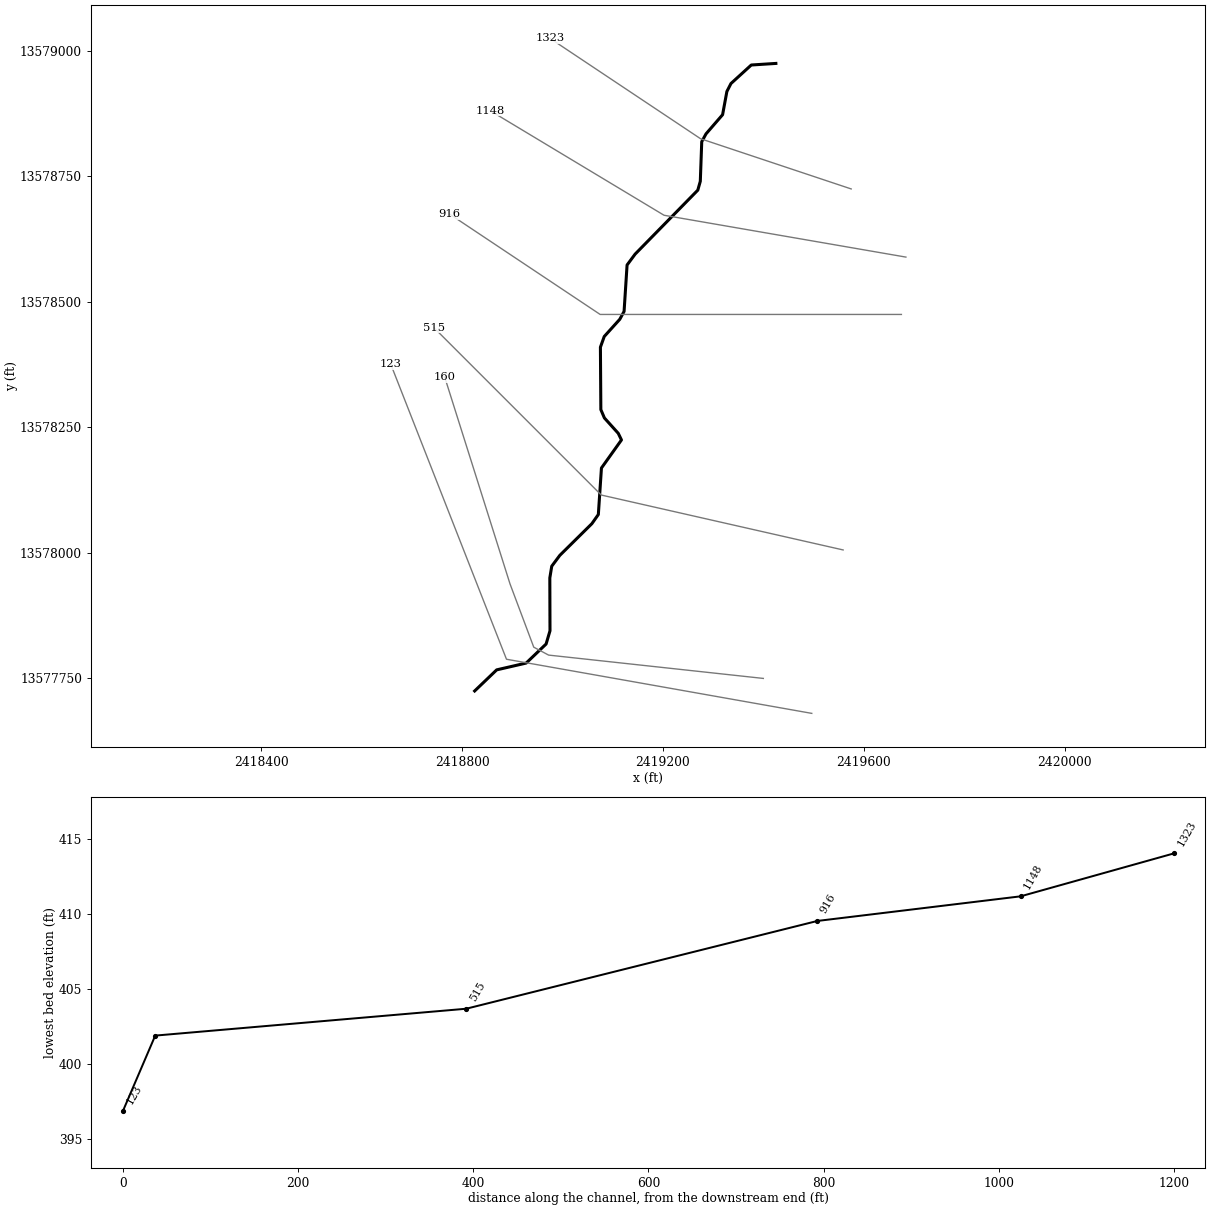
--- TRIB 5 TO LITTLE SALT CREEK.prj (project) ---

Proj Title=TRIB 5 TO LITTLE SALT CREEK Base Level Engineering
Current Plan=p01
Default Exp/Contr=0.3,0.1
English Units
Geom File=g01
Flow File=f01
Plan File=p01
BEGIN DESCRIPTION:
TRIB 5 TO LITTLE SALT CREEK
END DESCRIPTION:

--- TRIB 5 TO LITTLE SALT CREEK.p01 (plan) ---

Plan Title=Multiple Run
Short Identifier=Multiple
Geom File=g01
Flow File=f01
Subcritical Flow
K Sum by GR= 0
Std Step Tol= 0.01
Critical Tol= 0.01
Num of Std Step Trials= 20
Max Error Tol= 0.3
Flow Tol Ratio= 0.001
Split Flow NTrial= 30
Split Flow Tol= 0.02
Split Flow Ratio= 0.02
Log Output Level= 0
Friction Slope Method= 1
Unsteady Friction Slope Method= 2
Unsteady Bridges Friction Slope Method= 1
Parabolic Critical Depth
Global Vel Dist=  1 , 1 , 1
Global Log Level= 0
CheckData=True
Encroach Param= -1, 0, 0, 0
BEGIN DESCRIPTION:
Multiple Run
END DESCRIPTION:

--- TRIB 5 TO LITTLE SALT CREEK.f01 (steady flow) ---

Flow Title=Multiple
Number of Profiles=7
Profile Names=10-year,25-year,50-year,1pct_min,100-year,1pct_plu,500-year
River Rch & RM= TRIB 5 TO LITTLE,Reach-1,1323
     303     472     620     396     791    1578    1269
Boundary for River Rch & Prof#=TRIB 5 TO LITTLE,Reach-1,1
Up Type=0
Dn Type=3
Dn Slope=0.005
Boundary for River Rch & Prof#=TRIB 5 TO LITTLE,Reach-1,2
Up Type=0
Dn Type=3
Dn Slope=0.005
Boundary for River Rch & Prof#=TRIB 5 TO LITTLE,Reach-1,3
Up Type=0
Dn Type=3
Dn Slope=0.005
Boundary for River Rch & Prof#=TRIB 5 TO LITTLE,Reach-1,4
Up Type=0
Dn Type=3
Dn Slope=0.005
Boundary for River Rch & Prof#=TRIB 5 TO LITTLE,Reach-1,5
Up Type=0
Dn Type=3
Dn Slope=0.005
Boundary for River Rch & Prof#=TRIB 5 TO LITTLE,Reach-1,6
Up Type=0
Dn Type=3
Dn Slope=0.005
Boundary for River Rch & Prof#=TRIB 5 TO LITTLE,Reach-1,7
Up Type=0
Dn Type=3
Dn Slope=0.005

--- TRIB 5 TO LITTLE SALT CREEK.g01 (geometry) ---

Geom Title=Existing Conditions

River Reach=TRIB 5 TO LITTLE,Reach-1
Reach XY= 30
      2419425.00     13578975.00      2419376.03     13578971.86
      2419335.55     13578934.98      2419327.41     13578919.11
      2419318.87     13578872.84      2419285.83     13578834.66
      2419277.33     13578819.03      2419274.48     13578740.22
      2419269.48     13578722.57      2419144.63     13578595.15
      2419128.61     13578573.50      2419122.64     13578480.98
      2419114.10     13578465.37      2419083.13     13578431.06
      2419075.51     13578409.78      2419076.37     13578285.44
      2419083.45     13578268.82      2419111.05     13578238.21
      2419117.44     13578225.00      2419077.56     13578169.10
      2419071.38     13578076.50      2419058.51     13578058.26
      2418994.65     13577995.14      2418978.56     13577973.53
      2418974.73     13577950.11      2418975.07     13577844.89
      2418967.32     13577818.52      2418927.65     13577780.59
      2418868.89     13577767.05      2418825.00     13577725.00

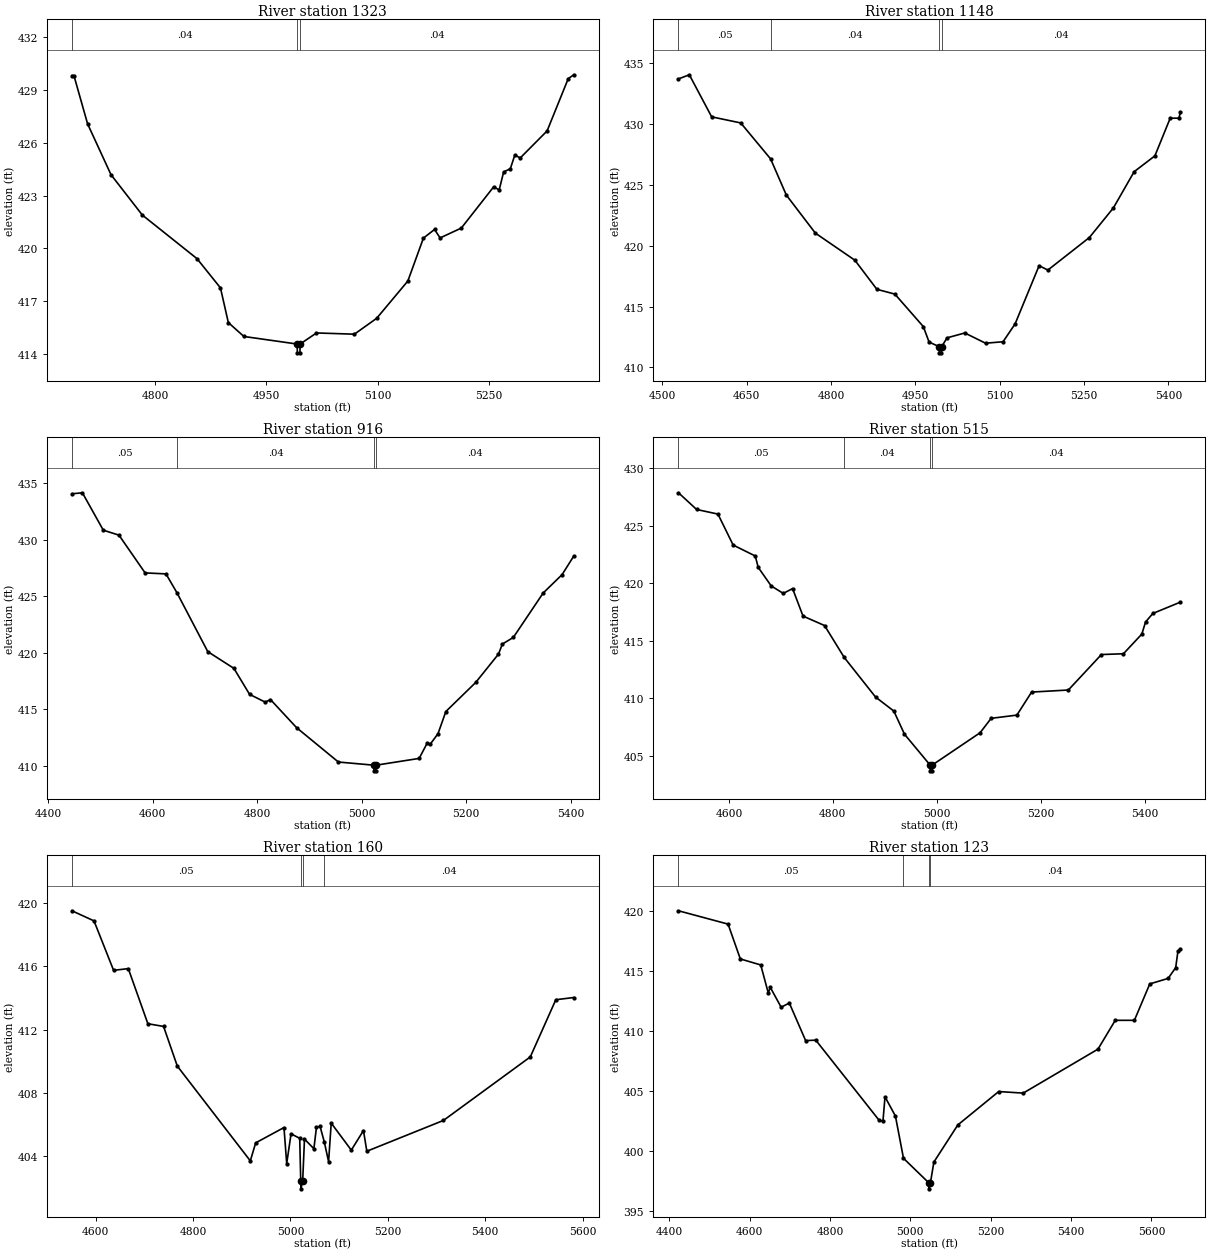
Type RM Length L Ch R = 1,1323,175,175,175
BEGIN DESCRIPTION:
TRIB 5 TO LITTLE SALT CREEK 3.0
END DESCRIPTION:
XS GIS Cut Line= 3
      2419575.04     13578724.99      2419275.00     13578825.00
      2418975.02     13579024.98
#Sta/Elev= 30
  4687.9  429.81  4690.6  429.81  4709.0  427.07  4740.6  424.18  4782.8  421.89
  4856.6  419.41  4888.2  417.75  4898.8  415.78  4919.8  414.99  4991.6  414.56
  4991.9  414.06  4995.4  414.06  4995.6  414.56  5017.7  415.19  5068.8  415.12
  5098.8  416.02  5140.9  418.14  5161.9  420.58  5176.9  421.07  5184.4  420.59
  5213.0  421.15  5256.6  423.49  5264.1  423.32  5270.1  424.34  5279.1  424.52
  5285.1  425.29  5292.6  425.14  5328.7  426.67  5357.2  429.64  5364.7  429.86
#Mann=3,-1,0
  4687.9    0.04       0  4991.6    0.04       0  4995.6    0.04       0
Bank Sta=4991.6,4995.6
Exp/Cntr=0.3,0.1

Type RM Length L Ch R = 1,1148,232,232,232
BEGIN DESCRIPTION:
Mapping XS 77ef8400
END DESCRIPTION:
XS GIS Cut Line= 3
      2419684.04     13578589.23      2419202.24     13578672.57
      2418856.60     13578880.47
#Sta/Elev= 30
  4528.9  433.67  4548.2  434.01  4587.9  430.56  4639.6  430.06  4692.7  427.11
  4720.7  424.14  4772.3  421.02  4842.5  418.80  4881.7  416.41  4913.6  416.02
  4964.3  413.35  4974.5  412.08  4992.8  411.70  4993.0  411.20  4996.5  411.20
  4996.8  411.70  5006.4  412.43  5038.0  412.83  5074.9  411.99  5106.0  412.11
  5127.4  413.57  5170.1  418.35  5185.7  417.99  5259.5  420.66  5302.2  423.09
  5339.1  426.06  5376.0  427.36  5403.2  430.45  5418.8  430.45  5421.2  430.93
#Mann=4,-1,0
  4528.9    0.05       0  4692.7    0.04       0  4992.8    0.04       0
  4996.8    0.04       0
Bank Sta=4992.8,4996.8
Exp/Cntr=0.3,0.1

Type RM Length L Ch R = 1,916,401,401,401
BEGIN DESCRIPTION:
TRIB 5 TO LITTLE SALT CREEK 2.0
END DESCRIPTION:
XS GIS Cut Line= 3
      2419675.04     13578475.00      2419075.00     13578475.00
      2418775.00     13578675.00
#Sta/Elev= 30
  4445.3  434.08  4465.3  434.17  4505.3  430.86  4535.3  430.42  4585.3  427.08
  4625.3  426.99  4646.2  425.33  4705.3  420.11  4755.3  418.63  4785.3  416.33
  4815.3  415.64  4825.3  415.87  4875.3  413.38  4955.3  410.34  5023.3  410.06
  5023.6  409.56  5027.1  409.56  5027.3  410.06  5109.9  410.66  5125.0  411.99
  5131.0  411.91  5146.0  412.85  5161.0  414.81  5218.1  417.38  5261.7  419.89
  5269.2  420.78  5290.2  421.37  5347.3  425.30  5383.4  426.92  5405.9  428.57
#Mann=4,-1,0
  4445.3    0.05       0  4646.2    0.04       0  5023.3    0.04       0
  5027.3    0.04       0
Bank Sta=5023.3,5027.3
Exp/Cntr=0.3,0.1

Type RM Length L Ch R = 1,515,355,355,355
BEGIN DESCRIPTION:
Mapping XS 1d11ec76
END DESCRIPTION:
XS GIS Cut Line= 3
      2419559.01     13578005.91      2419077.24     13578115.28
      2418743.93     13578448.59
#Sta/Elev= 30
  4503.0  427.86  4537.9  426.41  4578.9  426.01  4608.2  423.32  4650.7  422.37
  4656.4  421.38  4681.4  419.77  4704.6  419.12  4722.5  419.54  4742.6  417.15
  4784.0  416.33  4821.8  413.56  4882.1  410.12  4917.3  408.90  4937.8  406.89
  4987.1  404.21  4987.3  403.71  4990.8  403.71  4991.1  404.21  5083.3  407.02
  5104.5  408.27  5154.0  408.55  5182.3  410.55  5253.0  410.73  5316.6  413.81
  5359.0  413.88  5394.4  415.59  5401.5  416.64  5415.6  417.38  5468.4  418.36
#Mann=4,-1,0
  4503.0    0.05       0  4821.8    0.04       0  4987.1    0.04       0
  4991.1    0.04       0
Bank Sta=4987.1,4991.1
Exp/Cntr=0.3,0.1

Type RM Length L Ch R = 1,160,37,37,37
BEGIN DESCRIPTION:
4830
END DESCRIPTION:
XS GIS Cut Line= 5
      2419400.00     13577750.00      2418972.27     13577796.48
      2418942.71     13577812.25      2418895.41     13577938.38
      2418765.37     13578350.17
#Sta/Elev= 30
  4551.5  419.52  4596.8  418.88  4637.0  415.75  4667.2  415.86  4707.4  412.37
  4739.6  412.20  4767.8  409.69  4917.7  403.69  4928.7  404.83  4986.8  405.80
  4992.4  403.52  5001.3  405.40  5019.1  405.12  5021.2  402.42  5021.5  401.92
  5025.2  402.42  5028.9  405.07  5048.2  404.46  5053.5  405.82  5060.9  405.87
  5069.5  404.90  5078.4  403.64  5083.8  406.08  5125.0  404.37  5150.0  405.61
  5156.9  404.30  5314.2  406.25  5492.5  410.27  5544.9  413.89  5581.8  414.03
#Mann=4,-1,0
  4551.5    0.05       0  5021.2    0.05       0  5025.2    0.05       0
  5069.5    0.04       0
Bank Sta=5021.2,5025.2
Exp/Cntr=0.3,0.1

Type RM Length L Ch R = 1,123,0,0,0
BEGIN DESCRIPTION:
TRIB 5 TO LITTLE SALT CREEK 1.0
END DESCRIPTION:
XS GIS Cut Line= 3
      2419496.54     13577680.38      2418888.40     13577788.22
      2418657.96     13578375.72
#Sta/Elev= 30
  4423.1  420.03  4546.5  418.92  4577.0  416.02  4627.8  415.52  4646.5  413.19
  4651.6  413.65  4678.6  412.00  4698.9  412.35  4739.5  409.22  4764.7  409.26
  4922.3  402.59  4931.9  402.52  4937.0  404.54  4962.9  402.94  4983.0  399.42
  5046.0  397.38  5046.3  396.88  5050.0  397.38  5058.6  399.11  5118.2  402.20
  5219.9  404.98  5280.9  404.85  5466.9  408.51  5509.9  410.91  5557.5  410.91
  5595.8  413.94  5641.5  414.40  5660.3  415.30  5665.9  416.68  5671.8  416.85
#Mann=4,-1,0
  4423.1    0.05       0  4983.0    0.04       0  5046.0    0.04       0
  5050.0    0.04       0
Bank Sta=5046,5050
Exp/Cntr=0.3,0.1

Chan Stop Cuts=-1