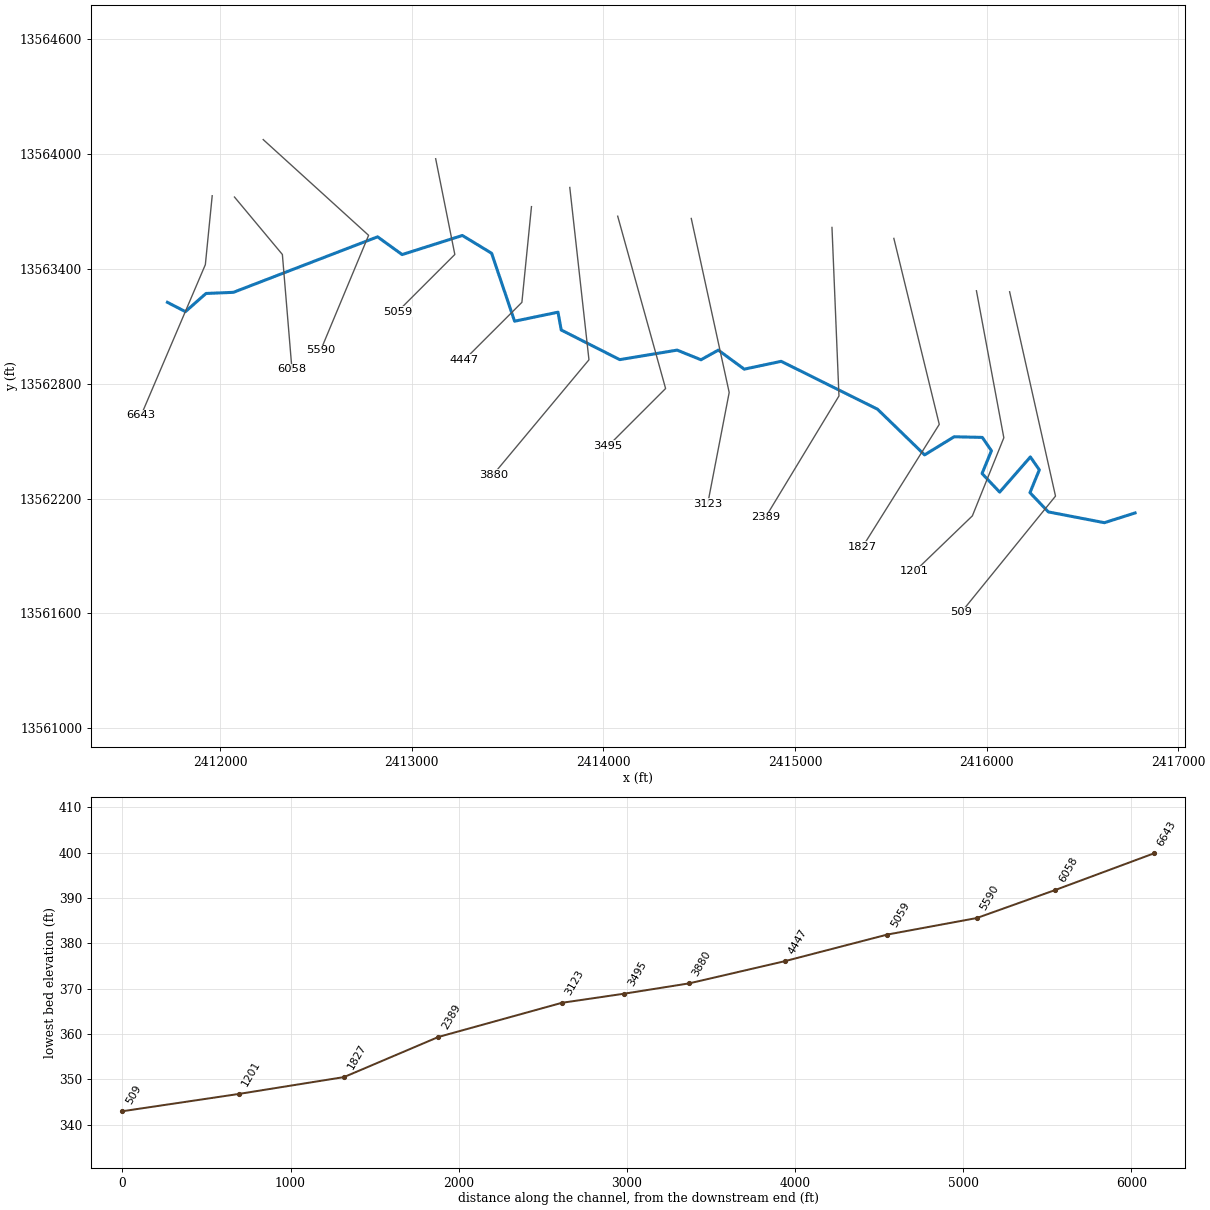
--- TRIB 5 TO SALT CREEK.prj (project) ---

Proj Title=TRIB 5 TO SALT CREEK Base Level Engineering
Current Plan=p01
Default Exp/Contr=0.3,0.1
English Units
Geom File=g01
Flow File=f01
Plan File=p01
BEGIN DESCRIPTION:
TRIB 5 TO SALT CREEK
END DESCRIPTION:

--- TRIB 5 TO SALT CREEK.p01 (plan) ---

Plan Title=Multiple Run
Short Identifier=Multiple
Geom File=g01
Flow File=f01
Subcritical Flow
K Sum by GR= 0
Std Step Tol= 0.01
Critical Tol= 0.01
Num of Std Step Trials= 20
Max Error Tol= 0.3
Flow Tol Ratio= 0.001
Split Flow NTrial= 30
Split Flow Tol= 0.02
Split Flow Ratio= 0.02
Log Output Level= 0
Friction Slope Method= 1
Unsteady Friction Slope Method= 2
Unsteady Bridges Friction Slope Method= 1
Parabolic Critical Depth
Global Vel Dist=  1 , 1 , 1
Global Log Level= 0
CheckData=True
Encroach Param= -1, 0, 0, 0
BEGIN DESCRIPTION:
Multiple Run
END DESCRIPTION:

--- TRIB 5 TO SALT CREEK.f01 (steady flow) ---

Flow Title=Multiple
Number of Profiles=7
Profile Names=10-year,25-year,50-year,1pct_min,100-year,1pct_plu,500-year
River Rch & RM= TRIB 5 TO SALT C,Reach-1,6643
     449     721     966     628    1253    2500    2089
River Rch & RM= TRIB 5 TO SALT C,Reach-1,2389
     711    1175    1605    1062    2119    4229    3663
Boundary for River Rch & Prof#=TRIB 5 TO SALT C,Reach-1,1
Up Type=0
Dn Type=3
Dn Slope=0.005
Boundary for River Rch & Prof#=TRIB 5 TO SALT C,Reach-1,2
Up Type=0
Dn Type=3
Dn Slope=0.005
Boundary for River Rch & Prof#=TRIB 5 TO SALT C,Reach-1,3
Up Type=0
Dn Type=3
Dn Slope=0.005
Boundary for River Rch & Prof#=TRIB 5 TO SALT C,Reach-1,4
Up Type=0
Dn Type=3
Dn Slope=0.005
Boundary for River Rch & Prof#=TRIB 5 TO SALT C,Reach-1,5
Up Type=0
Dn Type=3
Dn Slope=0.005
Boundary for River Rch & Prof#=TRIB 5 TO SALT C,Reach-1,6
Up Type=0
Dn Type=3
Dn Slope=0.005
Boundary for River Rch & Prof#=TRIB 5 TO SALT C,Reach-1,7
Up Type=0
Dn Type=3
Dn Slope=0.005

--- TRIB 5 TO SALT CREEK.g01 (geometry) ---

Geom Title=Existing Conditions

River Reach=TRIB 5 TO SALT C,Reach-1
Reach XY= 30
      2411725.00     13563225.00      2411819.03     13563176.55
      2411926.47     13563271.44      2412069.07     13563277.25
      2412821.77     13563567.15      2412949.96     13563474.51
      2413264.32     13563574.25      2413416.98     13563481.34
      2413536.83     13563126.51      2413763.40     13563173.56
      2413780.29     13563080.55      2414085.69     13562925.77
      2414385.19     13562975.45      2414509.61     13562925.11
      2414600.03     13562975.48      2414735.44     13562876.04
      2414928.32     13562916.96      2415431.06     13562666.86
      2415676.71     13562428.30      2415830.86     13562522.94
      2415977.77     13562519.65      2416025.53     13562450.13
      2415976.62     13562331.02      2416068.47     13562233.88
      2416228.65     13562417.52      2416275.49     13562350.22
      2416226.62     13562231.03      2416322.53     13562130.45
      2416614.94     13562074.22      2416775.00     13562125.00

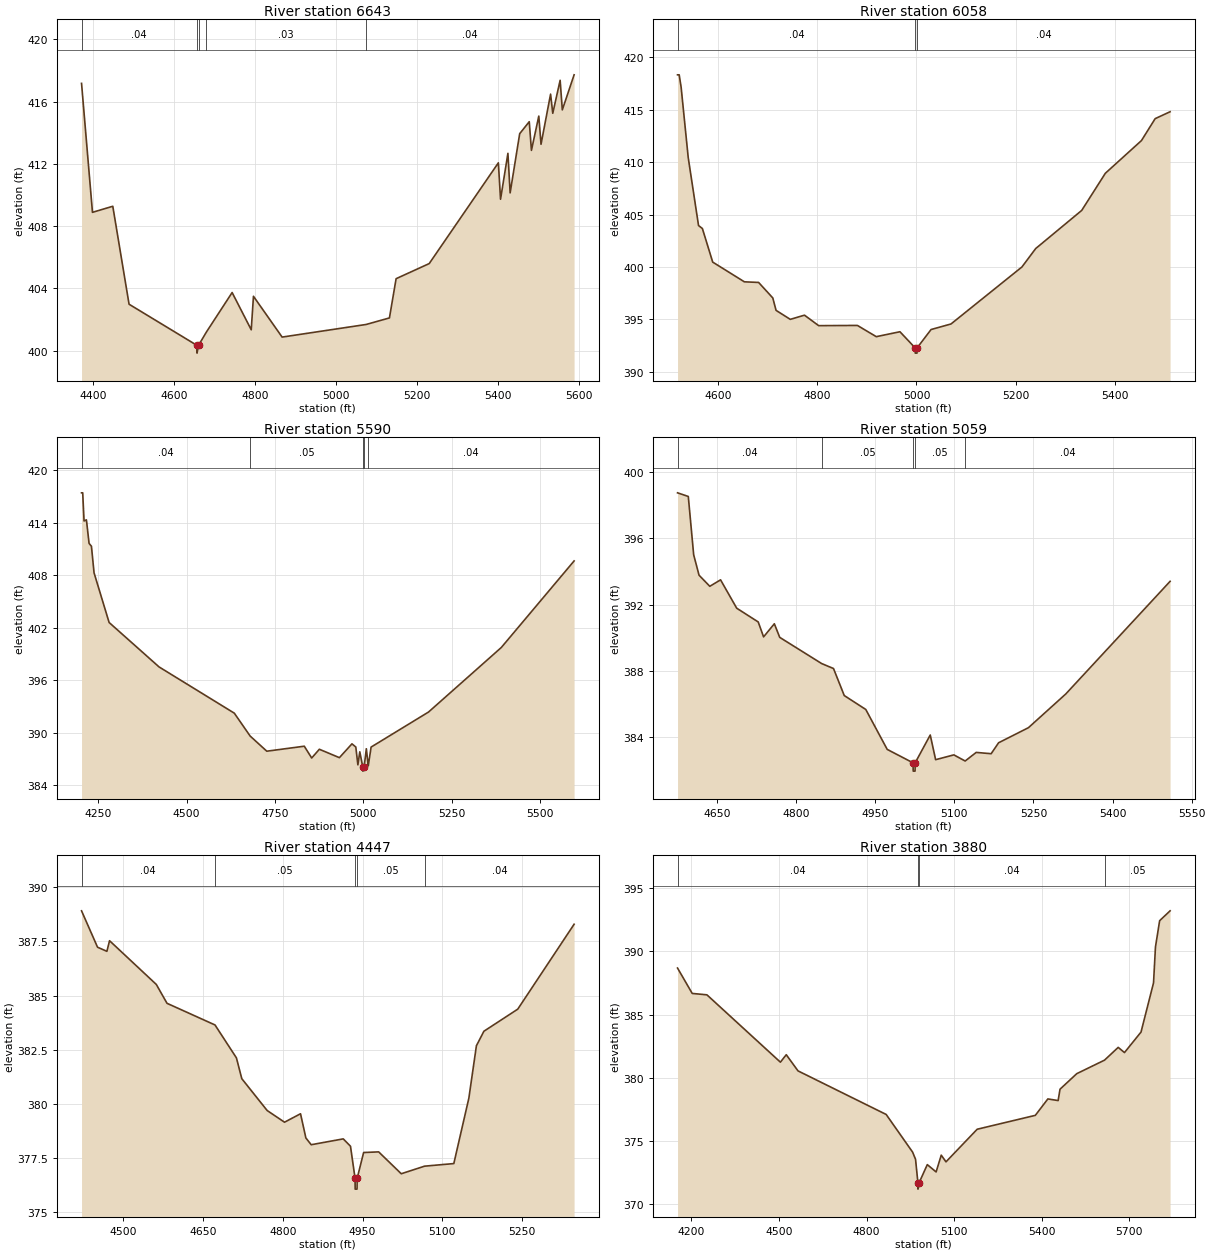
Type RM Length L Ch R = 1,6643,585,585,585
BEGIN DESCRIPTION:
TRIB 5 TO SALT CREEK 12.0
END DESCRIPTION:
XS GIS Cut Line= 3
      2411958.76     13563781.85      2411923.00     13563421.98
      2411587.75     13562635.27
#Sta/Elev= 30
  4371.4  417.17  4398.4  408.89  4448.6  409.28  4488.8  402.99  4656.4  400.35
  4656.7  399.85  4660.4  400.35  4680.0  401.21  4743.4  403.74  4790.6  401.35
  4796.1  403.50  4866.9  400.88  5074.5  401.69  5132.0  402.11  5148.5  404.63
  5230.3  405.60  5401.1  412.07  5406.5  409.73  5424.7  412.68  5430.2  410.14
  5453.8  413.94  5477.4  414.71  5482.8  412.87  5501.0  415.07  5506.5  413.26
  5530.1  416.48  5535.5  415.25  5553.7  417.37  5559.1  415.47  5588.2  417.72
#Mann=5,-1,0
  4371.4    0.04       0  4656.4    0.03       0  4660.4    0.04       0
  4680.0    0.03       0  5074.5    0.04       0
Bank Sta=4656.4,4660.4
Exp/Cntr=0.3,0.1

Type RM Length L Ch R = 1,6058,468,468,468
BEGIN DESCRIPTION:
TRIB 5 TO SALT CREEK 11.0
END DESCRIPTION:
XS GIS Cut Line= 3
      2412075.00     13563775.00      2412325.00     13563475.00
      2412375.00     13562875.00
#Sta/Elev= 30
  4518.5  418.33  4521.8  418.33  4525.7  417.17  4540.0  410.45  4560.8  403.96
  4568.6  403.67  4589.4  400.47  4653.2  398.59  4681.9  398.53  4710.5  397.05
  4717.0  395.87  4745.7  395.01  4774.3  395.41  4802.9  394.41  4881.0  394.43
  4919.0  393.36  4966.7  393.83  4997.3  392.29  4997.6  391.79  5001.1  391.79
  5001.3  392.29  5029.4  394.04  5069.6  394.57  5212.6  400.01  5240.2  401.76
  5333.0  405.40  5380.6  408.94  5453.4  412.06  5481.0  414.15  5511.1  414.81
#Mann=3,-1,0
  4518.5    0.04       0  4997.3    0.04       0  5001.3    0.04       0
Bank Sta=4997.3,5001.3
Exp/Cntr=0.3,0.1

Type RM Length L Ch R = 1,5590,531,531,531
BEGIN DESCRIPTION:
TRIB 5 TO SALT CREEK 10.0
END DESCRIPTION:
XS GIS Cut Line= 3
      2412225.02     13564074.98      2412775.00     13563575.00
      2412524.99     13562974.98
#Sta/Elev= 30
  4203.1  417.42  4206.4  417.42  4210.2  414.20  4216.9  414.33  4224.4  411.64
  4231.1  411.31  4238.5  408.27  4281.1  402.59  4422.3  397.51  4635.2  392.22
  4680.1  389.60  4727.1  387.87  4833.2  388.44  4854.1  387.09  4875.8  388.09
  4932.5  387.13  4968.0  388.71  4978.9  388.35  4984.8  386.31  4990.2  387.80
  4998.5  386.09  4998.8  385.59  5002.5  386.09  5008.7  388.15  5012.5  386.77
  5014.1  386.19  5022.2  388.34  5184.7  392.35  5390.5  399.73  5596.4  409.63
#Mann=5,-1,0
  4203.1    0.04       0  4680.1    0.05       0  4998.5    0.05       0
  5002.5    0.05       0  5012.5    0.04       0
Bank Sta=4998.5,5002.5
Exp/Cntr=0.3,0.1

Type RM Length L Ch R = 1,5059,612,612,612
BEGIN DESCRIPTION:
TRIB 5 TO SALT CREEK 9.0
END DESCRIPTION:
XS GIS Cut Line= 3
      2413125.00     13563975.02      2413225.00     13563475.00
      2412924.99     13563174.99
#Sta/Elev= 30
  4574.9  398.74  4595.3  398.52  4605.5  395.00  4615.7  393.77  4636.1  393.10
  4656.5  393.49  4687.1  391.78  4727.9  390.95  4738.1  390.05  4758.5  390.84
  4768.7  390.02  4848.2  388.44  4870.7  388.14  4891.1  386.51  4931.9  385.67
  4972.6  383.26  5021.6  382.45  5021.9  381.95  5025.4  381.95  5025.6  382.45
  5054.2  384.13  5064.4  382.64  5099.0  382.93  5120.4  382.56  5141.4  383.08
  5169.7  383.00  5183.8  383.66  5240.4  384.57  5311.1  386.60  5509.1  393.40
#Mann=5,-1,0
  4574.9    0.04       0  4848.2    0.05       0  5021.6    0.05       0
  5025.6    0.05       0  5120.4    0.04       0
Bank Sta=5021.6,5025.6
Exp/Cntr=0.3,0.1

Type RM Length L Ch R = 1,4447,567,567,567
BEGIN DESCRIPTION:
TRIB 5 TO SALT CREEK 8.0
END DESCRIPTION:
XS GIS Cut Line= 3
      2413625.00     13563724.96      2413575.00     13563225.00
      2413275.01     13562925.01
#Sta/Elev= 30
  4421.2  388.91  4451.3  387.23  4468.9  387.04  4473.9  387.53  4561.9  385.51
  4582.0  384.64  4672.3  383.64  4712.6  382.12  4722.7  381.16  4770.4  379.69
  4803.1  379.15  4833.2  379.54  4843.3  378.42  4853.3  378.11  4913.6  378.38
  4927.2  378.04  4935.8  376.56  4936.0  376.06  4939.5  376.06  4939.8  376.56
  4951.9  377.75  4980.2  377.78  5022.7  376.77  5066.6  377.12  5121.6  377.24
  5149.9  380.26  5164.1  382.68  5178.2  383.35  5241.9  384.37  5347.9  388.29
#Mann=5,-1,0
  4421.2    0.04       0  4672.3    0.05       0  4935.8    0.05       0
  4939.8    0.05       0  5066.6    0.04       0
Bank Sta=4935.8,4939.8
Exp/Cntr=0.3,0.1

Type RM Length L Ch R = 1,3880,385,385,385
BEGIN DESCRIPTION:
TRIB 5 TO SALT CREEK 7.0
END DESCRIPTION:
XS GIS Cut Line= 3
      2413825.00     13563825.01      2413925.00     13562925.00
      2413424.98     13562324.98
#Sta/Elev= 30
  4152.9  388.68  4203.2  386.67  4253.5  386.56  4505.1  381.23  4525.2  381.82
  4565.4  380.54  4867.3  377.09  4957.8  374.11  4967.9  373.54  4976.0  371.68
  4976.2  371.18  4980.0  371.68  5008.1  373.12  5038.3  372.54  5055.9  373.87
  5072.1  373.34  5178.9  375.92  5378.0  377.02  5421.0  378.32  5456.1  378.19
  5462.6  379.09  5519.9  380.32  5615.0  381.39  5661.8  382.40  5683.3  381.99
  5739.9  383.61  5782.8  387.51  5789.4  390.35  5803.7  392.43  5839.5  393.21
#Mann=4,-1,0
  4152.9    0.04       0  4976.0    0.04       0  4980.0    0.04       0
  5615.0    0.05       0
Bank Sta=4976,4980
Exp/Cntr=0.3,0.1

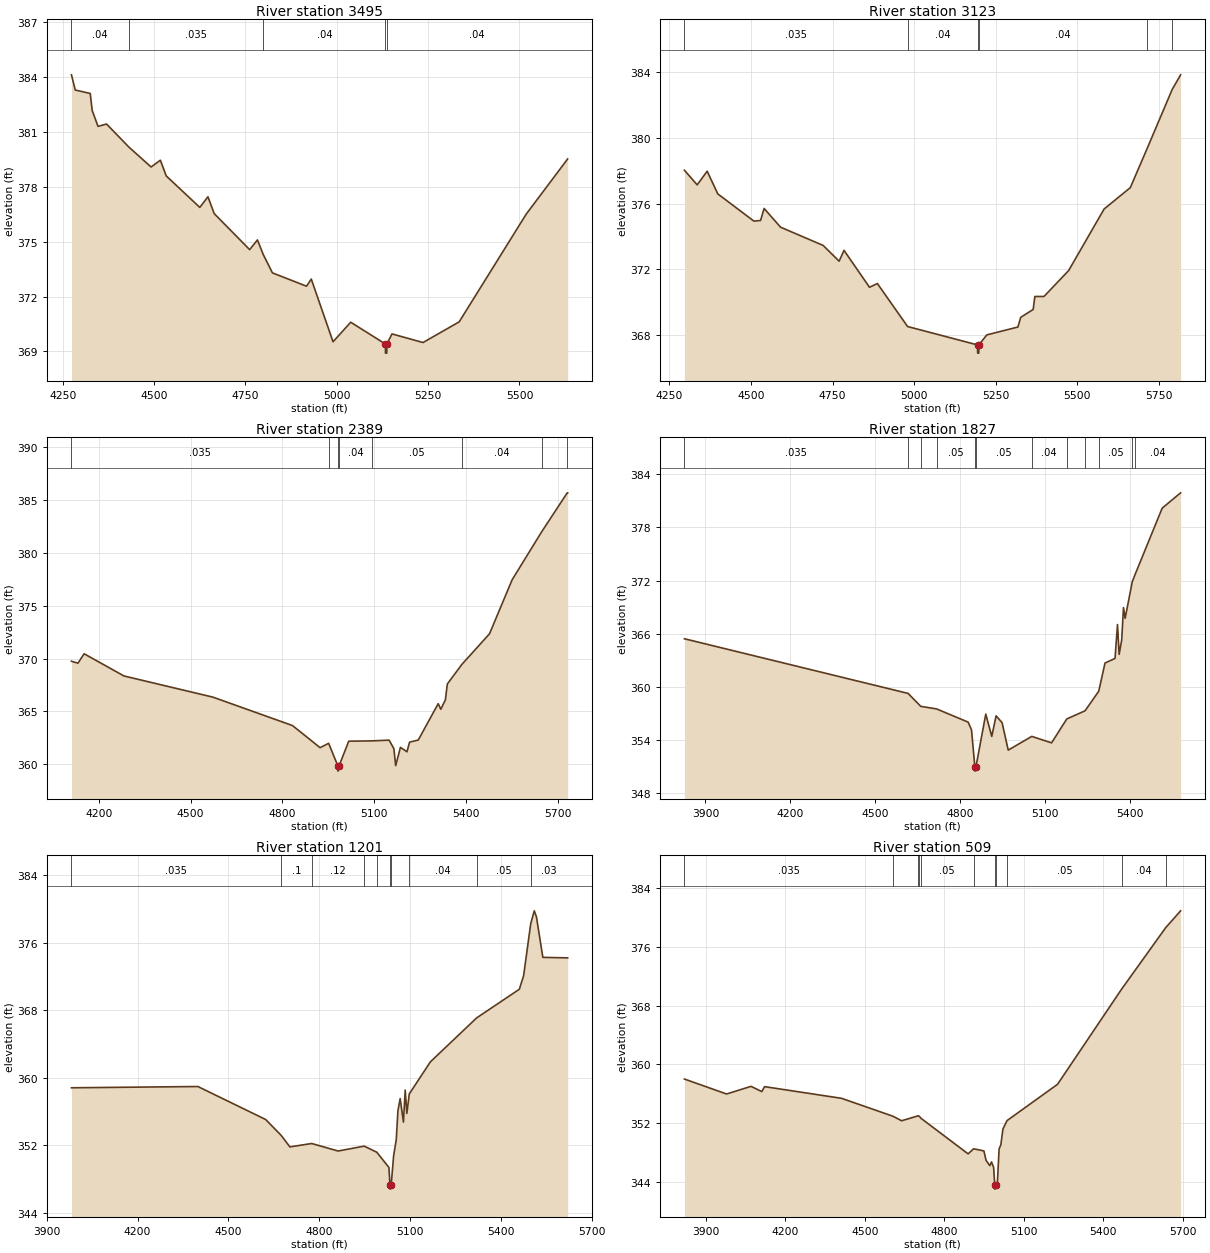
Type RM Length L Ch R = 1,3495,372,372,372
BEGIN DESCRIPTION:
TRIB 5 TO SALT CREEK 6.0
END DESCRIPTION:
XS GIS Cut Line= 3
      2414075.00     13563675.01      2414325.00     13562775.00
      2414024.97     13562474.97
#Sta/Elev= 30
  4273.6  384.13  4284.0  383.30  4325.0  383.11  4330.2  382.19  4346.3  381.31
  4369.6  381.44  4431.2  380.17  4491.6  379.09  4517.0  379.46  4533.1  378.60
  4624.9  376.88  4647.2  377.46  4664.4  376.54  4761.4  374.57  4782.7  375.10
  4798.7  374.30  4823.7  373.30  4917.1  372.57  4930.1  372.96  4989.7  369.53
  5038.0  370.60  5133.0  369.41  5133.3  368.91  5136.8  368.91  5137.0  369.41
  5151.1  369.96  5236.0  369.49  5335.0  370.62  5518.8  376.52  5632.0  379.53
#Mann=5,-1,0
  4273.6    0.04       0  4431.2   0.035       0  4798.7    0.04       0
  5133.0    0.04       0  5137.0    0.04       0
Bank Sta=5133,5137
Exp/Cntr=0.3,0.1

Type RM Length L Ch R = 1,3123,734,734,734
BEGIN DESCRIPTION:
Mapping XS 13f8da1a
END DESCRIPTION:
XS GIS Cut Line= 3
      2414458.93     13563663.18      2414656.85     13562754.30
      2414544.87     13562173.57
#Sta/Elev= 30
  4295.8  378.03  4334.9  377.14  4365.6  377.97  4398.1  376.59  4508.9  374.93
  4529.3  374.97  4540.2  375.70  4590.7  374.56  4721.2  373.45  4770.3  372.49
  4785.2  373.15  4863.4  370.90  4887.5  371.13  4980.2  368.51  5194.7  367.39
  5195.0  366.89  5198.5  366.89  5198.7  367.39  5223.1  368.00  5318.5  368.48
  5327.1  369.07  5365.3  369.55  5370.4  370.34  5398.4  370.34  5474.1  371.92
  5582.9  375.67  5663.2  376.97  5715.8  379.40  5791.4  382.94  5817.4  383.84
#Mann=6,-1,0
  4295.8   0.035       0  4980.2    0.04       0  5194.7    0.04       0
  5198.7    0.04       0  5715.8    0.03       0  5791.4    0.05       0
Bank Sta=5194.7,5198.7
Exp/Cntr=0.3,0.1

Type RM Length L Ch R = 1,2389,562,562,562
BEGIN DESCRIPTION:
Mapping XS 4fd9d25b
END DESCRIPTION:
XS GIS Cut Line= 3
      2415193.31     13563616.28      2415229.77     13562736.07
      2414846.94     13562103.22
#Sta/Elev= 30
  4111.1  369.75  4132.4  369.57  4152.4  370.46  4282.5  368.36  4572.8  366.36
  4833.0  363.67  4923.1  361.58  4951.0  361.99  4981.1  359.86  4981.4  359.36
  4985.1  359.86  5016.7  362.19  5091.5  362.22  5148.6  362.29  5164.1  361.48
  5170.0  359.88  5185.5  361.61  5206.8  361.19  5215.4  362.10  5243.7  362.30
  5308.9  365.74  5317.4  365.21  5332.3  366.10  5338.7  367.60  5386.4  369.46
  5476.5  372.35  5550.2  377.45  5646.7  381.99  5730.4  385.68  5731.7  385.68
#Mann=8,-1,0
  4111.1   0.035       0  4951.0    0.04       0  4981.1    0.04       0
  4985.1    0.04       0  5091.5    0.05       0  5386.4    0.04       0
  5646.7    0.03       0  5730.4    0.04       0
Bank Sta=4981.1,4985.1
Exp/Cntr=0.3,0.1

Type RM Length L Ch R = 1,1827,626,626,626
BEGIN DESCRIPTION:
Mapping XS ae5950b2
END DESCRIPTION:
XS GIS Cut Line= 3
      2415516.22     13563559.02      2415753.21     13562587.63
      2415353.11     13561948.51
#Sta/Elev= 30
  3825.5  365.44  4616.3  359.27  4660.9  357.81  4717.0  357.52  4828.4  356.03
  4840.3  355.17  4852.1  351.00  4852.4  350.50  4856.1  351.00  4890.7  356.93
  4911.9  354.42  4927.2  356.74  4948.4  355.97  4970.1  352.87  5053.2  354.42
  5123.4  353.69  5177.1  356.39  5241.7  357.31  5290.1  359.52  5312.2  362.70
  5347.6  363.22  5356.3  367.04  5362.2  363.68  5371.2  365.31  5377.5  368.95
  5383.4  367.75  5408.5  371.87  5418.9  372.72  5514.3  380.18  5579.4  381.91
#Mann=12,-1,0
  3825.5   0.035       0  4616.3    0.04       0  4660.9   0.035       0
  4717.0    0.05       0  4852.1    0.05       0  4856.1    0.05       0
  5053.2    0.04       0  5177.1    0.05       0  5241.7    0.03       0
  5290.1    0.05       0  5408.5    0.03       0  5418.9    0.04       0
Bank Sta=4852.1,4856.1
Exp/Cntr=0.3,0.1

Type RM Length L Ch R = 1,1201,692,692,692
BEGIN DESCRIPTION:
4833
END DESCRIPTION:
XS GIS Cut Line= 4
      2415947.21     13563285.55      2416090.19     13562517.67
      2415926.03     13562109.92      2415624.90     13561819.35
#Sta/Elev= 30
  3981.6  358.80  4399.2  358.95  4623.0  355.04  4674.5  353.15  4703.1  351.79
  4775.1  352.19  4862.6  351.30  4948.4  351.88  4990.1  351.16  5030.3  349.35
  5033.7  347.28  5034.0  346.78  5037.7  347.28  5045.8  350.74  5054.5  352.66
  5059.9  356.06  5067.4  357.52  5078.2  354.73  5084.0  358.53  5089.4  355.76
  5097.6  358.08  5167.3  361.88  5319.7  367.08  5461.1  370.49  5475.2  372.10
  5498.8  378.29  5510.4  379.79  5517.6  379.07  5538.7  374.27  5620.7  374.21
#Mann=10,-1,0
  3981.6   0.035       0  4674.5     0.1       0  4775.1    0.12       0
  4948.4    0.05       0  4990.1    0.12       0  5033.7    0.05       0
  5037.7    0.12       0  5097.6    0.04       0  5319.7    0.05       0
  5498.8    0.03       0
Bank Sta=5033.7,5037.7
Exp/Cntr=0.3,0.1

Type RM Length L Ch R = 1,509,0,0,0
BEGIN DESCRIPTION:
TRIB 5 TO SALT CREEK 3.0
END DESCRIPTION:
XS GIS Cut Line= 3
      2416120.39     13563280.34      2416359.90     13562213.02
      2415868.87     13561607.19
#Sta/Elev= 30
  3818.3  357.98  3977.5  355.94  4069.7  356.98  4110.7  356.27  4121.0  356.94
  4411.7  355.35  4605.6  352.91  4638.6  352.29  4701.6  352.97  4706.0  352.88
  4710.4  352.66  4889.6  347.78  4910.3  348.47  4949.2  348.18  4957.2  346.91
  4971.5  346.17  4978.0  346.68  4985.9  345.94  4990.3  343.47  4990.6  342.97
  4994.3  343.47  4999.7  343.58  5006.7  348.46  5013.2  349.02  5021.1  351.16
  5036.5  352.31  5227.3  357.26  5469.9  370.27  5635.4  378.60  5692.0  380.91
#Mann=11,-1,0
  3818.3   0.035       0  4605.6     0.1       0  4701.6   0.035       0
  4706.0     0.1       0  4710.4    0.05       0  4910.3    0.12       0
  4990.3    0.05       0  4994.3    0.12       0  5036.5    0.05       0
  5469.9    0.04       0  5635.4    0.05       0
Bank Sta=4990.3,4994.3
Exp/Cntr=0.3,0.1

Chan Stop Cuts=-1