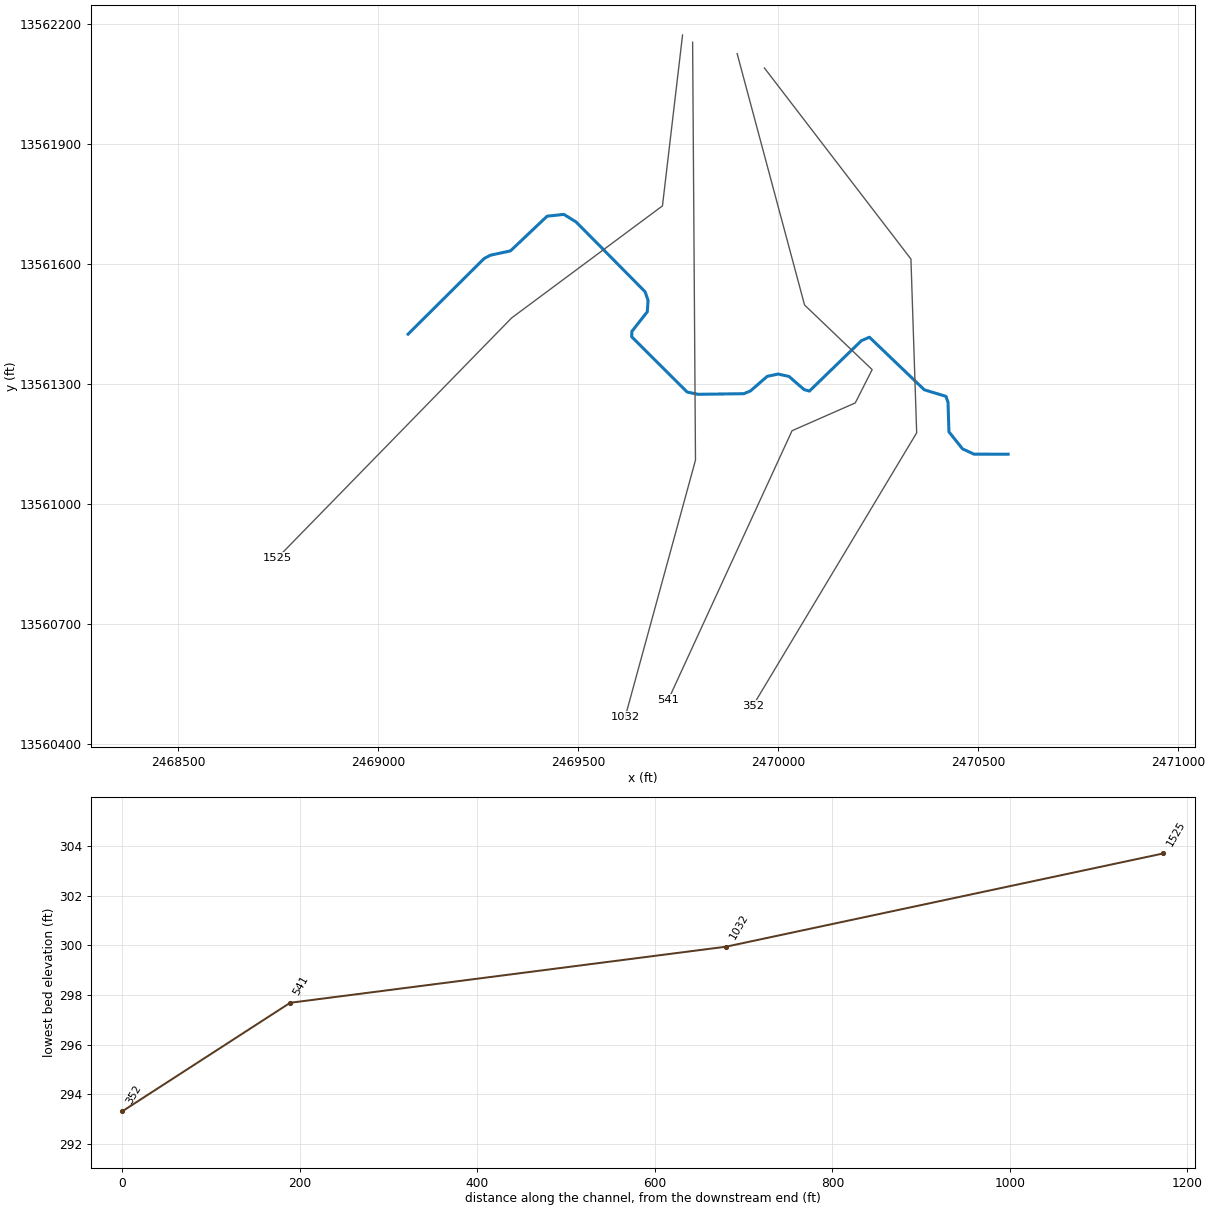
--- TRIB 5 TO SHILOH CREEK.prj (project) ---

Proj Title=TRIB 5 TO SHILOH CREEK Base Level Engineering
Current Plan=p01
Default Exp/Contr=0.3,0.1
English Units
Geom File=g01
Flow File=f01
Plan File=p01
BEGIN DESCRIPTION:
TRIB 5 TO SHILOH CREEK
END DESCRIPTION:

--- TRIB 5 TO SHILOH CREEK.p01 (plan) ---

Plan Title=Multiple Run
Short Identifier=Multiple
Geom File=g01
Flow File=f01
Subcritical Flow
K Sum by GR= 0
Std Step Tol= 0.01
Critical Tol= 0.01
Num of Std Step Trials= 20
Max Error Tol= 0.3
Flow Tol Ratio= 0.001
Split Flow NTrial= 30
Split Flow Tol= 0.02
Split Flow Ratio= 0.02
Log Output Level= 0
Friction Slope Method= 1
Unsteady Friction Slope Method= 2
Unsteady Bridges Friction Slope Method= 1
Parabolic Critical Depth
Global Vel Dist=  1 , 1 , 1
Global Log Level= 0
CheckData=True
Encroach Param= -1, 0, 0, 0
BEGIN DESCRIPTION:
Multiple Run
END DESCRIPTION:

--- TRIB 5 TO SHILOH CREEK.f01 (steady flow) ---

Flow Title=Multiple
Number of Profiles=7
Profile Names=10-year,25-year,50-year,1pct_min,100-year,1pct_plu,500-year
River Rch & RM= TRIB 5 TO SHILOH,Reach-1,1525
     286     441     575     365     728    1453    1152
Boundary for River Rch & Prof#=TRIB 5 TO SHILOH,Reach-1,1
Up Type=0
Dn Type=3
Dn Slope=0.005
Boundary for River Rch & Prof#=TRIB 5 TO SHILOH,Reach-1,2
Up Type=0
Dn Type=3
Dn Slope=0.005
Boundary for River Rch & Prof#=TRIB 5 TO SHILOH,Reach-1,3
Up Type=0
Dn Type=3
Dn Slope=0.005
Boundary for River Rch & Prof#=TRIB 5 TO SHILOH,Reach-1,4
Up Type=0
Dn Type=3
Dn Slope=0.005
Boundary for River Rch & Prof#=TRIB 5 TO SHILOH,Reach-1,5
Up Type=0
Dn Type=3
Dn Slope=0.005
Boundary for River Rch & Prof#=TRIB 5 TO SHILOH,Reach-1,6
Up Type=0
Dn Type=3
Dn Slope=0.005
Boundary for River Rch & Prof#=TRIB 5 TO SHILOH,Reach-1,7
Up Type=0
Dn Type=3
Dn Slope=0.005

--- TRIB 5 TO SHILOH CREEK.g01 (geometry) ---

Geom Title=Existing Conditions

River Reach=TRIB 5 TO SHILOH,Reach-1
Reach XY= 30
      2469075.00     13561425.00      2469265.32     13561614.22
      2469281.05     13561622.47      2469331.04     13561633.18
      2469422.72     13561719.92      2469464.36     13561724.45
      2469495.09     13561705.58      2469667.50     13561531.05
      2469674.99     13561509.64      2469673.01     13561481.05
      2469634.33     13561431.55      2469634.15     13561418.27
      2469772.55     13561280.45      2469799.89     13561274.68
      2469914.50     13561276.22      2469931.07     13561283.18
      2469972.83     13561319.60      2470000.04     13561325.31
      2470027.30     13561319.34      2470065.13     13561286.39
      2470078.41     13561282.82      2470208.33     13561408.81
      2470228.33     13561417.41      2470365.62     13561285.91
      2470419.74     13561269.52      2470424.78     13561254.73
      2470427.10     13561180.78      2470461.22     13561138.17
      2470489.88     13561125.05      2470575.00     13561125.00

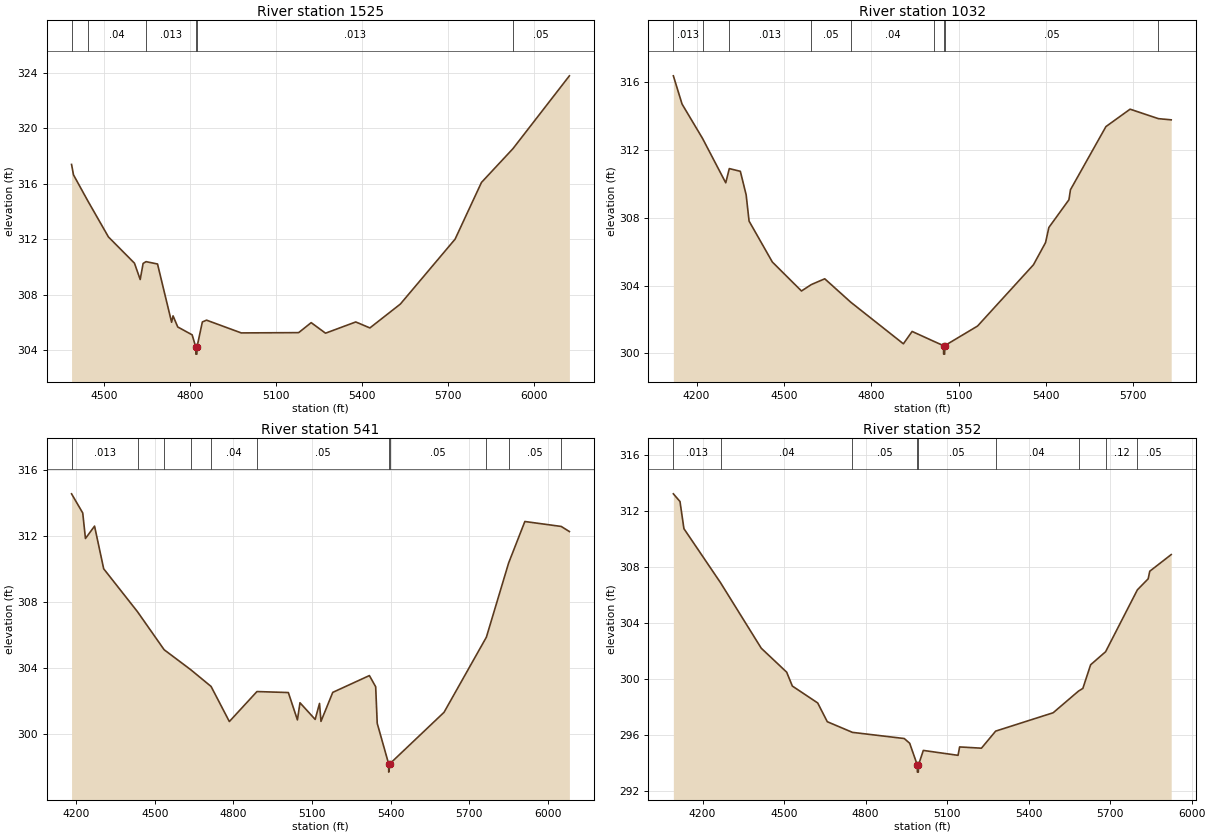
Type RM Length L Ch R = 1,1525,493,493,493
BEGIN DESCRIPTION:
LGII4583
END DESCRIPTION:
XS GIS Cut Line= 4
      2469761.23     13562172.85      2469710.97     13561745.66
      2469333.99     13561465.62      2468749.39     13560866.67
#Sta/Elev= 30
  4386.5  317.39  4393.2  316.64  4443.0  314.77  4515.2  312.16  4605.9  310.27
  4626.0  309.09  4636.1  310.25  4646.3  310.38  4686.4  310.21  4735.5  306.01
  4740.6  306.47  4756.9  305.67  4807.2  305.10  4820.0  304.21  4820.2  303.71
  4823.7  303.71  4824.0  304.21  4842.8  306.03  4857.4  306.16  4978.4  305.24
  5178.7  305.26  5222.5  305.98  5272.5  305.22  5377.9  306.03  5427.3  305.60
  5533.5  307.32  5724.4  312.00  5816.4  316.09  5926.4  318.53  6123.2  323.78
#Mann=6,-1,0
  4386.5   0.013       0  4443.0    0.04       0  4646.3   0.013       0
  4820.0    0.03       0  4824.0   0.013       0  5926.4    0.05       0
Bank Sta=4820,4824
Exp/Cntr=0.3,0.1

Type RM Length L Ch R = 1,1032,491,491,491
BEGIN DESCRIPTION:
LGII4582
END DESCRIPTION:
XS GIS Cut Line= 3
      2469786.36     13562154.95      2469793.54     13561110.18
      2469617.96     13560468.77
#Sta/Elev= 30
  4120.2  316.39  4150.1  314.72  4220.5  312.69  4300.1  310.07  4312.3  310.91
  4350.2  310.75  4370.2  309.36  4380.2  307.81  4460.2  305.39  4560.2  303.68
  4594.1  304.06  4640.2  304.40  4729.3  303.02  4910.2  300.56  4940.2  301.29
  5016.8  300.69  5048.2  300.45  5048.4  299.95  5051.9  299.95  5052.2  300.45
  5165.0  301.61  5357.0  305.23  5398.5  306.54  5409.8  307.43  5478.8  309.07
  5484.0  309.66  5605.8  313.39  5688.8  314.42  5786.1  313.86  5830.0  313.79
#Mann=9,-1,0
  4120.2   0.013       0  4220.5    0.04       0  4312.3   0.013       0
  4594.1    0.05       0  4729.3    0.04       0  5016.8    0.05       0
  5048.2    0.04       0  5052.2    0.05       0  5786.1    0.12       0
Bank Sta=5048.2,5052.2
Exp/Cntr=0.3,0.1

Type RM Length L Ch R = 1,541,189,189,189
BEGIN DESCRIPTION:
LGII4581
END DESCRIPTION:
XS GIS Cut Line= 6
      2469897.66     13562126.21      2470066.18     13561497.91
      2470235.14     13561336.37      2470192.92     13561253.12
      2470034.93     13561183.67      2469725.33     13560510.62
#Sta/Elev= 30
  4182.7  314.58  4225.3  313.42  4235.7  311.87  4270.4  312.62  4305.3  310.03
  4434.4  307.42  4535.7  305.12  4636.9  303.91  4714.8  302.89  4784.5  300.76
  4889.8  302.58  5009.5  302.52  5044.1  300.86  5053.9  301.90  5111.8  300.89
  5128.4  301.86  5134.0  300.77  5178.9  302.53  5318.6  303.55  5342.6  302.87
  5348.5  300.65  5392.1  298.19  5392.4  297.69  5396.1  298.19  5603.3  301.32
  5764.8  305.88  5849.6  310.38  5911.5  312.90  6050.3  312.60  6081.4  312.29
#Mann=11,-1,0
  4182.7   0.013       0  4434.4    0.05       0  4535.7    0.04       0
  4636.9    0.05       0  4714.8    0.04       0  4889.8    0.05       0
  5392.1    0.05       0  5396.1    0.05       0  5764.8    0.12       0
  5849.6    0.05       0  6050.3    0.12       0
Bank Sta=5392.1,5396.1
Exp/Cntr=0.3,0.1

Type RM Length L Ch R = 1,352,0,0,0
BEGIN DESCRIPTION:
LGII4580
END DESCRIPTION:
XS GIS Cut Line= 4
      2469965.86     13562090.34      2470332.08     13561612.82
      2470346.44     13561178.40      2469937.13     13560496.21
#Sta/Elev= 30
  4092.7  313.20  4117.1  312.65  4131.6  310.71  4266.3  306.85  4416.2  302.17
  4509.7  300.46  4530.5  299.47  4623.9  298.26  4659.2  296.92  4751.8  296.16
  4942.4  295.72  4962.4  295.38  4990.5  293.82  4990.7  293.32  4994.2  293.32
  4994.5  293.82  5012.5  294.87  5140.3  294.52  5146.1  295.12  5226.4  295.03
  5278.8  296.25  5490.2  297.56  5583.7  299.11  5599.6  299.30  5628.2  300.99
  5683.3  301.92  5800.2  306.34  5840.0  307.13  5845.8  307.67  5924.7  308.86
#Mann=9,-1,0
  4092.7   0.013       0  4266.3    0.04       0  4751.8    0.05       0
  4990.5    0.05       0  4994.5    0.05       0  5278.8    0.04       0
  5583.7    0.05       0  5683.3    0.12       0  5800.2    0.05       0
Bank Sta=4990.5,4994.5
Exp/Cntr=0.3,0.1

Chan Stop Cuts=-1