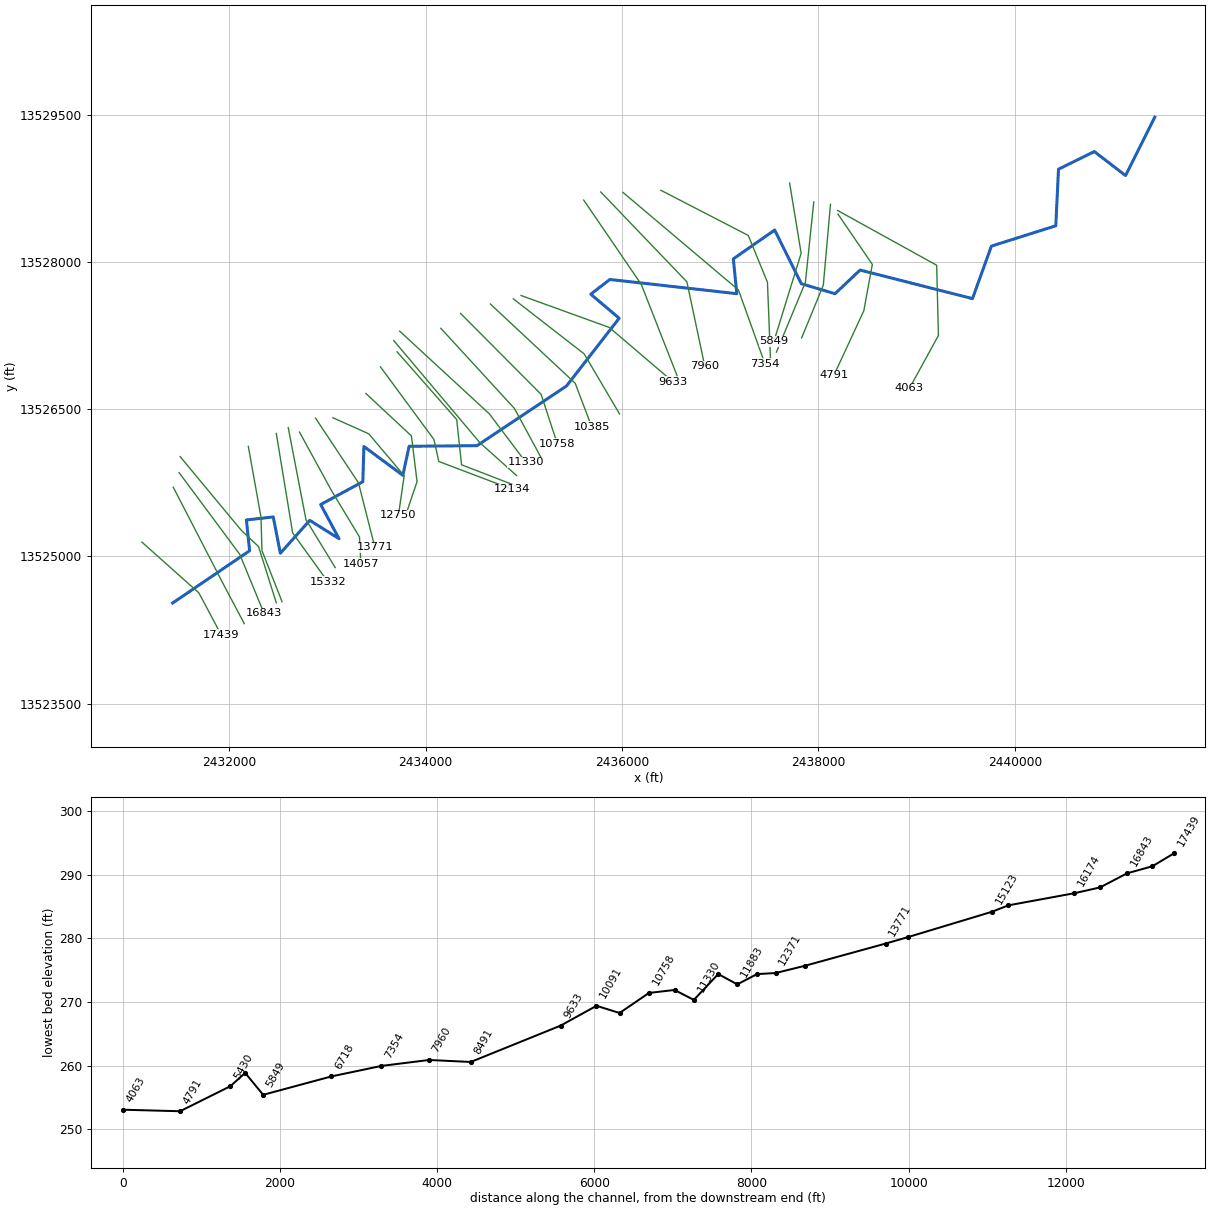
--- TRIB 5 TO SMITH CREEK.prj (project) ---

Proj Title=TRIB 5 TO SMITH CREEK Base Level Engineering
Current Plan=p01
Default Exp/Contr=0.3,0.1
English Units
Geom File=g01
Flow File=f01
Plan File=p01
BEGIN DESCRIPTION:
TRIB 5 TO SMITH CREEK
END DESCRIPTION:

--- TRIB 5 TO SMITH CREEK.p01 (plan) ---

Plan Title=Multiple Run
Short Identifier=Multiple
Geom File=g01
Flow File=f01
Subcritical Flow
K Sum by GR= 0
Std Step Tol= 0.01
Critical Tol= 0.01
Num of Std Step Trials= 20
Max Error Tol= 0.3
Flow Tol Ratio= 0.001
Split Flow NTrial= 30
Split Flow Tol= 0.02
Split Flow Ratio= 0.02
Log Output Level= 0
Friction Slope Method= 1
Unsteady Friction Slope Method= 2
Unsteady Bridges Friction Slope Method= 1
Parabolic Critical Depth
Global Vel Dist=  1 , 1 , 1
Global Log Level= 0
CheckData=True
Encroach Param= -1, 0, 0, 0
BEGIN DESCRIPTION:
Multiple Run
END DESCRIPTION:

--- TRIB 5 TO SMITH CREEK.f01 (steady flow) ---

Flow Title=Multiple
Number of Profiles=7
Profile Names=10-year,25-year,50-year,1pct_min,100-year,1pct_plu,500-year
River Rch & RM= TRIB 5 TO SMITH ,Reach-1,17439
    1022    1718    2372    1585    3162    6308    5563
River Rch & RM= TRIB 5 TO SMITH ,Reach-1,16174
    1059    1777    2450    1633    3258    6500    5709
River Rch & RM= TRIB 5 TO SMITH ,Reach-1,12134
    1692    2890    4031    2715    5417   10808    9690
River Rch & RM= TRIB 5 TO SMITH ,Reach-1,6718
    1791    3056    4261    2867    5720   11413   10212
Boundary for River Rch & Prof#=TRIB 5 TO SMITH ,Reach-1,1
Up Type=0
Dn Type=3
Dn Slope=0.005
Boundary for River Rch & Prof#=TRIB 5 TO SMITH ,Reach-1,2
Up Type=0
Dn Type=3
Dn Slope=0.005
Boundary for River Rch & Prof#=TRIB 5 TO SMITH ,Reach-1,3
Up Type=0
Dn Type=3
Dn Slope=0.005
Boundary for River Rch & Prof#=TRIB 5 TO SMITH ,Reach-1,4
Up Type=0
Dn Type=3
Dn Slope=0.005
Boundary for River Rch & Prof#=TRIB 5 TO SMITH ,Reach-1,5
Up Type=0
Dn Type=3
Dn Slope=0.005
Boundary for River Rch & Prof#=TRIB 5 TO SMITH ,Reach-1,6
Up Type=0
Dn Type=3
Dn Slope=0.005
Boundary for River Rch & Prof#=TRIB 5 TO SMITH ,Reach-1,7
Up Type=0
Dn Type=3
Dn Slope=0.005

--- TRIB 5 TO SMITH CREEK.g01 (geometry) ---

Geom Title=Existing Conditions

River Reach=TRIB 5 TO SMITH ,Reach-1
Reach XY= 30
      2431425.00     13524525.00      2432208.96     13525057.96
      2432176.03     13525371.39      2432449.52     13525402.16
      2432521.83     13525032.50      2432821.42     13525367.51
      2433119.59     13525180.10      2432932.65     13525528.69
      2433361.64     13525761.20      2433372.45     13526120.07
      2433769.17     13525826.53      2433833.05     13526122.17
      2434523.75     13526128.36      2435434.71     13526735.75
      2435971.70     13527426.76      2435682.58     13527671.66
      2435876.72     13527821.66      2437169.31     13527676.88
      2437133.96     13528031.67      2437554.87     13528325.41
      2437826.03     13527778.61      2438169.14     13527676.57
      2438424.91     13527917.71      2439568.98     13527626.61
      2439761.66     13528161.64      2440417.18     13528368.81
      2440444.76     13528945.42      2440809.79     13529124.76
      2441127.46     13528880.40      2441425.00     13529475.00

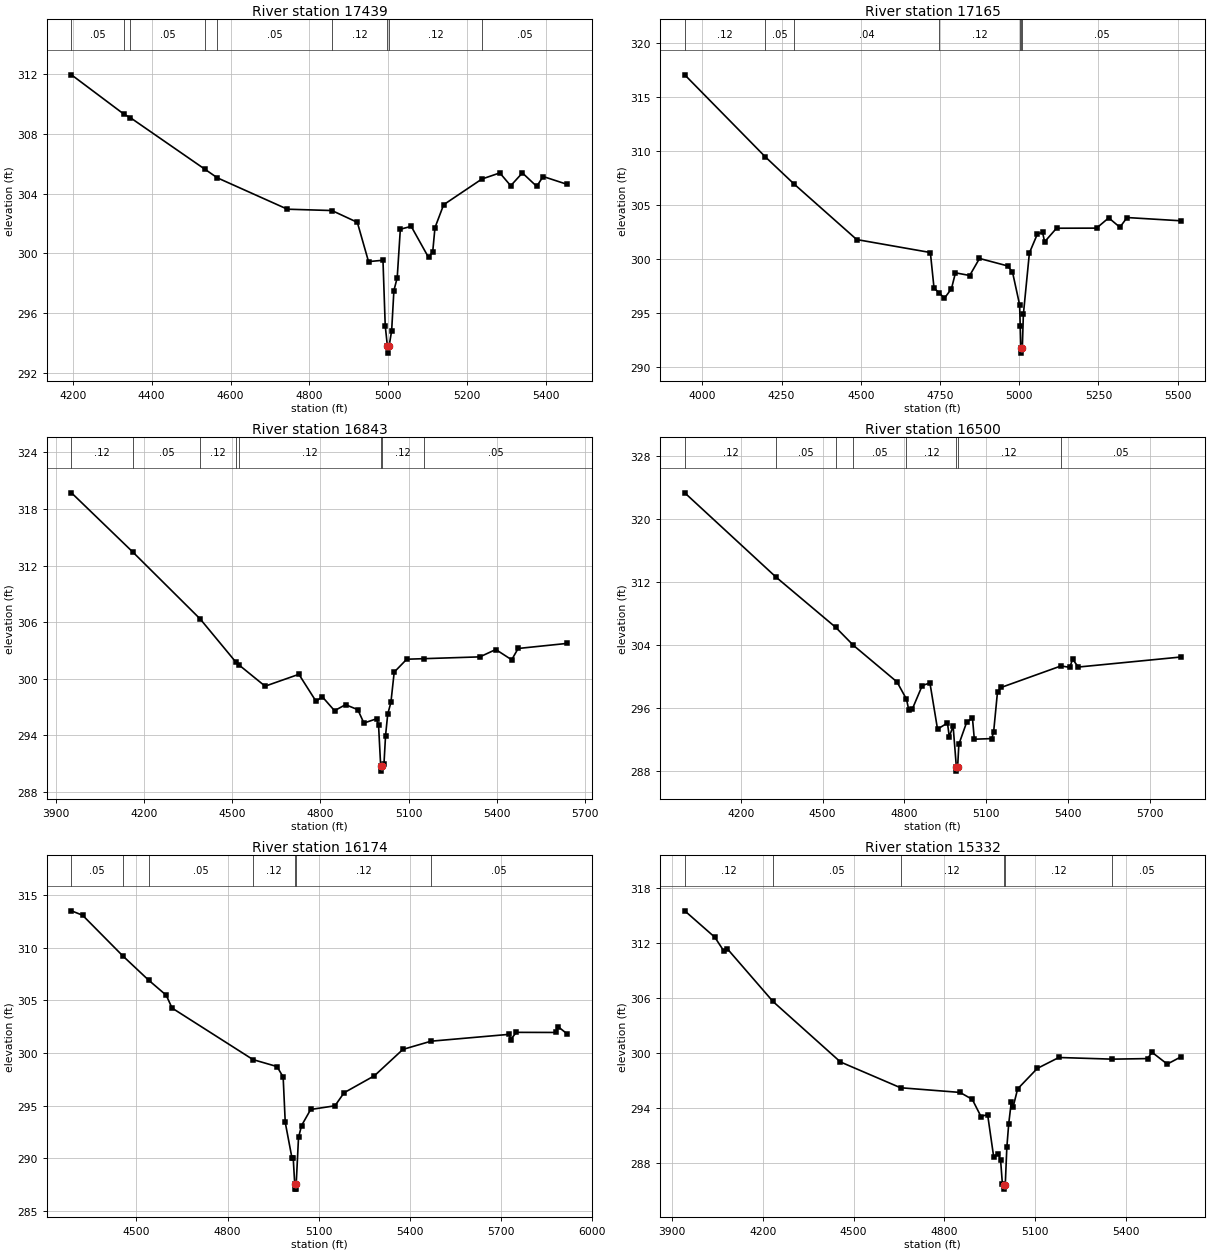
Type RM Length L Ch R = 1,17439,274,274,274
BEGIN DESCRIPTION:
Mapping XS 40598eb2
END DESCRIPTION:
XS GIS Cut Line= 3
      2431112.54     13525145.34      2431692.37     13524628.01
      2431918.09     13524204.36
#Sta/Elev= 30
  4196.7  311.96  4330.5  309.31  4346.0  309.09  4535.9  305.62  4566.6  305.06
  4744.1  302.96  4857.0  302.87  4921.4  302.08  4949.8  299.45  4986.4  299.54
  4992.1  295.16  4997.5  293.82  4997.9  293.32  5002.1  293.82  5008.4  294.82
  5014.1  297.51  5022.5  298.37  5030.4  301.62  5058.0  301.81  5101.9  299.73
  5112.5  300.10  5118.2  301.72  5140.2  303.26  5237.1  304.98  5282.6  305.39
  5310.2  304.53  5339.8  305.39  5376.1  304.49  5392.4  305.15  5453.8  304.62
#Mann=9,-1,0
  4196.7    0.05       0  4330.5    0.12       0  4346.0    0.05       0
  4535.9    0.04       0  4566.6    0.05       0  4857.0    0.12       0
  4997.5    0.05       0  5002.1    0.12       0  5237.1    0.05       0
Bank Sta=4997.5,5002.1
Exp/Cntr=0.3,0.1

Type RM Length L Ch R = 1,17165,322,322,322
BEGIN DESCRIPTION:
Mapping XS a77b0938
END DESCRIPTION:
XS GIS Cut Line= 3
      2431431.97     13525704.38      2431931.96     13524735.65
      2432154.16     13524315.54
#Sta/Elev= 30
  3944.2  317.08  4198.6  309.48  4289.2  306.97  4487.1  301.82  4719.6  300.62
  4731.2  297.31  4746.8  296.91  4763.9  296.38  4786.1  297.26  4798.8  298.74
  4843.8  298.49  4874.7  300.07  4963.3  299.38  4978.8  298.82  5001.3  295.78
  5003.3  293.79  5005.3  291.80  5005.7  291.30  5009.9  291.80  5013.2  294.89
  5032.2  300.58  5057.7  302.35  5073.8  302.48  5080.3  301.61  5117.8  302.87
  5244.2  302.88  5282.6  303.83  5317.9  302.96  5340.5  303.86  5509.6  303.56
#Mann=7,-1,0
  3944.2    0.12       0  4198.6    0.05       0  4289.2    0.04       0
  4746.8    0.12       0  5003.3    0.05       0  5005.3    0.05       0
  5009.9    0.05       0
Bank Sta=5005.3,5009.9
Exp/Cntr=0.3,0.1

Type RM Length L Ch R = 1,16843,343,343,343
BEGIN DESCRIPTION:
Mapping XS 0b2bb6ac
END DESCRIPTION:
XS GIS Cut Line= 3
      2431490.99     13525853.69      2432109.04     13525020.37
      2432355.49     13524419.87
#Sta/Elev= 30
  3953.4  319.71  4162.7  313.41  4391.2  306.33  4512.7  301.75  4521.7  301.49
  4612.1  299.20  4726.9  300.46  4785.4  297.59  4806.2  298.09  4848.2  296.60
  4885.5  297.24  4927.2  296.71  4948.1  295.29  4990.9  295.74  4997.8  295.11
  5005.2  290.69  5005.5  290.19  5009.8  290.69  5016.3  290.95  5021.7  293.96
  5029.1  296.24  5039.9  297.48  5051.1  300.69  5093.7  302.06  5153.3  302.12
  5342.6  302.31  5396.6  303.09  5450.7  302.00  5472.6  303.20  5640.0  303.74
#Mann=8,-1,0
  3953.4    0.12       0  4162.7    0.05       0  4391.2    0.12       0
  4512.7    0.04       0  4521.7    0.12       0  5005.2    0.05       0
  5009.8    0.12       0  5153.3    0.05       0
Bank Sta=5005.2,5009.8
Exp/Cntr=0.3,0.1

Type RM Length L Ch R = 1,16500,326,326,326
BEGIN DESCRIPTION:
Mapping XS 1e4e2308
END DESCRIPTION:
XS GIS Cut Line= 4
      2431501.41     13526016.88      2432126.40     13525263.42
      2432300.01     13525100.23      2432480.57     13524527.31
#Sta/Elev= 30
  3994.7  323.30  4329.8  312.59  4548.1  306.23  4612.5  303.96  4772.9  299.30
  4807.6  297.11  4815.7  295.80  4828.9  295.85  4865.4  298.84  4893.6  299.17
  4921.4  293.31  4957.9  294.09  4964.4  292.35  4978.6  293.69  4990.5  288.48
  4990.8  287.98  4995.1  288.48  4999.6  291.38  5028.0  294.16  5049.4  294.75
  5056.3  292.03  5120.2  292.11  5127.1  292.95  5141.3  298.06  5155.4  298.61
  5374.2  301.33  5406.1  301.15  5416.7  302.18  5437.6  301.19  5812.6  302.46
#Mann=8,-1,0
  3994.7    0.12       0  4329.8    0.05       0  4548.1    0.12       0
  4612.5    0.05       0  4807.6    0.12       0  4990.5    0.05       0
  4995.1    0.12       0  5374.2    0.05       0
Bank Sta=4990.5,4995.1
Exp/Cntr=0.3,0.1

Type RM Length L Ch R = 1,16174,842,842,842
BEGIN DESCRIPTION:
Mapping XS 69202b7e
END DESCRIPTION:
XS GIS Cut Line= 4
      2432195.84     13526121.07      2432324.32     13525402.31
      2432334.73     13525058.56      2432539.15     13524538.87
#Sta/Elev= 30
  4286.3  313.52  4322.9  313.10  4454.5  309.26  4540.0  306.94  4598.2  305.50
  4617.5  304.28  4884.0  299.38  4962.9  298.72  4983.2  297.73  4990.1  293.41
  5012.5  289.99  5016.4  289.99  5021.3  287.57  5021.7  287.07  5025.9  287.07
  5026.2  287.57  5033.8  291.98  5043.8  293.11  5073.8  294.64  5153.8  294.99
  5183.8  296.23  5283.9  297.85  5377.5  300.35  5470.1  301.13  5727.0  301.78
  5732.4  301.29  5751.0  301.97  5880.0  301.96  5889.6  302.48  5918.8  301.81
#Mann=7,-1,0
  4286.3    0.05       0  4454.5    0.12       0  4540.0    0.05       0
  4884.0    0.12       0  5021.3    0.05       0  5026.2    0.12       0
  5470.1    0.05       0
Bank Sta=5021.3,5026.2
Exp/Cntr=0.3,0.1

Type RM Length L Ch R = 1,15332,209,209,209
BEGIN DESCRIPTION:
Mapping XS 417a255c
END DESCRIPTION:
XS GIS Cut Line= 3
      2432480.56     13526253.04      2432647.23     13525239.12
      2433004.85     13524742.63
#Sta/Elev= 30
  3941.7  315.52  4041.1  312.64  4071.5  311.11  4081.6  311.41  4233.4  305.63
  4456.6  299.03  4655.1  296.22  4851.8  295.71  4892.3  294.95  4921.1  293.08
  4943.0  293.30  4963.3  288.63  4977.2  289.03  4985.8  288.38  4991.9  285.71
  4996.5  285.66  4996.8  285.16  5001.4  285.66  5006.6  289.73  5012.8  292.30
  5021.4  294.68  5027.5  294.14  5042.2  296.09  5107.3  298.33  5178.5  299.52
  5354.7  299.34  5471.8  299.40  5486.5  300.09  5536.8  298.80  5581.1  299.57
#Mann=6,-1,0
  3941.7    0.12       0  4233.4    0.05       0  4655.1    0.12       0
  4996.5    0.05       0  5001.4    0.12       0  5354.7    0.05       0
Bank Sta=4996.5,5001.4
Exp/Cntr=0.3,0.1

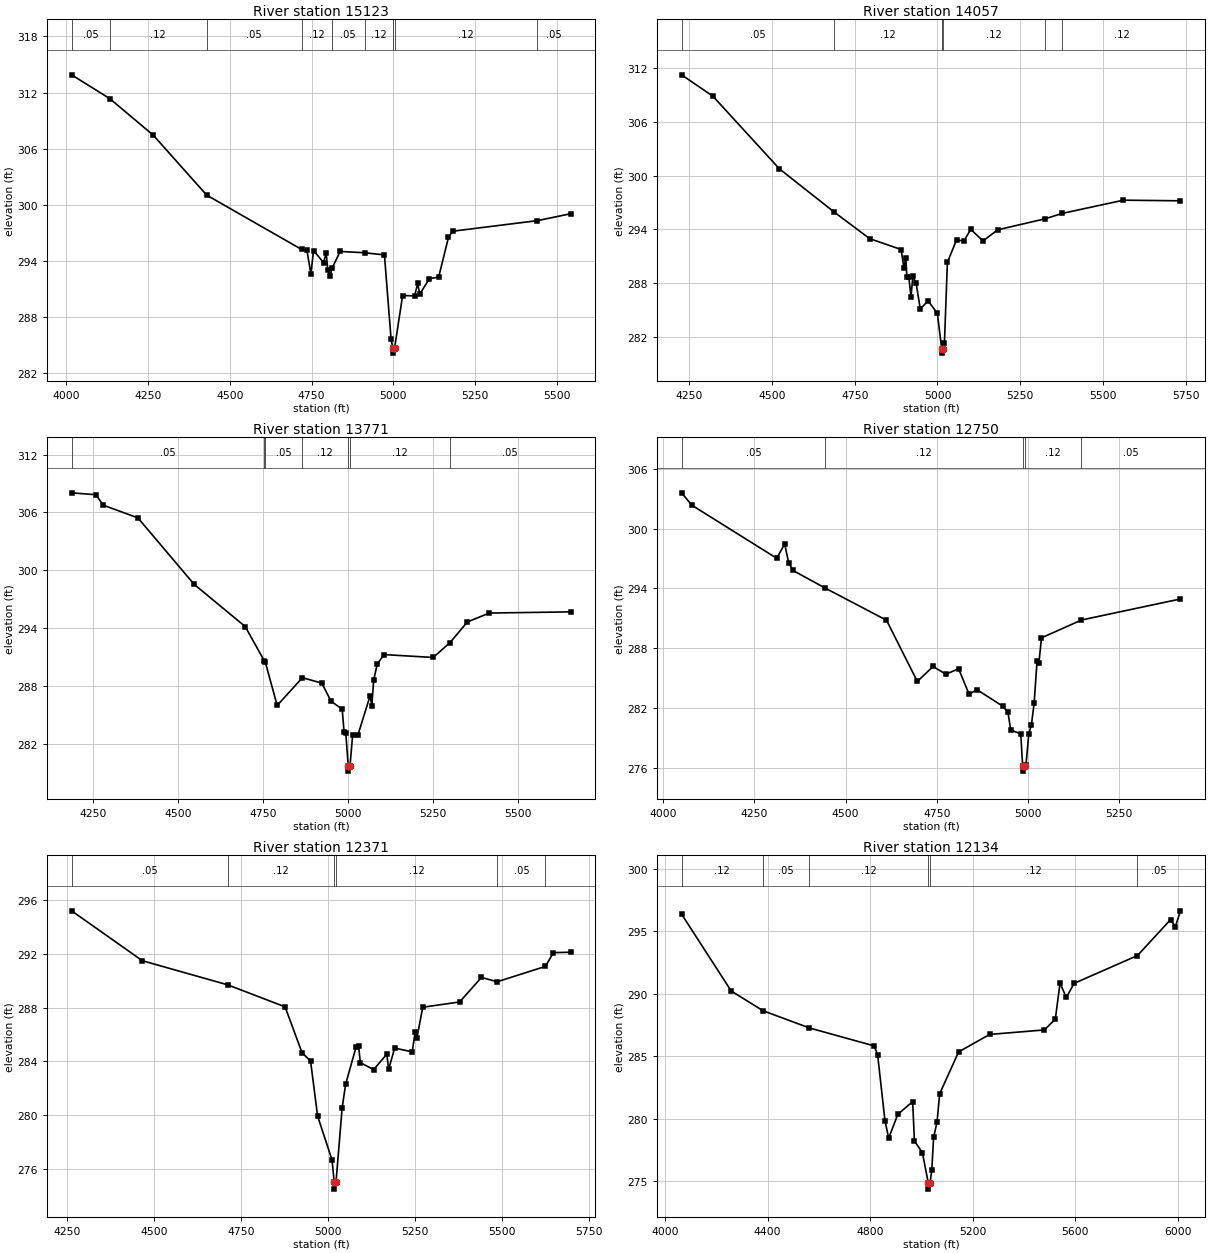
Type RM Length L Ch R = 1,15123,1066,1066,1066
BEGIN DESCRIPTION:
Mapping XS b3554768
END DESCRIPTION:
XS GIS Cut Line= 3
      2432602.09     13526312.08      2432782.65     13525374.53
      2433080.62     13524886.01
#Sta/Elev= 30
  4015.8  313.90  4132.8  311.35  4265.7  307.45  4429.2  301.04  4719.4  295.24
  4735.9  295.16  4748.1  292.61  4756.2  295.12  4786.8  293.83  4794.9  294.84
  4800.0  293.00  4807.2  292.38  4812.5  293.20  4837.7  295.02  4912.3  294.88
  4973.2  294.65  4993.5  285.64  4999.2  284.65  4999.5  284.15  5004.1  284.65
  5028.8  290.31  5065.5  290.27  5075.2  291.61  5081.0  290.44  5110.6  292.10
  5139.1  292.28  5169.2  296.52  5181.7  297.18  5440.8  298.31  5542.8  299.05
#Mann=9,-1,0
  4015.8    0.05       0  4132.8    0.12       0  4429.2    0.05       0
  4719.4    0.12       0  4812.5    0.05       0  4912.3    0.12       0
  4999.2    0.05       0  5004.1    0.12       0  5440.8    0.05       0
Bank Sta=4999.2,5004.1
Exp/Cntr=0.3,0.1

Type RM Length L Ch R = 1,14057,286,286,286
BEGIN DESCRIPTION:
Mapping XS 490cb87c
END DESCRIPTION:
XS GIS Cut Line= 4
      2432716.70     13526266.85      2433043.07     13525669.67
      2433327.79     13525197.45      2433341.68     13524923.16
#Sta/Elev= 30
  4227.1  311.24  4321.7  308.86  4522.9  300.74  4687.5  295.94  4795.1  292.96
  4890.2  291.74  4898.6  289.71  4904.3  290.85  4907.5  288.72  4913.3  288.72
  4920.0  286.47  4925.8  288.78  4935.5  287.99  4948.1  285.09  4971.5  286.02
  4999.6  284.63  5012.6  280.68  5013.0  280.18  5017.6  280.68  5021.0  281.35
  5029.9  290.31  5057.8  292.84  5079.2  292.67  5100.6  293.99  5137.5  292.70
  5181.7  293.94  5325.8  295.18  5377.3  295.78  5561.6  297.25  5733.7  297.18
#Mann=6,-1,0
  4227.1    0.05       0  4687.5    0.12       0  5012.6    0.05       0
  5017.6    0.12       0  5325.8    0.05       0  5377.3    0.12       0
Bank Sta=5012.6,5017.6
Exp/Cntr=0.3,0.1

Type RM Length L Ch R = 1,13771,1021,1021,1021
BEGIN DESCRIPTION:
Mapping XS 925dffbf
END DESCRIPTION:
XS GIS Cut Line= 3
      2432879.87     13526409.26      2433317.37     13525749.53
      2433484.04     13525093.28
#Sta/Elev= 30
  4186.4  308.03  4258.3  307.83  4279.3  306.75  4381.6  305.43  4547.0  298.54
  4697.4  294.16  4753.6  290.60  4756.8  290.44  4791.5  285.97  4865.7  288.85
  4923.0  288.29  4950.0  286.41  4982.9  285.59  4988.3  283.27  4993.4  283.13
  5000.8  279.66  5001.2  279.16  5005.8  279.66  5013.6  282.88  5029.2  282.91
  5065.0  286.97  5070.2  285.95  5075.5  288.58  5085.9  290.24  5105.9  291.25
  5250.9  290.95  5300.1  292.49  5351.6  294.64  5416.0  295.56  5655.1  295.68
#Mann=7,-1,0
  4186.4    0.05       0  4753.6    0.12       0  4756.8    0.05       0
  4865.7    0.12       0  5000.8    0.05       0  5005.8    0.12       0
  5300.1    0.05       0
Bank Sta=5000.8,5005.8
Exp/Cntr=0.3,0.1

Type RM Length L Ch R = 1,12750,379,379,379
BEGIN DESCRIPTION:
Mapping XS d69e068c
END DESCRIPTION:
XS GIS Cut Line= 4
      2433056.93     13526412.74      2433421.54     13526249.53
      2433782.65     13525822.45      2433723.89     13525418.06
#Sta/Elev= 30
  4050.5  303.59  4078.7  302.35  4311.3  297.03  4333.2  298.45  4344.2  296.59
  4355.8  295.81  4444.1  294.04  4612.2  290.82  4696.8  284.68  4739.7  286.18
  4774.8  285.41  4809.9  285.95  4838.5  283.41  4860.5  283.85  4930.8  282.20
  4945.1  281.58  4952.8  279.80  4980.2  279.43  4985.4  276.19  4985.8  275.69
  4990.5  276.19  4994.5  276.33  5002.3  279.43  5009.3  280.32  5016.8  282.47
  5024.8  286.70  5029.8  286.49  5037.0  289.05  5146.6  290.84  5417.9  292.95
#Mann=5,-1,0
  4050.5    0.05       0  4444.1    0.12       0  4985.4    0.05       0
  4990.5    0.12       0  5146.6    0.05       0
Bank Sta=4985.4,4990.5
Exp/Cntr=0.3,0.1

Type RM Length L Ch R = 1,12371,237,237,237
BEGIN DESCRIPTION:
Mapping XS 578f23e7
END DESCRIPTION:
XS GIS Cut Line= 4
      2433392.91     13526660.11      2433856.44     13526227.83
      2433913.73     13525761.69      2433807.52     13525448.26
#Sta/Elev= 30
  4263.6  295.17  4466.9  291.47  4712.4  289.68  4877.3  288.05  4926.0  284.65
  4950.6  284.02  4970.8  279.95  5012.4  276.68  5018.6  275.03  5019.0  274.53
  5023.7  275.03  5041.3  280.55  5051.4  282.31  5081.6  285.09  5088.6  285.16
  5093.7  283.90  5132.0  283.40  5169.9  284.54  5174.9  283.41  5192.4  284.99
  5242.8  284.71  5251.2  286.19  5256.2  285.73  5273.1  288.02  5379.0  288.41
  5441.9  290.23  5487.1  289.91  5625.9  291.05  5648.6  292.07  5698.0  292.10
#Mann=6,-1,0
  4263.6    0.05       0  4712.4    0.12       0  5018.6    0.05       0
  5023.7    0.12       0  5487.1    0.05       0  5625.9    0.12       0
Bank Sta=5018.6,5023.7
Exp/Cntr=0.3,0.1

Type RM Length L Ch R = 1,12134,251,251,251
BEGIN DESCRIPTION:
Mapping XS 5b669f1d
END DESCRIPTION:
XS GIS Cut Line= 4
      2433541.32     13526930.97      2434085.60     13526191.37
      2434135.08     13525967.42      2434881.24     13525684.03
#Sta/Elev= 30
  4064.3  296.39  4258.0  290.23  4381.9  288.65  4562.7  287.27  4815.9  285.83
  4829.1  285.11  4857.6  279.85  4872.2  278.44  4907.7  280.35  4965.7  281.37
  4972.5  278.22  5003.7  277.28  5026.5  274.86  5027.0  274.36  5033.6  274.86
  5040.3  275.89  5047.4  278.50  5060.8  279.74  5071.0  282.00  5144.9  285.35
  5265.8  286.75  5479.3  287.11  5522.1  287.98  5540.4  290.86  5564.9  289.71
  5595.3  290.84  5842.5  293.07  5971.3  295.94  5990.3  295.39  6010.1  296.65
#Mann=6,-1,0
  4064.3    0.12       0  4381.9    0.05       0  4562.7    0.12       0
  5026.5    0.05       0  5033.6    0.12       0  5842.5    0.05       0
Bank Sta=5026.5,5033.6
Exp/Cntr=0.3,0.1

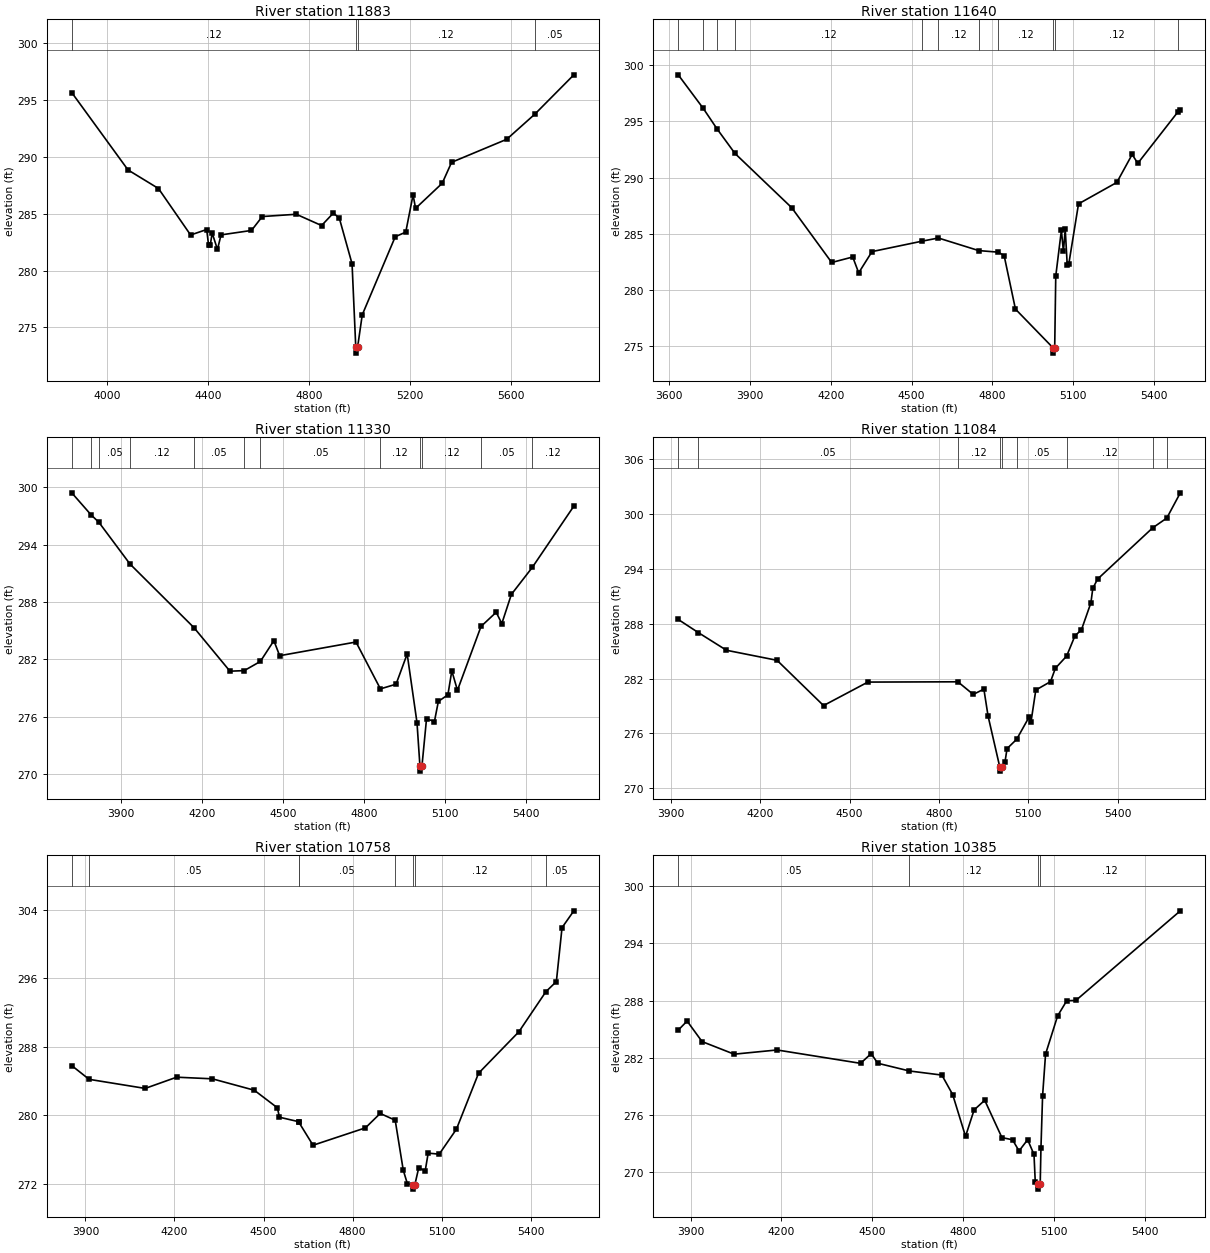
Type RM Length L Ch R = 1,11883,243,243,243
BEGIN DESCRIPTION:
Mapping XS 20e76a16
END DESCRIPTION:
XS GIS Cut Line= 4
      2433710.59     13527084.62      2434317.37     13526394.50
      2434366.85     13525933.56      2434930.94     13525715.21
#Sta/Elev= 30
  3860.7  295.62  4083.4  288.83  4203.9  287.20  4331.1  283.12  4394.7  283.60
  4402.2  282.24  4408.9  282.24  4416.5  283.29  4437.4  281.85  4451.6  283.13
  4572.1  283.52  4614.8  284.74  4749.5  284.94  4849.5  283.95  4896.4  285.05
  4919.9  284.59  4970.2  280.59  4984.9  273.25  4985.4  272.75  4992.0  273.25
  5010.5  276.11  5141.2  282.97  5182.7  283.37  5211.6  286.64  5221.7  285.46
  5327.0  287.66  5364.2  289.50  5582.3  291.52  5693.8  293.73  5848.1  297.18
#Mann=4,-1,0
  3860.7    0.12       0  4984.9    0.05       0  4992.0    0.12       0
  5693.8    0.05       0
Bank Sta=4984.9,4992
Exp/Cntr=0.3,0.1

Type RM Length L Ch R = 1,11640,310,310,310
BEGIN DESCRIPTION:
Mapping XS da156db1
END DESCRIPTION:
XS GIS Cut Line= 3
      2433676.72     13527199.22      2434554.35     13526157.52
      2434926.74     13525824.20
#Sta/Elev= 30
  3634.8  299.15  3727.3  296.17  3778.9  294.33  3845.2  292.15  4055.6  287.32
  4203.9  282.44  4281.9  282.93  4304.0  281.52  4353.4  283.41  4539.2  284.34
  4599.5  284.62  4749.1  283.50  4821.4  283.36  4843.3  283.06  4885.3  278.29
  5023.6  274.87  5024.1  274.37  5030.9  274.87  5034.8  281.23  5055.7  285.31
  5063.2  283.43  5069.9  285.40  5077.4  282.21  5083.2  282.32  5119.2  287.66
  5261.3  289.57  5318.1  292.06  5339.0  291.27  5488.8  295.88  5496.7  296.02
#Mann=11,-1,0
  3634.8    0.05       0  3727.3    0.12       0  3778.9    0.05       0
  3845.2    0.12       0  4539.2    0.05       0  4599.5    0.12       0
  4749.1    0.05       0  4821.4    0.12       0  5023.6    0.05       0
  5030.9    0.12       0  5488.8    0.05       0
Bank Sta=5023.6,5030.9
Exp/Cntr=0.3,0.1

Type RM Length L Ch R = 1,11330,246,246,246
BEGIN DESCRIPTION:
Mapping XS 487a91fd
END DESCRIPTION:
XS GIS Cut Line= 3
      2433736.68     13527295.51      2434650.71     13526451.79
      2435021.97     13525958.50
#Sta/Elev= 30
  3716.4  299.41  3788.2  297.10  3816.9  296.33  3932.1  291.97  4169.5  285.31
  4302.8  280.76  4355.8  280.82  4415.6  281.78  4465.6  283.95  4487.1  282.38
  4770.1  283.81  4860.6  278.91  4918.6  279.40  4959.8  282.56  4996.2  275.39
  5007.2  270.81  5007.7  270.31  5014.5  270.81  5031.6  275.79  5060.8  275.49
  5075.4  277.60  5110.8  278.29  5125.3  280.80  5146.2  278.76  5233.6  285.44
  5289.8  286.92  5310.7  285.74  5346.1  288.79  5423.6  291.61  5577.7  298.02
#Mann=12,-1,0
  3716.4    0.05       0  3788.2    0.12       0  3816.9    0.05       0
  3932.1    0.12       0  4169.5    0.05       0  4355.8    0.12       0
  4415.6    0.05       0  4860.6    0.12       0  5007.2    0.05       0
  5014.5    0.12       0  5233.6    0.05       0  5423.6    0.12       0
Bank Sta=5007.2,5014.5
Exp/Cntr=0.3,0.1

Type RM Length L Ch R = 1,11084,326,326,326
BEGIN DESCRIPTION:
Mapping XS e549179e
END DESCRIPTION:
XS GIS Cut Line= 3
      2434155.89     13527324.22      2434905.92     13526506.48
      2435179.36     13526001.25
#Sta/Elev= 30
  3925.5  288.46  3993.0  287.02  4087.3  285.09  4257.0  283.99  4412.9  279.04
  4561.6  281.61  4863.5  281.64  4915.0  280.26  4950.7  280.84  4964.8  277.89
  5003.7  272.37  5004.2  271.87  5011.0  272.37  5021.6  272.88  5028.4  274.33
  5060.6  275.35  5103.0  277.82  5108.7  277.24  5124.9  280.74  5174.3  281.66
  5190.5  283.12  5228.4  284.46  5256.2  286.67  5278.0  287.33  5309.7  290.28
  5316.1  291.87  5332.3  292.88  5516.9  298.48  5564.3  299.55  5609.6  302.31
#Mann=9,-1,0
  3925.5    0.12       0  3993.0    0.05       0  4863.5    0.12       0
  5003.7    0.05       0  5011.0    0.12       0  5060.6    0.05       0
  5228.4    0.12       0  5516.9    0.05       0  5564.3    0.03       0
Bank Sta=5003.7,5011
Exp/Cntr=0.3,0.1

Type RM Length L Ch R = 1,10758,373,373,373
BEGIN DESCRIPTION:
Mapping XS f2432a00
END DESCRIPTION:
XS GIS Cut Line= 3
      2434356.40     13527476.13      2435176.75     13526651.44
      2435341.33     13526149.03
#Sta/Elev= 30
  3853.9  285.81  3912.3  284.21  4101.2  283.15  4207.3  284.46  4327.5  284.27
  4468.9  282.94  4546.7  280.89  4553.7  279.79  4618.4  279.27  4619.0  279.21
  4666.9  276.52  4843.6  278.55  4893.2  280.23  4943.8  279.44  4970.9  273.62
  4985.1  272.00  5002.6  271.90  5003.1  271.40  5009.9  271.90  5023.1  273.89
  5044.9  273.53  5054.9  275.60  5092.1  275.48  5150.2  278.40  5224.7  284.92
  5360.6  289.76  5451.5  294.43  5486.9  295.62  5506.0  301.91  5545.8  303.87
#Mann=8,-1,0
  3853.9    0.12       0  3912.3    0.05       0  4618.4    0.12       0
  4619.0    0.05       0  4943.8    0.12       0  5002.6    0.05       0
  5009.9    0.12       0  5451.5    0.05       0
Bank Sta=5002.6,5009.9
Exp/Cntr=0.3,0.1

Type RM Length L Ch R = 1,10385,294,294,294
BEGIN DESCRIPTION:
Mapping XS 39e01313
END DESCRIPTION:
XS GIS Cut Line= 3
      2434660.24     13527571.60      2435523.97     13526764.29
      2435692.71     13526318.65
#Sta/Elev= 30
  3859.4  284.91  3888.7  285.86  3938.1  283.71  4044.1  282.39  4185.8  282.83
  4461.8  281.43  4496.9  282.45  4518.4  281.44  4623.1  280.63  4730.4  280.20
  4766.1  278.16  4808.6  273.78  4836.9  276.55  4872.0  277.56  4928.8  273.65
  4963.9  273.42  4985.4  272.25  5013.8  273.43  5034.8  271.88  5039.0  268.98
  5047.9  268.75  5048.4  268.25  5055.3  268.75  5057.8  272.60  5063.2  278.04
  5073.0  282.40  5112.8  286.40  5143.0  287.99  5173.1  288.02  5518.2  297.41
#Mann=4,-1,0
  3859.4    0.05       0  4623.1    0.12       0  5047.9    0.05       0
  5055.3    0.12       0
Bank Sta=5047.9,5055.3
Exp/Cntr=0.3,0.1

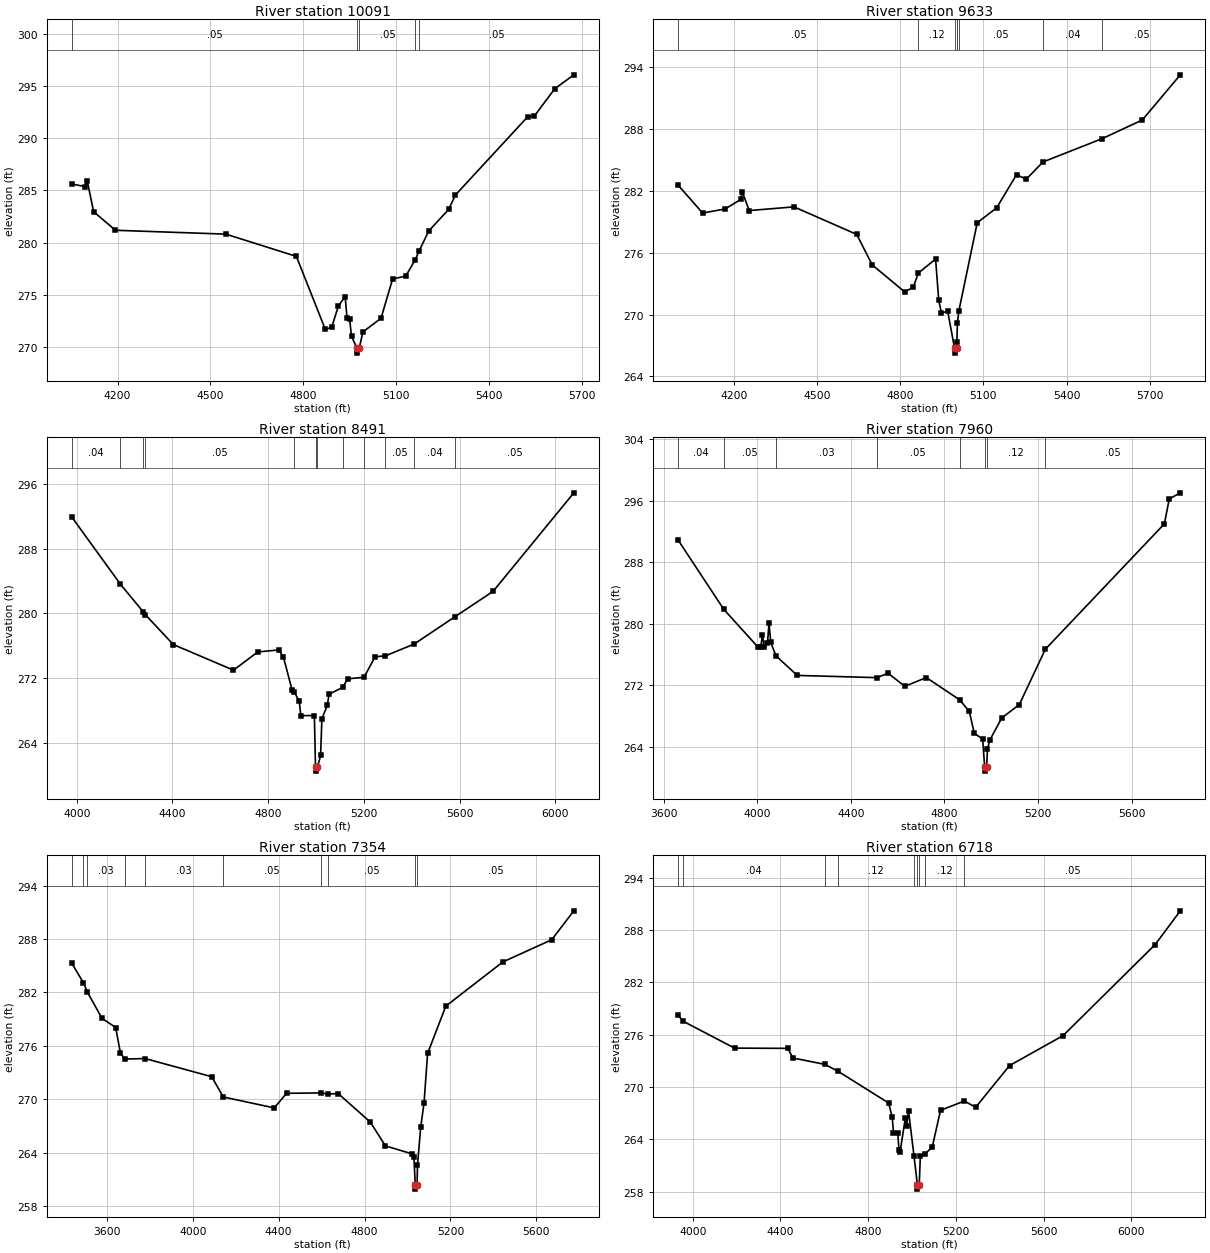
Type RM Length L Ch R = 1,10091,458,458,458
BEGIN DESCRIPTION:
Mapping XS c0a34fea
END DESCRIPTION:
XS GIS Cut Line= 3
      2434894.59     13527623.70      2435615.12     13527063.77
      2435975.34     13526451.83
#Sta/Elev= 30
  4052.0  285.63  4093.7  285.38  4101.9  285.93  4122.7  282.96  4193.3  281.18
  4549.8  280.81  4777.9  278.67  4871.1  271.68  4891.9  271.85  4913.7  273.91
  4935.4  274.81  4941.7  272.74  4949.9  272.65  4956.2  270.98  4973.5  269.88
  4974.0  269.38  4981.2  269.88  4993.0  271.42  5051.5  272.73  5088.7  276.49
  5131.6  276.79  5162.4  278.37  5174.0  279.16  5205.8  281.12  5270.2  283.19
  5291.7  284.56  5526.0  292.10  5547.4  292.17  5612.9  294.77  5674.6  296.11
#Mann=5,-1,0
  4052.0    0.05       0  4973.5    0.05       0  4981.2    0.05       0
  5162.4    0.12       0  5174.0    0.05       0
Bank Sta=4973.5,4981.2
Exp/Cntr=0.3,0.1

Type RM Length L Ch R = 1,9633,1142,1142,1142
BEGIN DESCRIPTION:
Mapping XS 49bd0a09
END DESCRIPTION:
XS GIS Cut Line= 3
      2434972.79     13527658.37      2435871.19     13527332.87
      2436521.09     13526778.29
#Sta/Elev= 30
  4000.1  282.53  4088.1  279.84  4169.4  280.24  4225.3  281.16  4230.6  281.92
  4256.0  280.08  4417.3  280.44  4643.5  277.77  4699.5  274.81  4816.7  272.19
  4847.3  272.65  4866.0  274.03  4927.8  275.38  4939.2  271.37  4949.1  270.14
  4971.3  270.34  4996.0  266.76  4996.5  266.26  5003.8  266.76  5004.4  267.30
  5006.5  269.20  5011.6  270.34  5077.9  278.90  5148.1  280.35  5219.5  283.56
  5254.6  283.12  5314.8  284.79  5528.9  287.06  5672.9  288.86  5810.0  293.24
#Mann=8,-1,0
  4000.1    0.05       0  4866.0    0.12       0  4996.0    0.05       0
  5003.8    0.12       0  5004.4    0.04       0  5011.6    0.05       0
  5314.8    0.04       0  5528.9    0.05       0
Bank Sta=4996,5003.8
Exp/Cntr=0.3,0.1

Type RM Length L Ch R = 1,8491,531,531,531
BEGIN DESCRIPTION:
Mapping XS f9bd79f9
END DESCRIPTION:
XS GIS Cut Line= 3
      2435610.77     13528630.62      2436196.71     13527771.24
      2436583.00     13526785.99
#Sta/Elev= 30
  3979.1  291.90  4182.7  283.60  4277.6  280.21  4285.9  279.87  4403.6  276.17
  4655.0  273.01  4756.6  275.26  4843.4  275.50  4863.4  274.67  4900.3  270.51
  4909.6  270.29  4930.0  269.15  4936.2  267.40  4993.0  267.42  4997.8  261.06
  4998.3  260.56  5006.0  261.06  5019.2  262.50  5024.4  267.04  5047.4  268.67
  5054.2  270.04  5110.7  270.88  5132.9  271.95  5200.7  272.13  5246.8  274.67
  5289.5  274.77  5410.1  276.23  5580.1  279.59  5740.4  282.74  6077.5  294.88
#Mann=12,-1,0
  3979.1    0.04       0  4182.7    0.05       0  4277.6    0.03       0
  4285.9    0.05       0  4909.6    0.12       0  4997.8    0.05       0
  5006.0    0.12       0  5110.7    0.05       0  5200.7    0.04       0
  5289.5    0.05       0  5410.1    0.04       0  5580.1    0.05       0
Bank Sta=4997.8,5006
Exp/Cntr=0.3,0.1

Type RM Length L Ch R = 1,7960,606,606,606
BEGIN DESCRIPTION:
Mapping XS 63b93bcb
END DESCRIPTION:
XS GIS Cut Line= 3
      2435784.36     13528713.11      2436661.12     13527797.28
      2436843.20     13526938.93
#Sta/Elev= 30
  3662.9  290.85  3857.3  281.89  4001.6  277.04  4015.7  276.97  4022.6  278.61
  4029.9  276.97  4044.0  277.46  4050.9  280.06  4058.2  277.58  4080.5  275.84
  4171.4  273.30  4511.5  273.01  4560.1  273.58  4630.9  271.88  4723.0  273.02
  4865.2  270.13  4906.7  268.62  4928.1  265.76  4963.8  265.06  4972.2  261.37
  4972.7  260.87  4980.5  261.37  4984.2  263.72  4994.4  264.91  5045.5  267.78
  5120.2  269.51  5231.5  276.70  5740.1  292.98  5761.1  296.23  5808.2  297.01
#Mann=8,-1,0
  3662.9    0.04       0  3857.3    0.05       0  4080.5    0.03       0
  4511.5    0.05       0  4865.2    0.12       0  4972.2    0.05       0
  4980.5    0.12       0  5231.5    0.05       0
Bank Sta=4972.2,4980.5
Exp/Cntr=0.3,0.1

Type RM Length L Ch R = 1,7354,636,636,636
BEGIN DESCRIPTION:
Mapping XS 090f33ff
END DESCRIPTION:
XS GIS Cut Line= 3
      2436010.10     13528708.72      2437186.30     13527714.81
      2437455.38     13526963.97
#Sta/Elev= 30
  3436.9  285.29  3491.4  283.08  3510.1  282.02  3577.6  279.10  3641.3  278.07
  3663.3  275.22  3683.8  274.53  3778.4  274.59  4088.5  272.55  4142.1  270.28
  4379.7  269.05  4436.9  270.69  4597.6  270.73  4630.3  270.61  4677.5  270.66
  4826.9  267.46  4897.2  264.79  5020.9  263.90  5029.7  263.55  5036.1  260.44
  5036.6  259.94  5044.5  260.44  5046.4  262.60  5061.6  266.92  5077.1  269.65
  5093.5  275.16  5178.4  280.47  5444.0  285.43  5671.0  287.91  5774.4  291.16
#Mann=10,-1,0
  3436.9    0.04       0  3491.4    0.05       0  3510.1    0.03       0
  3683.8    0.05       0  3778.4    0.03       0  4142.1    0.05       0
  4597.6    0.12       0  4630.3    0.05       0  5036.1    0.05       0
  5044.5    0.05       0
Bank Sta=5036.1,5044.5
Exp/Cntr=0.3,0.1

Type RM Length L Ch R = 1,6718,869,869,869
BEGIN DESCRIPTION:
Mapping XS 43ac15c3
END DESCRIPTION:
XS GIS Cut Line= 4
      2436396.33     13528730.46      2437286.12     13528270.37
      2437481.44     13527792.94      2437511.82     13527020.37
#Sta/Elev= 30
  3933.5  278.22  3955.8  277.55  4190.5  274.47  4434.1  274.44  4456.3  273.34
  4603.0  272.60  4662.0  271.82  4893.5  268.17  4910.0  266.51  4915.6  264.71
  4935.2  264.68  4940.5  262.83  4945.9  262.58  4969.9  266.50  4975.3  265.49
  4984.2  267.24  5009.5  262.04  5024.5  258.79  5025.0  258.29  5033.0  258.79
  5038.2  262.13  5058.7  262.32  5092.3  263.11  5130.2  267.33  5238.9  268.40
  5290.5  267.68  5445.3  272.47  5689.2  275.90  6109.5  286.35  6224.2  290.22
#Mann=9,-1,0
  3933.5    0.05       0  3955.8    0.04       0  4603.0    0.05       0
  4662.0    0.12       0  5009.5    0.05       0  5024.5    0.05       0
  5033.0    0.05       0  5058.7    0.12       0  5238.9    0.05       0
Bank Sta=5024.5,5033
Exp/Cntr=0.3,0.1

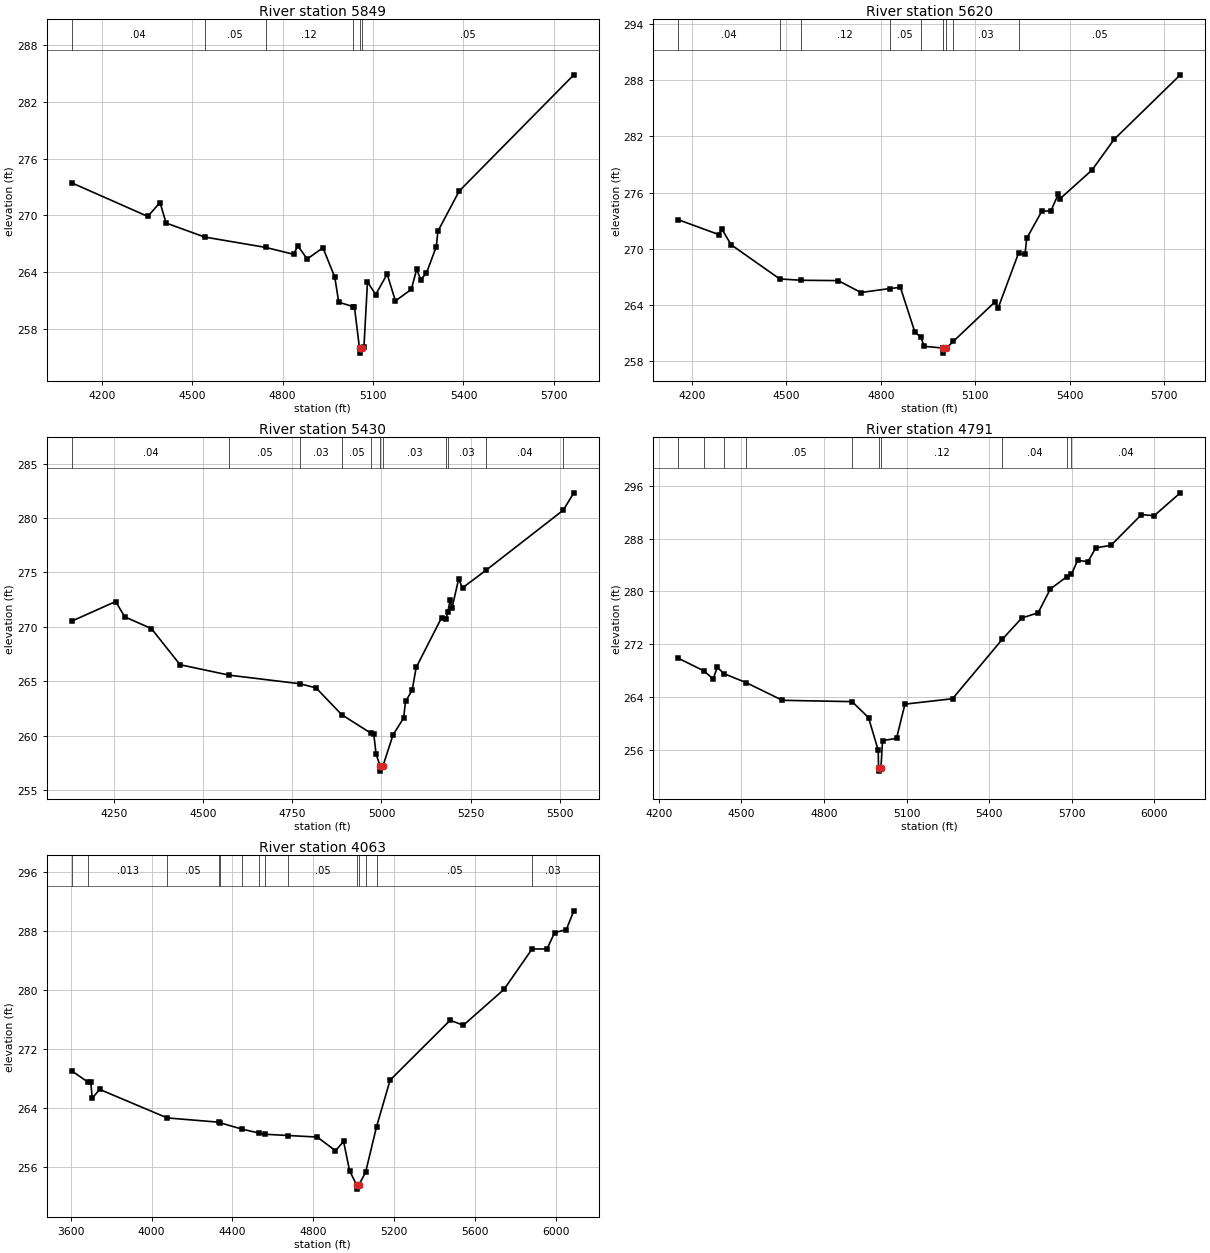
Type RM Length L Ch R = 1,5849,229,229,229
BEGIN DESCRIPTION:
Mapping XS f0776596
END DESCRIPTION:
XS GIS Cut Line= 3
      2437707.13     13528804.24      2437824.32     13528088.08
      2437546.60     13527189.82
#Sta/Elev= 30
  4100.2  273.44  4352.8  269.88  4393.3  271.35  4413.6  269.18  4540.9  267.70
  4743.5  266.60  4837.4  265.86  4850.0  266.80  4881.4  265.37  4933.8  266.56
  4973.2  263.44  4986.1  260.80  5033.1  260.33  5038.4  260.26  5055.1  255.90
  5055.6  255.40  5063.6  255.90  5069.9  256.08  5081.5  262.93  5108.9  261.61
  5146.8  263.77  5174.2  260.93  5226.9  262.15  5244.7  264.27  5258.3  263.19
  5277.3  263.89  5309.9  266.69  5315.1  268.31  5385.6  272.56  5766.1  284.88
#Mann=6,-1,0
  4100.2    0.04       0  4540.9    0.05       0  4743.5    0.12       0
  5033.1    0.05       0  5055.1    0.05       0  5063.6    0.05       0
Bank Sta=5055.1,5063.6
Exp/Cntr=0.3,0.1

Type RM Length L Ch R = 1,5620,190,190,190
BEGIN DESCRIPTION:
Mapping XS 29b89590
END DESCRIPTION:
XS GIS Cut Line= 3
      2437953.06     13528612.16      2437867.72     13527792.94
      2437572.59     13527081.16
#Sta/Elev= 30
  4156.7  273.11  4286.2  271.51  4294.6  272.16  4324.8  270.43  4479.3  266.77
  4546.9  266.63  4665.2  266.59  4737.0  265.32  4827.9  265.74  4862.3  265.87
  4907.9  261.13  4927.3  260.53  4938.1  259.57  4997.3  259.38  4998.5  259.34
  4999.0  258.84  5007.2  259.34  5030.7  260.11  5162.4  264.31  5173.0  263.70
  5237.4  269.53  5257.9  269.39  5263.3  271.11  5311.1  274.00  5340.4  274.06
  5364.2  275.89  5369.6  275.36  5470.6  278.41  5541.1  281.70  5750.9  288.59
#Mann=10,-1,0
  4156.7    0.04       0  4479.3    0.05       0  4546.9    0.12       0
  4827.9    0.05       0  4927.3    0.03       0  4997.3    0.05       0
  4998.5    0.05       0  5007.2    0.05       0  5030.7    0.03       0
  5237.4    0.05       0
Bank Sta=4998.5,5007.2
Exp/Cntr=0.3,0.1

Type RM Length L Ch R = 1,5430,639,639,639
BEGIN DESCRIPTION:
Mapping XS 7a044baf
END DESCRIPTION:
XS GIS Cut Line= 3
      2438123.21     13528587.91      2438050.01     13527762.56
      2437829.31     13527225.96
#Sta/Elev= 30
  4130.9  270.52  4254.3  272.33  4279.9  270.92  4354.7  269.84  4435.0  266.52
  4573.0  265.56  4771.5  264.77  4816.5  264.39  4888.5  261.93  4970.8  260.22
  4978.5  260.15  4984.8  258.34  4995.7  257.24  4996.2  256.74  5004.4  257.24
  5032.5  260.07  5062.1  261.62  5067.5  263.14  5086.1  264.17  5097.4  266.27
  5168.8  270.85  5180.8  270.69  5186.5  271.41  5192.7  272.47  5198.1  271.74
  5216.4  274.39  5227.5  273.59  5294.4  275.23  5510.1  280.73  5539.7  282.32
#Mann=11,-1,0
  4130.9    0.04       0  4573.0    0.05       0  4771.5    0.03       0
  4888.5    0.05       0  4970.8    0.03       0  4995.7    0.03       0
  5004.4    0.03       0  5180.8    0.05       0  5186.5    0.03       0
  5294.4    0.04       0  5510.1    0.05       0
Bank Sta=4995.7,5004.4
Exp/Cntr=0.3,0.1

Type RM Length L Ch R = 1,4791,728,728,728
BEGIN DESCRIPTION:
Mapping XS 31265b01
END DESCRIPTION:
XS GIS Cut Line= 4
      2438199.56     13528487.20      2438549.14     13527975.23
      2438462.34     13527502.14      2438158.52     13526846.76
#Sta/Elev= 30
  4270.6  269.91  4363.6  267.99  4398.0  266.76  4412.9  268.56  4435.9  267.58
  4516.8  266.22  4649.2  263.53  4902.3  263.33  4961.9  260.91  4997.1  255.97
  4998.3  253.32  4998.8  252.82  5007.0  253.32  5012.8  257.43  5063.6  257.78
  5094.1  262.95  5266.9  263.77  5447.2  272.74  5518.5  275.98  5577.8  276.77
  5621.9  280.36  5682.8  282.25  5698.5  282.59  5721.1  284.69  5758.6  284.50
  5787.2  286.59  5842.3  286.97  5952.9  291.62  5998.7  291.44  6093.9  294.91
#Mann=10,-1,0
  4270.6    0.04       0  4363.6   0.013       0  4435.9    0.04       0
  4516.8    0.05       0  4902.3    0.12       0  4998.3    0.05       0
  5007.0    0.12       0  5447.2    0.04       0  5682.8    0.05       0
  5698.5    0.04       0
Bank Sta=4998.3,5007
Exp/Cntr=0.3,0.1

Type RM Length L Ch R = 1,4063,0,0,0
BEGIN DESCRIPTION:
Mapping XS 881bd8b6
END DESCRIPTION:
XS GIS Cut Line= 4
      2438195.86     13528524.84      2439204.53     13527966.55
      2439221.89     13527250.40      2438926.76     13526712.24
#Sta/Elev= 30
  3604.9  269.08  3688.2  267.50  3699.3  267.55  3706.8  265.36  3742.8  266.57
  4077.5  262.70  4333.4  262.12  4339.3  262.04  4447.6  261.18  4532.9  260.64
  4561.8  260.49  4676.0  260.32  4819.3  260.11  4909.4  258.26  4949.4  259.51
  4979.0  255.56  5014.9  253.56  5015.4  253.06  5023.8  253.56  5058.2  255.34
  5112.4  261.51  5179.4  267.82  5476.3  275.92  5541.7  275.25  5742.6  280.10
  5881.7  285.58  5955.0  285.57  5992.9  287.79  6050.5  288.19  6087.9  290.74
#Mann=14,-1,0
  3604.9    0.04       0  3688.2   0.013       0  4077.5    0.05       0
  4333.4   0.013       0  4339.3    0.05       0  4447.6    0.12       0
  4532.9    0.05       0  4561.8    0.12       0  4676.0    0.05       0
  5014.9    0.05       0  5023.8    0.05       0  5058.2    0.12       0
  5112.4    0.05       0  5881.7    0.03       0
Bank Sta=5014.9,5023.8
Exp/Cntr=0.3,0.1

Chan Stop Cuts=-1