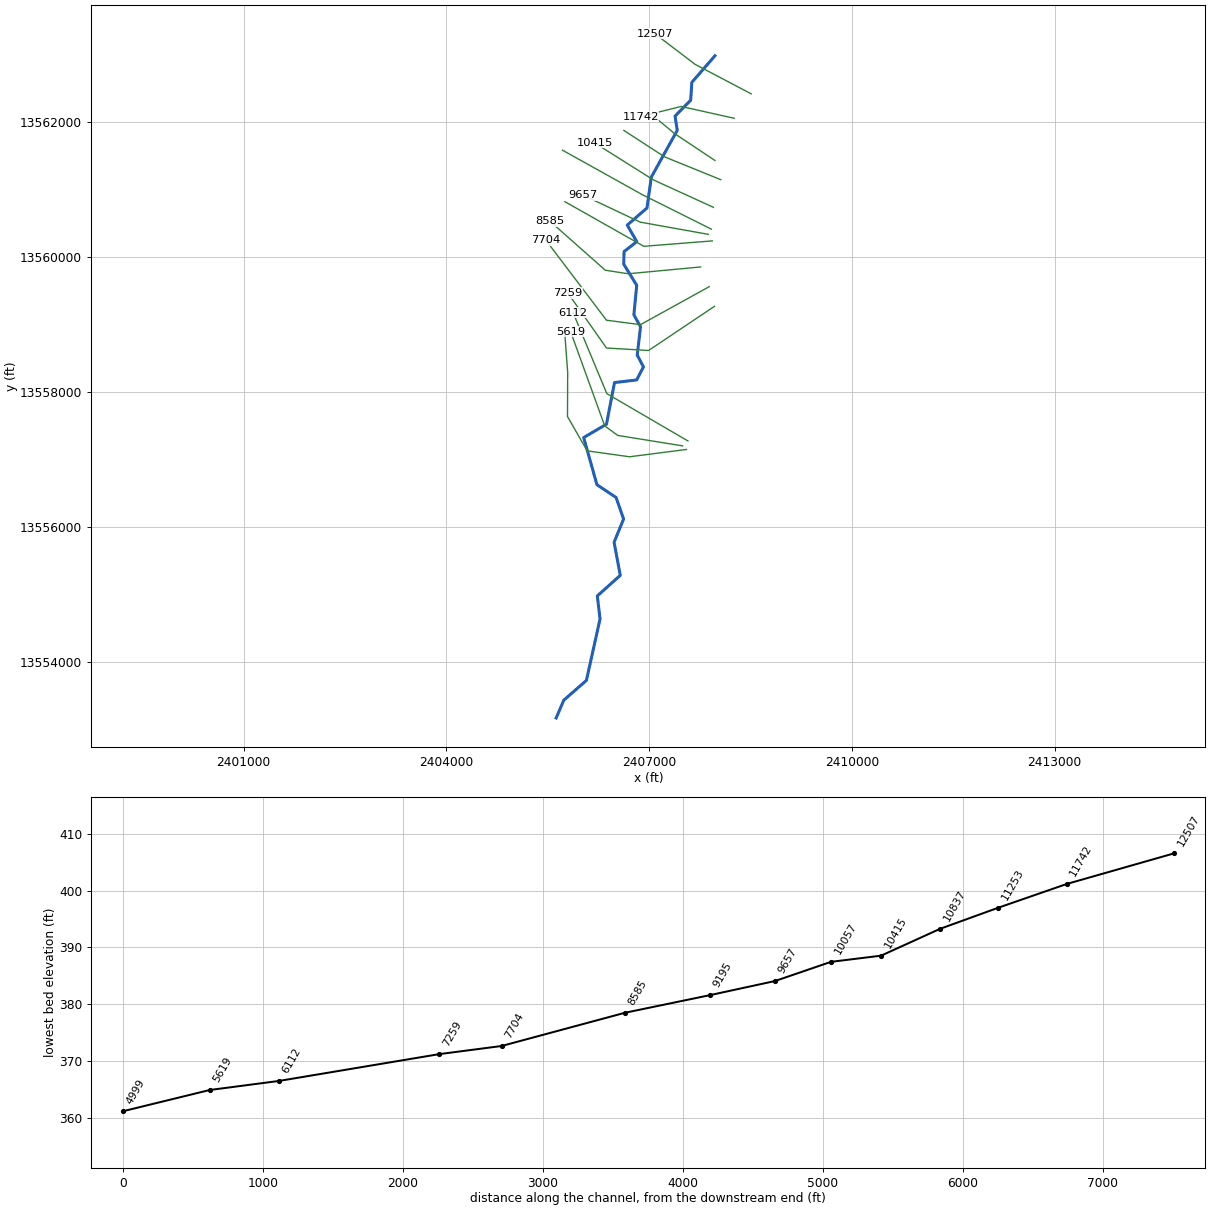
--- TRIB 5 TO THOMAS CREEK.prj (project) ---

Proj Title=TRIB 5 TO THOMAS CREEK Base Level Engineering
Current Plan=p01
Default Exp/Contr=0.3,0.1
English Units
Geom File=g01
Flow File=f01
Plan File=p01
BEGIN DESCRIPTION:
TRIB 5 TO THOMAS CREEK
END DESCRIPTION:

--- TRIB 5 TO THOMAS CREEK.p01 (plan) ---

Plan Title=Multiple Run
Short Identifier=Multiple
Geom File=g01
Flow File=f01
Subcritical Flow
K Sum by GR= 0
Std Step Tol= 0.01
Critical Tol= 0.01
Num of Std Step Trials= 20
Max Error Tol= 0.3
Flow Tol Ratio= 0.001
Split Flow NTrial= 30
Split Flow Tol= 0.02
Split Flow Ratio= 0.02
Log Output Level= 0
Friction Slope Method= 1
Unsteady Friction Slope Method= 2
Unsteady Bridges Friction Slope Method= 1
Parabolic Critical Depth
Global Vel Dist=  1 , 1 , 1
Global Log Level= 0
CheckData=True
Encroach Param= -1, 0, 0, 0
BEGIN DESCRIPTION:
Multiple Run
END DESCRIPTION:

--- TRIB 5 TO THOMAS CREEK.f01 (steady flow) ---

Flow Title=Multiple
Number of Profiles=7
Profile Names=10-year,25-year,50-year,1pct_min,100-year,1pct_plu,500-year
River Rch & RM= TRIB 5 TO THOMAS,Reach-1,12507
     462     743     997     650    1297    2587    2170
River Rch & RM= TRIB 5 TO THOMAS,Reach-1,11253
     642    1048    1420     932    1859    3709    3158
Boundary for River Rch & Prof#=TRIB 5 TO THOMAS,Reach-1,1
Up Type=0
Dn Type=3
Dn Slope=0.005
Boundary for River Rch & Prof#=TRIB 5 TO THOMAS,Reach-1,2
Up Type=0
Dn Type=3
Dn Slope=0.005
Boundary for River Rch & Prof#=TRIB 5 TO THOMAS,Reach-1,3
Up Type=0
Dn Type=3
Dn Slope=0.005
Boundary for River Rch & Prof#=TRIB 5 TO THOMAS,Reach-1,4
Up Type=0
Dn Type=3
Dn Slope=0.005
Boundary for River Rch & Prof#=TRIB 5 TO THOMAS,Reach-1,5
Up Type=0
Dn Type=3
Dn Slope=0.005
Boundary for River Rch & Prof#=TRIB 5 TO THOMAS,Reach-1,6
Up Type=0
Dn Type=3
Dn Slope=0.005
Boundary for River Rch & Prof#=TRIB 5 TO THOMAS,Reach-1,7
Up Type=0
Dn Type=3
Dn Slope=0.005

--- TRIB 5 TO THOMAS CREEK.g01 (geometry) ---

Geom Title=Existing Conditions

River Reach=TRIB 5 TO THOMAS,Reach-1
Reach XY= 30
      2407975.00     13562975.00      2407632.74     13562581.45
      2407615.97     13562317.99      2407384.58     13562081.55
      2407417.25     13561871.36      2407032.83     13561178.39
      2406969.48     13560722.57      2406676.88     13560469.29
      2406818.02     13560224.79      2406630.11     13560077.30
      2406625.15     13559890.42      2406817.21     13559578.42
      2406775.08     13559140.39      2406873.91     13558964.45
      2406824.63     13558545.20      2406916.98     13558371.69
      2406816.54     13558177.63      2406488.44     13558138.63
      2406369.60     13557522.29      2406032.29     13557325.09
      2406228.54     13556626.47      2406511.52     13556438.75
      2406623.02     13556119.11      2406482.34     13555775.10
      2406573.96     13555285.44      2406234.12     13554981.76
      2406274.49     13554640.21      2406072.67     13553730.96
      2405738.48     13553438.56      2405625.00     13553175.00

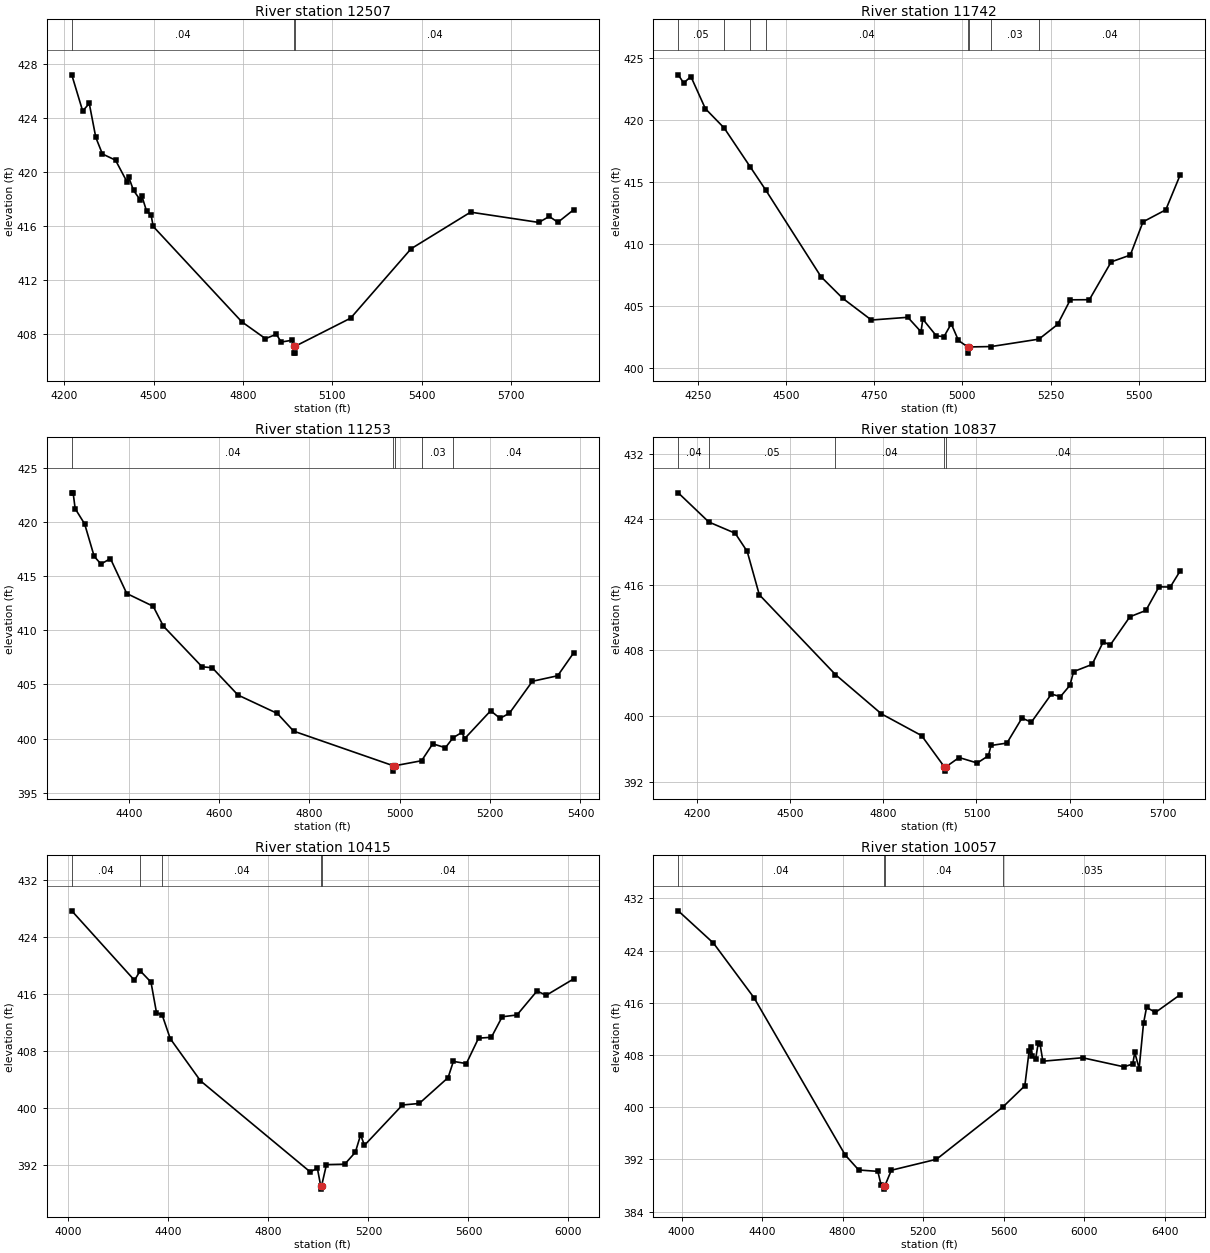
Type RM Length L Ch R = 1,12507,765,765,765
BEGIN DESCRIPTION:
LGII4667
END DESCRIPTION:
XS GIS Cut Line= 3
      2408510.32     13562411.83      2407682.22     13562847.67
      2407085.93     13563301.10
#Sta/Elev= 30
  4225.5  427.17  4262.1  424.49  4284.2  425.05  4306.2  422.53  4328.3  421.31
  4372.3  420.85  4410.7  419.25  4416.4  419.60  4432.8  418.61  4454.8  417.92
  4460.5  418.21  4476.9  417.05  4491.4  416.81  4498.9  415.94  4796.1  408.88
  4875.6  407.63  4911.9  407.96  4928.3  407.38  4966.0  407.52  4970.4  407.06
  4970.6  406.56  4974.1  406.56  4974.4  407.06  5161.3  409.15  5364.2  414.29
  5563.9  417.00  5792.6  416.24  5827.9  416.68  5857.0  416.25  5910.4  417.19
#Mann=3,-1,0
  4225.5    0.04       0  4970.4    0.04       0  4974.4    0.04       0
Bank Sta=4970.4,4974.4
Exp/Cntr=0.3,0.1

Type RM Length L Ch R = 1,11742,489,489,489
BEGIN DESCRIPTION:
TRIB 5_1 TO THOMAS CREEK 9.0
END DESCRIPTION:
XS GIS Cut Line= 3
      2408260.01     13562049.80      2407475.00     13562225.00
      2406874.99     13562075.00
#Sta/Elev= 30
  4194.8  423.63  4210.2  422.97  4230.7  423.49  4271.7  420.90  4325.0  419.34
  4399.4  416.18  4442.4  414.35  4599.5  407.34  4661.0  405.60  4742.2  403.85
  4845.4  404.07  4882.8  402.90  4887.9  403.92  4926.3  402.57  4947.9  402.51
  4968.4  403.55  4988.9  402.20  5015.2  401.68  5015.4  401.18  5019.2  401.68
  5081.6  401.71  5217.0  402.31  5269.7  403.49  5305.8  405.48  5359.9  405.49
  5421.7  408.54  5475.9  409.09  5511.9  411.77  5576.4  412.74  5617.6  415.58
#Mann=8,-1,0
  4194.8    0.05       0  4325.0    0.04       0  4399.4    0.05       0
  4442.4    0.04       0  5015.2    0.04       0  5019.2    0.04       0
  5081.6    0.03       0  5217.0    0.04       0
Bank Sta=5015.2,5019.2
Exp/Cntr=0.3,0.1

Type RM Length L Ch R = 1,11253,416,416,416
BEGIN DESCRIPTION:
TRIB 5_1 TO THOMAS CREEK 8.0
END DESCRIPTION:
XS GIS Cut Line= 3
      2407974.98     13561425.01      2407375.00     13561825.00
      2407075.00     13562075.00
#Sta/Elev= 30
  4273.7  422.68  4276.7  422.68  4281.2  421.22  4302.2  419.81  4323.3  416.82
  4338.3  416.11  4359.3  416.61  4395.4  413.39  4454.0  412.21  4476.5  410.38
  4562.1  406.63  4584.7  406.54  4641.7  404.02  4728.9  402.32  4764.9  400.69
  4985.3  397.50  4985.5  397.00  4989.3  397.50  5048.2  397.96  5072.9  399.52
  5100.9  399.16  5117.9  400.08  5137.3  400.57  5143.8  400.01  5201.1  402.57
  5221.9  401.87  5242.8  402.35  5293.5  405.29  5349.5  405.80  5385.3  407.94
#Mann=5,-1,0
  4273.7    0.04       0  4985.3    0.04       0  4989.3    0.04       0
  5048.2    0.03       0  5117.9    0.04       0
Bank Sta=4985.3,4989.3
Exp/Cntr=0.3,0.1

Type RM Length L Ch R = 1,10837,422,422,422
BEGIN DESCRIPTION:
Mapping XS 1307e5f3
END DESCRIPTION:
XS GIS Cut Line= 3
      2408060.62     13561141.47      2407230.79     13561478.26
      2406627.09     13561870.32
#Sta/Elev= 30
  4140.4  427.23  4238.8  423.67  4323.6  422.30  4362.3  420.08  4401.2  414.80
  4646.2  405.06  4794.0  400.27  4923.5  397.61  4997.0  393.78  4997.3  393.28
  5001.0  393.78  5044.0  394.94  5102.5  394.27  5138.3  395.16  5146.8  396.41
  5197.9  396.70  5246.3  399.75  5276.6  399.25  5341.0  402.68  5370.2  402.37
  5400.5  403.74  5412.5  405.42  5472.1  406.30  5507.9  409.05  5530.3  408.66
  5593.6  412.11  5645.0  412.88  5687.2  415.76  5723.5  415.74  5755.8  417.73
#Mann=5,-1,0
  4140.4    0.04       0  4238.8    0.05       0  4646.2    0.04       0
  4997.0    0.04       0  5001.0    0.04       0
Bank Sta=4997,5001
Exp/Cntr=0.3,0.1

Type RM Length L Ch R = 1,10415,358,358,358
BEGIN DESCRIPTION:
Mapping XS 109d538d
END DESCRIPTION:
XS GIS Cut Line= 3
      2407953.04     13560731.72      2407064.12     13561137.98
      2406192.58     13561686.61
#Sta/Elev= 30
  4014.2  427.61  4264.9  417.86  4287.7  419.19  4330.9  417.60  4352.9  413.32
  4375.7  412.98  4407.9  409.67  4528.8  403.75  4967.7  390.96  4995.9  391.50
  5009.2  389.05  5009.4  388.55  5013.2  389.05  5032.4  391.99  5105.4  392.05
  5147.8  393.72  5169.0  396.17  5184.3  394.70  5336.2  400.36  5403.2  400.57
  5518.6  404.20  5539.8  406.48  5591.6  406.17  5640.4  409.74  5691.7  409.86
  5734.9  412.74  5794.0  412.99  5874.2  416.36  5910.7  415.75  6021.4  418.07
#Mann=5,-1,0
  4014.2    0.04       0  4287.7    0.05       0  4375.7    0.04       0
  5009.2    0.04       0  5013.2    0.04       0
Bank Sta=5009.2,5013.2
Exp/Cntr=0.3,0.1

Type RM Length L Ch R = 1,10057,400,400,400
BEGIN DESCRIPTION:
Mapping XS 0db16526
END DESCRIPTION:
XS GIS Cut Line= 3
      2407921.74     13560408.83      2406900.93     13560919.23
      2405718.49     13561578.07
#Sta/Elev= 30
  3983.5  430.08  4158.7  425.13  4360.0  416.77  4813.1  392.69  4880.2  390.39
  4975.2  390.18  4992.0  388.05  5006.4  387.96  5006.7  387.46  5010.4  387.96
  5042.3  390.35  5266.7  392.03  5597.0  400.05  5705.7  403.28  5727.4  408.68
  5737.7  409.24  5743.4  407.82  5759.4  407.41  5772.6  409.86  5781.1  409.73
  5795.5  407.05  5992.6  407.58  6198.3  406.19  6242.0  406.62  6252.0  408.39
  6273.8  405.93  6295.5  412.83  6310.7  415.30  6354.9  414.52  6478.4  417.25
#Mann=4,-1,0
  3983.5    0.04       0  5006.4    0.04       0  5010.4    0.04       0
  5597.0   0.035       0
Bank Sta=5006.4,5010.4
Exp/Cntr=0.3,0.1

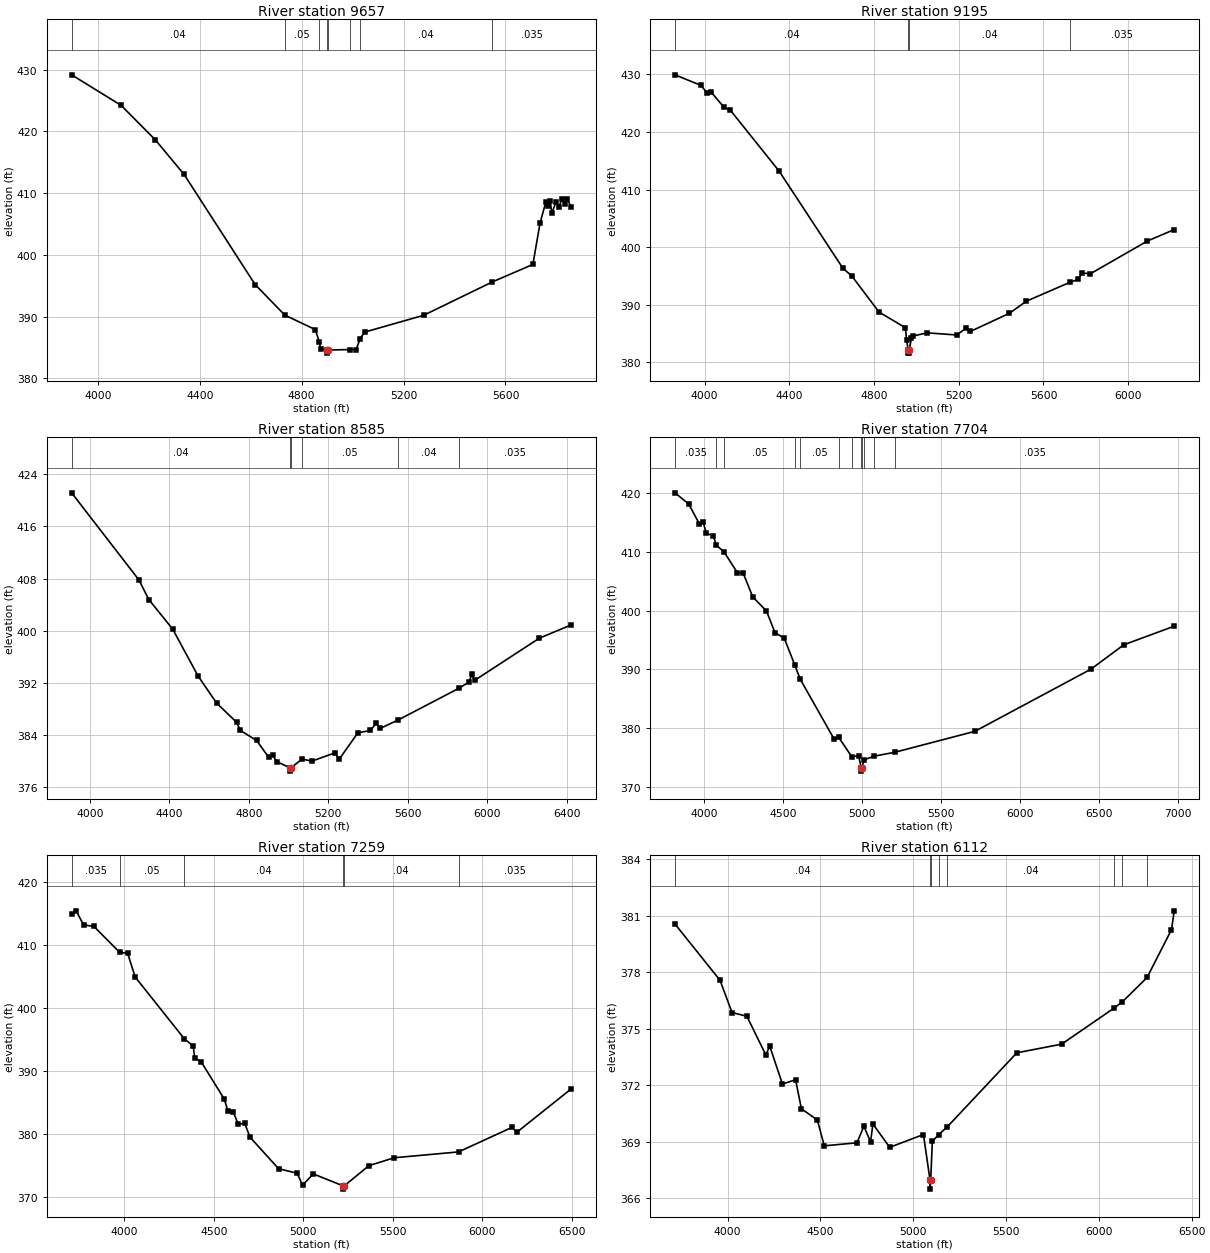
Type RM Length L Ch R = 1,9657,462,462,462
BEGIN DESCRIPTION:
Mapping XS c6b4af63
END DESCRIPTION:
XS GIS Cut Line= 3
      2407876.63     13560332.43      2406869.68     13560512.98
      2406022.47     13560912.28
#Sta/Elev= 30
  3897.1  429.15  4091.8  424.19  4226.1  418.60  4338.7  413.01  4617.4  395.18
  4733.8  390.24  4853.7  387.89  4869.1  385.88  4874.1  384.79  4899.3  384.58
  4899.6  384.08  4903.3  384.58  4990.8  384.66  5013.7  384.65  5029.9  386.44
  5046.9  387.48  5279.0  390.21  5548.4  395.61  5707.6  398.44  5735.9  405.19
  5758.7  408.58  5765.5  407.92  5776.0  408.76  5781.5  406.70  5798.6  408.59
  5809.8  407.73  5820.7  408.97  5832.6  408.24  5842.8  409.05  5856.7  407.80
#Mann=8,-1,0
  3897.1    0.04       0  4733.8    0.05       0  4869.1    0.04       0
  4899.3    0.05       0  4903.3    0.04       0  4990.8    0.05       0
  5029.9    0.04       0  5548.4   0.035       0
Bank Sta=4899.3,4903.3
Exp/Cntr=0.3,0.1

Type RM Length L Ch R = 1,9195,610,610,610
BEGIN DESCRIPTION:
Mapping XS f2d1e46a
END DESCRIPTION:
XS GIS Cut Line= 3
      2407935.69     13560235.21      2406921.76     13560155.35
      2405755.14     13560815.04
#Sta/Elev= 30
  3860.1  429.92  3981.2  428.11  4011.3  426.83  4031.3  426.90  4091.5  424.29
  4121.6  423.78  4352.3  413.18  4653.2  396.33  4694.5  395.03  4823.8  388.73
  4947.8  386.03  4953.9  383.84  4961.7  382.11  4962.0  381.61  4965.5  381.61
  4965.7  382.11  4976.8  384.21  4985.4  384.59  5050.3  385.13  5190.4  384.76
  5233.7  385.91  5255.3  385.38  5438.6  388.51  5519.5  390.63  5723.6  393.88
  5762.0  394.40  5783.6  395.53  5821.2  395.38  6091.2  401.08  6217.4  403.06
#Mann=4,-1,0
  3860.1    0.04       0  4961.7    0.04       0  4965.7    0.04       0
  5723.6   0.035       0
Bank Sta=4961.7,4965.7
Exp/Cntr=0.3,0.1

Type RM Length L Ch R = 1,8585,881,881,881
BEGIN DESCRIPTION:
Mapping XS 1da7ebb2
END DESCRIPTION:
XS GIS Cut Line= 4
      2407762.03     13559849.79      2406692.59     13559749.10
      2406352.32     13559801.18      2405532.87     13560526.88
#Sta/Elev= 30
  3907.9  421.14  4246.4  407.80  4296.6  404.78  4417.2  400.23  4544.2  393.07
  4638.1  388.90  4738.6  385.97  4756.4  384.74  4839.0  383.19  4899.3  380.63
  4919.4  380.99  4939.5  379.96  5008.0  378.99  5008.2  378.49  5012.0  378.99
  5067.6  380.33  5118.2  380.03  5232.5  381.29  5255.1  380.33  5348.7  384.36
  5412.3  384.72  5440.7  385.83  5461.6  385.04  5552.9  386.35  5860.0  391.23
  5908.3  392.15  5922.5  393.32  5936.7  392.40  6262.1  398.86  6420.9  400.88
#Mann=6,-1,0
  3907.9    0.04       0  5008.0    0.04       0  5012.0    0.04       0
  5067.6    0.05       0  5552.9    0.04       0  5860.0   0.035       0
Bank Sta=5008,5012
Exp/Cntr=0.3,0.1

Type RM Length L Ch R = 1,7704,445,445,445
BEGIN DESCRIPTION:
Mapping XS a404daba
END DESCRIPTION:
XS GIS Cut Line= 4
      2407890.53     13559558.14      2406873.15     13558995.62
      2406369.68     13559061.60      2405470.38     13560249.09
#Sta/Elev= 30
  3815.8  420.08  3902.1  418.19  3970.7  414.77  3992.9  415.18  4014.6  413.15
  4058.2  412.80  4076.8  411.18  4125.9  410.02  4210.6  406.48  4248.3  406.34
  4307.9  402.35  4394.9  399.93  4448.8  396.26  4507.7  395.28  4574.8  390.69
  4608.1  388.33  4823.3  378.09  4851.9  378.40  4935.1  375.08  4978.3  375.29
  4994.6  373.14  4994.9  372.64  4998.6  373.14  5012.0  374.57  5078.5  375.20
  5208.1  375.86  5713.7  379.42  6448.1  390.01  6656.2  394.17  6975.7  397.35
#Mann=12,-1,0
  3815.8   0.035       0  4076.8    0.04       0  4125.9    0.05       0
  4574.8    0.04       0  4608.1    0.05       0  4851.9    0.12       0
  4935.1    0.05       0  4994.6    0.05       0  4998.6    0.05       0
  5012.0    0.12       0  5078.5    0.04       0  5208.1   0.035       0
Bank Sta=4994.6,4998.6
Exp/Cntr=0.3,0.1

Type RM Length L Ch R = 1,7259,1147,1147,1147
BEGIN DESCRIPTION:
TRIB 5_1 TO THOMAS CREEK 1.0
END DESCRIPTION:
XS GIS Cut Line= 4
      2407966.91     13559266.46      2406993.33     13558613.64
      2406369.78     13558649.97      2405798.91     13559463.32
#Sta/Elev= 30
  3705.0  414.98  3730.0  415.49  3772.0  413.24  3829.0  413.02  3973.7  408.88
  4018.1  408.73  4060.1  404.96  4335.4  395.11  4384.3  393.98  4393.2  392.05
  4429.3  391.46  4558.3  385.53  4579.3  383.60  4609.3  383.41  4636.4  381.55
  4672.4  381.66  4702.4  379.47  4861.4  374.46  4965.7  373.74  4995.7  371.84
  5055.8  373.63  5224.1  371.71  5224.4  371.21  5228.1  371.71  5366.3  374.94
  5507.9  376.20  5867.4  377.13  6168.3  381.06  6191.8  380.22  6495.5  387.12
#Mann=6,-1,0
  3705.0   0.035       0  3973.7    0.05       0  4335.4    0.04       0
  5224.1    0.04       0  5228.1    0.04       0  5867.4   0.035       0
Bank Sta=5224.1,5228.1
Exp/Cntr=0.3,0.1

Type RM Length L Ch R = 1,6112,493,493,493
BEGIN DESCRIPTION:
TRIB 5 TO THOMAS CREEK 1.0
END DESCRIPTION:
XS GIS Cut Line= 3
      2407575.01     13557274.99      2406375.00     13557975.00
      2405874.98     13559175.04
#Sta/Elev= 30
  3716.8  380.56  3959.5  377.57  4024.0  375.86  4104.2  375.66  4205.9  373.61
  4227.4  374.07  4295.7  372.06  4366.4  372.29  4397.8  370.75  4483.8  370.15
  4521.0  368.78  4697.1  368.94  4734.4  369.82  4770.3  368.99  4783.1  369.94
  4873.3  368.70  5055.2  369.38  5090.4  366.98  5090.7  366.48  5094.4  366.98
  5103.2  369.02  5137.3  369.37  5183.9  369.79  5558.3  373.72  5799.9  374.18
  6081.4  376.09  6127.2  376.43  6259.8  377.72  6391.4  380.26  6406.1  381.26
#Mann=8,-1,0
  3716.8    0.04       0  5090.4    0.04       0  5094.4    0.04       0
  5137.3    0.03       0  5183.9    0.04       0  6081.4    0.05       0
  6127.2    0.04       0  6259.8   0.035       0
Bank Sta=5090.4,5094.4
Exp/Cntr=0.3,0.1

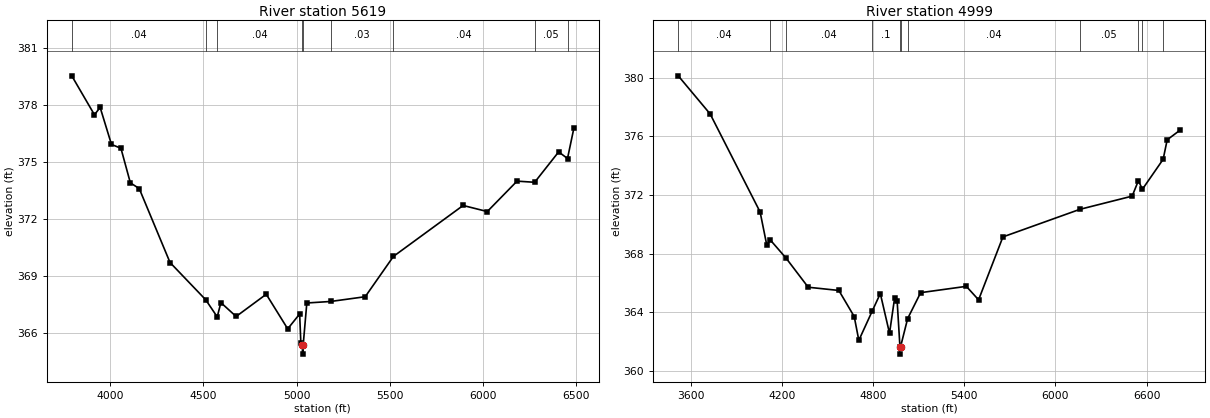
Type RM Length L Ch R = 1,5619,620,620,620
BEGIN DESCRIPTION:
Mapping XS cb0e7f40
END DESCRIPTION:
XS GIS Cut Line= 4
      2407495.20     13557202.17      2406536.44     13557356.57
      2406343.73     13557497.19      2405839.08     13558891.50
#Sta/Elev= 30
  3793.7  379.53  3915.4  377.48  3945.8  377.87  4006.6  375.92  4057.3  375.72
  4107.9  373.90  4155.5  373.60  4320.6  369.71  4511.9  367.75  4573.8  366.85
  4593.4  367.60  4675.1  366.87  4836.6  368.04  4951.7  366.22  5015.7  367.00
  5022.3  365.46  5030.9  365.39  5031.2  364.89  5034.9  365.39  5054.2  367.58
  5181.9  367.66  5367.4  367.91  5518.6  370.03  5892.4  372.71  6022.0  372.39
  6181.5  373.99  6276.1  373.93  6404.8  375.53  6452.2  375.18  6486.2  376.77
#Mann=9,-1,0
  3793.7    0.04       0  4511.9    0.05       0  4573.8    0.04       0
  5030.9    0.04       0  5034.9    0.04       0  5181.9    0.03       0
  5518.6    0.04       0  6276.1    0.05       0  6452.2    0.04       0
Bank Sta=5030.9,5034.9
Exp/Cntr=0.3,0.1

Type RM Length L Ch R = 1,4999,0,0,0
BEGIN DESCRIPTION:
4836
END DESCRIPTION:
XS GIS Cut Line= 6
      2407553.37     13557149.00      2406711.32     13557040.49
      2406083.55     13557128.33      2405792.74     13557636.73
      2405795.52     13558290.49      2405752.20     13558871.01
#Sta/Elev= 30
  3517.1  380.12  3727.2  377.52  4055.9  370.84  4100.3  368.56  4122.3  368.94
  4225.6  367.71  4372.5  365.71  4574.2  365.49  4675.4  363.71  4705.7  362.09
  4794.5  364.10  4847.1  365.28  4907.7  362.57  4941.4  364.99  4958.1  364.74
  4976.3  361.65  4976.6  361.15  4980.3  361.65  5026.9  363.57  5112.5  365.34
  5413.3  365.77  5493.9  364.85  5654.0  369.14  6160.7  371.02  6504.7  371.92
  6545.6  372.97  6572.2  372.39  6708.6  374.43  6735.3  375.76  6821.6  376.43
#Mann=11,-1,0
  3517.1    0.04       0  4122.3    0.05       0  4225.6    0.04       0
  4794.5     0.1       0  4976.3    0.05       0  4980.3     0.1       0
  5026.9    0.04       0  6160.7    0.05       0  6545.6     0.1       0
  6572.2    0.05       0  6708.6   0.035       0
Bank Sta=4976.3,4980.3
Exp/Cntr=0.3,0.1

Chan Stop Cuts=-1