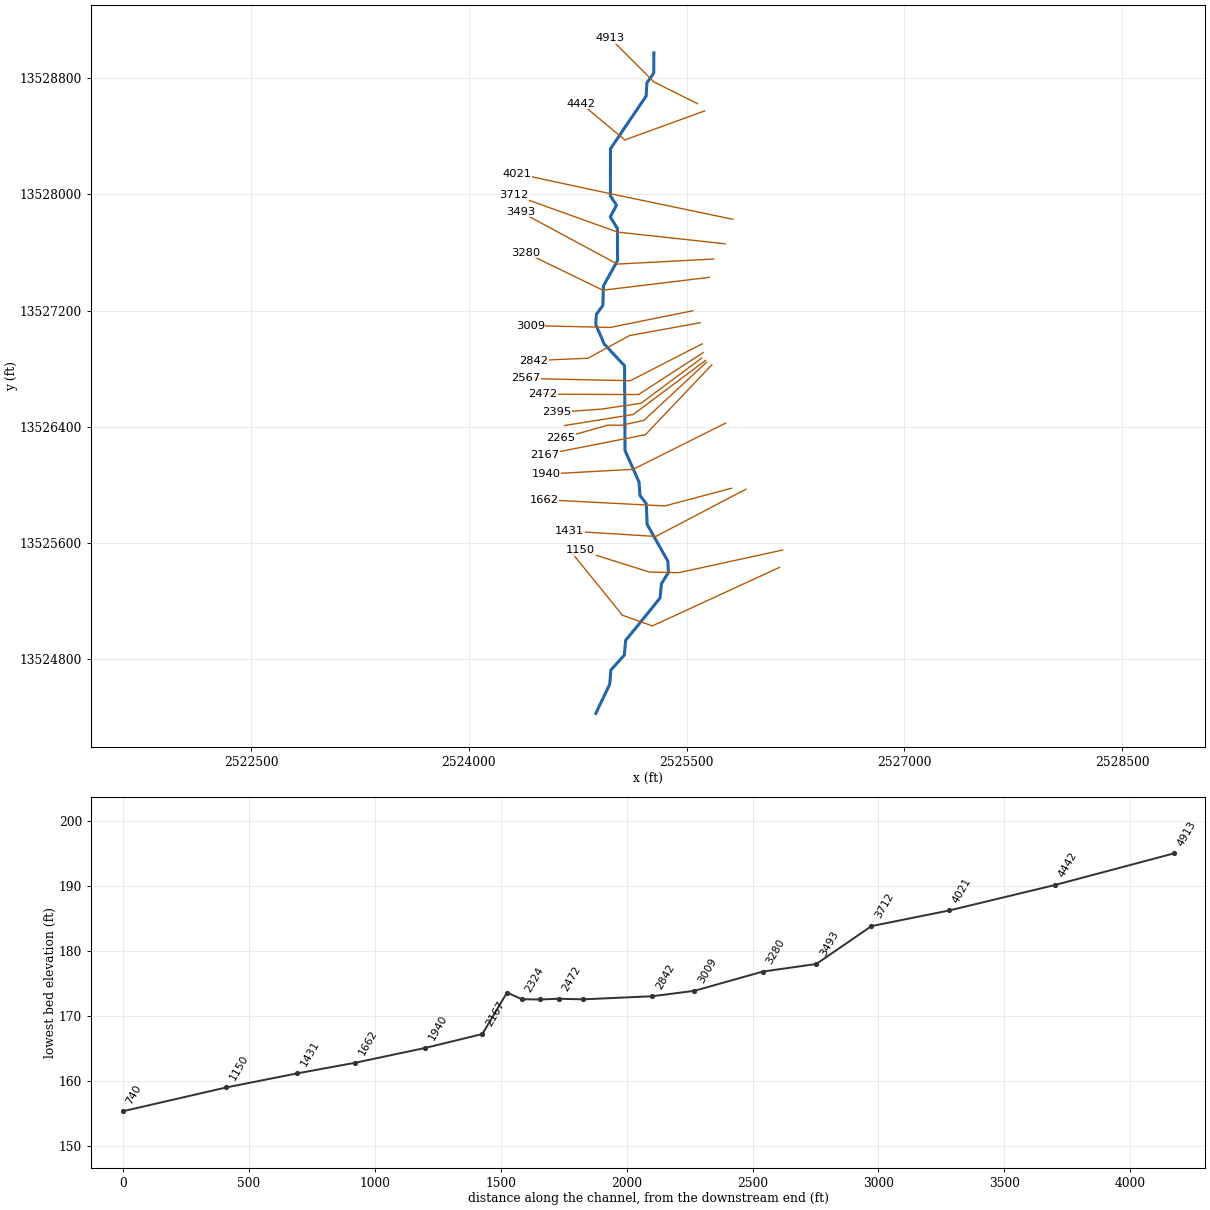
--- TRIB 5 TO TWELVEMILE CREEK.prj (project) ---

Proj Title=TRIB 5 TO TWELVEMILE CREEK Base Level Engineering
Current Plan=p01
Default Exp/Contr=0.3,0.1
English Units
Geom File=g01
Flow File=f01
Plan File=p01
Y Axis Title=Elevation
X Axis Title(PF)=Main Channel Distance
X Axis Title(XS)=Station
BEGIN DESCRIPTION:
TRIB 5 TO TWELVEMILE CREEK
END DESCRIPTION:
DSS Export Rating Curves= 0
DSS Export Rating Curve Sorted= 0
DSS Export Volume Flow Curves= 0
DXF OffsetX= 0
DXF OffsetY= 0
DXF ScaleX= 1
DXF ScaleY= 10

--- TRIB 5 TO TWELVEMILE CREEK.p01 (plan) ---

Plan Title=Multiple Run
Short Identifier=Multiple
Geom File=g01
Flow File=f01
Subcritical Flow
K Sum by GR= 0
Std Step Tol= 0.01
Critical Tol= 0.01
Num of Std Step Trials= 20
Max Error Tol= 0.3
Flow Tol Ratio= 0.001
Split Flow NTrial= 30
Split Flow Tol= 0.02
Split Flow Ratio= 0.02
Log Output Level= 0
Friction Slope Method= 1
Unsteady Friction Slope Method= 2
Unsteady Bridges Friction Slope Method= 1
Parabolic Critical Depth
Global Vel Dist=  1 , 1 , 1
Global Log Level= 0
CheckData=True
Encroach Param= -1, 0, 0, 0
BEGIN DESCRIPTION:
Multiple Run
END DESCRIPTION:

--- TRIB 5 TO TWELVEMILE CREEK.f01 (steady flow) ---

Flow Title=Multiple
Number of Profiles=7
Profile Names=10-year,25-year,50-year,1pct_min,100-year,1pct_plu,500-year
River Rch & RM= TRIB 5 TO TWELVE,Reach-1,4913
     564     903    1208     784    1564    3120    2588
Boundary for River Rch & Prof#=TRIB 5 TO TWELVE,Reach-1,1
Up Type=0
Dn Type=3
Dn Slope=0.005
Boundary for River Rch & Prof#=TRIB 5 TO TWELVE,Reach-1,2
Up Type=0
Dn Type=3
Dn Slope=0.005
Boundary for River Rch & Prof#=TRIB 5 TO TWELVE,Reach-1,3
Up Type=0
Dn Type=3
Dn Slope=0.005
Boundary for River Rch & Prof#=TRIB 5 TO TWELVE,Reach-1,4
Up Type=0
Dn Type=3
Dn Slope=0.005
Boundary for River Rch & Prof#=TRIB 5 TO TWELVE,Reach-1,5
Up Type=0
Dn Type=3
Dn Slope=0.005
Boundary for River Rch & Prof#=TRIB 5 TO TWELVE,Reach-1,6
Up Type=0
Dn Type=3
Dn Slope=0.005
Boundary for River Rch & Prof#=TRIB 5 TO TWELVE,Reach-1,7
Up Type=0
Dn Type=3
Dn Slope=0.005

--- TRIB 5 TO TWELVEMILE CREEK.g01 (geometry) ---

Geom Title=Existing Conditions
Program Version=4.10

River Reach=TRIB 5 TO TWELVE,Reach-1
Reach XY= 30
        2525275.       13528975.      2525273.83     13528835.48
      2525227.35     13528769.03      2525221.18     13528676.58
      2524976.05     13528314.56      2524975.66     13527990.16
      2525017.41     13527924.99      2524974.79     13527845.21
      2525023.76      13527764.5      2525024.94     13527545.03
      2524927.25     13527369.07      2524923.77     13527235.51
       2524878.7      13527173.4       2524874.4     13527104.95
      2524933.14     13526968.94      2525072.94     13526819.15
      2525076.22      13526235.5      2525172.65     13526019.03
      2525178.86      13525926.6      2525222.73     13525869.06
      2525228.76     13525726.56      2525371.33     13525473.42
       2525375.1      13525395.1      2525327.36     13525319.02
      2525317.14     13525218.83      2525080.54     13524927.42
      2525071.37      13524826.5      2524978.62      13524723.5
      2524971.17     13524626.59        2524875.       13524425.

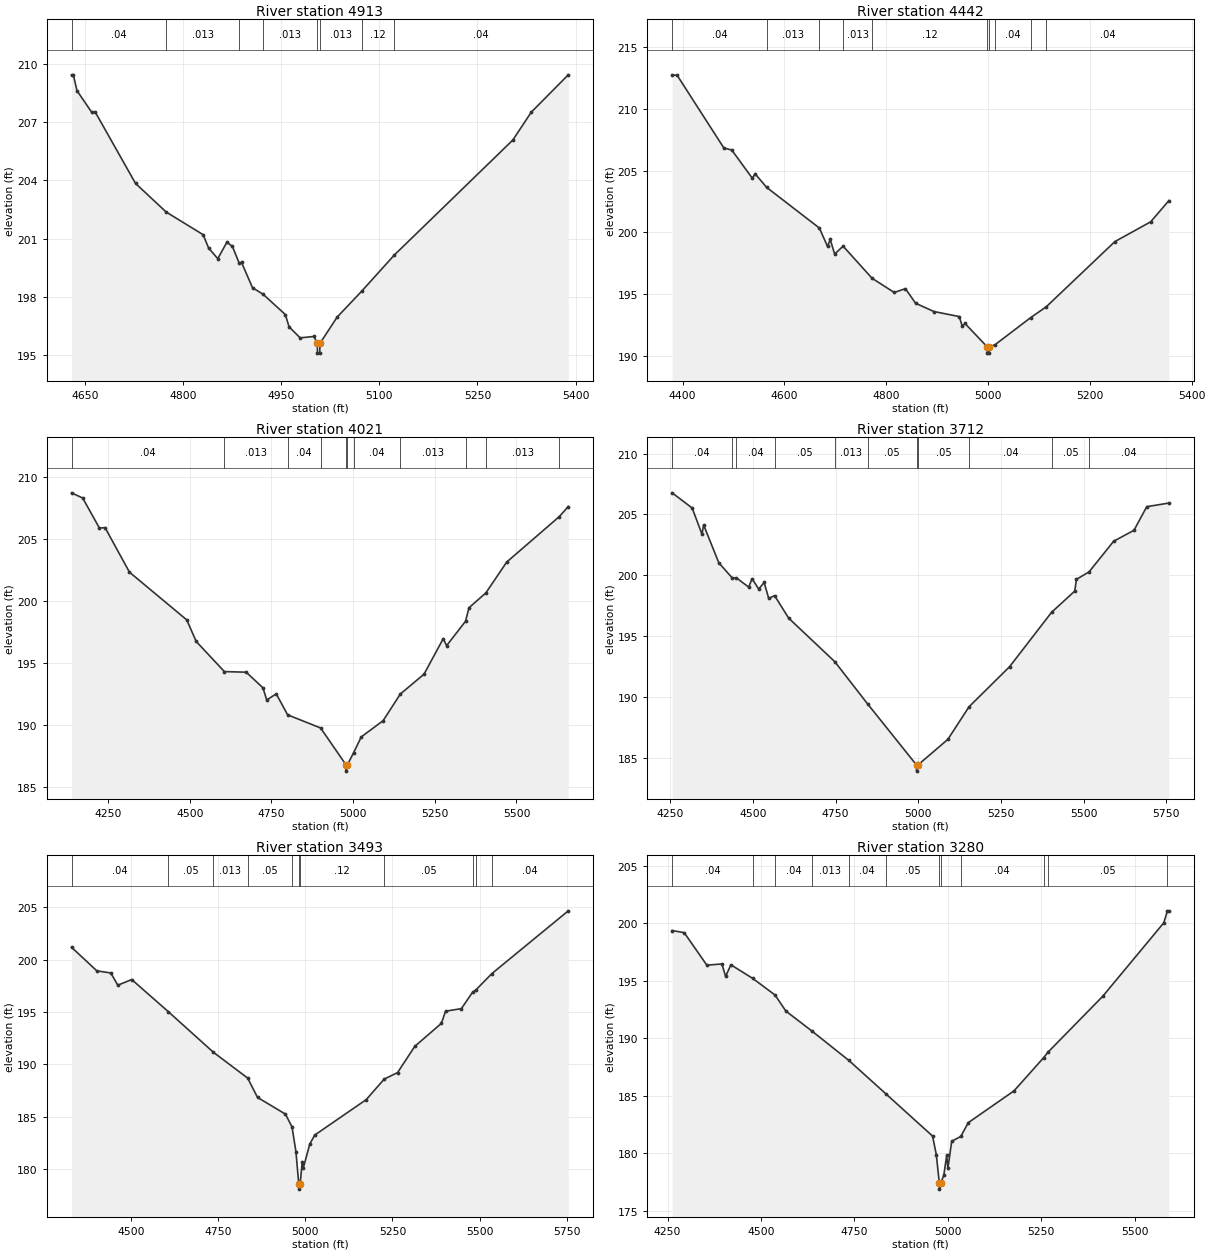
Type RM Length L Ch R = 1 ,4913    ,471,471,471
BEGIN DESCRIPTION:
TRIB 5 TO TWELVEMILE CREEK 10.0
END DESCRIPTION:
XS GIS Cut Line= 3
      2525575.04     13528624.98        2525275.       13528775.
      2524975.01     13529074.99
#Sta/Elev= 30
  4629.2  209.46    4632  209.46  4637.6  208.64    4660  207.53  4665.6  207.53
  4727.1  203.85    4774  202.37  4830.5   201.2  4838.9  200.51  4852.9  199.96
  4866.8  200.81  4875.2   200.6  4885.5  199.74  4889.2  199.77    4906  198.46
  4922.3  198.12  4956.3  197.07  4961.9  196.44  4978.8  195.87    5000  195.94
  5005.1  195.58  5005.3  195.08  5008.8  195.08  5009.1  195.58  5035.4  196.94
  5072.7  198.27  5122.9  200.15  5304.1  206.09  5332.3  207.53  5388.9  209.46
#Mann= 8 ,-1 , 0
  4629.2     .04       0    4774    .013       0  4885.5     .12       0
  4922.3    .013       0  5005.1     .03       0  5009.1    .013       0
  5072.7     .12       0  5122.9     .04       0
Bank Sta=5005.1,5009.1
XS Rating Curve= 0 ,0
Exp/Cntr=0.3,0.1

Type RM Length L Ch R = 1 ,4442    ,421,421,421
BEGIN DESCRIPTION:
TRIB 5 TO TWELVEMILE CREEK 9.0
END DESCRIPTION:
XS GIS Cut Line= 3
      2525624.95     13528574.98        2525075.       13528375.
        2524775.       13528625.
#Sta/Elev= 30
  4379.6  212.76  4389.5  212.72  4481.3  206.83  4496.6  206.68  4537.2  204.38
  4542.5  204.75  4565.2  203.65  4668.7  200.36  4684.8  198.87  4690.1  199.43
  4698.8  198.25  4715.4  198.89  4772.3  196.29  4815.8  195.14  4837.8  195.45
  4857.7  194.27  4893.6   193.6  4943.5  193.19  4949.5   192.4  4954.8  192.63
  4998.6  190.73  4998.8  190.23  5002.3  190.23  5002.6  190.73  5013.8  190.91
  5083.6   193.1  5114.4  193.98  5249.2  199.26  5319.5  200.86  5355.3  202.58
#Mann= 10 ,-1 , 0
  4379.6     .04       0  4565.2    .013       0  4668.7     .12       0
  4715.4    .013       0  4772.3     .12       0  4998.6     .05       0
  5002.6     .12       0  5013.8     .04       0  5083.6     .12       0
  5114.4     .04       0
Bank Sta=4998.6,5002.6
XS Rating Curve= 0 ,0
Exp/Cntr=0.3,0.1

Type RM Length L Ch R = 1 ,4021    ,309,309,309
BEGIN DESCRIPTION:
Mapping XS ee77a681
END DESCRIPTION:
XS GIS Cut Line= 3
      2525818.61     13527828.56      2524974.72     13528004.82
       2524330.9     13528143.58
#Sta/Elev= 30
  4137.9  208.75  4172.2  208.33  4223.3  205.91  4240.7  205.94  4315.3  202.35
  4490.7   198.5  4519.6  196.76  4605.9  194.33  4672.8  194.28  4723.9  193.02
  4735.5  192.04  4764.7  192.53  4799.5  190.84  4900.5  189.78  4978.4   186.8
  4978.7   186.3  4982.4   186.8  5001.6  187.79  5024.9  189.06  5091.8  190.37
  5144.5  192.52    5217  194.12  5275.9  196.99  5286.1  196.42  5344.1  198.39
  5354.7  199.48  5406.4  200.68  5470.3  203.17  5630.6  206.82  5658.6  207.64
#Mann= 11 ,-1 , 0
  4137.9     .04       0  4605.9    .013       0  4799.5     .04       0
  4900.5     .12       0  4978.4     .05       0  4982.4     .12       0
  5001.6     .04       0  5144.5    .013       0  5344.1     .04       0
  5406.4    .013       0  5630.6     .04       0
Bank Sta=4978.4,4982.4
XS Rating Curve= 0 ,0
Exp/Cntr=0.3,0.1

Type RM Length L Ch R = 1 ,3712    ,219,219,219
BEGIN DESCRIPTION:
Mapping XS 42238206
END DESCRIPTION:
XS GIS Cut Line= 3
      2525765.27     13527659.77      2525025.42     13527740.18
      2524311.96     13527996.18
#Sta/Elev= 30
  4255.8  206.77  4316.4  205.52    4346  203.37    4351  204.13  4396.9  201.02
    4437  199.79    4450  199.78  4487.4  199.02  4497.5  199.71  4517.6  198.86
  4534.1   199.4  4547.8  198.09  4565.6  198.32  4608.1  196.47  4747.6  192.89
  4846.8  189.42  4994.9  184.39  4995.1  183.89  4998.9  184.39  5089.5   186.5
  5153.6  189.18  5276.7  192.49  5403.3  196.95  5473.2  198.69  5478.5  199.66
  5516.5  200.27  5590.9  202.79  5652.4  203.69    5691  205.63    5758  205.93
#Mann= 11 ,-1 , 0
  4255.8     .04       0    4437    .013       0    4450     .04       0
  4565.6     .05       0  4747.6    .013       0  4846.8     .05       0
  4994.9     .05       0  4998.9     .05       0  5153.6     .04       0
  5403.3     .05       0  5516.5     .04       0
Bank Sta=4994.9,4998.9
XS Rating Curve= 0 ,0
Exp/Cntr=0.3,0.1

Type RM Length L Ch R = 1 ,3493    ,213,213,213
BEGIN DESCRIPTION:
Mapping XS 3de8f995
END DESCRIPTION:
XS GIS Cut Line= 3
      2525687.48     13527554.69      2525023.46     13527519.97
      2524355.26      13527880.1
#Sta/Elev= 30
  4330.1  201.19  4402.7  198.93  4442.7  198.73  4462.8  197.56  4502.8   198.1
  4607.2  195.04  4736.7  191.15    4835  188.68  4863.3  186.83  4943.4  185.23
  4962.2  184.01  4973.5  181.63  4981.5  178.56  4981.7  178.06  4985.5  178.56
  4991.5  180.69  4994.7   180.1  5013.2  182.38  5027.4  183.23    5175  186.62
  5226.4  188.58  5264.7   189.2  5314.1  191.71  5390.4  193.91  5402.2  195.07
  5447.7  195.32    5480   196.9  5488.5  197.08  5535.1  198.67  5754.1  204.67
#Mann= 11 ,-1 , 0
  4330.1     .04       0  4607.2     .05       0  4736.7    .013       0
    4835     .05       0  4962.2     .12       0  4981.5     .05       0
  4985.5     .12       0  5226.4     .05       0    5480     .04       0
  5488.5     .05       0  5535.1     .04       0
Bank Sta=4981.5,4985.5
XS Rating Curve= 0 ,0
Exp/Cntr=0.3,0.1

Type RM Length L Ch R = 1 ,3280    ,271,271,271
BEGIN DESCRIPTION:
Mapping XS 61202c98
END DESCRIPTION:
XS GIS Cut Line= 3
      2525657.18     13527428.83      2524923.63     13527339.85
      2524391.96     13527598.09
#Sta/Elev= 30
  4262.1  199.37  4294.5  199.18    4355  196.36  4395.3  196.46  4405.3  195.38
  4419.4  196.39  4478.1   195.2  4537.7  193.76  4566.5  192.37  4636.4  190.63
  4735.1  188.08  4833.8  185.19  4959.4   181.5  4969.4  179.88  4977.5  177.39
  4977.8  176.89  4981.5  177.39  4989.6  178.14  4997.2  179.82  5000.4   178.7
  5010.6  181.05  5034.9  181.47  5055.1  182.67  5177.4  185.43  5256.6  188.31
  5268.6   188.8  5414.9  193.65  5578.4  200.04  5588.2  201.08  5592.1  201.08
#Mann= 12 ,-1 , 0
  4262.1     .04       0  4478.1     .05       0  4537.7     .04       0
  4636.4    .013       0  4735.1     .04       0  4833.8     .05       0
  4977.5     .05       0  4981.5     .05       0  5034.9     .04       0
  5256.6     .12       0  5268.6     .05       0  5588.2     .04       0
Bank Sta=4977.5,4981.5
XS Rating Curve= 0 ,0
Exp/Cntr=0.3,0.1

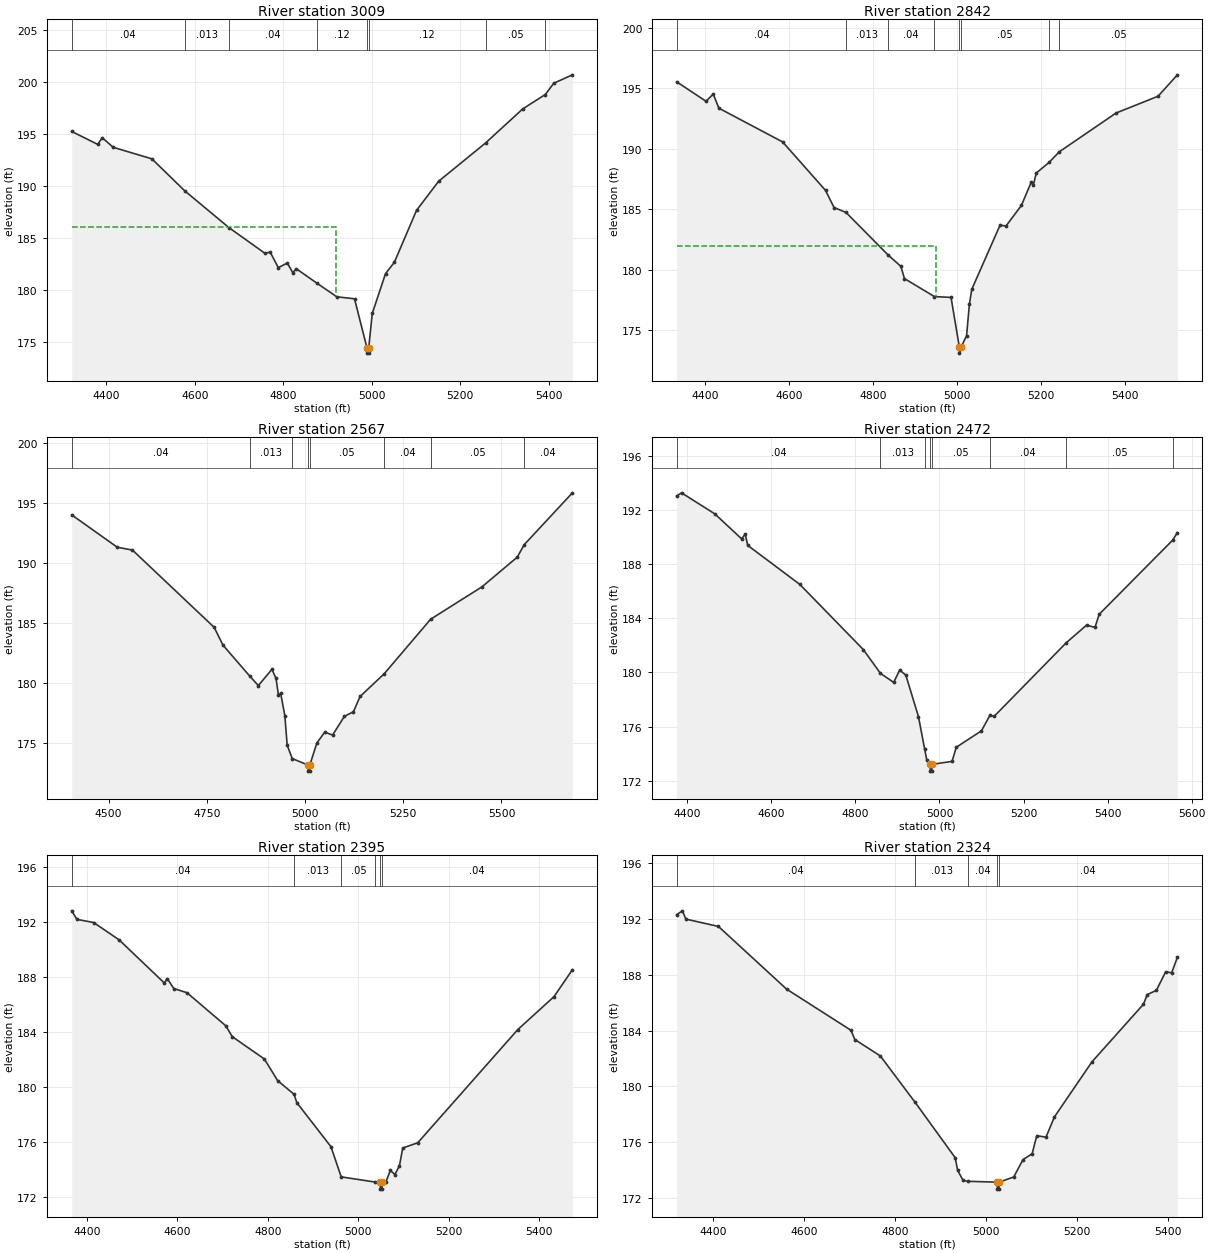
Type RM Length L Ch R = 1 ,3009    ,167,167,167
BEGIN DESCRIPTION:
Mapping XS 1e386e4e
END DESCRIPTION:
XS GIS Cut Line= 3
      2525542.62     13527198.41        2524974.     13527083.39
      2524422.79     13527096.41
#Sta/Elev= 30
  4321.9  195.22  4380.7  193.98  4390.9  194.62  4415.6   193.7  4503.1  192.59
  4577.3  189.52  4677.1  185.99  4758.2  183.53  4770.6  183.62  4788.8  182.14
  4809.2  182.58  4821.4  181.66  4829.6  182.03  4876.6  180.63    4921  179.34
    4961  179.15  4989.1  174.43  4989.3  173.93  4992.8  173.93  4993.1  174.43
  5001.1  177.74  5031.1  181.57  5051.1  182.66  5101.1  187.64  5151.1  190.44
    5257  194.11  5341.2  197.39  5392.1  198.77  5411.2  199.85  5453.4  200.66
#Mann= 8 ,-1 , 0
  4321.9     .04       0  4577.3    .013       0  4677.1     .04       0
  4876.6     .12       0  4989.1     .05       0  4993.1     .12       0
    5257     .05       0  5392.1     .04       0
#XS Ineff= 2 , 0
       0    4920     186               0
Permanent Ineff=
       F       F
Bank Sta=4989.1,4993.1
XS Rating Curve= 0 ,0
Exp/Cntr=0.3,0.1

Type RM Length L Ch R = 1 ,2842    ,275,275,275
BEGIN DESCRIPTION:
Mapping XS 5c2ee5e8
END DESCRIPTION:
XS GIS Cut Line= 4
      2525593.86     13527115.91      2525106.85     13527027.37
      2524820.39     13526871.12      2524449.01     13526855.53
#Sta/Elev= 30
    4332  195.55    4402  193.94  4419.1  194.54  4432.5  193.37  4584.3  190.58
  4686.6  186.57  4706.9  185.15  4735.5  184.74  4835.8  181.22  4866.1  180.28
  4874.7  179.27  4946.1  177.78  4985.7  177.71  5005.5   173.6  5005.8   173.1
  5009.5   173.6  5022.7  174.53  5029.4  177.14  5035.1  178.38  5102.5  183.69
  5116.7  183.62  5153.3  185.32  5176.8  187.25  5181.8  186.99  5188.7     188
  5219.5  188.89  5243.6  189.76  5378.9  192.97    5479  194.36    5525  196.13
#Mann= 8 ,-1 , 0
    4332     .04       0  4735.5    .013       0  4835.8     .04       0
  4946.1     .05       0  5005.5     .05       0  5009.5     .05       0
  5219.5     .04       0  5243.6     .05       0
#XS Ineff= 2 , 0
       0    4950     182               0
Permanent Ineff=
       F       F
Bank Sta=5005.5,5009.5
XS Rating Curve= 0 ,0
Exp/Cntr=0.3,0.1

Type RM Length L Ch R = 1 ,2567    ,95,95,95
BEGIN DESCRIPTION:
Mapping XS ce7b1f10
END DESCRIPTION:
XS GIS Cut Line= 3
      2525607.71     13526970.56      2525112.89     13526716.63
      2524394.62     13526731.82
#Sta/Elev= 30
    4406  194.01  4521.9  191.31  4560.7  191.07  4768.7  184.62  4791.2  183.13
    4859  180.56  4881.1  179.76  4915.7  181.12  4926.1  180.36  4932.3  178.95
  4937.9  179.12  4948.6  177.24  4954.5  174.79  4967.3  173.67  5008.1  173.12
  5008.3  172.62  5011.8  172.62  5012.1  173.12  5030.1  174.97  5050.1  175.87
  5070.1  175.63  5100.1  177.19  5123.2  177.58  5140.1  178.85  5201.3  180.74
  5319.7   185.3  5450.2     188  5540.2  190.48  5557.8  191.52  5680.6  195.85
#Mann= 8 ,-1 , 0
    4406     .04       0    4859    .013       0  4967.3     .05       0
  5008.1     .05       0  5012.1     .05       0  5201.3     .04       0
  5319.7     .05       0  5557.8     .04       0
Bank Sta=5008.1,5012.1
XS Rating Curve= 0 ,0
Exp/Cntr=0.3,0.1

Type RM Length L Ch R = 1 ,2472    ,77,77,77
BEGIN DESCRIPTION:
Mapping XS bd28546b
END DESCRIPTION:
XS GIS Cut Line= 3
      2525614.64     13526910.16      2525169.35     13526621.12
      2524508.93     13526623.72
#Sta/Elev= 30
  4374.8  193.03  4386.3  193.26  4465.4  191.71  4529.4  189.86  4537.9  190.21
  4543.8  189.38  4667.7   186.5  4818.7  181.69  4859.6  179.93  4891.2  179.26
  4905.3  180.17    4920   179.8    4950  176.74  4964.6  174.37    4970   173.5
    4978  173.21  4978.3  172.71  4981.8  172.71    4982  173.21    5030  173.43
    5040  174.47    5100  175.69  5119.9  176.82    5130  176.75  5301.7  182.19
    5350  183.49    5370  183.32    5380  184.29  5554.7  189.76  5566.1  190.33
#Mann= 8 ,-1 , 0
  4374.8     .04       0  4859.6    .013       0  4964.6     .05       0
    4978     .05       0    4982     .05       0  5119.9     .04       0
  5301.7     .05       0  5554.7     .04       0
Bank Sta=4978,4982
XS Rating Curve= 0 ,0
Exp/Cntr=0.3,0.1

Type RM Length L Ch R = 1 ,2395    ,71,71,71
BEGIN DESCRIPTION:
Mapping XS cb62cd59
END DESCRIPTION:
XS GIS Cut Line= 4
      2525604.26     13526872.43      2525186.28     13526561.22
      2524914.14     13526520.86      2524604.26     13526498.72
#Sta/Elev= 30
  4366.4  192.83  4377.9  192.21  4414.9  191.98  4471.2  190.72  4571.3  187.58
  4577.5  187.91  4592.1  187.18  4621.1  186.88  4706.8  184.48  4721.5  183.68
  4792.3  182.06  4821.6  180.49    4858  179.49  4864.2  178.88  4939.4  175.69
  4962.2  173.49  5037.9  173.11  5048.6   173.1  5048.8   172.6  5052.3   172.6
  5052.6   173.1  5060.7   173.1  5070.8  173.96  5080.9  173.66    5091  174.31
  5098.2  175.59  5131.4  175.97  5352.3  184.19  5432.5  186.59  5473.3  188.55
#Mann= 6 ,-1 , 0
  4366.4     .04       0    4858    .013       0  4962.2     .05       0
  5037.9     .04       0  5048.6     .05       0  5052.6     .04       0
Bank Sta=5048.6,5052.6
XS Rating Curve= 0 ,0
Exp/Cntr=0.3,0.1

Type RM Length L Ch R = 1 ,2324    ,59,59,59
BEGIN DESCRIPTION:
Mapping XS 74f0f6e5
END DESCRIPTION:
XS GIS Cut Line= 3
      2525631.13     13526856.84      2525131.98     13526483.56
      2524659.42     13526407.69
#Sta/Elev= 30
    4319  192.31  4331.7  192.58  4339.1  191.99  4410.9  191.46  4560.9  186.97
  4702.6  184.02    4711  183.36  4767.2  182.18  4843.7  178.86  4931.9  174.89
  4937.3  173.99  4949.4  173.26  4960.1   173.2  5024.6  173.14  5024.8  172.64
  5028.3  172.64  5028.6  173.14  5060.8  173.51    5081  174.75  5101.3  175.18
  5111.4  176.47  5131.7  176.36  5150.4  177.82  5232.9  181.76  5346.3  185.89
  5354.5  186.58  5374.7  186.88    5395  188.21  5408.3  188.14  5420.9  189.25
#Mann= 5 ,-1 , 0
    4319     .04       0  4843.7    .013       0  4960.1     .04       0
  5024.6     .04       0  5028.6     .04       0
Bank Sta=5024.6,5028.6
XS Rating Curve= 0 ,0
Exp/Cntr=0.3,0.1

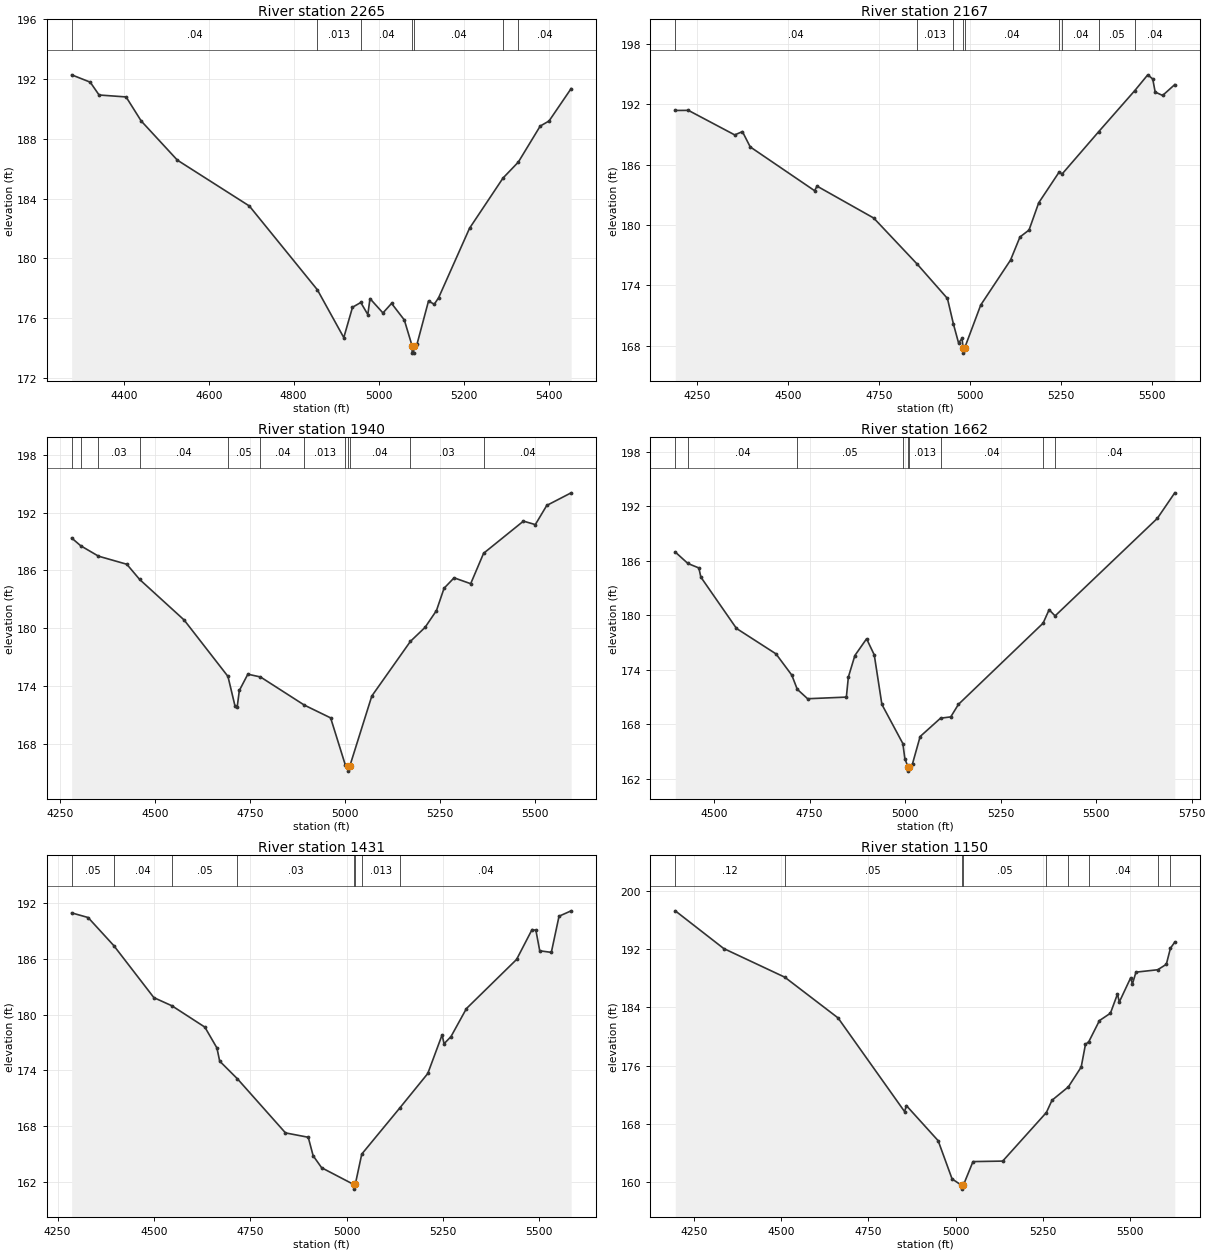
Type RM Length L Ch R = 1 ,2265    ,98,98,98
BEGIN DESCRIPTION:
Mapping XS 67489195
END DESCRIPTION:
XS GIS Cut Line= 5
       2525637.6     13526843.78      2525206.91     13526444.03
      2525053.86     13526409.78      2524956.04     13526410.18
      2524635.01     13526318.63
#Sta/Elev= 30
  4277.2  192.29  4320.9   191.8  4341.8  190.94  4405.4  190.81    4441   189.2
  4526.1  186.58  4695.6  183.51  4855.8   177.9    4918   174.7  4938.5  176.73
    4958  177.05  4974.6  176.24  4979.7  177.31  5010.2  176.35  5030.5  176.99
  5060.5  175.88  5078.7  174.16    5079  173.66  5082.5  173.66  5082.7  174.16
  5090.5  174.27  5117.5  177.15    5131  176.93  5141.3  177.37  5214.1  182.02
  5292.9  185.38    5329  186.45  5380.5  188.86  5401.3   189.2  5453.3  191.37
#Mann= 7 ,-1 , 0
  4277.2     .04       0  4855.8    .013       0    4958     .04       0
  5078.7     .04       0  5082.7     .04       0  5292.9     .03       0
    5329     .04       0
Bank Sta=5078.7,5082.7
XS Rating Curve= 0 ,0
Exp/Cntr=0.3,0.1

Type RM Length L Ch R = 1 ,2167    ,227,227,227
BEGIN DESCRIPTION:
Mapping XS 0fcf556a
END DESCRIPTION:
XS GIS Cut Line= 3
       2525674.5     13526826.43      2525216.62     13526344.67
      2524522.19     13526207.96
#Sta/Elev= 30
  4190.9  191.39  4226.9   191.4  4354.3  188.96  4375.4  189.29  4396.8  187.77
  4573.6  183.42  4580.5  183.87  4736.2   180.7  4855.7  176.12  4938.7  172.71
  4955.3  170.15  4969.3  168.29  4978.8  168.74  4981.9  167.78  4982.2  167.28
  4985.9  167.78  5030.2  172.06    5112  176.52    5138  178.82  5162.9  179.51
  5189.4  182.21  5244.9  185.23  5254.3   185.1    5354  189.27  5453.6  193.37
  5489.1  194.93  5502.7  194.52  5509.5  193.22  5529.9  192.88  5563.3  193.96
#Mann= 9 ,-1 , 0
  4190.9     .04       0  4855.7    .013       0  4955.3     .04       0
  4981.9     .04       0  4985.9     .04       0  5244.9     .03       0
  5254.3     .04       0    5354     .05       0  5453.6     .04       0
Bank Sta=4981.9,4985.9
XS Rating Curve= 0 ,0
Exp/Cntr=0.3,0.1

Type RM Length L Ch R = 1 ,1940    ,278,278,278
BEGIN DESCRIPTION:
Mapping XS aa4af766
END DESCRIPTION:
XS GIS Cut Line= 3
        2525770.     13526424.96      2525131.98     13526105.96
      2524530.89     13526073.41
#Sta/Elev= 30
  4279.6  189.36  4303.5  188.55  4350.3  187.47  4424.9  186.63  4458.7  185.05
  4575.8  180.84  4691.2  174.98    4710  171.87  4715.6  171.82  4721.2  173.52
  4743.6  175.21  4776.9  174.92  4892.3     172  4961.6  170.67    5000  165.81
  5007.9  165.64  5008.2  165.14  5011.9  165.64    5070  172.94  5171.7  178.62
  5210.2  180.07  5240.3  181.82  5260.3  184.14  5286.7  185.22  5330.4  184.61
  5364.4  187.77  5469.3  191.11  5500.6  190.75  5530.7  192.74  5594.9  194.05
#Mann= 12 ,-1 , 0
  4279.6     .03       0  4303.5     .04       0  4350.3     .03       0
  4458.7     .04       0  4691.2     .05       0  4776.9     .04       0
  4892.3    .013       0    5000     .04       0  5007.9     .03       0
  5011.9     .04       0  5171.7     .03       0  5364.4     .04       0
Bank Sta=5007.9,5011.9
XS Rating Curve= 0 ,0
Exp/Cntr=0.3,0.1

Type RM Length L Ch R = 1 ,1662    ,231,231,231
BEGIN DESCRIPTION:
4837
END DESCRIPTION:
XS GIS Cut Line= 3
      2525809.78     13525975.78      2525350.87     13525853.88
      2524519.51     13525896.88
#Sta/Elev= 30
  4398.5  186.98  4431.6  185.72  4460.2  185.23  4465.5  184.22  4558.7  178.57
  4662.1  175.77  4703.5  173.43  4717.8  171.87  4744.9  170.83  4846.3  171.01
  4851.5  173.21  4868.6  175.59  4899.2  177.43  4919.3  175.66  4939.3   170.2
  4994.2  165.89  4999.4  164.22  5007.4  163.36  5007.6  162.86  5011.4  163.36
  5019.4  163.67  5039.4  166.67  5092.8  168.69  5119.5  168.83  5139.6  170.21
  5361.2  179.15  5376.9  180.63  5392.6  179.95  5660.2  190.69  5705.8   193.5
#Mann= 9 ,-1 , 0
  4398.5     .05       0  4431.6     .04       0  4717.8     .05       0
  4994.2    .013       0  5007.4     .03       0  5011.4    .013       0
  5092.8     .04       0  5361.2     .03       0  5392.6     .04       0
Bank Sta=5007.4,5011.4
XS Rating Curve= 0 ,0
Exp/Cntr=0.3,0.1

Type RM Length L Ch R = 1 ,1431    ,281,281,281
BEGIN DESCRIPTION:
Mapping XS 30b8fcac
END DESCRIPTION:
XS GIS Cut Line= 3
      2525908.92     13525969.25      2525288.23     13525643.72
      2524693.65     13525680.61
#Sta/Elev= 30
  4286.4  190.94  4329.1  190.44  4395.8  187.42  4499.9  181.82  4546.9  180.94
  4632.2  178.65  4663.5  176.41  4670.7  174.99  4716.9  173.08  4841.5  167.27
  4900.6   166.8  4913.3  164.81  4935.4  163.52  5018.6  161.72  5018.8  161.22
  5022.6  161.72  5039.5  164.99  5138.2  169.95  5210.9  173.66  5248.1  177.82
  5253.1  176.86  5271.1  177.63  5311.1  180.64  5441.4  185.93  5481.5  189.14
  5491.5  189.07  5501.5  186.86  5531.6  186.69  5551.6  190.58    5583  191.16
#Mann= 8 ,-1 , 0
  4286.4     .05       0  4395.8     .04       0  4546.9     .05       0
  4716.9     .03       0  5018.6     .03       0  5022.6     .03       0
  5039.5    .013       0  5138.2     .04       0
Bank Sta=5018.6,5022.6
XS Rating Curve= 0 ,0
Exp/Cntr=0.3,0.1

Type RM Length L Ch R = 1 ,1150    ,410,410,410
BEGIN DESCRIPTION:
Mapping XS fa0ce514
END DESCRIPTION:
XS GIS Cut Line= 4
      2526162.77      13525550.4      2525446.66     13525394.15
      2525244.83     13525398.49      2524768.73     13525547.81
#Sta/Elev= 30
  4195.5  197.27  4334.7  192.09  4509.8  188.16  4662.7  182.57  4853.8   169.7
  4858.9  170.53  4950.1  165.71  4990.1  160.46  5018.1  159.56  5018.4  159.06
  5022.1  159.56  5050.1  162.84  5135.4  162.91  5260.8  169.58  5276.9  171.26
  5323.9   173.1  5360.7  175.82  5372.9  178.92  5382.7  179.32  5413.1   182.2
  5444.6  183.21  5464.9  185.85  5470.1  184.75  5502.6  188.06  5507.8  187.23
  5517.9  188.85  5580.4  189.18  5605.1  189.93  5616.9  192.14  5629.3  192.97
#Mann= 9 ,-1 , 0
  4195.5     .12       0  4509.8     .05       0  5018.1     .05       0
  5022.1     .05       0  5260.8    .013       0  5323.9     .05       0
  5382.7     .04       0  5580.4     .05       0  5616.9     .04       0
Bank Sta=5018.1,5022.1
XS Rating Curve= 0 ,0
Exp/Cntr=0.3,0.1

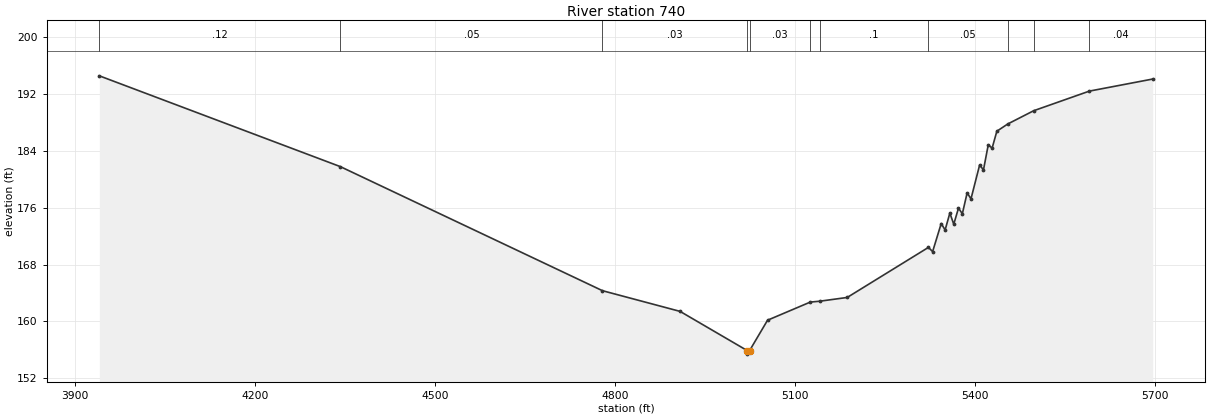
Type RM Length L Ch R = 1 ,740     ,0,0,0
BEGIN DESCRIPTION:
Mapping XS 4af4b964
END DESCRIPTION:
XS GIS Cut Line= 4
      2526141.07     13525431.03      2525264.36      13525027.4
       2525058.2     13525101.18      2524699.01     13525544.76
#Sta/Elev= 30
  3940.8  194.54  4342.3  181.77    4779  164.32  4908.3  161.41  5020.1   155.9
  5020.4   155.4  5024.1   155.9    5054  160.17  5125.2  162.72  5140.8  162.84
  5186.7  163.37    5322  170.41    5329  169.82  5343.3  173.77  5349.8  172.86
  5357.7  175.24  5364.2  173.67  5372.1  175.94  5378.5  175.14  5386.5  178.08
  5392.9  177.24  5407.3     182  5413.7  181.31  5421.7  184.85  5428.1  184.37
    5436  186.75  5454.2  187.77  5497.3  189.63  5590.1  192.39  5695.7  194.09
#Mann= 11 ,-1 , 0
  3940.8     .12       0  4342.3     .05       0    4779     .03       0
  5020.1     .03       0  5024.1     .03       0  5125.2     .05       0
  5140.8      .1       0    5322     .05       0  5454.2     .04       0
  5497.3     .05       0  5590.1     .04       0
Bank Sta=5020.1,5024.1
XS Rating Curve= 0 ,0
Exp/Cntr=0.3,0.1

Chan Stop Cuts=-1
Use User Specified Reach Order=0
Composite Channel Slope=5