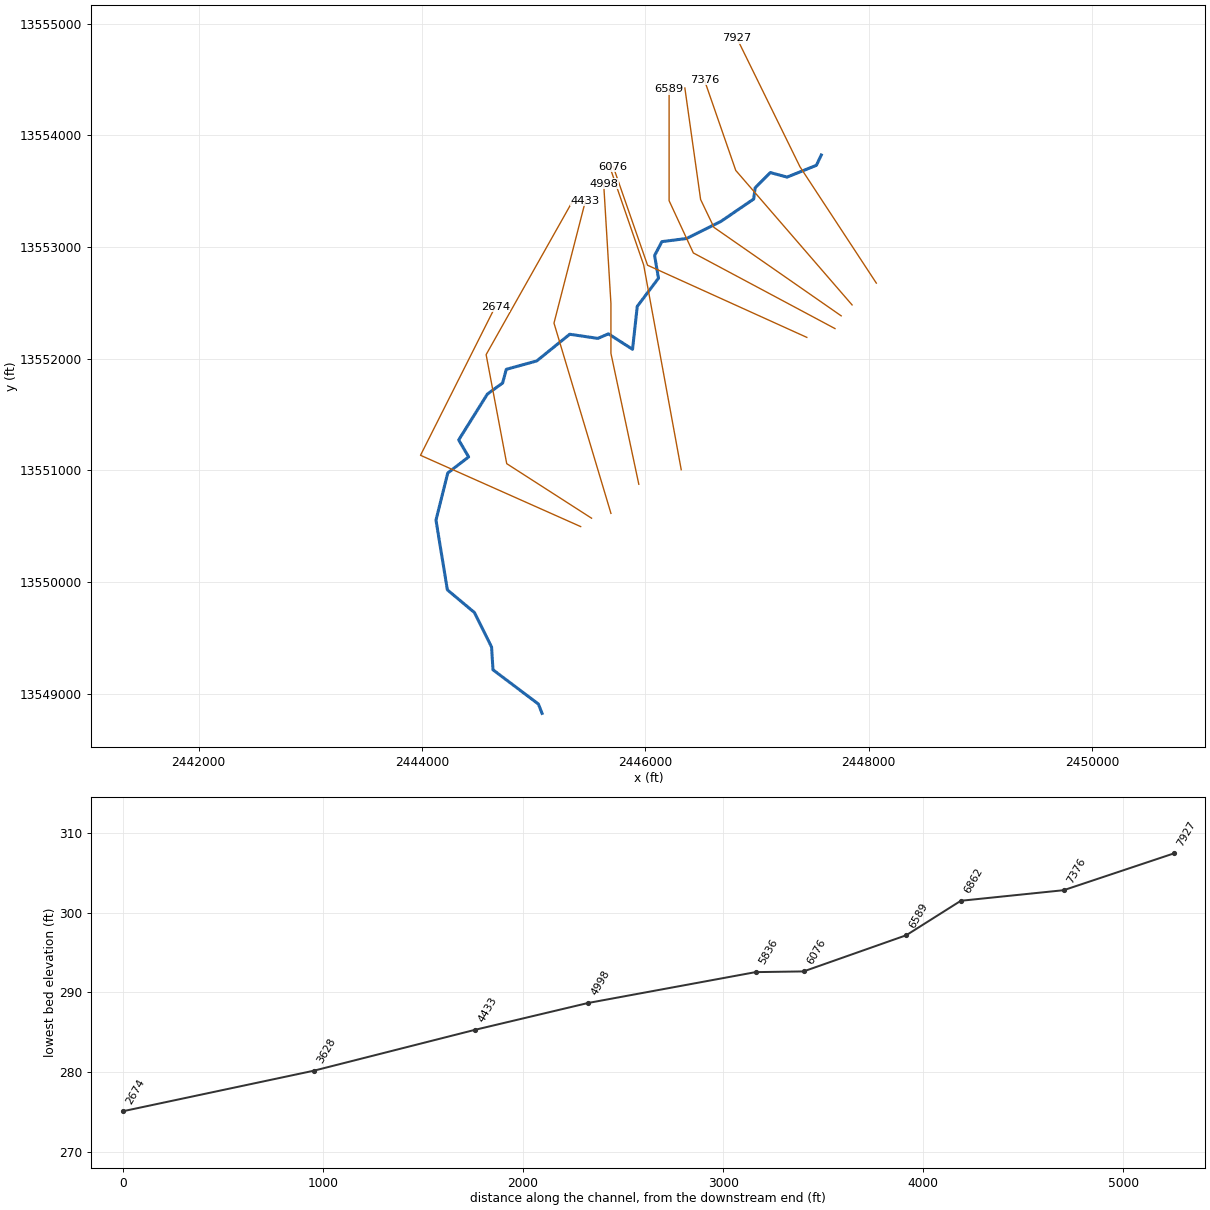
--- TRIB 5 TO YORKTOWN CREEK.prj (project) ---

Proj Title=TRIB 5 TO YORKTOWN CREEK Base Level Engineering
Current Plan=p01
Default Exp/Contr=0.3,0.1
English Units
Geom File=g01
Flow File=f01
Plan File=p01
BEGIN DESCRIPTION:
TRIB 5 TO YORKTOWN CREEK
END DESCRIPTION:

--- TRIB 5 TO YORKTOWN CREEK.p01 (plan) ---

Plan Title=Multiple Run
Short Identifier=Multiple
Geom File=g01
Flow File=f01
Subcritical Flow
K Sum by GR= 0
Std Step Tol= 0.01
Critical Tol= 0.01
Num of Std Step Trials= 20
Max Error Tol= 0.3
Flow Tol Ratio= 0.001
Split Flow NTrial= 30
Split Flow Tol= 0.02
Split Flow Ratio= 0.02
Log Output Level= 0
Friction Slope Method= 1
Unsteady Friction Slope Method= 2
Unsteady Bridges Friction Slope Method= 1
Parabolic Critical Depth
Global Vel Dist=  1 , 1 , 1
Global Log Level= 0
CheckData=True
Encroach Param= -1, 0, 0, 0
BEGIN DESCRIPTION:
Multiple Run
END DESCRIPTION:

--- TRIB 5 TO YORKTOWN CREEK.f01 (steady flow) ---

Flow Title=Multiple
Number of Profiles=7
Profile Names=10-year,25-year,50-year,1pct_min,100-year,1pct_plu,500-year
River Rch & RM= TRIB 5 TO YORKTO,Reach-1,7927
     392     616     814     522    1041    2077    1686
River Rch & RM= TRIB 5 TO YORKTO,Reach-1,6076
     532     852    1138     737    1470    2934    2432
Boundary for River Rch & Prof#=TRIB 5 TO YORKTO,Reach-1,1
Up Type=0
Dn Type=3
Dn Slope=0.005
Boundary for River Rch & Prof#=TRIB 5 TO YORKTO,Reach-1,2
Up Type=0
Dn Type=3
Dn Slope=0.005
Boundary for River Rch & Prof#=TRIB 5 TO YORKTO,Reach-1,3
Up Type=0
Dn Type=3
Dn Slope=0.005
Boundary for River Rch & Prof#=TRIB 5 TO YORKTO,Reach-1,4
Up Type=0
Dn Type=3
Dn Slope=0.005
Boundary for River Rch & Prof#=TRIB 5 TO YORKTO,Reach-1,5
Up Type=0
Dn Type=3
Dn Slope=0.005
Boundary for River Rch & Prof#=TRIB 5 TO YORKTO,Reach-1,6
Up Type=0
Dn Type=3
Dn Slope=0.005
Boundary for River Rch & Prof#=TRIB 5 TO YORKTO,Reach-1,7
Up Type=0
Dn Type=3
Dn Slope=0.005

--- TRIB 5 TO YORKTOWN CREEK.g01 (geometry) ---

Geom Title=Existing Conditions

River Reach=TRIB 5 TO YORKTO,Reach-1
Reach XY= 30
      2447575.00     13553825.00      2447531.45     13553732.64
      2447268.89     13553626.80      2447118.94     13553667.52
      2446982.88     13553531.12      2446969.75     13553430.44
      2446677.30     13553230.83      2446369.07     13553077.24
      2446147.79     13553048.97      2446082.76     13552924.92
      2446117.18     13552721.59      2445927.24     13552469.07
      2445885.05     13552085.02      2445668.95     13552223.35
      2445574.91     13552182.81      2445322.34     13552219.66
      2445027.30     13551980.83      2444754.36     13551905.58
      2444721.83     13551783.35      2444585.77     13551684.70
      2444328.31     13551273.26      2444417.51     13551121.42
      2444230.46     13550977.46      2444125.07     13550554.97
      2444227.06     13549930.85      2444469.58     13549727.67
      2444622.76     13549419.07      2444635.47     13549215.18
      2445042.03     13548908.61      2445075.00     13548825.00

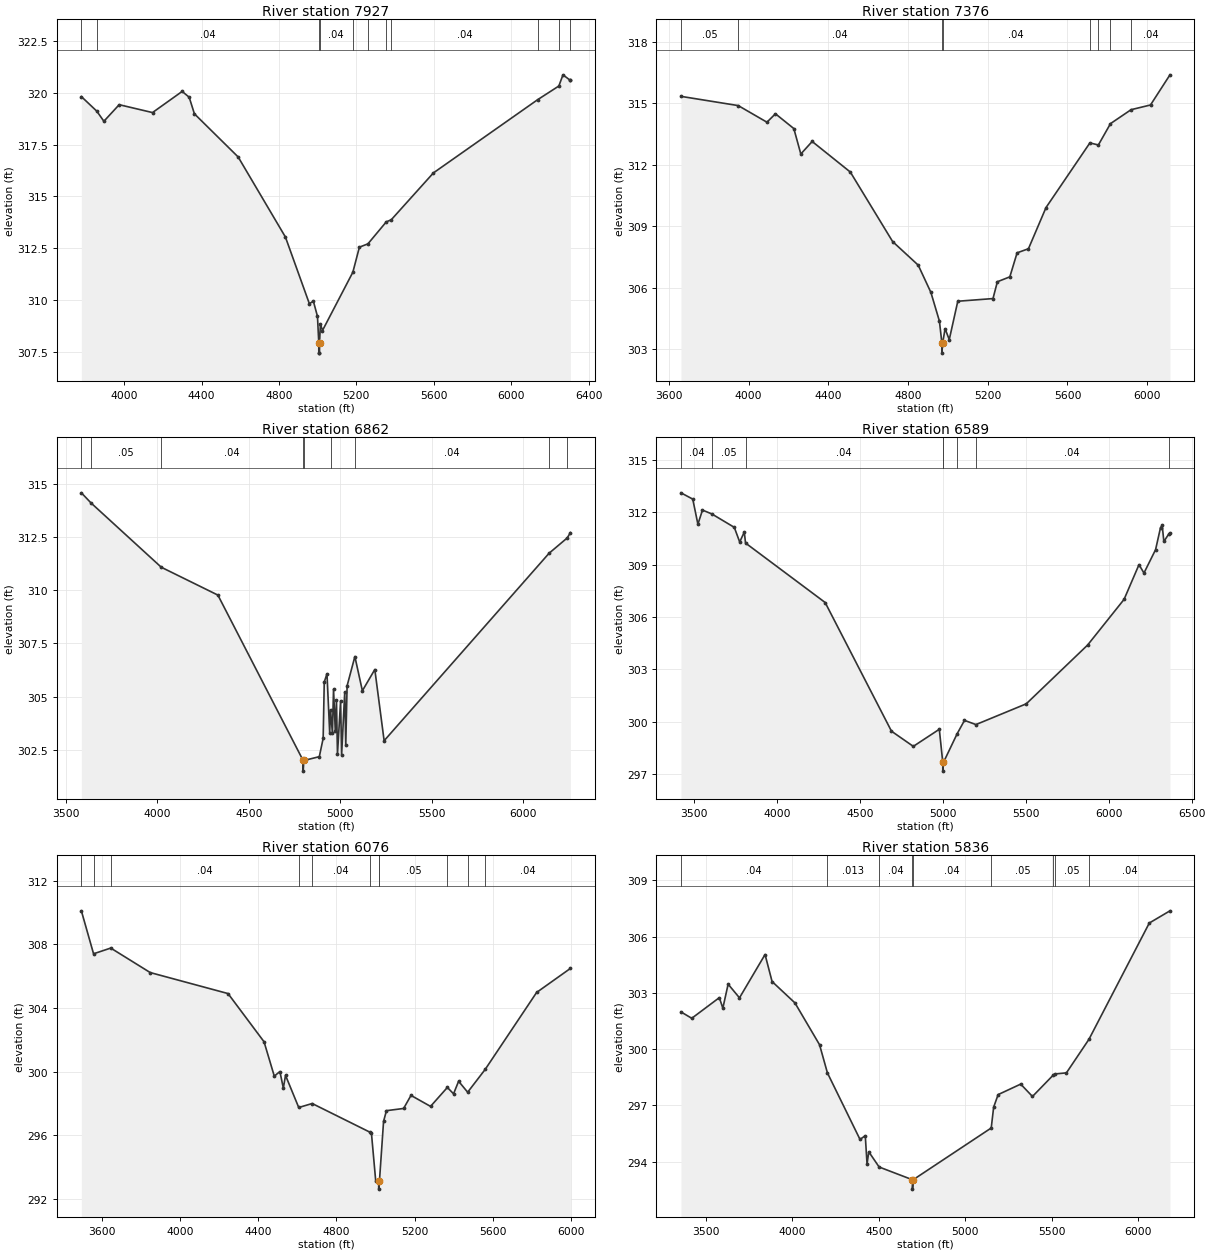
Type RM Length L Ch R = 1,7927,551,551,551
BEGIN DESCRIPTION:
LGII4613
END DESCRIPTION:
XS GIS Cut Line= 3
      2448067.93     13552677.70      2447384.36     13553719.33
      2446820.13     13554869.50
#Sta/Elev= 30
  3779.2  319.81  3858.7  319.11  3895.6  318.62  3974.6  319.42  4146.8  319.04
  4300.1  320.06  4336.3  319.78  4363.3  318.98  4589.3  316.90  4833.5  313.04
  4957.1  309.83  4978.2  309.94  4999.3  309.21  5006.0  307.94  5006.2  307.44
  5009.7  307.44  5010.0  307.94  5014.4  308.85  5025.1  308.53  5182.0  311.34
  5215.9  312.55  5260.0  312.71  5354.8  313.77  5380.4  313.87  5598.3  316.13
  6138.3  319.67  6246.5  320.32  6267.8  320.86  6303.3  320.61  6306.2  320.61
#Mann=11,-1,0
  3779.2    0.05       0  3858.7    0.04       0  5006.0    0.04       0
  5010.0    0.04       0  5182.0   0.013       0  5260.0    0.04       0
  5354.8   0.013       0  5380.4    0.04       0  6138.3   0.013       0
  6246.5    0.04       0  6303.3   0.013       0
Bank Sta=5006,5010
Exp/Cntr=0.3,0.1

Type RM Length L Ch R = 1,7376,514,514,514
BEGIN DESCRIPTION:
LGII4612
END DESCRIPTION:
XS GIS Cut Line= 3
      2447850.96     13552482.33      2446809.27     13553686.78
      2446527.26     13554500.26
#Sta/Elev= 30
  3660.8  315.34  3948.2  314.89  4092.2  314.08  4134.9  314.49  4227.1  313.77
  4262.2  312.53  4319.2  313.14  4510.5  311.65  4722.8  308.26  4851.1  307.11
  4914.8  305.78  4957.5  304.38  4969.8  303.32  4970.0  302.82  4973.8  303.32
  4986.0  304.01  5006.9  303.48  5049.7  305.35  5226.3  305.48  5248.2  306.30
  5310.8  306.54  5347.2  307.71  5404.2  307.91  5492.4  309.92  5712.4  313.07
  5755.0  312.97  5815.7  314.01  5919.0  314.69  6016.5  314.92  6114.2  316.39
#Mann=8,-1,0
  3660.8    0.05       0  3948.2    0.04       0  4969.8    0.04       0
  4973.8    0.04       0  5712.4   0.013       0  5755.0    0.04       0
  5815.7   0.013       0  5919.0    0.04       0
Bank Sta=4969.8,4973.8
Exp/Cntr=0.3,0.1

Type RM Length L Ch R = 1,6862,273,273,273
BEGIN DESCRIPTION:
LGII4611
END DESCRIPTION:
XS GIS Cut Line= 4
      2447753.28     13552384.70      2446613.96     13553176.80
      2446494.60     13553426.36      2446353.55     13554424.60
#Sta/Elev= 30
  3584.6  314.58  3637.8  314.10  4021.3  311.08  4330.6  309.77  4796.5  301.99
  4796.7  301.49  4800.5  301.99  4884.9  302.17  4905.9  303.03  4911.9  305.68
  4926.8  306.07  4941.6  303.30  4946.1  304.38  4956.5  303.28  4962.6  305.34
  4972.2  303.39  4978.6  304.84  4984.1  302.28  5001.2  304.79  5006.8  302.25
  5023.9  305.22  5029.5  302.73  5036.7  305.50  5079.2  306.88  5120.2  305.27
  5188.2  306.27  5239.1  302.92  6140.7  311.74  6239.9  312.46  6257.0  312.71
#Mann=9,-1,0
  3584.6    0.04       0  3637.8    0.05       0  4021.3    0.04       0
  4796.5    0.05       0  4800.5    0.04       0  4946.1    0.05       0
  5079.2    0.04       0  6140.7   0.013       0  6239.9    0.04       0
Bank Sta=4796.5,4800.5
Exp/Cntr=0.3,0.1

Type RM Length L Ch R = 1,6589,513,513,513
BEGIN DESCRIPTION:
LGII4610
END DESCRIPTION:
XS GIS Cut Line= 4
      2447697.85     13552270.54      2446429.45     13552947.76
      2446212.48     13553415.51      2446212.48     13554411.92
#Sta/Elev= 30
  3419.3  313.12  3490.5  312.76  3521.6  311.32  3549.2  312.13  3605.5  311.91
  3741.1  311.14  3773.7  310.30  3801.3  310.87  3809.0  310.24  4289.2  306.83
  4689.3  299.45  4821.0  298.58  4977.8  299.56  4998.7  297.66  4998.9  297.16
  5002.7  297.66  5085.2  299.30  5129.7  300.07  5198.8  299.83  5502.3  301.02
  5872.3  304.39  6092.3  307.01  6182.3  309.00  6212.3  308.52  6282.3  309.86
  6312.3  311.13  6322.3  311.25  6332.3  310.33  6360.8  310.74  6369.2  310.82
#Mann=8,-1,0
  3419.3    0.04       0  3605.5    0.05       0  3809.0    0.04       0
  4998.7    0.04       0  5002.7    0.04       0  5085.2    0.05       0
  5198.8    0.04       0  6360.8   0.013       0
Bank Sta=4998.7,5002.7
Exp/Cntr=0.3,0.1

Type RM Length L Ch R = 1,6076,240,240,240
BEGIN DESCRIPTION:
4838
END DESCRIPTION:
XS GIS Cut Line= 3
      2447445.66     13552191.77      2446019.45     13552837.89
      2445712.22     13553720.19
#Sta/Elev= 30
  3496.0  310.11  3558.3  307.41  3646.2  307.77  3848.0  306.23  4245.8  304.91
  4429.9  301.88  4482.3  299.72  4510.9  300.01  4528.5  298.97  4539.7  299.77
  4607.2  297.75  4676.0  298.00  4969.3  296.21  4978.8  296.15  5000.8  293.13
  5015.8  293.12  5016.1  292.62  5019.8  293.12  5040.9  296.88  5055.6  297.55
  5143.4  297.69  5181.1  298.51  5281.0  297.82  5367.0  299.01  5398.7  298.61
  5424.5  299.40  5470.8  298.71  5560.7  300.15  5823.3  304.98  5996.0  306.49
#Mann=11,-1,0
  3496.0    0.04       0  3558.3    0.05       0  3646.2    0.04       0
  4607.2    0.05       0  4676.0    0.04       0  4969.3    0.05       0
  5015.8    0.05       0  5019.8    0.05       0  5367.0    0.04       0
  5470.8    0.05       0  5560.7    0.04       0
Bank Sta=5015.8,5019.8
Exp/Cntr=0.3,0.1

Type RM Length L Ch R = 1,5836,838,838,838
BEGIN DESCRIPTION:
LGII4609
END DESCRIPTION:
XS GIS Cut Line= 3
      2446320.98     13551006.70      2445984.62     13552840.43
      2445670.30     13553750.88
#Sta/Elev= 30
  3355.2  301.98  3417.8  301.64  3577.1  302.74  3597.5  302.18  3628.0  303.46
  3693.6  302.73  3841.5  305.04  3882.1  303.60  4014.3  302.46  4156.6  300.23
  4202.0  298.73  4390.5  295.18  4421.0  295.38  4431.2  293.87  4441.3  294.52
  4501.0  293.71  4693.7  293.03  4694.0  292.53  4697.7  293.03  5149.2  295.79
  5163.2  296.90  5189.1  297.57  5319.6  298.13  5387.6  297.47  5508.7  298.62
  5515.9  298.67  5584.0  298.73  5714.3  300.52  6063.2  306.72  6182.7  307.37
#Mann=9,-1,0
  3355.2    0.04       0  4202.0   0.013       0  4501.0    0.04       0
  4693.7    0.04       0  4697.7    0.04       0  5149.2    0.05       0
  5508.7    0.04       0  5515.9    0.05       0  5714.3    0.04       0
Bank Sta=4693.7,4697.7
Exp/Cntr=0.3,0.1

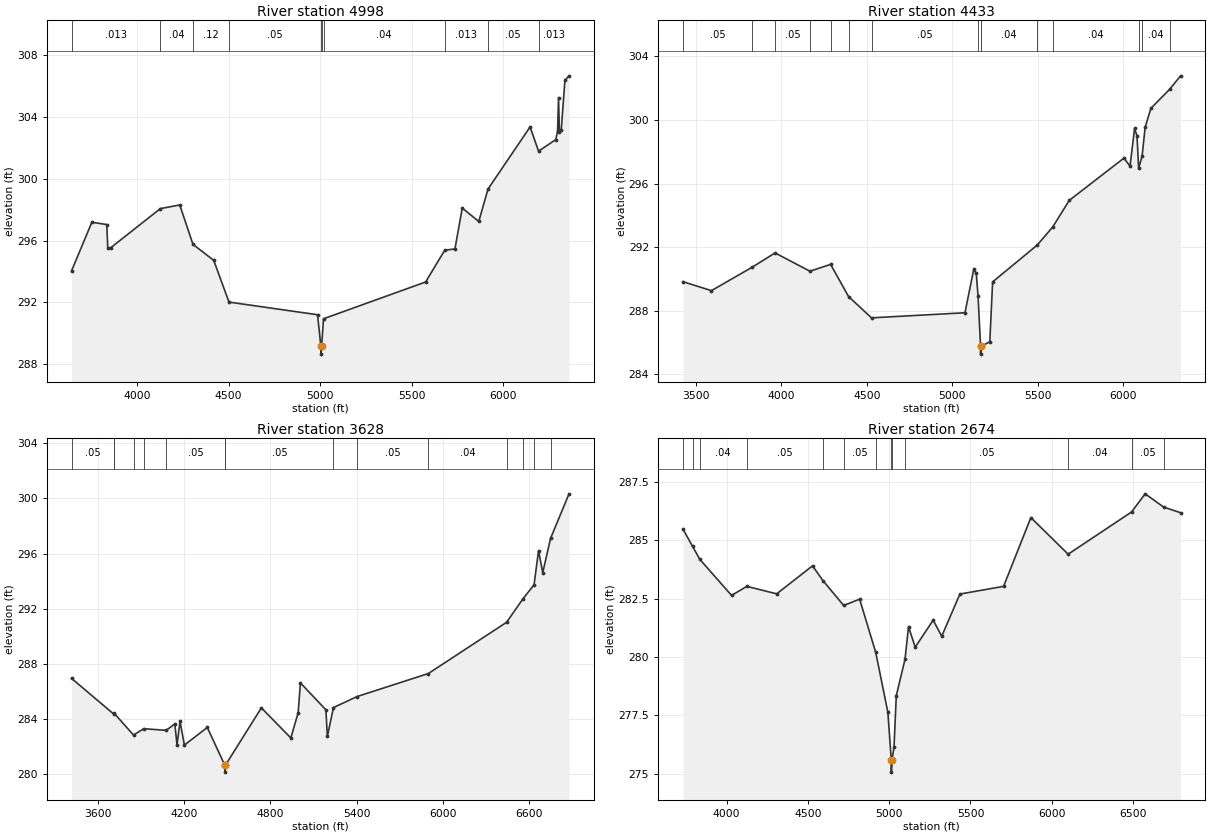
Type RM Length L Ch R = 1,4998,565,565,565
BEGIN DESCRIPTION:
LGII4608
END DESCRIPTION:
XS GIS Cut Line= 4
      2445941.21     13550876.47      2445691.65     13552048.32
      2445691.65     13552493.20      2445626.55     13553567.42
#Sta/Elev= 30
  3641.4  294.04  3752.4  297.19  3834.1  297.04  3839.3  295.55  3854.6  295.53
  4126.6  298.07  4232.9  298.31  4305.0  295.76  4418.7  294.72  4502.0  292.02
  4986.2  291.20  5004.2  289.15  5004.5  288.65  5008.2  289.15  5018.7  290.94
  5576.7  293.32  5681.4  295.38  5737.0  295.46  5777.1  298.11  5867.3  297.24
  5917.9  299.34  6147.8  303.36  6194.2  301.79  6288.0  302.54  6298.1  303.07
  6303.3  305.26  6308.3  303.01  6318.1  303.17  6338.1  306.37  6360.6  306.67
#Mann=10,-1,0
  3641.4   0.013       0  4126.6    0.04       0  4305.0    0.12       0
  4502.0    0.05       0  5004.2    0.05       0  5008.2    0.05       0
  5018.7    0.04       0  5681.4   0.013       0  5917.9    0.05       0
  6194.2   0.013       0
Bank Sta=5004.2,5008.2
Exp/Cntr=0.3,0.1

Type RM Length L Ch R = 1,4433,805,805,805
BEGIN DESCRIPTION:
LGII4607
END DESCRIPTION:
XS GIS Cut Line= 3
      2445691.65     13550616.02      2445181.67     13552319.59
      2445463.78     13553415.50
#Sta/Elev= 30
  3425.2  289.83  3591.1  289.27  3829.0  290.74  3963.3  291.64  4167.4  290.49
  4288.2  290.92  4393.2  288.90  4527.4  287.56  5074.2  287.88  5125.6  290.62
  5140.4  290.35  5150.7  288.92  5165.4  285.78  5165.6  285.28  5169.4  285.78
  5219.4  286.06  5235.9  289.82  5497.5  292.14  5588.0  293.28  5684.0  294.94
  6004.2  297.60  6039.7  297.09  6066.1  299.46  6080.4  299.00  6090.0  296.97
  6110.2  297.72  6128.1  299.54  6161.8  300.73  6271.9  301.93  6335.1  302.77
#Mann=15,-1,0
  3425.2    0.05       0  3829.0    0.12       0  3963.3    0.05       0
  4167.4    0.04       0  4288.2    0.05       0  4393.2    0.12       0
  4527.4    0.05       0  5150.7    0.04       0  5165.4    0.05       0
  5169.4    0.04       0  5497.5   0.013       0  5588.0    0.04       0
  6090.0   0.013       0  6110.2    0.04       0  6271.9    0.05       0
Bank Sta=5165.4,5169.4
Exp/Cntr=0.3,0.1

Type RM Length L Ch R = 1,3628,954,954,954
BEGIN DESCRIPTION:
LGII4606
END DESCRIPTION:
XS GIS Cut Line= 4
      2445518.07     13550572.61      2444758.49     13551060.91
      2444574.03     13552037.47      2445344.41     13553404.64
#Sta/Elev= 30
  3413.8  286.95  3706.6  284.37  3711.4  284.41  3845.5  282.84  3917.0  283.30
  4072.6  283.18  4133.4  283.64  4148.6  282.14  4169.8  283.83  4200.1  282.11
  4359.6  283.39  4481.8  280.65  4482.0  280.15  4485.8  280.65  4736.4  284.81
  4941.7  282.63  4992.6  284.45  5008.5  286.62  5186.0  284.67  5196.2  282.74
  5238.6  284.83  5403.1  285.63  5900.0  287.30  6445.5  291.02  6559.0  292.72
  6636.3  293.73  6667.6  296.21  6696.7  294.61  6751.3  297.10  6879.9  300.33
#Mann=15,-1,0
  3413.8    0.05       0  3706.6    0.12       0  3711.4    0.04       0
  3845.5    0.05       0  3917.0    0.12       0  4072.6    0.05       0
  4481.8    0.05       0  4485.8    0.05       0  5238.6    0.04       0
  5403.1    0.05       0  5900.0    0.04       0  6445.5    0.05       0
  6559.0    0.04       0  6636.3   0.013       0  6751.3    0.04       0
Bank Sta=4481.8,4485.8
Exp/Cntr=0.3,0.1

Type RM Length L Ch R = 1,2674,0,0,0
BEGIN DESCRIPTION:
4839
END DESCRIPTION:
XS GIS Cut Line= 3
      2445420.62     13550497.63      2443986.50     13551135.89
      2444656.25     13552467.51
#Sta/Elev= 30
  3732.2  285.48  3790.3  284.75  3835.1  284.19  4030.8  282.64  4124.1  283.03
  4308.3  282.71  4528.5  283.91  4593.6  283.27  4720.2  282.21  4818.3  282.48
  4917.3  280.20  4992.0  277.63  5013.2  275.56  5013.5  275.06  5017.2  275.56
  5029.9  276.14  5043.9  278.34  5097.5  279.90  5119.1  281.30  5160.2  280.42
  5270.7  281.58  5323.3  280.89  5435.3  282.70  5703.9  283.03  5871.8  285.98
  6101.0  284.41  6491.0  286.22  6574.9  287.00  6688.7  286.43  6792.5  286.19
#Mann=13,-1,0
  3732.2    0.04       0  3790.3    0.05       0  3835.1    0.04       0
  4124.1    0.05       0  4593.6    0.12       0  4720.2    0.05       0
  4917.3     0.1       0  5013.2    0.05       0  5017.2     0.1       0
  5097.5    0.05       0  6101.0    0.04       0  6491.0    0.05       0
  6688.7    0.04       0
Bank Sta=5013.2,5017.2
Exp/Cntr=0.3,0.1

Chan Stop Cuts=-1