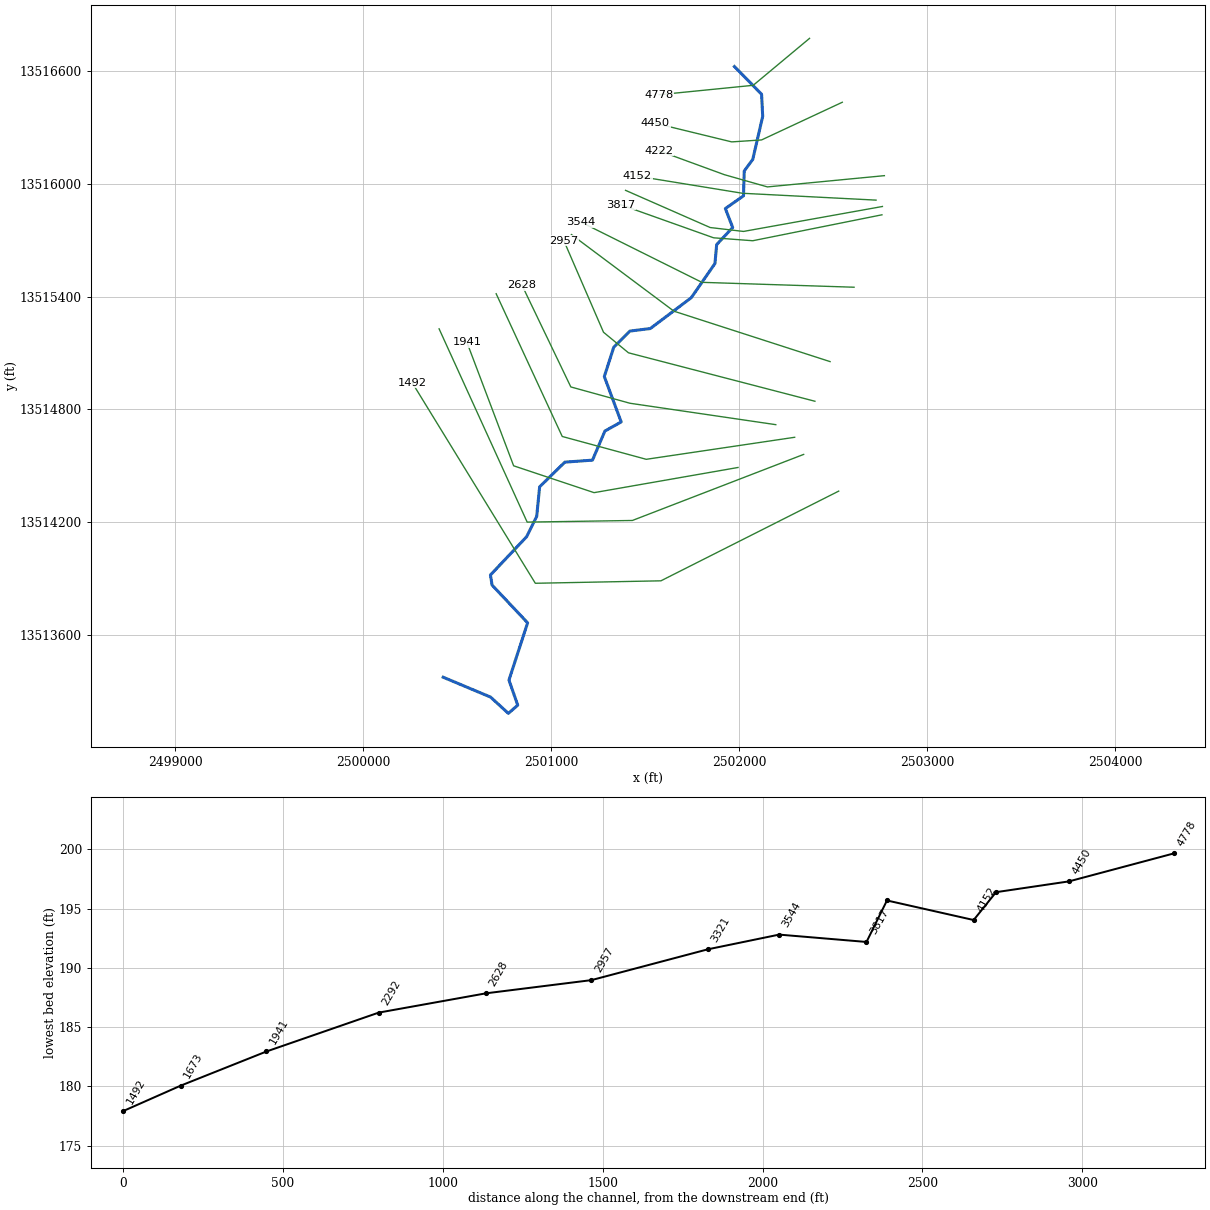
--- TRIB 5_1 TO FIFTEENMILE CREEK.prj (project) ---

Proj Title=TRIB 5_1 TO FIFTEENMILE CREEK Base Level Engineering
Current Plan=p01
Default Exp/Contr=0.3,0.1
English Units
Geom File=g01
Flow File=f01
Plan File=p01
BEGIN DESCRIPTION:
TRIB 5_1 TO FIFTEENMILE CREEK
END DESCRIPTION:

--- TRIB 5_1 TO FIFTEENMILE CREEK.p01 (plan) ---

Plan Title=Multiple Run
Short Identifier=Multiple
Geom File=g01
Flow File=f01
Subcritical Flow
K Sum by GR= 0
Std Step Tol= 0.01
Critical Tol= 0.01
Num of Std Step Trials= 20
Max Error Tol= 0.3
Flow Tol Ratio= 0.001
Split Flow NTrial= 30
Split Flow Tol= 0.02
Split Flow Ratio= 0.02
Log Output Level= 0
Friction Slope Method= 1
Unsteady Friction Slope Method= 2
Unsteady Bridges Friction Slope Method= 1
Parabolic Critical Depth
Global Vel Dist=  1 , 1 , 1
Global Log Level= 0
CheckData=True
Encroach Param= -1, 0, 0, 0
BEGIN DESCRIPTION:
Multiple Run
END DESCRIPTION:

--- TRIB 5_1 TO FIFTEENMILE CREEK.f01 (steady flow) ---

Flow Title=Multiple
Number of Profiles=7
Profile Names=10-year,25-year,50-year,1pct_min,100-year,1pct_plu,500-year
River Rch & RM= TRIB 5_1 TO FIFT,Reach-1,4778
     417     649     851     541    1079    2152    1712
River Rch & RM= TRIB 5_1 TO FIFT,Reach-1,2957
     464     728     959     612    1221    2437    1958
Boundary for River Rch & Prof#=TRIB 5_1 TO FIFT,Reach-1,1
Up Type=0
Dn Type=3
Dn Slope=0.005
Boundary for River Rch & Prof#=TRIB 5_1 TO FIFT,Reach-1,2
Up Type=0
Dn Type=3
Dn Slope=0.005
Boundary for River Rch & Prof#=TRIB 5_1 TO FIFT,Reach-1,3
Up Type=0
Dn Type=3
Dn Slope=0.005
Boundary for River Rch & Prof#=TRIB 5_1 TO FIFT,Reach-1,4
Up Type=0
Dn Type=3
Dn Slope=0.005
Boundary for River Rch & Prof#=TRIB 5_1 TO FIFT,Reach-1,5
Up Type=0
Dn Type=3
Dn Slope=0.005
Boundary for River Rch & Prof#=TRIB 5_1 TO FIFT,Reach-1,6
Up Type=0
Dn Type=3
Dn Slope=0.005
Boundary for River Rch & Prof#=TRIB 5_1 TO FIFT,Reach-1,7
Up Type=0
Dn Type=3
Dn Slope=0.005

--- TRIB 5_1 TO FIFTEENMILE CREEK.g01 (geometry) ---

Geom Title=Existing Conditions

River Reach=TRIB 5_1 TO FIFT,Reach-1
Reach XY= 30
      2501975.00     13516625.00      2502119.55     13516477.45
      2502125.47     13516359.84      2502072.73     13516130.94
      2502027.28     13516069.05      2502023.34     13515936.84
      2501926.61     13515869.12      2501965.83     13515768.28
      2501880.55     13515677.43      2501871.37     13515576.50
      2501745.42     13515394.77      2501527.42     13515230.54
      2501418.81     13515217.14      2501332.85     13515131.19
      2501282.56     13514975.00      2501372.35     13514733.49
      2501285.70     13514684.98      2501219.59     13514530.18
      2501072.56     13514519.53      2500938.37     13514388.32
      2500922.75     13514230.93      2500869.17     13514122.70
      2500676.58     13513918.95      2500685.17     13513865.32
      2500874.40     13513664.38      2500775.10     13513359.60
      2500821.87     13513226.14      2500771.91     13513182.52
      2500677.30     13513269.14      2500425.00     13513375.00

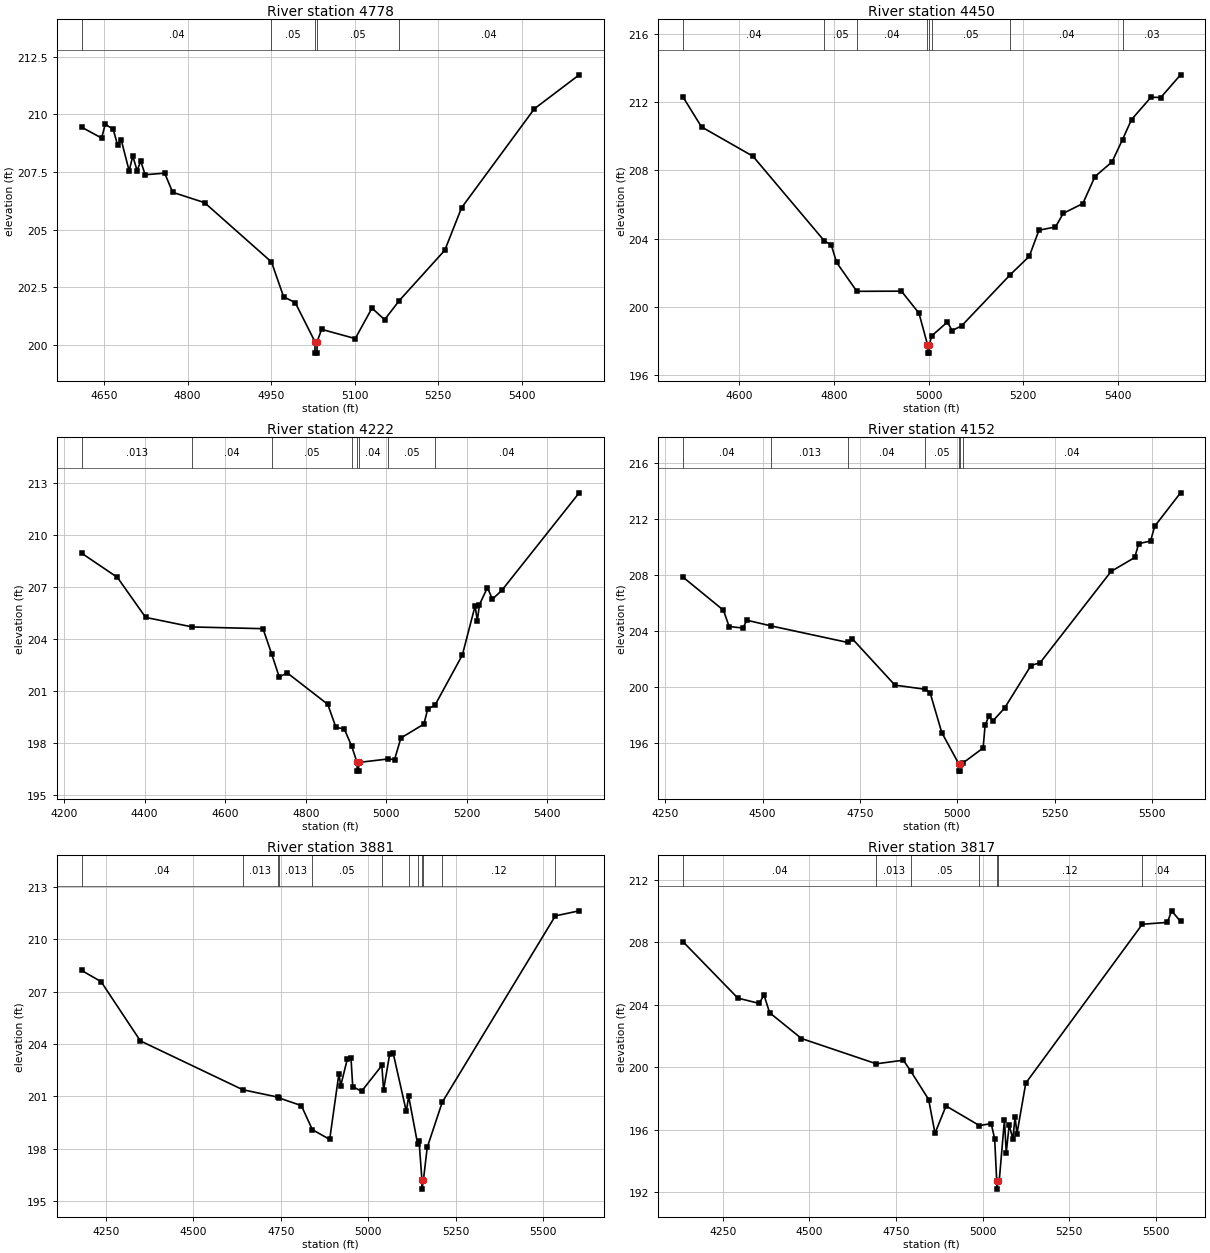
Type RM Length L Ch R = 1,4778,328,328,328
BEGIN DESCRIPTION:
TRIB 5_1 TO FIFTEENMILE CREEK 8.0
END DESCRIPTION:
XS GIS Cut Line= 3
      2502374.96     13516774.97      2502075.00     13516525.00
      2501574.96     13516475.00
#Sta/Elev= 30
  4609.8  209.44  4645.6  208.97  4652.1  209.57  4666.4  209.35  4674.2  208.67
  4680.7  208.90  4695.0  207.55  4701.5  208.19  4709.3  207.56  4715.8  207.97
  4723.7  207.38  4758.8  207.45  4773.1  206.62  4830.4  206.17  4950.5  203.60
  4972.3  202.09  4993.1  201.84  5028.4  200.15  5028.7  199.65  5032.2  199.65
  5032.4  200.15  5040.5  200.68  5100.8  200.28  5130.9  201.60  5153.5  201.10
  5180.0  201.93  5261.6  204.11  5291.7  205.95  5422.4  210.24  5502.8  211.71
#Mann=5,-1,0
  4609.8    0.04       0  4950.5    0.05       0  5028.4    0.05       0
  5032.4    0.05       0  5180.0    0.04       0
Bank Sta=5028.4,5032.4
Exp/Cntr=0.3,0.1

Type RM Length L Ch R = 1,4450,228,228,228
BEGIN DESCRIPTION:
Mapping XS e5e5fad4
END DESCRIPTION:
XS GIS Cut Line= 4
      2502549.14     13516434.81      2502119.43     13516234.28
      2501960.58     13516223.86      2501554.34     13516322.82
#Sta/Elev= 30
  4480.9  212.29  4520.0  210.54  4628.8  208.82  4779.7  203.86  4794.3  203.62
  4805.5  202.60  4848.3  200.91  4942.5  200.92  4979.6  199.63  4997.6  197.79
  4997.9  197.29  5001.4  197.29  5001.6  197.79  5006.5  198.30  5039.7  199.11
  5049.7  198.61  5069.8  198.89  5172.7  201.89  5212.7  202.96  5233.2  204.49
  5268.1  204.68  5284.7  205.48  5325.9  206.05  5351.5  207.63  5387.6  208.49
  5409.8  209.80  5428.8  210.97  5470.0  212.28  5490.6  212.26  5532.4  213.59
#Mann=8,-1,0
  4480.9    0.04       0  4779.7    0.05       0  4848.3    0.04       0
  4997.6    0.04       0  5001.6    0.04       0  5006.5    0.05       0
  5172.7    0.04       0  5409.8    0.03       0
Bank Sta=4997.6,5001.6
Exp/Cntr=0.3,0.1

Type RM Length L Ch R = 1,4222,70,70,70
BEGIN DESCRIPTION:
Mapping XS 561a6f4d
END DESCRIPTION:
XS GIS Cut Line= 4
      2502773.05     13516044.17      2502150.68     13515984.28
      2501921.52     13516049.38      2501572.59     13516176.98
#Sta/Elev= 30
  4243.9  208.94  4332.4  207.55  4402.7  205.24  4518.3  204.69  4694.0  204.59
  4715.3  203.15  4734.2  201.81  4754.3  202.04  4854.8  200.23  4875.0  198.90
  4895.8  198.81  4914.3  197.81  4927.4  196.88  4927.7  196.38  4931.2  196.38
  4931.4  196.88  5004.2  197.08  5020.6  197.05  5036.3  198.29  5093.4  199.09
  5103.0  199.97  5120.7  200.17  5188.8  203.07  5220.6  205.91  5225.9  205.04
  5231.4  205.98  5251.1  206.96  5263.4  206.29  5286.9  206.80  5478.9  212.42
#Mann=8,-1,0
  4243.9   0.013       0  4518.3    0.04       0  4715.3    0.05       0
  4914.3    0.04       0  4927.4    0.04       0  4931.4    0.04       0
  5004.2    0.05       0  5120.7    0.04       0
Bank Sta=4927.4,4931.4
Exp/Cntr=0.3,0.1

Type RM Length L Ch R = 1,4152,271,271,271
BEGIN DESCRIPTION:
Mapping XS a3180081
END DESCRIPTION:
XS GIS Cut Line= 3
      2502728.78     13515913.97      2502017.87     13515950.43
      2501458.97     13516041.41
#Sta/Elev= 30
  4295.6  207.86  4399.5  205.50  4414.0  204.34  4449.6  204.23  4459.6  204.79
  4522.2  204.38  4719.3  203.20  4730.0  203.48  4840.1  200.16  4916.5  199.87
  4930.2  199.63  4960.3  196.78  5004.4  194.53  5004.6  194.03  5008.1  194.03
  5008.4  194.53  5015.2  194.62  5066.6  195.68  5071.6  197.30  5081.3  197.94
  5091.4  197.60  5121.8  198.53  5189.6  201.56  5213.0  201.76  5395.4  208.27
  5456.1  209.26  5466.3  210.25  5496.7  210.43  5507.3  211.49  5573.7  213.87
#Mann=7,-1,0
  4295.6    0.04       0  4522.2   0.013       0  4719.3    0.04       0
  4916.5    0.05       0  5004.4    0.05       0  5008.4    0.05       0
  5015.2    0.04       0
Bank Sta=5004.4,5008.4
Exp/Cntr=0.3,0.1

Type RM Length L Ch R = 1,3881,64,64,64
BEGIN DESCRIPTION:
Mapping XS a7301409
END DESCRIPTION:
XS GIS Cut Line= 4
      2502762.66     13515880.11      2502023.08     13515747.30
      2501845.99     13515768.13      2501395.47     13515966.05
#Sta/Elev= 30
  4180.9  208.22  4236.3  207.58  4348.7  204.18  4641.3  201.38  4740.7  200.96
  4744.8  200.91  4808.7  200.47  4840.1  199.09  4889.7  198.53  4916.1  202.31
  4921.2  201.61  4940.4  203.17  4950.5  203.22  4955.5  201.56  4980.7  201.29
  5038.8  202.77  5043.6  201.36  5061.3  203.45  5071.3  203.46  5108.6  200.14
  5115.4  201.00  5140.8  198.29  5145.0  198.45  5153.4  196.18  5153.6  195.68
  5157.4  196.18  5168.4  198.07  5211.2  200.66  5534.5  211.35  5602.7  211.64
#Mann=12,-1,0
  4180.9    0.04       0  4641.3   0.013       0  4740.7    0.04       0
  4744.8   0.013       0  4840.1    0.05       0  5038.8    0.12       0
  5115.4    0.05       0  5140.8    0.04       0  5153.4    0.05       0
  5157.4    0.04       0  5211.2    0.12       0  5534.5    0.04       0
Bank Sta=5153.4,5157.4
Exp/Cntr=0.3,0.1

Type RM Length L Ch R = 1,3817,273,273,273
BEGIN DESCRIPTION:
Mapping XS 19d780b0
END DESCRIPTION:
XS GIS Cut Line= 4
      2502760.07     13515835.85      2502072.56     13515697.82
      2501864.22     13515713.45      2501369.12     13515889.71
#Sta/Elev= 30
  4135.4  208.03  4293.6  204.42  4354.8  204.08  4369.2  204.61  4385.4  203.48
  4477.2  201.83  4693.2  200.21  4771.3  200.44  4792.9  199.73  4844.2  197.92
  4862.5  195.76  4894.4  197.51  4990.9  196.25  5024.7  196.38  5034.7  195.41
  5040.7  192.68  5040.9  192.18  5044.7  192.68  5047.8  192.68  5062.9  196.60
  5068.2  194.52  5076.6  196.28  5087.2  195.40  5093.7  196.81  5099.0  195.72
  5124.5  198.97  5460.8  209.15  5533.0  209.27  5545.5  210.01  5571.1  209.33
#Mann=7,-1,0
  4135.4    0.04       0  4693.2   0.013       0  4792.9    0.05       0
  4990.9    0.12       0  5040.7    0.05       0  5044.7    0.12       0
  5460.8    0.04       0
Bank Sta=5040.7,5044.7
Exp/Cntr=0.3,0.1

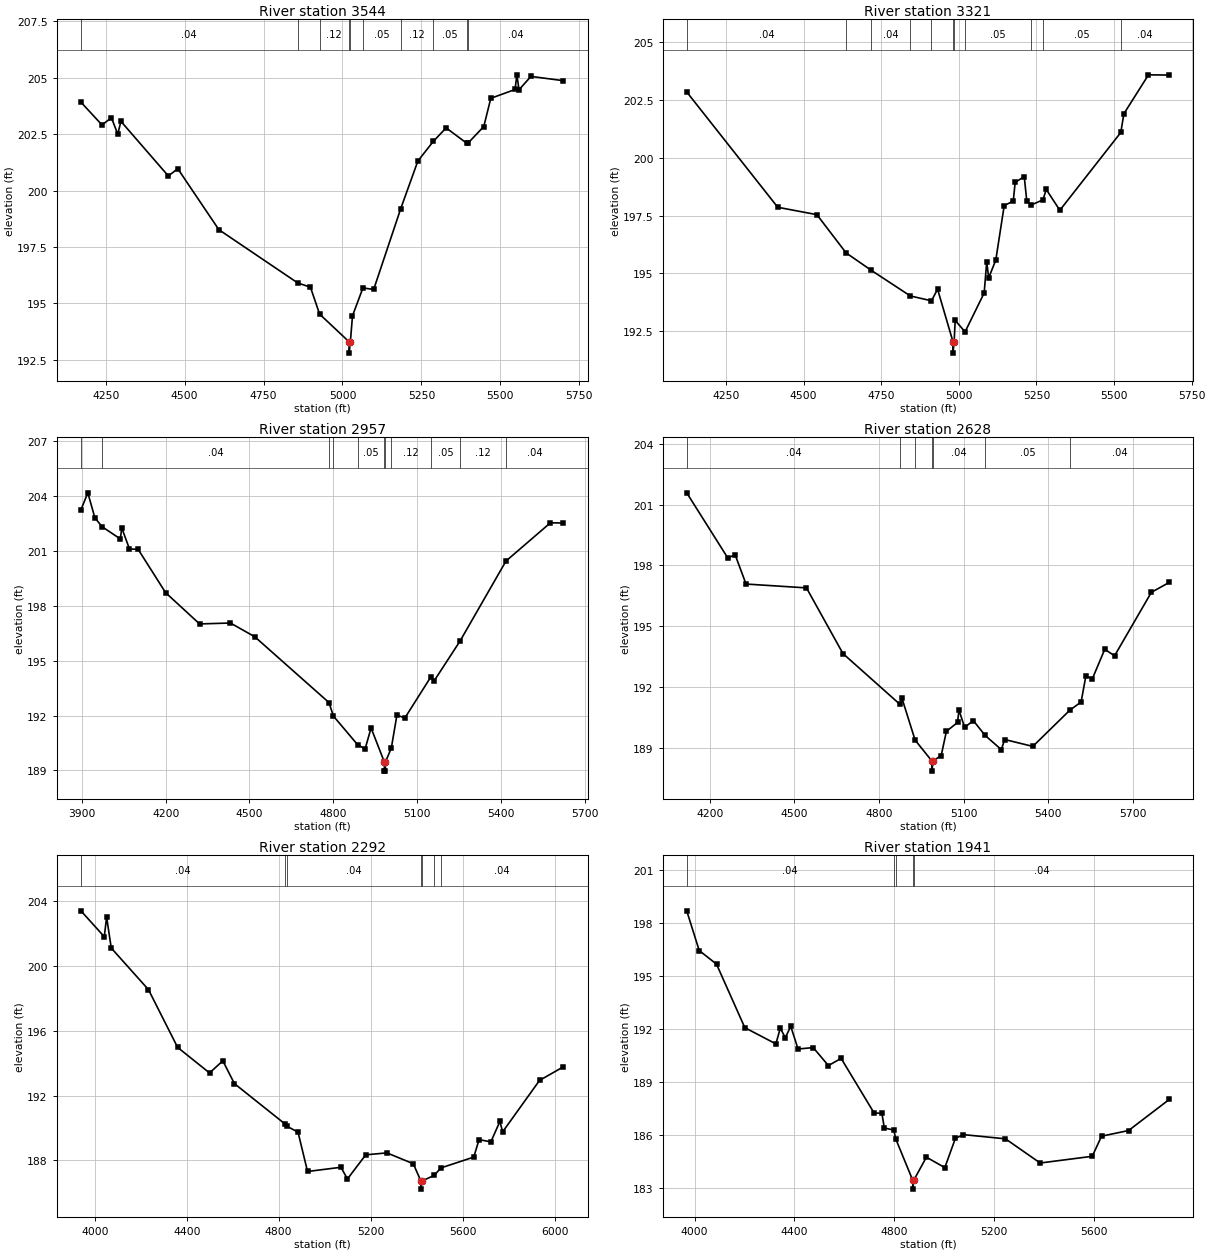
Type RM Length L Ch R = 1,3544,223,223,223
BEGIN DESCRIPTION:
Mapping XS 76c421c7
END DESCRIPTION:
XS GIS Cut Line= 3
      2502611.66     13515450.42      2501801.72     13515476.47
      2501159.23     13515796.41
#Sta/Elev= 30
  4171.7  203.92  4238.4  202.91  4268.4  203.23  4288.4  202.50  4298.4  203.07
  4448.5  200.65  4478.5  200.97  4608.6  198.27  4858.3  195.91  4898.7  195.72
  4927.6  194.53  5021.1  193.30  5021.3  192.80  5025.1  193.30  5031.8  194.45
  5064.9  195.69  5098.9  195.62  5184.3  199.19  5238.8  201.31  5287.7  202.18
  5328.4  202.78  5393.6  202.10  5398.1  202.11  5447.6  202.84  5469.9  204.09
  5546.7  204.48  5552.3  205.13  5559.3  204.47  5597.0  205.06  5699.8  204.87
#Mann=10,-1,0
  4171.7    0.04       0  4858.3   0.013       0  4927.6    0.12       0
  5021.1    0.05       0  5025.1    0.12       0  5064.9    0.05       0
  5184.3    0.12       0  5287.7    0.05       0  5393.6    0.12       0
  5398.1    0.04       0
Bank Sta=5021.1,5025.1
Exp/Cntr=0.3,0.1

Type RM Length L Ch R = 1,3321,364,364,364
BEGIN DESCRIPTION:
Mapping XS 2404fde2
END DESCRIPTION:
XS GIS Cut Line= 3
      2502483.98     13515054.60      2501653.29     13515322.82
      2501107.56     13515730.82
#Sta/Elev= 30
  4123.4  202.84  4416.6  197.86  4542.7  197.54  4636.7  195.89  4718.6  195.13
  4843.7  194.03  4911.8  193.82  4931.5  194.32  4980.9  192.06  4981.2  191.56
  4984.9  192.06  4988.2  192.97  5020.1  192.48  5081.6  194.16  5089.8  195.51
  5096.1  194.81  5119.0  195.58  5146.1  197.93  5175.3  198.13  5181.5  198.94
  5210.7  199.18  5218.9  198.12  5231.5  197.95  5270.9  198.18  5281.6  198.63
  5325.3  197.73  5521.7  201.09  5531.7  201.90  5610.9  203.58  5677.7  203.57
#Mann=11,-1,0
  4123.4    0.04       0  4636.7    0.12       0  4718.6    0.04       0
  4843.7   0.013       0  4911.8    0.12       0  4980.9    0.05       0
  4984.9    0.12       0  5020.1    0.05       0  5231.5    0.12       0
  5270.9    0.05       0  5521.7    0.04       0
Bank Sta=4980.9,4984.9
Exp/Cntr=0.3,0.1

Type RM Length L Ch R = 1,2957,329,329,329
BEGIN DESCRIPTION:
Mapping XS f75f3c4b
END DESCRIPTION:
XS GIS Cut Line= 4
      2502403.33     13514843.64      2501411.10     13515101.47
      2501278.29     13515210.84      2501067.36     13515697.79
#Sta/Elev= 30
  3896.4  203.25  3921.1  204.18  3946.3  202.82  3971.8  202.33  4037.6  201.66
  4042.7  202.26  4070.3  201.11  4101.3  201.09  4199.7  198.72  4321.4  197.01
  4431.9  197.06  4518.9  196.31  4784.7  192.71  4800.7  191.97  4887.0  190.41
  4914.1  190.17  4935.5  191.32  4983.0  189.46  4983.2  188.96  4986.7  188.96
  4987.0  189.46  5008.0  190.22  5028.0  192.02  5056.7  191.87  5149.5  194.11
  5161.5  193.90  5254.0  196.07  5418.7  200.45  5577.7  202.54  5624.3  202.53
#Mann=11,-1,0
  3896.4    0.12       0  3971.8    0.04       0  4784.7   0.013       0
  4800.7    0.04       0  4887.0    0.05       0  4983.0    0.05       0
  4987.0    0.05       0  5008.0    0.12       0  5149.5    0.05       0
  5254.0    0.12       0  5418.7    0.04       0
Bank Sta=4983,4987
Exp/Cntr=0.3,0.1

Type RM Length L Ch R = 1,2628,336,336,336
BEGIN DESCRIPTION:
4840
END DESCRIPTION:
XS GIS Cut Line= 4
      2502195.02     13514719.01      2501419.06     13514832.96
      2501104.36     13514919.77      2500844.48     13515461.20
#Sta/Elev= 30
  4118.0  201.58  4263.5  198.37  4289.8  198.52  4328.3  197.08  4542.7  196.89
  4672.1  193.65  4874.6  191.14  4881.5  191.44  4928.0  189.38  4987.5  188.35
  4987.7  187.85  4991.5  188.35  5020.6  188.62  5038.9  189.81  5078.4  190.25
  5083.6  190.86  5103.6  190.01  5134.7  190.34  5176.4  189.61  5233.9  188.91
  5245.6  189.41  5345.5  189.07  5477.1  190.86  5516.8  191.26  5533.9  192.56
  5556.2  192.39  5600.6  193.86  5635.5  193.54  5765.9  196.67  5829.3  197.16
#Mann=7,-1,0
  4118.0    0.04       0  4874.6   0.013       0  4928.0    0.04       0
  4987.5    0.04       0  4991.5    0.04       0  5176.4    0.05       0
  5477.1    0.04       0
Bank Sta=4987.5,4991.5
Exp/Cntr=0.3,0.1

Type RM Length L Ch R = 1,2292,351,351,351
BEGIN DESCRIPTION:
Mapping XS 22d6cb86
END DESCRIPTION:
XS GIS Cut Line= 4
      2502295.60     13514651.81      2501505.72     13514534.63
      2501058.67     13514656.15      2500707.09     13515415.73
#Sta/Elev= 30
  3939.8  203.42  4041.5  201.82  4051.6  203.03  4071.8  201.12  4233.6  198.55
  4360.5  194.98  4499.4  193.40  4557.1  194.15  4607.6  192.74  4828.1  190.24
  4837.0  190.10  4884.2  189.74  4925.6  187.31  5070.7  187.57  5099.3  186.85
  5178.8  188.34  5270.9  188.46  5385.5  187.79  5418.7  186.72  5419.0  186.22
  5422.7  186.72  5476.8  187.07  5505.5  187.53  5648.7  188.20  5671.6  189.28
  5723.0  189.14  5762.3  190.40  5774.3  189.76  5934.8  192.94  6038.6  193.78
#Mann=7,-1,0
  3939.8    0.04       0  4828.1   0.013       0  4837.0    0.04       0
  5418.7    0.04       0  5422.7    0.04       0  5476.8    0.05       0
  5505.5    0.04       0
Bank Sta=5418.7,5422.7
Exp/Cntr=0.3,0.1

Type RM Length L Ch R = 1,1941,268,268,268
BEGIN DESCRIPTION:
4841
END DESCRIPTION:
XS GIS Cut Line= 4
      2501994.22     13514491.13      2501228.20     13514357.18
      2500800.00     13514500.00      2500550.91     13515158.53
#Sta/Elev= 30
  3968.4  198.71  4018.4  196.46  4087.7  195.69  4201.1  192.09  4325.6  191.17
  4343.2  192.06  4363.5  191.52  4385.1  192.17  4414.3  190.88  4475.2  190.96
  4536.1  189.94  4586.9  190.35  4718.8  187.26  4750.4  187.23  4760.1  186.40
  4798.0  186.29  4806.0  185.78  4873.9  183.44  4874.2  182.94  4877.9  183.44
  4928.6  184.75  5002.4  184.16  5044.6  185.81  5076.2  186.03  5245.5  185.79
  5384.5  184.42  5593.1  184.80  5630.4  185.94  5738.6  186.26  5901.5  188.02
#Mann=5,-1,0
  3968.4    0.04       0  4798.0    0.12       0  4806.0    0.04       0
  4873.9    0.04       0  4877.9    0.04       0
Bank Sta=4873.9,4877.9
Exp/Cntr=0.3,0.1

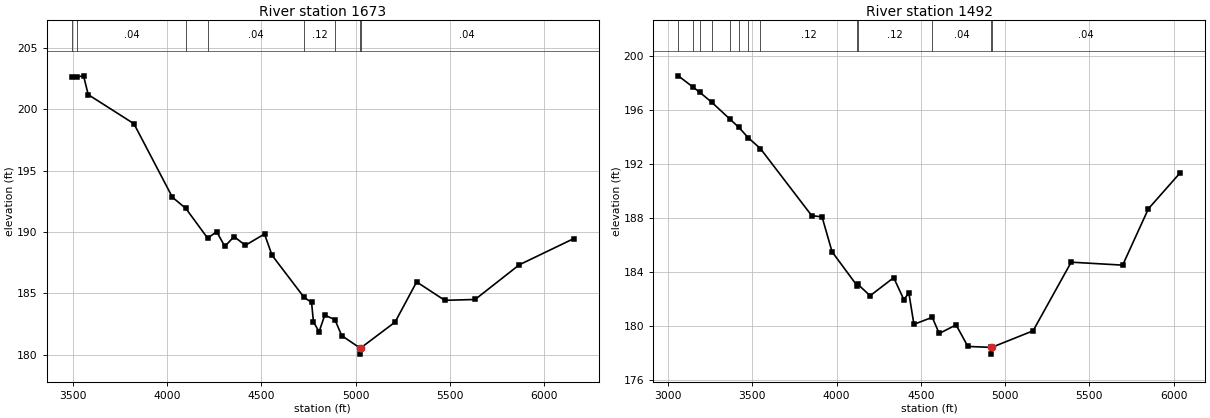
Type RM Length L Ch R = 1,1673,181,181,181
BEGIN DESCRIPTION:
Mapping XS 612ef8a2
END DESCRIPTION:
XS GIS Cut Line= 4
      2502343.39     13514560.67      2501431.93     13514209.11
      2500872.04     13514200.43      2500403.28     13515229.08
#Sta/Elev= 30
  3492.1  202.65  3520.9  202.64  3554.8  202.72  3579.4  201.19  3822.3  198.82
  4026.8  192.83  4097.7  191.93  4214.0  189.50  4262.1  190.03  4305.1  188.83
  4354.3  189.63  4414.2  188.92  4516.0  189.84  4556.0  188.11  4726.3  184.68
  4766.0  184.27  4776.0  182.69  4806.0  181.88  4836.0  183.23  4890.0  182.87
  4926.0  181.57  5023.0  180.56  5023.2  180.06  5027.0  180.56  5209.8  182.67
  5324.2  185.94  5473.6  184.44  5634.8  184.51  5869.2  187.33  6159.4  189.47
#Mann=8,-1,0
  3492.1    0.12       0  3520.9    0.04       0  4097.7    0.12       0
  4214.0    0.04       0  4726.3    0.12       0  4890.0    0.04       0
  5023.0    0.04       0  5027.0    0.04       0
Bank Sta=5023,5027
Exp/Cntr=0.3,0.1

Type RM Length L Ch R = 1,1492,0,0,0
BEGIN DESCRIPTION:
Mapping XS b45380be
END DESCRIPTION:
XS GIS Cut Line= 4
      2502530.02     13514365.35      2501583.84     13513887.93
      2500915.44     13513874.90      2500260.86     13514941.30
#Sta/Elev= 30
  3060.5  198.54  3150.8  197.68  3188.9  197.31  3259.4  196.58  3367.9  195.32
  3420.8  194.71  3476.5  193.94  3547.7  193.15  3852.6  188.17  3913.9  188.08
  3973.4  185.49  4123.1  182.96  4127.3  183.07  4199.2  182.23  4339.2  183.57
  4399.2  181.95  4429.2  182.43  4459.2  180.11  4568.1  180.63  4609.2  179.43
  4709.3  180.07  4779.3  178.47  4916.9  178.40  4917.2  177.90  4920.9  178.40
  5166.4  179.63  5392.5  184.72  5698.0  184.50  5850.7  188.68  6040.1  191.36
#Mann=13,-1,0
  3060.5    0.05       0  3150.8    0.12       0  3188.9    0.05       0
  3259.4    0.04       0  3367.9    0.12       0  3420.8    0.05       0
  3476.5    0.04       0  3547.7    0.12       0  4123.1    0.04       0
  4127.3    0.12       0  4568.1    0.04       0  4916.9    0.04       0
  4920.9    0.04       0
Bank Sta=4916.9,4920.9
Exp/Cntr=0.3,0.1

Chan Stop Cuts=-1