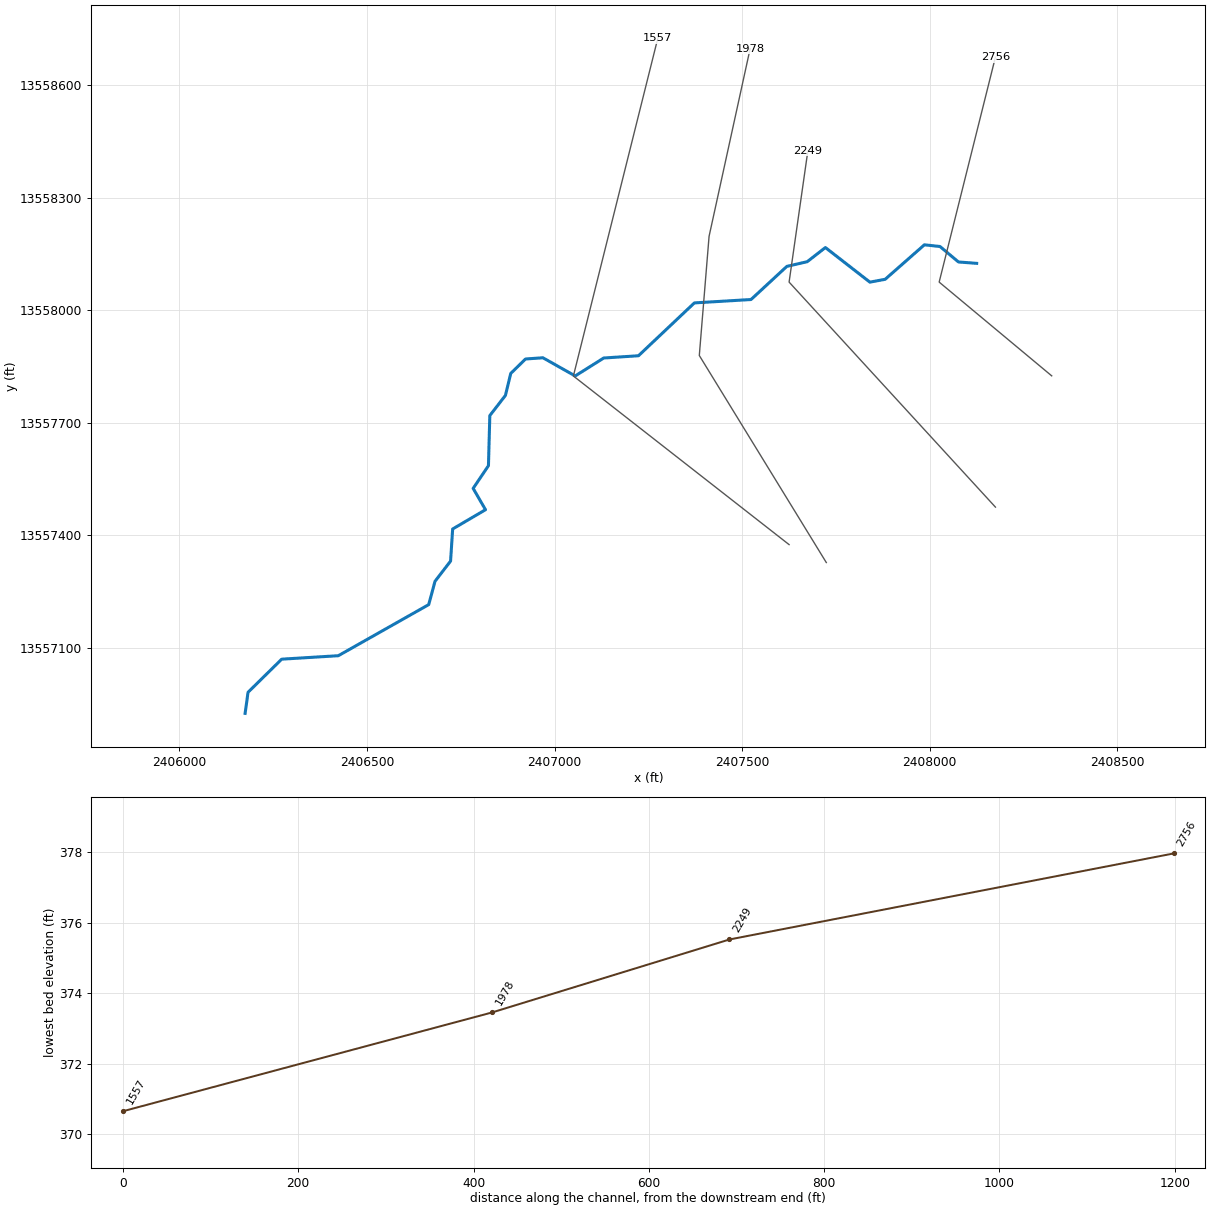
--- TRIB 5_1 TO THOMAS CREEK.prj (project) ---

Proj Title=TRIB 5_1 TO THOMAS CREEK Base Level Engineering
Current Plan=p01
Default Exp/Contr=0.3,0.1
English Units
Geom File=g01
Flow File=f01
Plan File=p01
BEGIN DESCRIPTION:
TRIB 5_1 TO THOMAS CREEK
END DESCRIPTION:

--- TRIB 5_1 TO THOMAS CREEK.p01 (plan) ---

Plan Title=Multiple Run
Short Identifier=Multiple
Geom File=g01
Flow File=f01
Subcritical Flow
K Sum by GR= 0
Std Step Tol= 0.01
Critical Tol= 0.01
Num of Std Step Trials= 20
Max Error Tol= 0.3
Flow Tol Ratio= 0.001
Split Flow NTrial= 30
Split Flow Tol= 0.02
Split Flow Ratio= 0.02
Log Output Level= 0
Friction Slope Method= 1
Unsteady Friction Slope Method= 2
Unsteady Bridges Friction Slope Method= 1
Parabolic Critical Depth
Global Vel Dist=  1 , 1 , 1
Global Log Level= 0
CheckData=True
Encroach Param= -1, 0, 0, 0
BEGIN DESCRIPTION:
Multiple Run
END DESCRIPTION:

--- TRIB 5_1 TO THOMAS CREEK.f01 (steady flow) ---

Flow Title=Multiple
Number of Profiles=7
Profile Names=10-year,25-year,50-year,1pct_min,100-year,1pct_plu,500-year
River Rch & RM= TRIB 5_1 TO THOM,Reach-1,2756
     416     665     887     575    1147    2289    1898
Boundary for River Rch & Prof#=TRIB 5_1 TO THOM,Reach-1,1
Up Type=0
Dn Type=3
Dn Slope=0.005
Boundary for River Rch & Prof#=TRIB 5_1 TO THOM,Reach-1,2
Up Type=0
Dn Type=3
Dn Slope=0.005
Boundary for River Rch & Prof#=TRIB 5_1 TO THOM,Reach-1,3
Up Type=0
Dn Type=3
Dn Slope=0.005
Boundary for River Rch & Prof#=TRIB 5_1 TO THOM,Reach-1,4
Up Type=0
Dn Type=3
Dn Slope=0.005
Boundary for River Rch & Prof#=TRIB 5_1 TO THOM,Reach-1,5
Up Type=0
Dn Type=3
Dn Slope=0.005
Boundary for River Rch & Prof#=TRIB 5_1 TO THOM,Reach-1,6
Up Type=0
Dn Type=3
Dn Slope=0.005
Boundary for River Rch & Prof#=TRIB 5_1 TO THOM,Reach-1,7
Up Type=0
Dn Type=3
Dn Slope=0.005

--- TRIB 5_1 TO THOMAS CREEK.g01 (geometry) ---

Geom Title=Existing Conditions

River Reach=TRIB 5_1 TO THOM,Reach-1
Reach XY= 30
      2408125.00     13558125.00      2408076.49     13558128.69
      2408027.24     13558169.91      2407985.61     13558174.43
      2407881.04     13558082.48      2407840.36     13558074.90
      2407721.77     13558167.16      2407673.35     13558129.46
      2407618.96     13558116.86      2407523.53     13558028.55
      2407372.55     13558019.53      2407223.50     13557878.61
      2407130.97     13557872.62      2407054.82     13557824.72
      2406968.84     13557873.21      2406922.45     13557870.01
      2406883.02     13557831.43      2406868.85     13557772.86
      2406827.25     13557719.07      2406823.61     13557585.44
      2406782.81     13557524.89      2406815.77     13557468.07
      2406728.21     13557416.66      2406722.63     13557331.05
      2406681.15     13557277.15      2406664.37     13557215.00
      2406423.44     13557078.76      2406272.53     13557069.55
      2406182.75     13556981.24      2406175.00     13556925.00

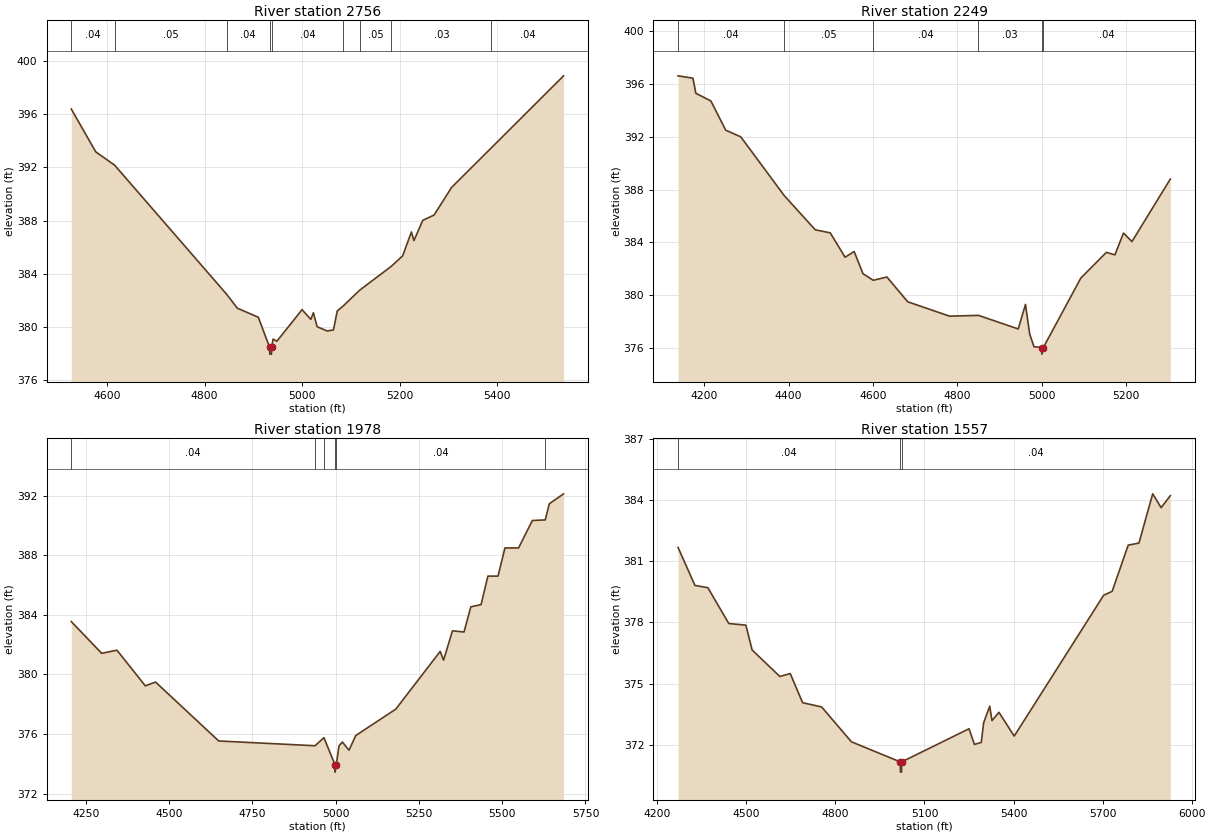
Type RM Length L Ch R = 1,2756,507,507,507
BEGIN DESCRIPTION:
TRIB 5 TO THOMAS CREEK 5.0
END DESCRIPTION:
XS GIS Cut Line= 3
      2408325.00     13557825.00      2408025.00     13558075.00
      2408175.00     13558675.02
#Sta/Elev= 30
  4526.6  396.38  4576.7  393.16  4615.4  392.16  4844.8  382.47  4867.0  381.41
  4910.0  380.73  4933.2  378.46  4933.4  377.96  4936.9  377.96  4937.2  378.46
  4940.3  379.09  4948.0  378.93  4999.6  381.30  5017.6  380.57  5022.8  381.07
  5030.5  380.02  5051.1  379.70  5064.0  379.78  5071.7  381.20  5084.3  381.59
  5117.6  382.76  5182.9  384.57  5205.7  385.34  5223.8  387.14  5228.9  386.49
  5247.0  388.01  5270.2  388.41  5306.2  390.49  5387.6  393.46  5535.6  398.87
#Mann=9,-1,0
  4526.6    0.04       0  4615.4    0.05       0  4844.8    0.04       0
  4933.2    0.04       0  4937.2    0.04       0  5084.3    0.03       0
  5117.6    0.05       0  5182.9    0.03       0  5387.6    0.04       0
Bank Sta=4933.2,4937.2
Exp/Cntr=0.3,0.1

Type RM Length L Ch R = 1,2249,271,271,271
BEGIN DESCRIPTION:
TRIB 5 TO THOMAS CREEK 4.0
END DESCRIPTION:
XS GIS Cut Line= 3
      2408174.98     13557475.02      2407625.00     13558075.00
      2407675.00     13558425.03
#Sta/Elev= 30
  4137.9  396.63  4173.3  396.45  4180.1  395.31  4215.9  394.72  4251.0  392.51
  4286.8  392.00  4389.4  387.56  4463.4  384.95  4498.9  384.72  4534.1  382.87
  4555.6  383.30  4576.6  381.62  4600.9  381.12  4633.3  381.37  4682.7  379.49
  4781.9  378.40  4850.4  378.46  4944.7  377.43  4961.9  379.29  4972.0  377.03
  4982.1  376.08  5000.3  376.02  5000.6  375.52  5004.3  376.02  5093.2  381.29
  5153.8  383.24  5174.0  383.05  5194.3  384.70  5214.5  384.06  5305.4  388.80
#Mann=6,-1,0
  4137.9    0.04       0  4389.4    0.05       0  4600.9    0.04       0
  4850.4    0.03       0  5000.3    0.03       0  5004.3    0.04       0
Bank Sta=5000.3,5004.3
Exp/Cntr=0.3,0.1

Type RM Length L Ch R = 1,1978,421,421,421
BEGIN DESCRIPTION:
TRIB 5 TO THOMAS CREEK 3.0
END DESCRIPTION:
XS GIS Cut Line= 4
      2407724.19     13557327.18      2407385.64     13557879.28
      2407411.68     13558196.99      2407521.04     13558696.95
#Sta/Elev= 30
  4206.0  383.55  4297.3  381.42  4343.1  381.63  4428.3  379.24  4459.2  379.49
  4648.7  375.54  4937.9  375.22  4964.6  375.76  4997.8  373.95  4998.1  373.45
  5001.8  373.95  5009.9  375.21  5019.9  375.47  5040.0  374.92  5060.0  375.90
  5180.6  377.68  5313.7  381.55  5323.9  380.96  5350.6  382.93  5385.3  382.85
  5405.8  384.54  5436.5  384.69  5457.0  386.60  5487.4  386.60  5508.2  388.49
  5549.1  388.49  5590.5  390.33  5629.2  390.37  5641.3  391.45  5684.2  392.12
#Mann=6,-1,0
  4206.0    0.04       0  4937.9    0.03       0  4964.6    0.04       0
  4997.8    0.04       0  5001.8    0.04       0  5629.2    0.05       0
Bank Sta=4997.8,5001.8
Exp/Cntr=0.3,0.1

Type RM Length L Ch R = 1,1557,0,0,0
BEGIN DESCRIPTION:
TRIB 5 TO THOMAS CREEK 2.0
END DESCRIPTION:
XS GIS Cut Line= 3
      2407624.99     13557375.01      2407050.00     13557824.61
      2407275.00     13558725.02
#Sta/Elev= 30
  4270.1  381.69  4327.1  379.82  4370.5  379.71  4441.0  377.95  4498.6  377.87
  4519.7  376.65  4612.8  375.35  4648.1  375.49  4689.7  374.06  4753.9  373.85
  4854.0  372.14  5019.0  371.15  5019.3  370.65  5022.8  370.65  5023.0  371.15
  5250.2  372.78  5268.4  372.01  5291.5  372.11  5299.3  373.07  5319.9  373.89
  5327.5  373.18  5350.9  373.59  5402.4  372.42  5703.8  379.34  5732.2  379.53
  5786.3  381.80  5822.4  381.90  5868.8  384.32  5897.2  383.64  5928.1  384.23
#Mann=3,-1,0
  4270.1    0.04       0  5019.0    0.04       0  5023.0    0.04       0
Bank Sta=5019,5023
Exp/Cntr=0.3,0.1

Chan Stop Cuts=-1