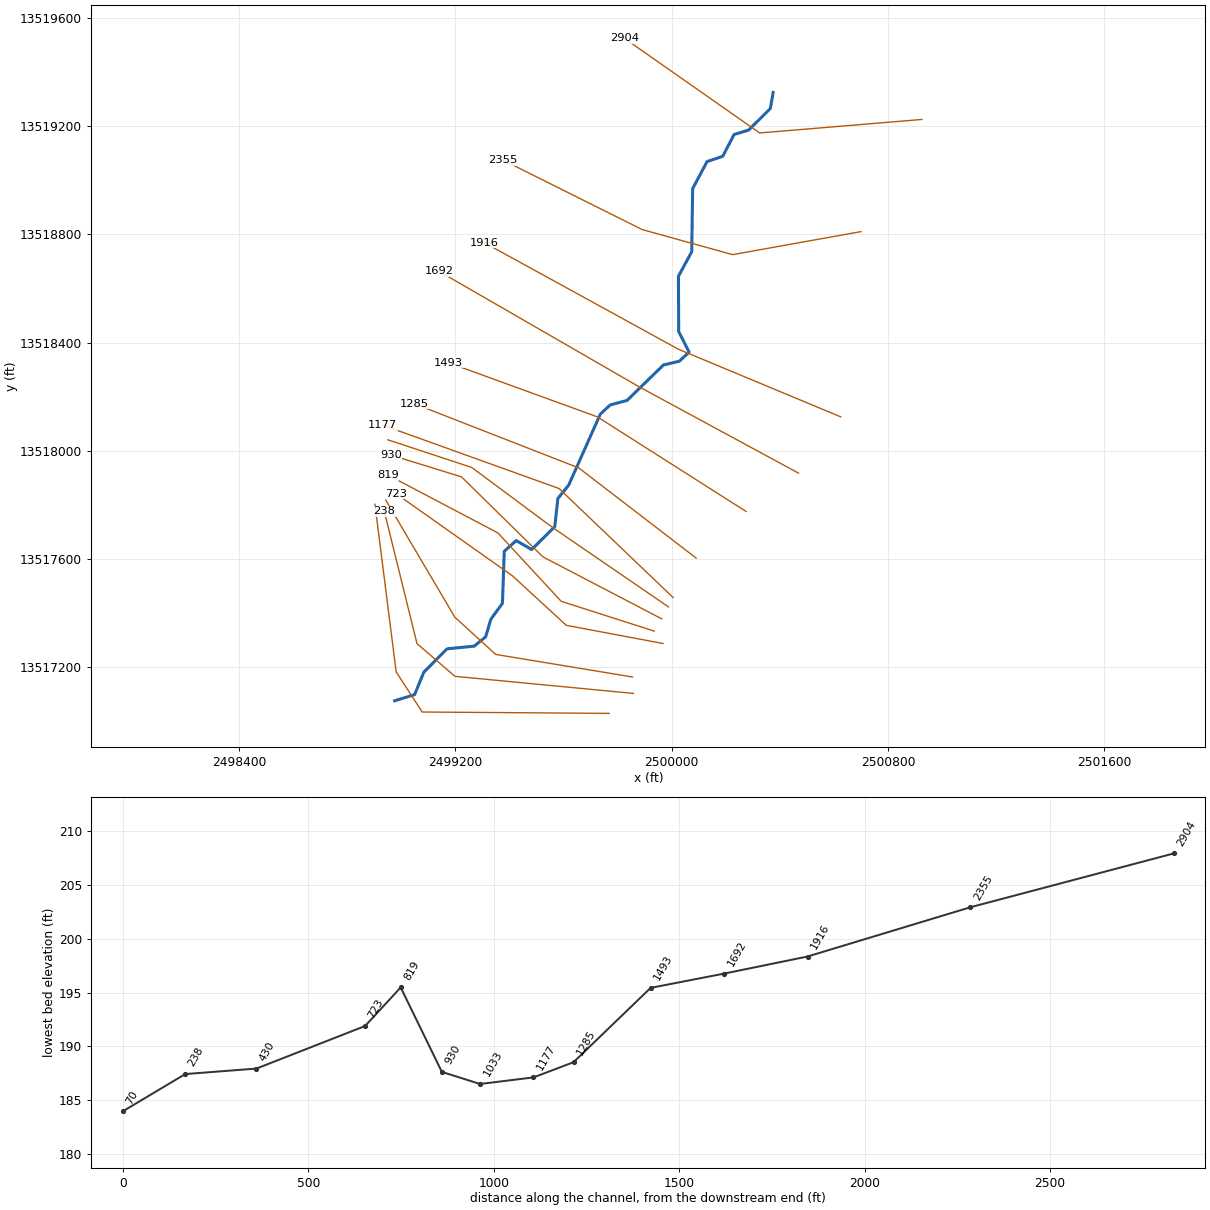
--- TRIB 5_2 TO FIFTEENMILE CREEK.prj (project) ---

Proj Title=TRIB 5_2 TO FIFTEENMILE CREEK Base Level Engineering
Current Plan=p01
Default Exp/Contr=0.3,0.1
English Units
Geom File=g01
Flow File=f01
Plan File=p01
Y Axis Title=Elevation
X Axis Title(PF)=Main Channel Distance
X Axis Title(XS)=Station
BEGIN DESCRIPTION:
TRIB 5_2 TO FIFTEENMILE CREEK
END DESCRIPTION:
DSS Export Rating Curves= 0
DSS Export Rating Curve Sorted= 0
DSS Export Volume Flow Curves= 0
DXF OffsetX= 0
DXF OffsetY= 0
DXF ScaleX= 1
DXF ScaleY= 10

--- TRIB 5_2 TO FIFTEENMILE CREEK.p01 (plan) ---

Plan Title=Multiple Run
Short Identifier=Multiple
Geom File=g01
Flow File=f01
Subcritical Flow
K Sum by GR= 0
Std Step Tol= 0.01
Critical Tol= 0.01
Num of Std Step Trials= 20
Max Error Tol= 0.3
Flow Tol Ratio= 0.001
Split Flow NTrial= 30
Split Flow Tol= 0.02
Split Flow Ratio= 0.02
Log Output Level= 0
Friction Slope Method= 1
Unsteady Friction Slope Method= 2
Unsteady Bridges Friction Slope Method= 1
Parabolic Critical Depth
Global Vel Dist=  1 , 1 , 1
Global Log Level= 0
CheckData=True
Encroach Param= -1, 0, 0, 0
BEGIN DESCRIPTION:
Multiple Run
END DESCRIPTION:

--- TRIB 5_2 TO FIFTEENMILE CREEK.f01 (steady flow) ---

Flow Title=Multiple
Number of Profiles=7
Profile Names=10-year,25-year,50-year,1pct_min,100-year,1pct_plu,500-year
River Rch & RM= TRIB 5_2 TO FIFT,Reach-1,2904
     349     541     708     450     897    1790    1423
Boundary for River Rch & Prof#=TRIB 5_2 TO FIFT,Reach-1,1
Up Type=0
Dn Type=3
Dn Slope=0.005
Boundary for River Rch & Prof#=TRIB 5_2 TO FIFT,Reach-1,2
Up Type=0
Dn Type=3
Dn Slope=0.005
Boundary for River Rch & Prof#=TRIB 5_2 TO FIFT,Reach-1,3
Up Type=0
Dn Type=3
Dn Slope=0.005
Boundary for River Rch & Prof#=TRIB 5_2 TO FIFT,Reach-1,4
Up Type=0
Dn Type=3
Dn Slope=0.005
Boundary for River Rch & Prof#=TRIB 5_2 TO FIFT,Reach-1,5
Up Type=0
Dn Type=3
Dn Slope=0.005
Boundary for River Rch & Prof#=TRIB 5_2 TO FIFT,Reach-1,6
Up Type=0
Dn Type=3
Dn Slope=0.005
Boundary for River Rch & Prof#=TRIB 5_2 TO FIFT,Reach-1,7
Up Type=0
Dn Type=3
Dn Slope=0.005

--- TRIB 5_2 TO FIFTEENMILE CREEK.g01 (geometry) ---

Geom Title=Existing Conditions
Program Version=4.10

River Reach=TRIB 5_2 TO FIFT,Reach-1
Reach XY= 30
        2500375.       13519325.      2500364.49     13519265.18
      2500284.43     13519185.87      2500230.63     13519169.35
      2500188.31     13519088.65      2500130.62     13519069.38
      2500077.23      13518969.1      2500073.78      13518735.5
      2500024.64     13518645.15      2500025.67     13518440.15
      2500064.03     13518364.62      2500027.85     13518330.85
      2499968.99     13518316.84      2499834.66     13518185.79
      2499772.46     13518169.25      2499735.63       13518135.
      2499618.88     13517872.82      2499578.83     13517823.41
      2499567.14     13517718.79      2499481.68      13517634.3
      2499424.76     13517667.54      2499380.46       13517628.
       2499373.8      13517435.5      2499331.15     13517377.14
      2499311.55     13517311.37      2499269.29     13517277.08
      2499168.81     13517267.14      2499083.14     13517181.06
      2499048.98     13517097.82        2498975.       13517075.

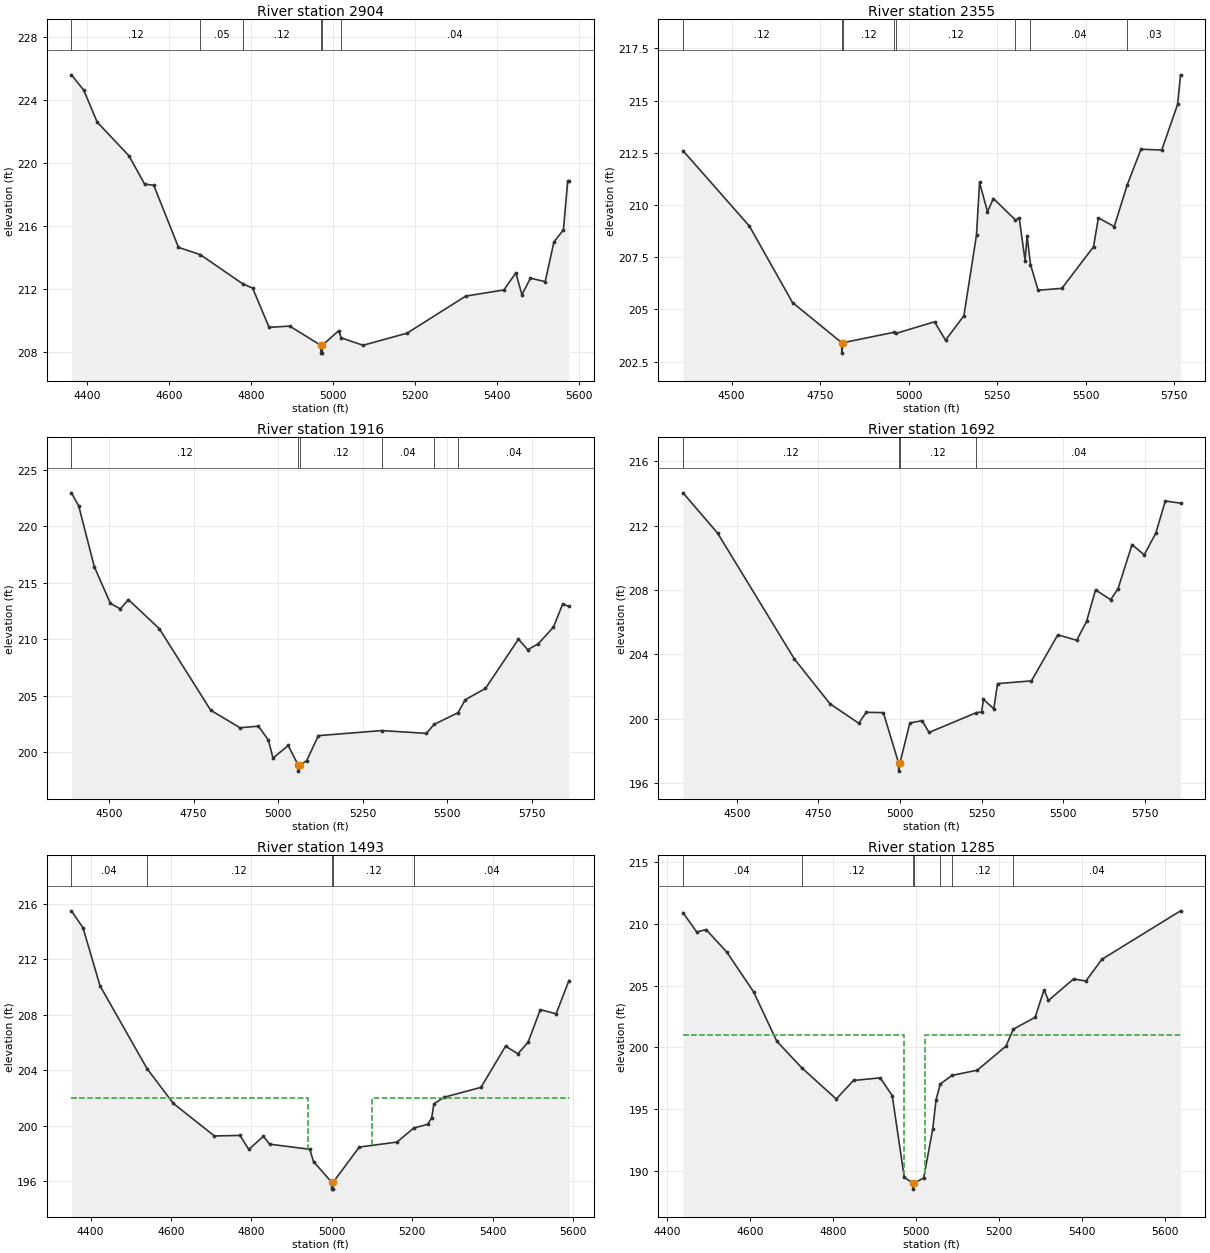
Type RM Length L Ch R = 1 ,2904    ,549,549,549
BEGIN DESCRIPTION:
TRIB 5_2 TO FIFTEENMILE CREEK 6.0
END DESCRIPTION:
XS GIS Cut Line= 3
      2500925.04       13519225.        2500325.       13519175.
      2499825.04     13519524.97
#Sta/Elev= 30
  4362.1  225.62  4392.2  224.64  4424.9  222.61  4502.6  220.46  4540.3  218.67
  4562.8  218.59    4623  214.64    4676  214.18  4779.5  212.32  4803.7  212.05
  4843.8  209.55    4894  209.63  4969.6  208.41  4969.9  207.91  4973.4  207.91
  4973.6  208.41  5013.5  209.34  5019.5  208.88  5072.8  208.41    5180  209.18
    5323  211.54  5415.9  211.93  5445.1  213.01  5459.9  211.63  5480.8  212.68
  5516.6  212.46  5537.9  214.99    5561  215.75  5571.5  218.87  5574.5  218.87
#Mann= 6 ,-1 , 0
  4362.1     .12       0    4676     .05       0  4779.5     .12       0
  4969.6     .05       0  4973.6     .12       0  5019.5     .04       0
Bank Sta=4969.6,4973.6
XS Rating Curve= 0 ,0
Exp/Cntr=0.3,0.1

Type RM Length L Ch R = 1 ,2355    ,439,439,439
BEGIN DESCRIPTION:
TRIB 5_2 TO FIFTEENMILE CREEK 5.0
END DESCRIPTION:
XS GIS Cut Line= 4
      2500699.52     13518810.13        2500225.       13518725.
      2499890.67     13518817.69      2499375.04     13519074.98
#Sta/Elev= 30
  4362.7   212.6  4550.2  208.99  4672.1  205.33  4810.9  203.41  4811.1  202.91
  4814.9  203.41  4959.6  203.91  4965.2  203.86  5073.1  204.41  5104.2  203.53
  5156.1   204.7  5191.7  208.57  5200.3  211.08  5222.7  209.68  5239.5  210.31
  5301.7  209.28  5312.2  209.39  5328.9  207.34  5334.5  208.53  5344.2  207.15
  5365.7  205.92  5432.8  206.01  5522.2     208  5535.9  209.38  5580.7  208.97
  5617.8  210.98  5656.3  212.67  5714.9  212.63  5759.6  214.81    5768  216.23
#Mann= 8 ,-1 , 0
  4362.7     .12       0  4810.9     .05       0  4814.9     .12       0
  4959.6     .05       0  4965.2     .12       0  5301.7     .05       0
  5344.2     .04       0  5617.8     .03       0
Bank Sta=4810.9,4814.9
XS Rating Curve= 0 ,0
Exp/Cntr=0.3,0.1

Type RM Length L Ch R = 1 ,1916    ,224,224,224
BEGIN DESCRIPTION:
TRIB 5_2 TO FIFTEENMILE CREEK 4.0
END DESCRIPTION:
XS GIS Cut Line= 3
      2500624.96     13518125.02        2500025.       13518375.
      2499305.69     13518769.82
#Sta/Elev= 30
  4388.7  222.97  4410.3  221.81  4456.4  216.43    4504  213.18  4533.3   212.7
  4557.1  213.52  4648.7  210.94  4800.3  203.73    4887  202.18  4941.2  202.32
  4970.9  201.09  4984.5  199.49  5029.4  200.61  5059.5  198.84  5059.7  198.34
  5063.5  198.84  5084.3  199.28  5118.5  201.48  5306.1  201.93  5437.9  201.68
  5460.3  202.47  5531.3  203.51  5552.8  204.66  5612.5  205.66    5710  210.02
  5737.5  209.08  5768.7  209.62  5813.3  211.08  5840.8  213.14  5859.2  212.91
#Mann= 6 ,-1 , 0
  4388.7     .12       0  5059.5     .05       0  5063.5     .12       0
  5306.1     .04       0  5460.3     .12       0  5531.3     .04       0
Bank Sta=5059.5,5063.5
XS Rating Curve= 0 ,0
Exp/Cntr=0.3,0.1

Type RM Length L Ch R = 1 ,1692    ,199,199,199
BEGIN DESCRIPTION:
Mapping XS adce556a
END DESCRIPTION:
XS GIS Cut Line= 3
      2500468.63     13517917.03      2499881.82     13518234.74
      2499139.38     13518663.21
#Sta/Elev= 30
    4335  214.03    4441  211.53  4675.9  203.73  4785.3  200.94  4873.6  199.73
  4896.3  200.41  4948.9  200.39  4995.6  197.26  4995.9  196.76  4999.6  197.26
  5030.2  199.75  5067.5  199.89    5089  199.16  5234.1  200.39  5249.9  200.43
  5255.6  201.21  5287.2  200.63  5298.8  202.19  5402.7  202.36  5483.5  205.22
  5541.3  204.88  5571.6  206.05    5599  208.01  5645.2   207.4  5667.8  208.07
  5710.9  210.82  5748.2  210.18  5783.7  211.53  5812.8  213.52  5859.5  213.39
#Mann= 4 ,-1 , 0
    4335     .12       0  4995.6     .05       0  4999.6     .12       0
  5234.1     .04       0
Bank Sta=4995.6,4999.6
XS Rating Curve= 0 ,0
Exp/Cntr=0.3,0.1

Type RM Length L Ch R = 1 ,1493    ,208,208,208
BEGIN DESCRIPTION:
TRIB 5_2 TO FIFTEENMILE CREEK 3.0
END DESCRIPTION:
XS GIS Cut Line= 3
      2500275.02     13517774.99        2499725.       13518125.
      2499174.98     13518325.01
#Sta/Elev= 30
  4352.3  215.48  4381.1  214.26  4423.4  210.08  4540.4  204.11  4605.5  201.61
  4707.9  199.26  4771.4   199.3  4793.4  198.29  4829.8  199.24  4845.1  198.67
    4945   198.3  4954.3  197.42  4999.3  195.93  4999.5  195.43    5003  195.43
  5003.3  195.93  5068.1  198.46  5161.9  198.82  5203.5  199.83  5238.3   200.1
  5248.3  200.58  5253.6  201.57  5278.9  202.05  5370.7  202.76  5431.9  205.73
  5462.5  205.18  5487.7     206  5518.3  208.36  5557.6  208.06  5589.5  210.46
#Mann= 5 ,-1 , 0
  4352.3     .04       0  4540.4     .12       0  4999.3     .04       0
  5003.3     .12       0  5203.5     .04       0
#XS Ineff= 2 , 0
       0    4940     202    5100       0     202
Permanent Ineff=
       F       F
Bank Sta=4999.3,5003.3
XS Rating Curve= 0 ,0
Exp/Cntr=0.3,0.1

Type RM Length L Ch R = 1 ,1285    ,108,108,108
BEGIN DESCRIPTION:
Mapping XS 88882726
END DESCRIPTION:
XS GIS Cut Line= 3
      2500090.14     13517602.81      2499656.13     13517936.13
      2499048.42     13518173.33
#Sta/Elev= 30
  4437.7  210.89  4470.8  209.33  4493.5  209.52  4543.4   207.7  4607.7   204.5
  4663.9  200.49  4723.5  198.36  4807.1  195.82  4848.8  197.32  4913.1  197.53
  4942.1   196.1  4971.2  189.49  4991.6  189.03  4991.8  188.53  4995.6  189.03
    5018  189.43  5039.8  193.39  5047.9  195.76  5057.9  197.03  5086.3  197.73
  5147.2  198.15  5216.3  200.09  5233.9  201.46  5286.7  202.43  5308.2  204.65
  5318.9  203.79  5379.3  205.53  5409.1  205.36  5447.7  207.12  5637.3  211.04
#Mann= 7 ,-1 , 0
  4437.7     .04       0  4723.5     .12       0  4991.6     .04       0
  4995.6     .12       0  5057.9     .05       0  5086.3     .12       0
  5233.9     .04       0
#XS Ineff= 2 , 0
       0    4970     201    5020       0     201
Permanent Ineff=
       F       F
Bank Sta=4991.6,4995.6
XS Rating Curve= 0 ,0
Exp/Cntr=0.3,0.1

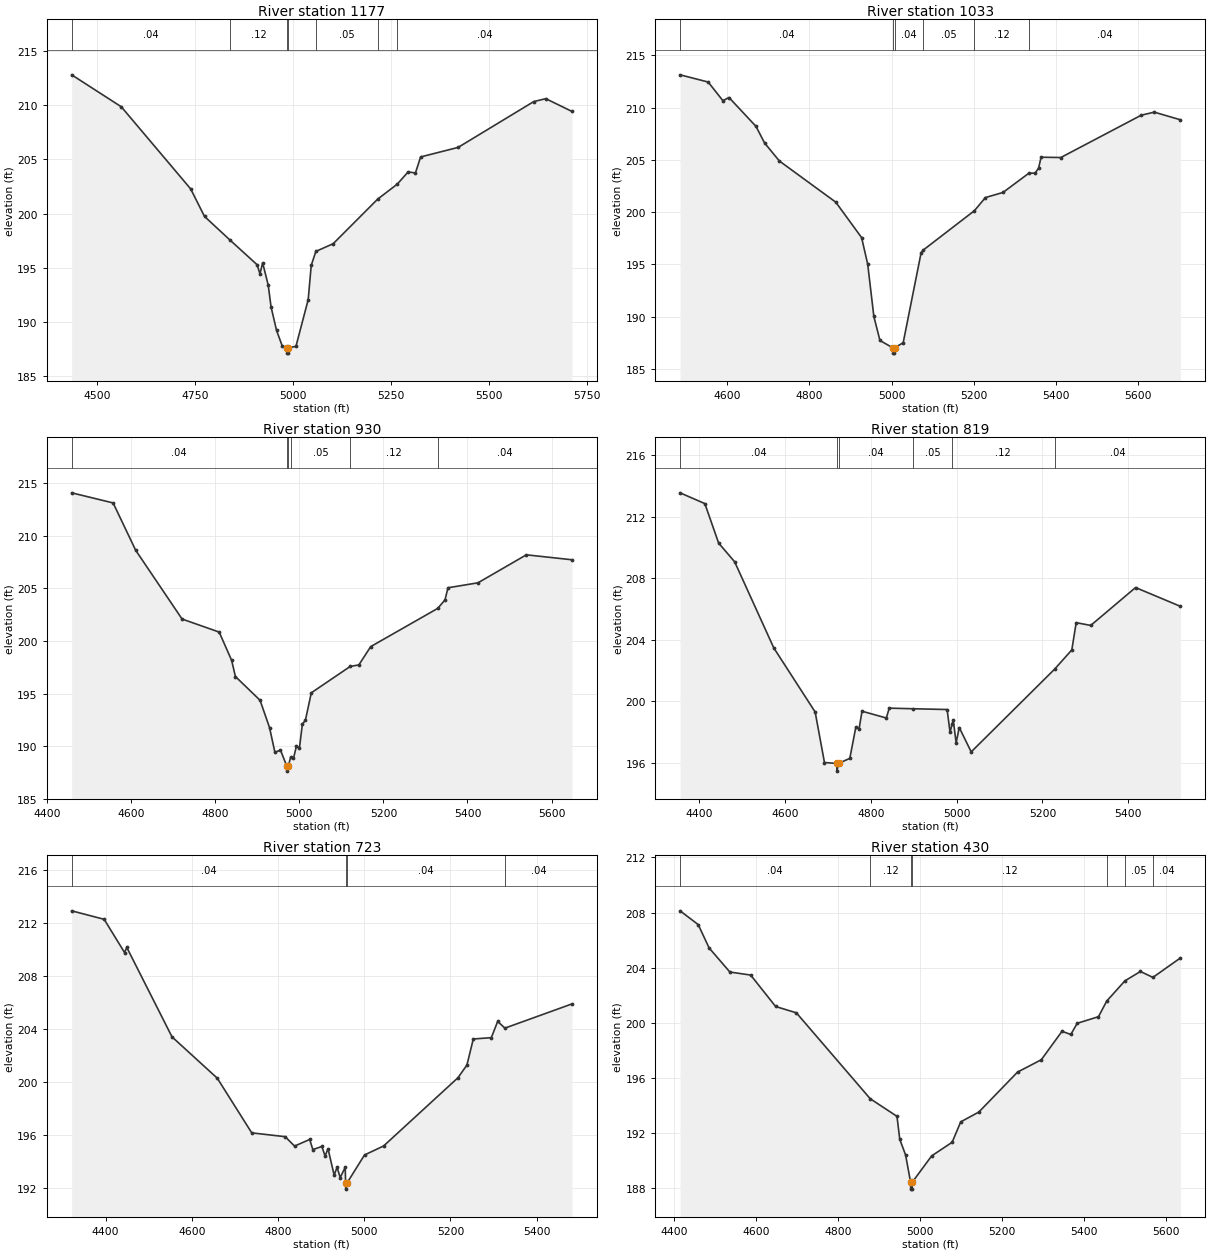
Type RM Length L Ch R = 1 ,1177    ,144,144,144
BEGIN DESCRIPTION:
Mapping XS 4e3200f9
END DESCRIPTION:
XS GIS Cut Line= 3
      2500005.48     13517456.37      2499582.92      13517860.1
      2498931.56     13518094.26
#Sta/Elev= 30
  4434.8  212.81  4561.4  209.86  4738.4  202.28  4773.7  199.74  4838.7  197.56
  4907.9  195.28  4915.2  194.44  4922.1  195.45  4936.3   193.4  4943.5  191.39
  4957.6  189.21  4971.8  187.81    4984  187.62  4984.2  187.12  4987.7  187.12
    4988  187.62    5007  187.74  5038.3  192.06    5046  195.21  5057.8  196.51
    5102  197.22  5215.7  201.34  5265.6  202.72  5293.3  203.85  5311.9  203.75
  5325.2  205.23  5420.8  206.11  5613.8  210.34  5644.5  210.61  5711.4  209.43
#Mann= 7 ,-1 , 0
  4434.8     .04       0  4838.7     .12       0    4984     .04       0
    4988     .12       0  5057.8     .05       0  5215.7     .12       0
  5265.6     .04       0
Bank Sta=4984,4988
XS Rating Curve= 0 ,0
Exp/Cntr=0.3,0.1

Type RM Length L Ch R = 1 ,1033    ,103,103,103
BEGIN DESCRIPTION:
Mapping XS 2fbcf4d7
END DESCRIPTION:
XS GIS Cut Line= 4
      2499987.71     13517422.25      2499557.17     13517717.38
      2499260.29     13517937.87      2498950.19     13518040.08
#Sta/Elev= 30
  4485.1  213.13  4553.5  212.44  4589.3  210.66  4604.2  210.96  4669.9   208.2
  4690.9  206.61  4726.8  204.89  4864.2  200.95  4927.1  197.56    4942  195.01
  4956.9  190.02  4971.8  187.72  5003.4  187.01  5003.6  186.51  5007.1  186.51
  5007.4  187.01  5028.4  187.51  5072.1  196.13  5076.9  196.36    5202  200.14
  5228.6  201.39  5271.4  201.88  5334.5  203.72  5349.6  203.73    5358   204.2
  5364.2  205.25  5412.2  205.22  5608.1  209.27  5639.8  209.56  5703.4  208.83
#Mann= 6 ,-1 , 0
  4485.1     .04       0  5003.4     .04       0  5007.4     .04       0
  5076.9     .05       0    5202     .12       0  5334.5     .04       0
Bank Sta=5003.4,5007.4
XS Rating Curve= 0 ,0
Exp/Cntr=0.3,0.1

Type RM Length L Ch R = 1 ,930     ,111,111,111
BEGIN DESCRIPTION:
Mapping XS a324e566
END DESCRIPTION:
XS GIS Cut Line= 4
      2499962.46      13517378.3      2499523.71      13517607.1
      2499222.26     13517903.16       2498961.2      13517983.9
#Sta/Elev= 30
  4458.1  214.07  4556.7  213.11  4610.3  208.62  4720.8  202.08  4809.1  200.84
  4838.7  198.16  4847.7  196.62  4906.4  194.36  4928.9  191.77  4941.7  189.42
    4955  189.63  4969.7  188.13    4970  187.63  4973.7  188.13  4979.3  188.96
  4985.9  188.83    4993  190.02    5000  189.79  5007.2  192.12  5014.2  192.44
  5028.3  195.07  5121.1  197.58  5141.5  197.72  5169.7  199.46  5329.2  203.09
  5346.5   203.9  5353.6  205.05  5424.9  205.52  5540.1  208.18  5648.7  207.71
#Mann= 6 ,-1 , 0
  4458.1     .04       0  4969.7     .05       0  4973.7     .04       0
  4979.3     .05       0  5121.1     .12       0  5329.2     .04       0
Bank Sta=4969.7,4973.7
XS Rating Curve= 0 ,0
Exp/Cntr=0.3,0.1

Type RM Length L Ch R = 1 ,819     ,96,96,96
BEGIN DESCRIPTION:
Mapping XS a1389d31
END DESCRIPTION:
XS GIS Cut Line= 4
      2499935.46     13517332.58      2499590.99     13517442.91
      2499356.84     13517695.91      2498950.07       13517910.
#Sta/Elev= 30
  4355.5  213.54  4413.2  212.84  4445.3  210.28  4482.7  209.06  4573.9  203.47
  4670.3  199.31    4692  196.03  4720.8  195.97    4721  195.47  4724.8  195.97
  4751.1   196.3  4765.3  198.35  4772.6   198.2  4779.5  199.36  4836.2  198.92
    4843  199.56  4898.5  199.52  4977.9  199.47  4984.7  197.99  4989.5  198.52
  4992.1   198.8  4998.9  197.31  5006.2   198.3    5034  196.72  5228.4  202.09
  5268.5  203.34  5278.7  205.11  5312.6  204.93  5417.1  207.39  5521.6  206.17
#Mann= 6 ,-1 , 0
  4355.5     .04       0  4720.8     .05       0  4724.8     .04       0
  4898.5     .05       0  4989.5     .12       0  5228.4     .04       0
Bank Sta=4720.8,4724.8
XS Rating Curve= 0 ,0
Exp/Cntr=0.3,0.1

Type RM Length L Ch R = 1 ,723     ,293,293,293
BEGIN DESCRIPTION:
Mapping XS 8b209e7d
END DESCRIPTION:
XS GIS Cut Line= 4
      2499967.81     13517286.81      2499609.84      13517354.1
      2499410.66     13517537.12      2498980.88     13517840.65
#Sta/Elev= 30
  4321.2  212.91  4396.5  212.27  4443.9  209.76    4449  210.15    4554  203.39
    4659  200.27    4739  196.14  4816.7  195.85  4838.3  195.14  4873.4  195.64
  4880.8  194.88  4901.8  195.11  4909.2  194.39    4916  194.94  4930.2  192.95
    4937  193.54  4944.3  192.76  4955.9  193.54  4956.8  192.39  4957.1  191.89
  4960.8  192.39  5000.7  194.47    5045  195.15  5217.4   200.3  5238.3  201.26
  5253.1  203.23  5294.9  203.33  5309.7  204.56  5326.4  204.05  5482.1  205.88
#Mann= 4 ,-1 , 0
  4321.2     .04       0  4956.8     .05       0  4960.8     .04       0
  5326.4     .04       0
Bank Sta=4956.8,4960.8
XS Rating Curve= 0 ,0
Exp/Cntr=0.3,0.1

Type RM Length L Ch R = 1 ,430     ,192,192,192
BEGIN DESCRIPTION:
Mapping XS 7977db2f
END DESCRIPTION:
XS GIS Cut Line= 4
      2499854.76       13517163.      2499348.76     13517246.44
      2499198.04      13517383.7      2498942.36       13517817.
#Sta/Elev= 30
  4415.5  208.13  4459.7  207.13  4486.2  205.44  4536.9  203.69  4587.6  203.47
  4648.4  201.19    4699  200.73    4879   194.5  4944.3  193.22  4951.1  191.55
  4965.3  190.42  4977.5  188.44  4977.7  187.94  4981.2  187.94  4981.5  188.44
  5028.8  190.35  5078.8  191.34  5099.7  192.82  5143.8  193.53  5238.2  196.43
  5296.3  197.33  5346.6  199.39  5368.1  199.16  5383.7  199.97  5435.6  200.45
  5455.6  201.58    5500  203.05  5537.9  203.73  5568.2   203.3  5635.3  204.71
#Mann= 7 ,-1 , 0
  4415.5     .04       0    4879     .12       0  4977.5     .05       0
  4981.5     .12       0  5455.6     .04       0    5500     .05       0
  5568.2     .04       0
Bank Sta=4977.5,4981.5
XS Rating Curve= 0 ,0
Exp/Cntr=0.3,0.1

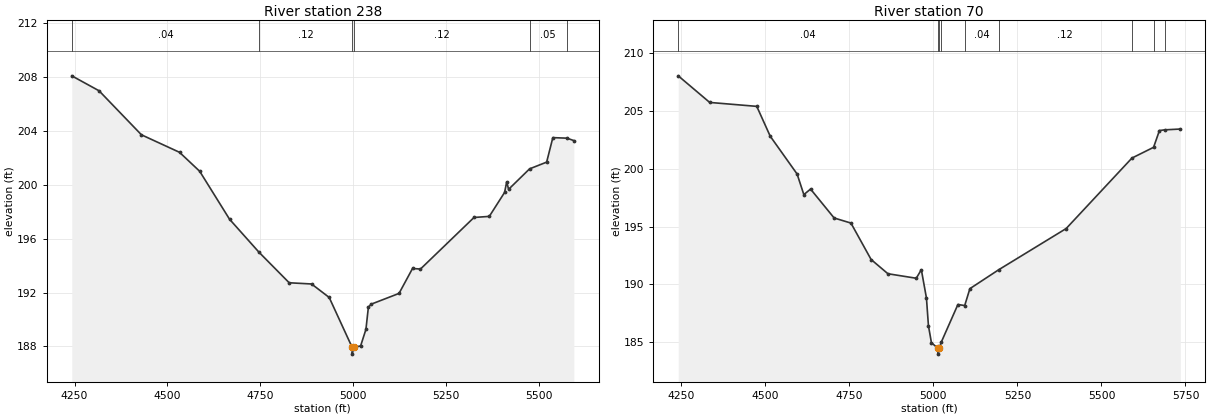
Type RM Length L Ch R = 1 ,238     ,168,168,168
BEGIN DESCRIPTION:
Mapping XS 65bd0e04
END DESCRIPTION:
XS GIS Cut Line= 4
      2499858.16     13517102.22        2499198.     13517165.49
      2499057.72     13517286.52      2498936.69     13517776.13
#Sta/Elev= 30
  4242.4   208.1  4315.9  206.99  4430.1  203.72  4532.7  202.42  4587.1  201.01
  4667.5  197.45  4746.8     195  4828.2  192.73  4888.5  192.64    4936  191.64
  4997.9  187.93  4998.1  187.43  5001.9  187.93  5020.7  188.04    5035  189.27
  5041.6  190.92  5049.2  191.14  5124.2  191.94  5160.5  193.79    5182  193.75
  5326.2  197.58  5367.4  197.66  5408.6  199.44  5414.3  200.23  5419.4  199.67
  5475.9  201.19  5521.9  201.69  5538.6  203.51  5576.7  203.47  5595.2  203.29
#Mann= 6 ,-1 , 0
  4242.4     .04       0  4746.8     .12       0  4997.9     .05       0
  5001.9     .12       0  5475.9     .05       0  5576.7     .04       0
Bank Sta=4997.9,5001.9
XS Rating Curve= 0 ,0
Exp/Cntr=0.3,0.1

Type RM Length L Ch R = 1 ,70      ,0,0,0
BEGIN DESCRIPTION:
Mapping XS 14a46889
END DESCRIPTION:
XS GIS Cut Line= 4
      2499768.64     13517028.43      2499076.98     13517033.46
       2498980.7     13517181.99       2498902.2     13517801.75
#Sta/Elev= 30
  4241.2  208.04  4334.8  205.74  4474.8   205.4  4514.8  202.82  4594.8  199.55
  4614.8  197.77  4634.8  198.25  4704.9  195.75  4754.9  195.31  4814.9  192.16
  4864.9  190.93  4949.2  190.54  4964.3  191.28  4979.5  188.83  4985.4  186.44
  4994.3  184.97  5013.7  184.48    5014  183.98  5017.7  184.48  5023.2  184.99
  5073.1  188.27  5093.3  188.18  5108.7  189.64  5194.7  191.28  5395.2  194.84
  5590.7  200.93  5655.1  201.86  5672.5  203.31  5688.1  203.37  5734.6  203.44
#Mann= 9 ,-1 , 0
  4241.2     .04       0  5013.7     .04       0  5017.7     .04       0
  5023.2     .12       0  5093.3     .04       0  5194.7     .12       0
  5590.7     .05       0  5655.1     .12       0  5688.1     .05       0
Bank Sta=5013.7,5017.7
XS Rating Curve= 0 ,0
Exp/Cntr=0.3,0.1

Chan Stop Cuts=-1
Use User Specified Reach Order=0
Composite Channel Slope=5