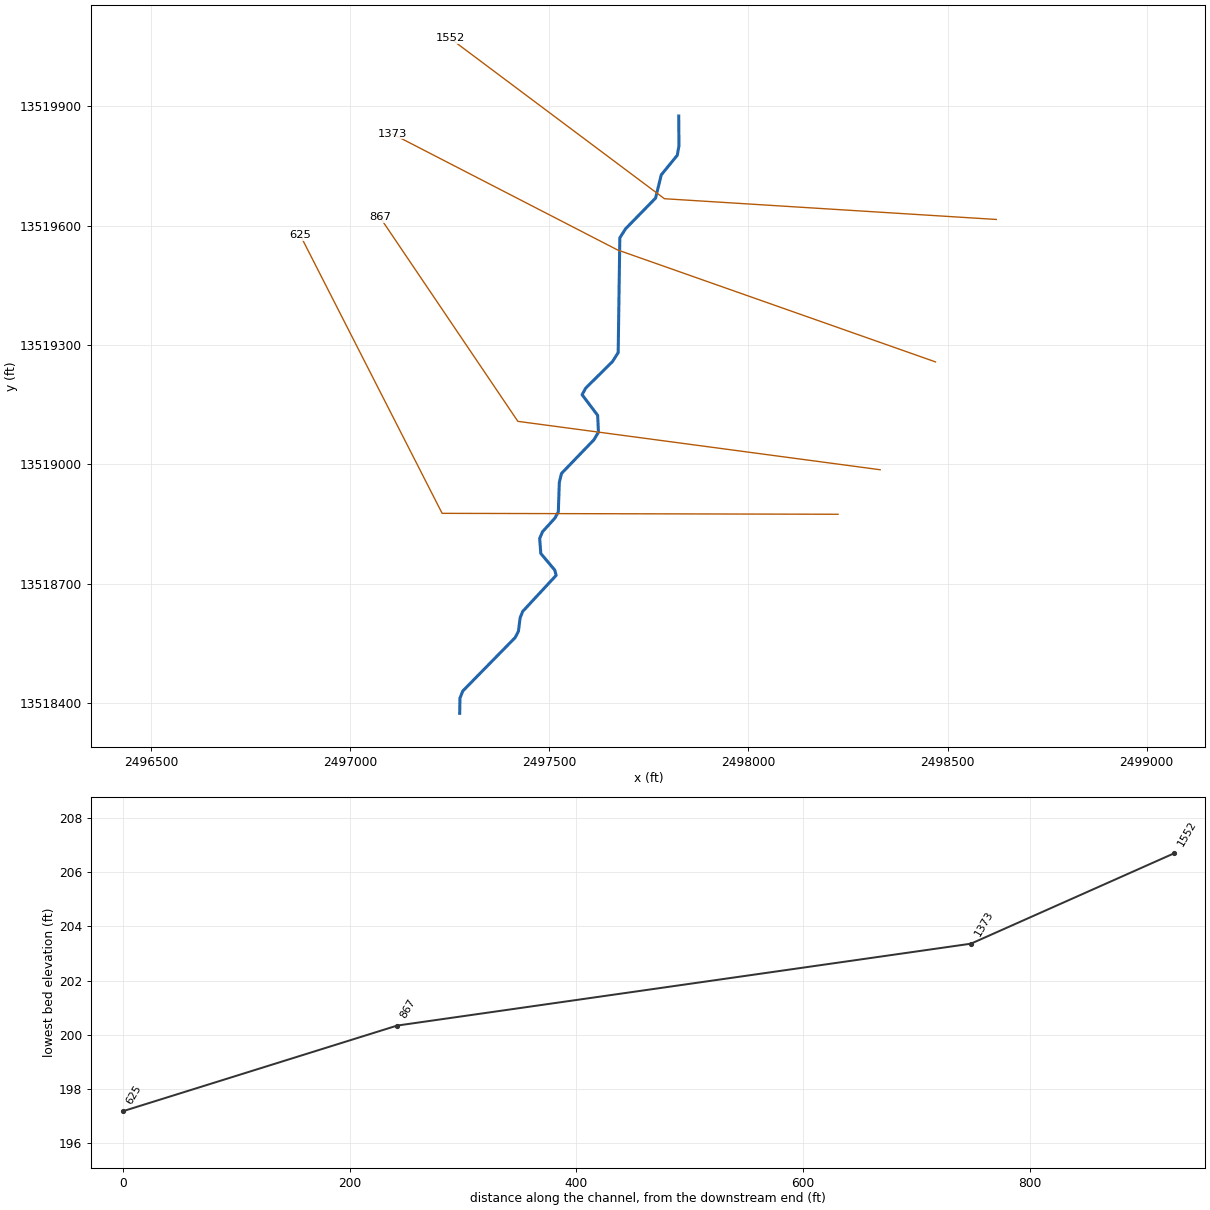
--- TRIB 5_3 TO FIFTEENMILE CREEK.prj (project) ---

Proj Title=TRIB 5_3 TO FIFTEENMILE CREEK Base Level Engineering
Current Plan=p01
Default Exp/Contr=0.3,0.1
English Units
Geom File=g01
Flow File=f01
Plan File=p01
BEGIN DESCRIPTION:
TRIB 5_3 TO FIFTEENMILE CREEK
END DESCRIPTION:

--- TRIB 5_3 TO FIFTEENMILE CREEK.p01 (plan) ---

Plan Title=Multiple Run
Short Identifier=Multiple
Geom File=g01
Flow File=f01
Subcritical Flow
K Sum by GR= 0
Std Step Tol= 0.01
Critical Tol= 0.01
Num of Std Step Trials= 20
Max Error Tol= 0.3
Flow Tol Ratio= 0.001
Split Flow NTrial= 30
Split Flow Tol= 0.02
Split Flow Ratio= 0.02
Log Output Level= 0
Friction Slope Method= 1
Unsteady Friction Slope Method= 2
Unsteady Bridges Friction Slope Method= 1
Parabolic Critical Depth
Global Vel Dist=  1 , 1 , 1
Global Log Level= 0
CheckData=True
Encroach Param= -1, 0, 0, 0
BEGIN DESCRIPTION:
Multiple Run
END DESCRIPTION:

--- TRIB 5_3 TO FIFTEENMILE CREEK.f01 (steady flow) ---

Flow Title=Multiple
Number of Profiles=7
Profile Names=10-year,25-year,50-year,1pct_min,100-year,1pct_plu,500-year
River Rch & RM= TRIB 5_3 TO FIFT,Reach-1,1552
     275     419     541     340     678    1354    1051
Boundary for River Rch & Prof#=TRIB 5_3 TO FIFT,Reach-1,1
Up Type=0
Dn Type=3
Dn Slope=0.005
Boundary for River Rch & Prof#=TRIB 5_3 TO FIFT,Reach-1,2
Up Type=0
Dn Type=3
Dn Slope=0.005
Boundary for River Rch & Prof#=TRIB 5_3 TO FIFT,Reach-1,3
Up Type=0
Dn Type=3
Dn Slope=0.005
Boundary for River Rch & Prof#=TRIB 5_3 TO FIFT,Reach-1,4
Up Type=0
Dn Type=3
Dn Slope=0.005
Boundary for River Rch & Prof#=TRIB 5_3 TO FIFT,Reach-1,5
Up Type=0
Dn Type=3
Dn Slope=0.005
Boundary for River Rch & Prof#=TRIB 5_3 TO FIFT,Reach-1,6
Up Type=0
Dn Type=3
Dn Slope=0.005
Boundary for River Rch & Prof#=TRIB 5_3 TO FIFT,Reach-1,7
Up Type=0
Dn Type=3
Dn Slope=0.005

--- TRIB 5_3 TO FIFTEENMILE CREEK.g01 (geometry) ---

Geom Title=Existing Conditions

River Reach=TRIB 5_3 TO FIFT,Reach-1
Reach XY= 30
      2497825.00     13519875.00      2497825.48     13519799.80
      2497821.37     13519776.50      2497781.11     13519727.18
      2497766.84     13519668.95      2497691.46     13519591.75
      2497677.06     13519569.14      2497672.93     13519280.85
      2497658.50     13519258.24      2497591.34     13519191.69
      2497582.36     13519175.08      2497621.41     13519123.35
      2497623.33     13519081.05      2497611.84     13519061.80
      2497530.54     13518977.42      2497525.13     13518954.95
      2497522.62     13518880.97      2497514.05     13518865.35
      2497482.83     13518830.91      2497475.82     13518814.29
      2497478.62     13518776.63      2497513.61     13518734.87
      2497517.17     13518721.60      2497433.20     13518631.05
      2497426.56     13518614.36      2497422.47     13518581.05
      2497414.22     13518565.32      2497282.76     13518431.21
      2497275.59     13518413.16      2497275.00     13518375.00

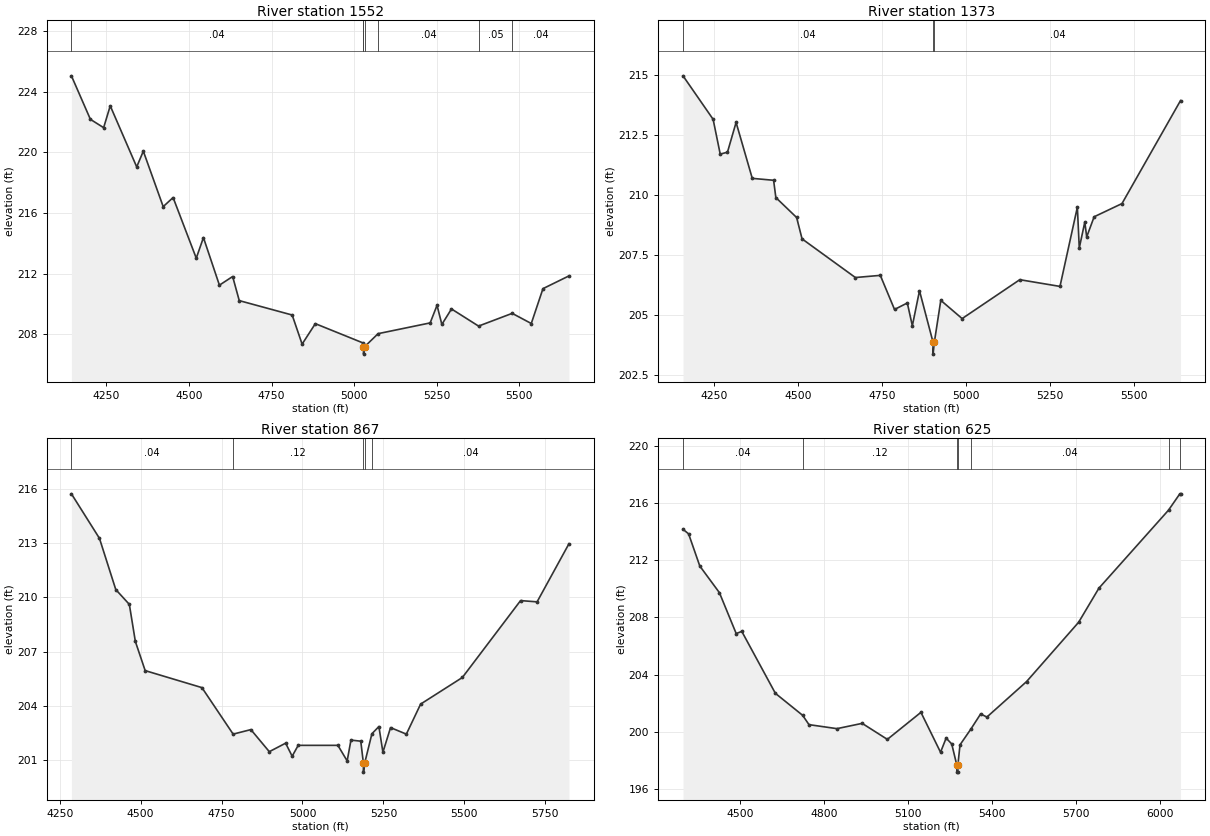
Type RM Length L Ch R = 1,1552,179,179,179
BEGIN DESCRIPTION:
Mapping XS 84885bcf
END DESCRIPTION:
XS GIS Cut Line= 3
      2498622.42     13519615.26      2497789.10     13519667.34
      2497250.96     13520070.08
#Sta/Elev= 30
  4143.9  225.05  4201.4  222.18  4241.5  221.63  4261.5  223.07  4341.7  219.04
  4361.7  220.08  4421.9  216.42  4451.9  217.02  4522.1  213.02  4543.8  214.38
  4592.2  211.24  4632.3  211.81  4652.3  210.22  4812.6  209.27  4842.7  207.35
  4882.8  208.70  5025.9  207.44  5028.5  207.19  5028.8  206.69  5032.5  207.19
  5072.9  208.04  5230.6  208.75  5251.4  209.91  5266.0  208.65  5295.2  209.67
  5377.2  208.54  5479.1  209.38  5536.9  208.71  5572.3  211.01  5651.0  211.85
#Mann=7,-1,0
  4143.9    0.04       0  5025.9    0.05       0  5028.5    0.04       0
  5032.5    0.05       0  5072.9    0.04       0  5377.2    0.05       0
  5479.1    0.04       0
Bank Sta=5028.5,5032.5
Exp/Cntr=0.3,0.1

Type RM Length L Ch R = 1,1373,506,506,506
BEGIN DESCRIPTION:
Mapping XS a33625de
END DESCRIPTION:
XS GIS Cut Line= 3
      2498469.65     13519257.62      2497671.04     13519538.87
      2497105.59     13519830.27
#Sta/Elev= 30
  4157.0  214.95  4246.7  213.14  4267.9  211.69  4289.5  211.77  4315.2  213.01
  4363.4  210.68  4427.0  210.60  4433.7  209.88  4495.6  209.05  4511.8  208.16
  4670.7  206.55  4745.0  206.64  4787.4  205.22  4825.5  205.49  4840.5  204.54
  4861.8  206.00  4902.1  203.86  4902.3  203.36  4906.1  203.86  4925.3  205.60
  4988.9  204.84  5160.7  206.46  5280.5  206.18  5332.3  209.48  5338.0  207.78
  5354.5  208.86  5360.1  208.24  5382.3  209.08  5465.3  209.63  5639.8  213.92
#Mann=3,-1,0
  4157.0    0.04       0  4902.1    0.04       0  4906.1    0.04       0
Bank Sta=4902.1,4906.1
Exp/Cntr=0.3,0.1

Type RM Length L Ch R = 1,867,242,242,242
BEGIN DESCRIPTION:
Mapping XS 441c4780
END DESCRIPTION:
XS GIS Cut Line= 3
      2498330.80     13518986.78      2497421.04     13519108.31
      2497074.57     13519621.09
#Sta/Elev= 30
  4286.3  215.72  4372.9  213.26  4423.3  210.43  4465.2  209.61  4483.8  207.56
  4514.1  205.95  4689.4  205.01  4785.8  202.44  4840.6  202.69  4897.5  201.47
  4947.9  201.94  4968.1  201.22  4986.8  201.82  5109.3  201.82  5138.0  200.96
  5149.7  202.11  5180.0  202.05  5188.1  200.84  5188.3  200.34  5192.1  200.84
  5214.4  202.46  5236.0  202.86  5248.4  201.44  5272.0  202.80  5320.8  202.44
  5364.9  204.10  5493.8  205.57  5673.6  209.82  5724.6  209.75  5823.0  212.96
#Mann=5,-1,0
  4286.3    0.04       0  4785.8    0.12       0  5188.1    0.05       0
  5192.1    0.12       0  5214.4    0.04       0
Bank Sta=5188.1,5192.1
Exp/Cntr=0.3,0.1

Type RM Length L Ch R = 1,625,0,0,0
BEGIN DESCRIPTION:
TRIB 5_3 TO FIFTEENMILE CREEK 1.0
END DESCRIPTION:
XS GIS Cut Line= 3
      2498225.02     13518875.00      2497230.86     13518877.29
      2496874.99     13519575.01
#Sta/Elev= 30
  4296.1  214.16  4316.1  213.84  4356.1  211.59  4426.1  209.73  4486.1  206.87
  4506.1  207.02  4626.1  202.69  4723.6  201.15  4746.1  200.50  4846.1  200.22
  4936.1  200.59  5026.1  199.47  5146.1  201.36  5216.1  198.57  5236.1  199.56
  5256.1  199.15  5274.1  197.68  5274.4  197.18  5277.9  197.18  5278.1  197.68
  5285.7  199.09  5324.8  200.20  5359.4  201.25  5381.7  201.03  5523.4  203.51
  5709.5  207.66  5781.8  210.04  6030.6  215.50  6071.0  216.64  6073.5  216.64
#Mann=7,-1,0
  4296.1    0.04       0  4723.6    0.12       0  5274.1    0.05       0
  5278.1    0.12       0  5324.8    0.04       0  6030.6   0.013       0
  6071.0    0.05       0
Bank Sta=5274.1,5278.1
Exp/Cntr=0.3,0.1

Chan Stop Cuts=-1