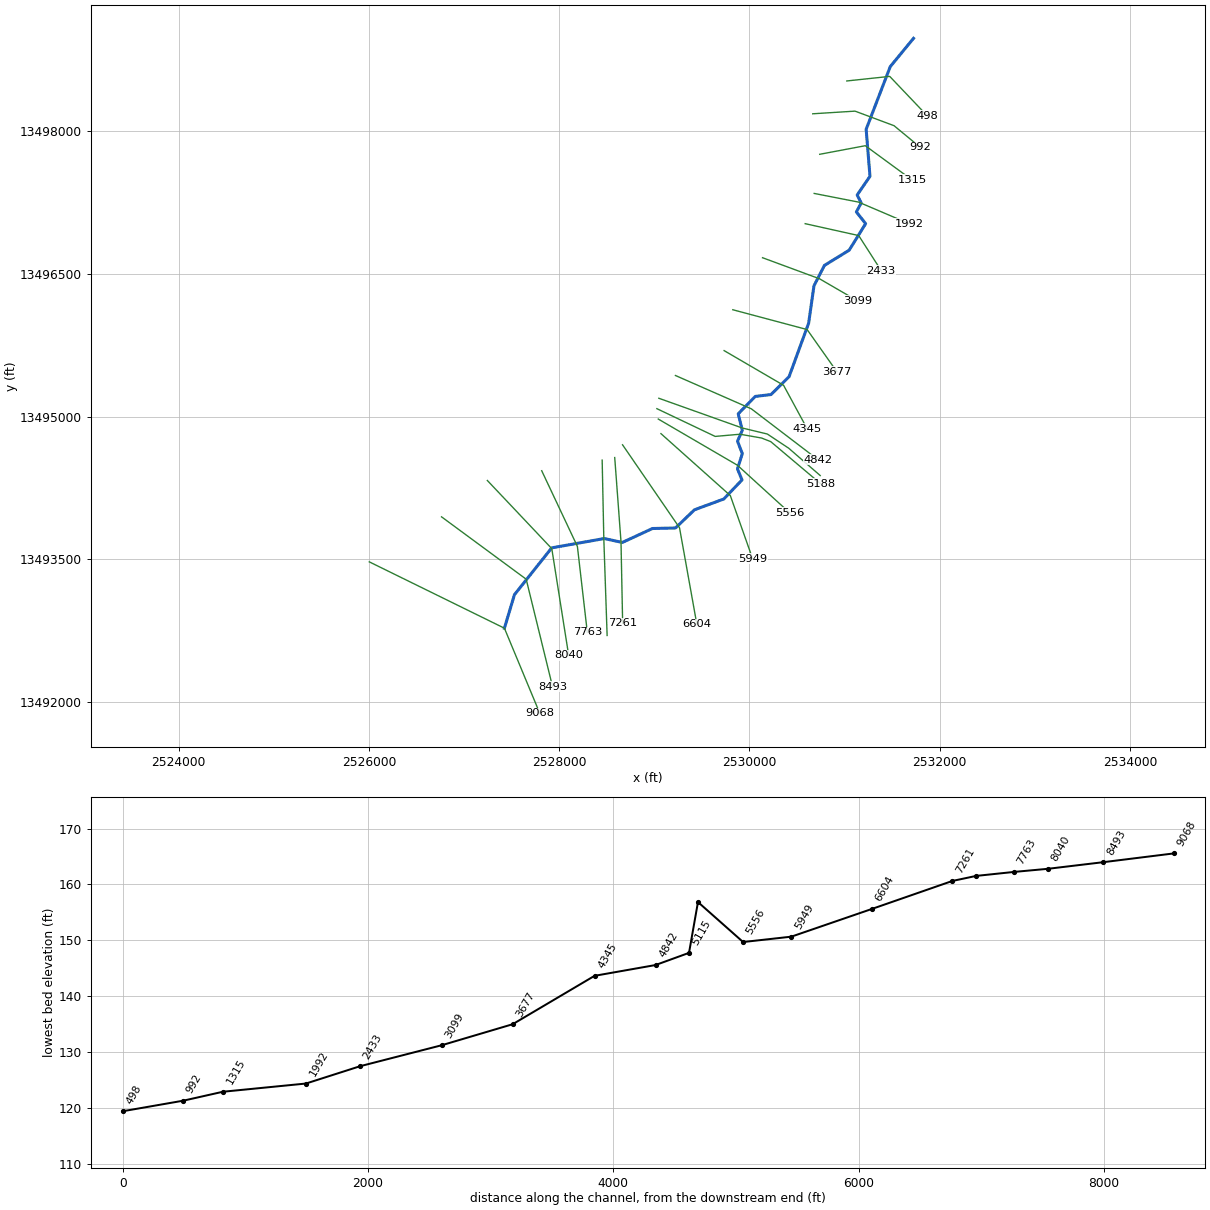
--- TRIB 6 TO COLETO CREEK.prj (project) ---

Proj Title=TRIB 6 TO COLETO CREEK Base Level Engineering
Current Plan=p01
Default Exp/Contr=0.3,0.1
English Units
Geom File=g01
Flow File=f01
Plan File=p01
Y Axis Title=Elevation
X Axis Title(PF)=Main Channel Distance
X Axis Title(XS)=Station
BEGIN DESCRIPTION:
TRIB 6 TO COLETO CREEK
END DESCRIPTION:
DSS Export Rating Curves= 0
DSS Export Rating Curve Sorted= 0
DSS Export Volume Flow Curves= 0
DXF OffsetX= 0
DXF OffsetY= 0
DXF ScaleX= 1
DXF ScaleY= 10

--- TRIB 6 TO COLETO CREEK.p01 (plan) ---

Plan Title=Multiple Run
Short Identifier=Multiple
Geom File=g01
Flow File=f01
Subcritical Flow
K Sum by GR= 0
Std Step Tol= 0.01
Critical Tol= 0.01
Num of Std Step Trials= 20
Max Error Tol= 0.3
Flow Tol Ratio= 0.001
Split Flow NTrial= 30
Split Flow Tol= 0.02
Split Flow Ratio= 0.02
Log Output Level= 0
Friction Slope Method= 1
Unsteady Friction Slope Method= 2
Unsteady Bridges Friction Slope Method= 1
Parabolic Critical Depth
Global Vel Dist=  1 , 1 , 1
Global Log Level= 0
CheckData=True
Encroach Param= -1, 0, 0, 0
BEGIN DESCRIPTION:
Multiple Run
END DESCRIPTION:

--- TRIB 6 TO COLETO CREEK.f01 (steady flow) ---

Flow Title=Multiple
Number of Profiles=7
Profile Names=10-year,25-year,50-year,1pct_min,100-year,1pct_plu,500-year
River Rch & RM= TRIB 6 TO COLETO,Reach-1,9068
     264     394     502     310     618    1233     927
River Rch & RM= TRIB 6 TO COLETO,Reach-1,6604
     441     680     885     558    1114    2222    1741
River Rch & RM= TRIB 6 TO COLETO,Reach-1,4842
     728    1161    1548     998    1990    3971    3255
Boundary for River Rch & Prof#=TRIB 6 TO COLETO,Reach-1,1
Up Type=0
Dn Type=3
Dn Slope=0.005
Boundary for River Rch & Prof#=TRIB 6 TO COLETO,Reach-1,2
Up Type=0
Dn Type=3
Dn Slope=0.005
Boundary for River Rch & Prof#=TRIB 6 TO COLETO,Reach-1,3
Up Type=0
Dn Type=3
Dn Slope=0.005
Boundary for River Rch & Prof#=TRIB 6 TO COLETO,Reach-1,4
Up Type=0
Dn Type=3
Dn Slope=0.005
Boundary for River Rch & Prof#=TRIB 6 TO COLETO,Reach-1,5
Up Type=0
Dn Type=3
Dn Slope=0.005
Boundary for River Rch & Prof#=TRIB 6 TO COLETO,Reach-1,6
Up Type=0
Dn Type=3
Dn Slope=0.005
Boundary for River Rch & Prof#=TRIB 6 TO COLETO,Reach-1,7
Up Type=0
Dn Type=3
Dn Slope=0.005

--- TRIB 6 TO COLETO CREEK.g01 (geometry) ---

Geom Title=Existing Conditions
Program Version=4.10

River Reach=TRIB 6 TO COLETO,Reach-1
Reach XY= 30
        2527425.       13492775.      2527530.52     13493127.43
      2527922.53     13493619.55        2528475.     13493717.44
      2528664.49      13493676.2      2528980.93     13493822.76
      2529223.54     13493828.54      2529422.57     13494019.48
      2529731.07     13494133.13      2529922.35     13494333.49
      2529874.61     13494449.99      2529925.71     13494609.94
      2529875.09     13494740.39      2529925.38     13494854.86
      2529882.79     13495028.42      2530061.66     13495211.35
      2530227.29     13495230.81      2530417.14     13495418.83
      2530622.75     13495980.93      2530678.75     13496373.45
      2530788.61     13496588.24      2531048.73     13496748.11
      2531221.84      13497027.1      2531124.49     13497149.88
      2531175.19      13497245.2      2531132.83      13497328.4
      2531267.47     13497524.99      2531227.26     13498019.06
      2531480.54     13498677.42        2531725.       13498975.

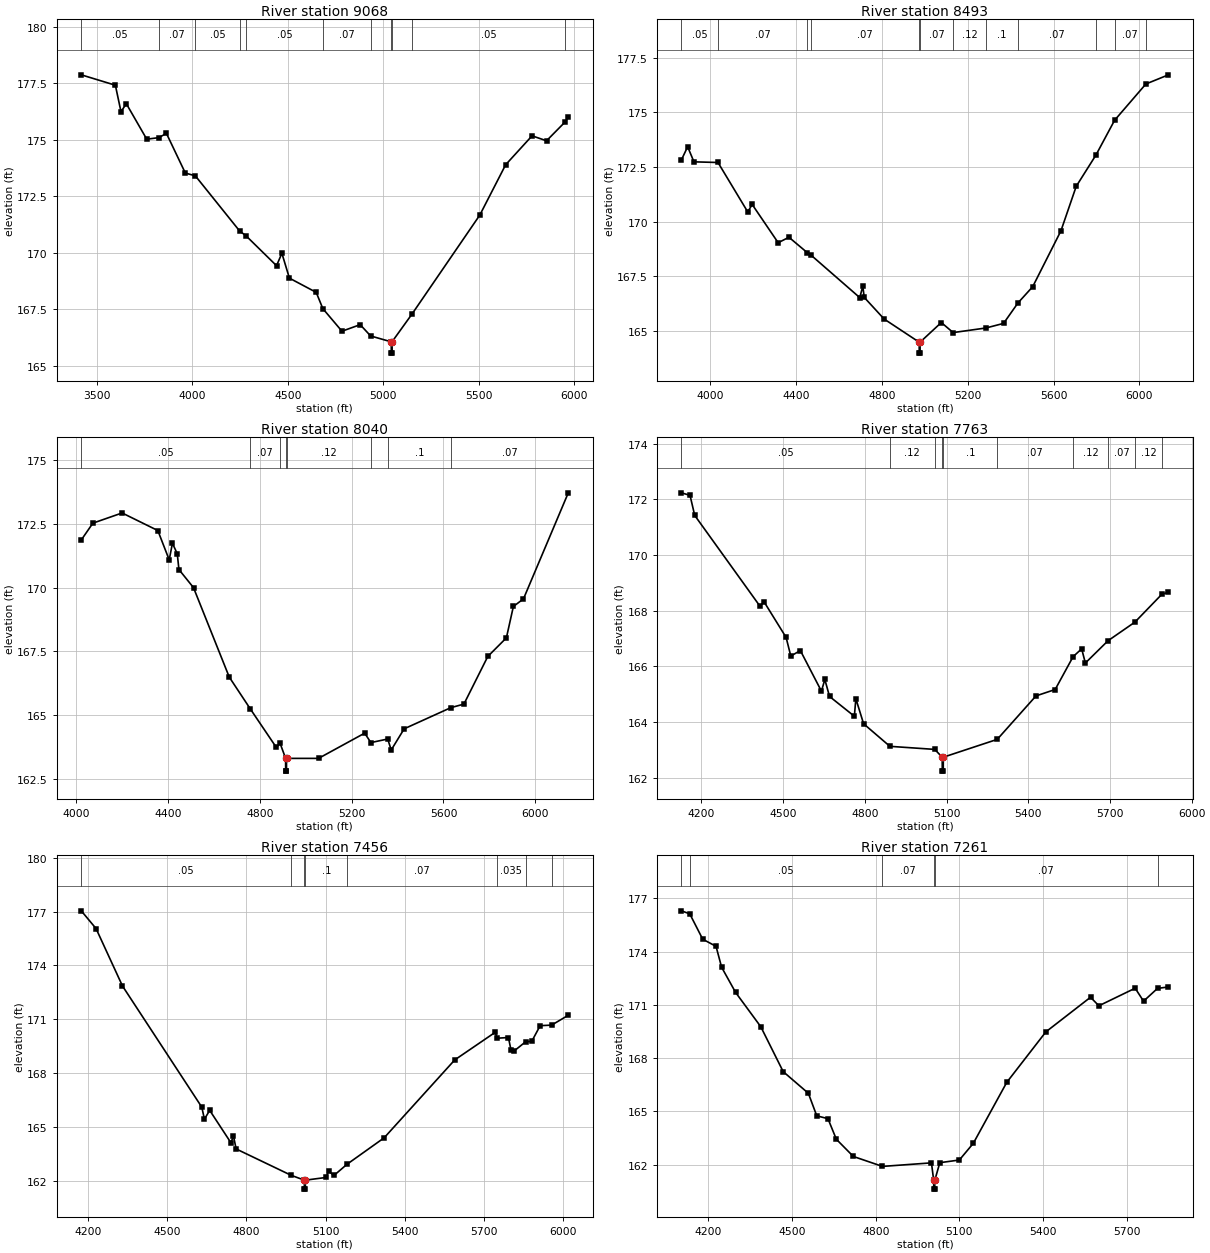
Type RM Length L Ch R = 1 ,9068    ,575,575,575
BEGIN DESCRIPTION:
TRIB 6 TO COLETO CREEK 18.0
END DESCRIPTION:
XS GIS Cut Line= 3
      2526004.59     13493472.44        2527425.       13492775.
      2527797.07     13491879.74
#Sta/Elev= 30
  3417.6  177.88  3596.3  177.42  3625.7  176.25  3653.8   176.6  3760.7  175.03
  3824.3   175.1  3863.7  175.29    3963  173.53  4015.2  173.41  4247.1  170.97
  4281.4  170.75  4440.8  169.43  4468.8  169.98  4508.2  168.88  4648.7  168.25
  4683.4  167.53  4783.6  166.53  4879.1  166.82  4933.9  166.32  5041.9  166.06
  5042.2  165.56  5045.7  165.56  5045.9  166.06  5152.3  167.31  5505.8  171.67
  5641.4   173.9  5779.7  175.18  5855.5  174.96  5953.6   175.8  5969.5  176.02
#Mann= 11 ,-1 , 0
  3417.6     .05       0  3824.3     .07       0  4015.2     .05       0
  4247.1     .07       0  4281.4     .05       0  4683.4     .07       0
  4933.9      .1       0  5041.9     .05       0  5045.9      .1       0
  5152.3     .05       0  5953.6     .07       0
Bank Sta=5041.9,5045.9
XS Rating Curve= 0 ,0
Exp/Cntr=0.3,0.1

Type RM Length L Ch R = 1 ,8493    ,453,453,453
BEGIN DESCRIPTION:
Mapping XS 4487118f
END DESCRIPTION:
XS GIS Cut Line= 3
      2526764.18     13493945.51      2527653.93     13493290.14
      2527931.39     13492158.62
#Sta/Elev= 30
  3865.3  172.83  3894.4  173.43  3923.7  172.74  4035.8  172.71  4174.4  170.45
  4195.2  170.79  4316.3  169.04  4366.5  169.29  4451.5  168.59  4467.4  168.49
  4696.5  166.53  4710.9  167.05  4717.4  166.54  4810.2  165.55  4973.7  164.49
  4973.9  163.99  4977.4  163.99  4977.7  164.49  5076.7  165.39  5131.9  164.93
  5284.7  165.14  5366.9  165.35  5434.4  166.29  5502.8  167.03  5634.6  169.59
  5705.6  171.62  5797.5  173.05  5884.4  174.64  6030.2   176.3  6135.4  176.72
#Mann= 12 ,-1 , 0
  3865.3     .05       0  4035.8     .07       0  4451.5     .05       0
  4467.4     .07       0  4973.7     .05       0  4977.7     .07       0
  5131.9     .12       0  5284.7      .1       0  5434.4     .07       0
  5797.5     .05       0  5884.4     .07       0  6030.2     .05       0
Bank Sta=4973.7,4977.7
XS Rating Curve= 0 ,0
Exp/Cntr=0.3,0.1

Type RM Length L Ch R = 1 ,8040    ,277,277,277
BEGIN DESCRIPTION:
Mapping XS 5d7fee38
END DESCRIPTION:
XS GIS Cut Line= 3
      2527245.91      13494327.5      2527923.02     13493611.32
      2528100.75      13492488.6
#Sta/Elev= 30
  4021.7  171.87  4072.3  172.53  4199.7  172.93  4355.4  172.24  4404.9  171.09
    4419  171.74    4440  171.33  4447.3  170.71  4510.8     170  4666.6  166.49
  4757.7  165.25  4871.7  163.73  4888.2  163.89  4912.2   163.3  4912.4   162.8
  4915.9   162.8  4916.2   163.3  5055.6   163.3  5256.7  164.29  5283.8  163.92
  5357.1  164.06  5372.4  163.63  5428.8  164.46  5632.1  165.29  5689.2  165.43
  5793.3   167.3  5874.3  168.03  5904.7  169.26  5948.8  169.56    6144  173.72
#Mann= 8 ,-1 , 0
  4021.7     .05       0  4757.7     .07       0  4888.2     .12       0
  4912.2     .05       0  4916.2     .12       0  5283.8     .07       0
  5357.1      .1       0  5632.1     .07       0
Bank Sta=4912.2,4916.2
XS Rating Curve= 0 ,0
Exp/Cntr=0.3,0.1

Type RM Length L Ch R = 1 ,7763    ,307,307,307
BEGIN DESCRIPTION:
Mapping XS 79a89a2b
END DESCRIPTION:
XS GIS Cut Line= 3
      2527817.15      13494429.9      2528192.15     13493634.76
      2528296.31     13492731.98
#Sta/Elev= 30
  4126.8  172.23  4158.4  172.14  4175.6  171.42  4414.5  168.17  4430.7  168.31
  4511.1  167.04  4528.4  166.37  4563.4  166.57  4640.8  165.11  4653.3  165.53
  4670.6  164.92  4761.7  164.21  4767.2  164.84  4795.6  163.94  4892.2  163.13
  5056.7  163.02  5084.2  162.74  5084.5  162.24    5088  162.24  5088.2  162.74
  5286.2  163.38  5428.5  164.94  5498.9  165.17  5564.8  166.35  5596.2  166.63
  5609.7  166.12  5692.9  166.92  5791.8  167.59  5890.7  168.59  5914.7  168.66
#Mann= 10 ,-1 , 0
  4126.8     .05       0  4892.2     .12       0  5056.7      .1       0
  5084.2     .05       0  5088.2      .1       0  5286.2     .07       0
  5564.8     .12       0  5692.9     .07       0  5791.8     .12       0
  5890.7     .05       0
Bank Sta=5084.2,5088.2
XS Rating Curve= 0 ,0
Exp/Cntr=0.3,0.1

Type RM Length L Ch R = 1 ,7456    ,195,195,195
BEGIN DESCRIPTION:
Mapping XS dcfdfa6d
END DESCRIPTION:
XS GIS Cut Line= 3
      2528452.56     13494540.98      2528469.92     13493714.62
       2528504.6     13492698.66
#Sta/Elev= 30
    4175  177.04    4231  176.05    4331  172.85  4631.1   166.1  4641.1  165.43
  4661.1  165.92  4741.1  164.12  4751.1  164.48  4761.1  163.77  4969.4   162.3
  5019.2  162.03  5019.4  161.53  5022.9  161.53  5023.2  162.03  5101.2  162.18
  5111.2  162.53  5131.2  162.29  5181.1  162.92  5321.3  164.39  5588.3  168.73
  5741.6  170.27  5748.7  169.94  5791.6  169.98  5801.6  169.26  5811.6  169.21
  5856.5  169.74    5880  169.77  5911.7  170.64    5955  170.67  6018.1  171.22
#Mann= 8 ,-1 , 0
    4175     .05       0  4969.4      .1       0  5019.2     .05       0
  5023.2      .1       0  5181.1     .07       0  5748.7    .035       0
  5856.5     .12       0    5955    .035       0
Bank Sta=5019.2,5023.2
XS Rating Curve= 0 ,0
Exp/Cntr=0.3,0.1

Type RM Length L Ch R = 1 ,7261    ,657,657,657
BEGIN DESCRIPTION:
Mapping XS e28df7f1
END DESCRIPTION:
XS GIS Cut Line= 3
      2528584.51     13494568.75      2528650.48     13493683.37
      2528667.84     13492825.78
#Sta/Elev= 30
  4103.6   176.3  4133.5  176.13    4180   174.7  4227.7   174.3  4247.7  173.12
  4297.9   171.7  4388.1  169.77  4468.4  167.24  4558.6  166.02  4588.7  164.75
  4628.8  164.59  4658.9  163.43  4719.9  162.46  4824.2   161.9  4999.8   162.1
  5007.8  161.12  5008.1  160.62  5011.6  160.62  5011.8  161.12  5029.8  162.11
  5099.8  162.26  5149.8   163.2  5269.9  166.64  5409.9  169.48  5569.9  171.43
  5599.9  170.95    5730  171.94    5760  171.21  5810.1  171.93  5849.2  172.01
#Mann= 6 ,-1 , 0
  4103.6     .12       0  4133.5     .05       0  4824.2     .07       0
  5007.8     .05       0  5011.8     .07       0  5810.1     .12       0
Bank Sta=5007.8,5011.8
XS Rating Curve= 0 ,0
Exp/Cntr=0.3,0.1

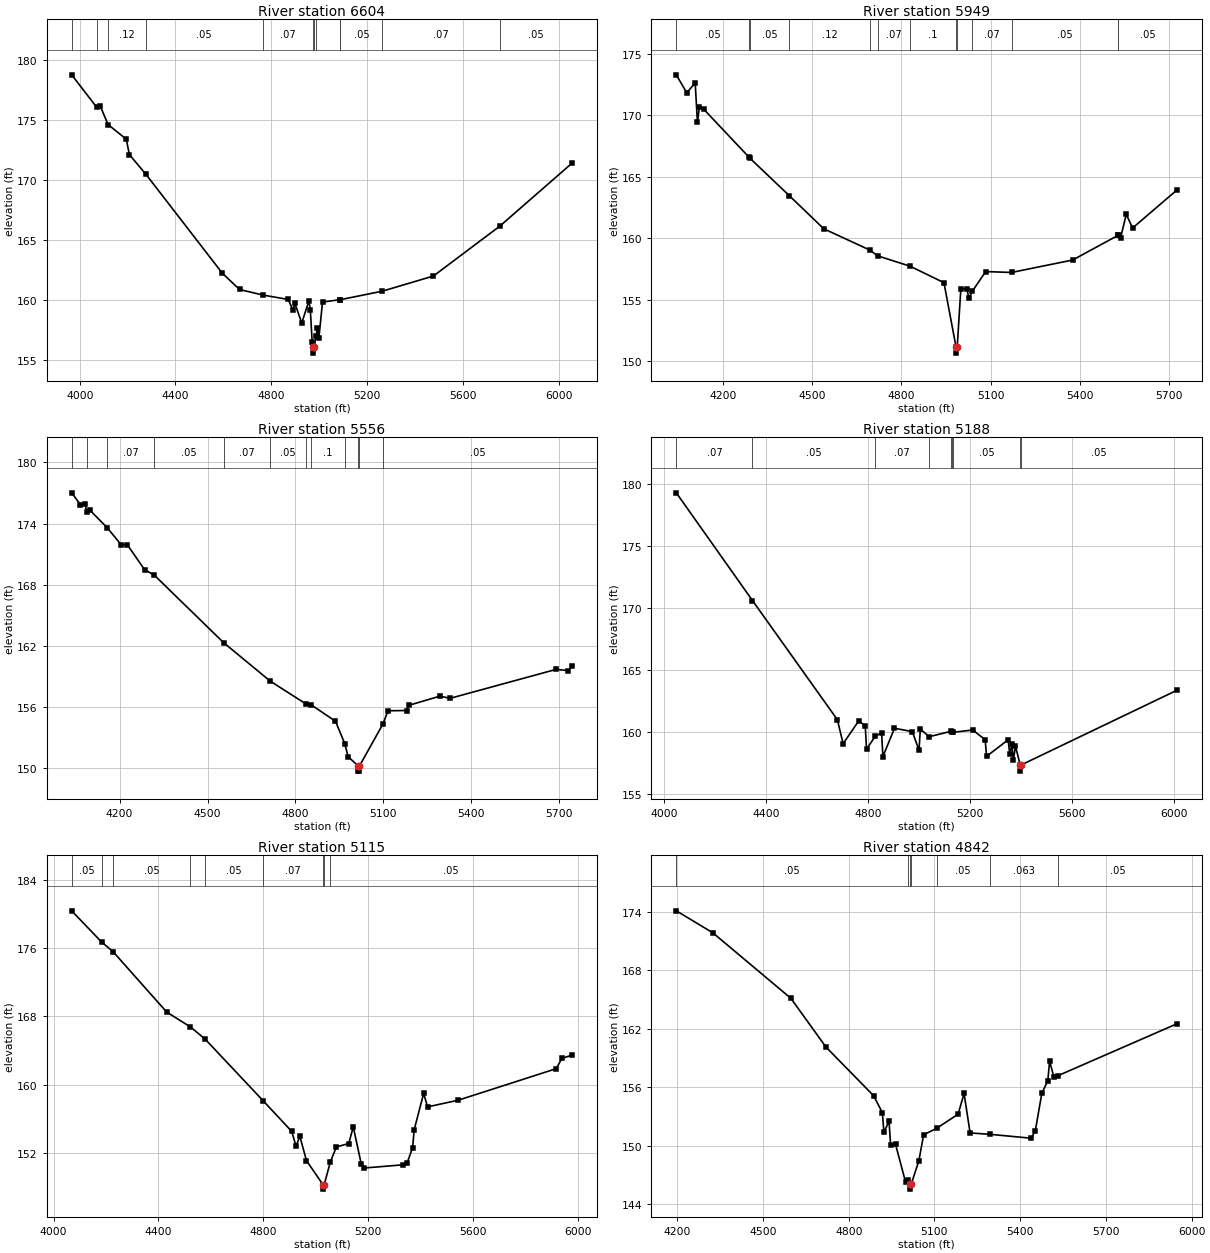
Type RM Length L Ch R = 1 ,6604    ,655,655,655
BEGIN DESCRIPTION:
Mapping XS 6f78cb5c
END DESCRIPTION:
XS GIS Cut Line= 3
      2528666.67     13494703.01      2529265.61     13493830.64
       2529447.9     13492815.06
#Sta/Elev= 30
  3966.5  178.77  4070.3  176.09  4085.4  176.19  4118.4  174.63  4194.6  173.41
  4207.4  172.13  4276.5  170.49  4595.8  162.25  4667.6   160.9  4763.7  160.44
  4870.6  160.07  4891.6  159.16  4898.1  159.77  4927.4  158.11  4957.2  159.94
  4963.3   159.2  4970.9  156.53  4976.2   156.1  4976.4   155.6  4980.2   156.1
  4986.4  156.99  4993.1   157.7  4999.2  156.89  5014.1  159.85  5087.1  160.05
  5088.9  160.05  5264.3  160.76  5477.4  162.02  5754.5  166.17  6056.5  171.42
#Mann= 12 ,-1 , 0
  3966.5     .12       0  4070.3     .05       0  4118.4     .12       0
  4276.5     .05       0  4763.7     .07       0  4976.2     .05       0
  4980.2     .07       0  4986.4      .1       0  5087.1     .07       0
  5088.9     .05       0  5264.3     .07       0  5754.5     .05       0
Bank Sta=4976.2,4980.2
XS Rating Curve= 0 ,0
Exp/Cntr=0.3,0.1

Type RM Length L Ch R = 1 ,5949    ,393,393,393
BEGIN DESCRIPTION:
Mapping XS 4a625467
END DESCRIPTION:
XS GIS Cut Line= 3
       2529070.3     13494820.22      2529799.47     13494169.18
      2530033.83     13493505.15
#Sta/Elev= 30
  4043.5  173.28  4078.6  171.82    4107  172.62  4114.5  169.42  4121.2   170.7
  4135.4  170.49  4288.3  166.57  4289.6  166.53  4423.4  163.45  4539.2  160.76
  4693.8  159.03  4720.2  158.56    4829  157.72    4943  156.38  4983.6  151.15
  4983.9  150.65  4987.6  151.15  4999.8  155.89  5020.4  155.86  5026.7  155.11
  5038.6  155.69  5083.2  157.28  5170.2  157.21  5375.4  158.22  5528.5  160.23
  5528.8  160.25  5536.6  160.02  5555.7  161.94  5576.9  160.82  5725.2   163.9
#Mann= 13 ,-1 , 0
  4043.5     .05       0  4288.3     .07       0  4289.6     .05       0
  4423.4     .12       0  4693.8     .05       0  4720.2     .07       0
    4829      .1       0  4983.6     .05       0  4987.6      .1       0
  5038.6     .07       0  5170.2     .05       0  5528.5     .07       0
  5528.8     .05       0
Bank Sta=4983.6,4987.6
XS Rating Curve= 0 ,0
Exp/Cntr=0.3,0.1

Type RM Length L Ch R = 1 ,5556    ,368,368,368
BEGIN DESCRIPTION:
Mapping XS 574f4fc2
END DESCRIPTION:
XS GIS Cut Line= 3
      2529042.15      13494973.4      2529873.53     13494488.43
      2530424.45     13493986.91
#Sta/Elev= 30
  4036.5  177.02  4065.9  175.87  4081.6  175.92  4088.1  175.17  4097.3  175.36
  4158.4  173.57  4204.8  171.94  4226.3  171.92  4285.1  169.48  4318.2  168.94
  4555.2   162.3  4714.4  158.52  4834.8  156.31  4852.6  156.22  4936.7  154.59
  4968.3  152.39  4979.7  151.11  5014.4  150.19  5014.6  149.69  5018.1  149.69
  5018.4  150.19  5099.2  154.35  5115.7  155.62  5179.2  155.64  5186.7  156.15
  5292.7  157.05  5327.9  156.84  5689.4  159.68  5731.3  159.56    5744  160.04
#Mann= 12 ,-1 , 0
  4036.5     .07       0  4088.1     .05       0  4158.4     .07       0
  4318.2     .05       0  4555.2     .07       0  4714.4     .05       0
  4834.8     .07       0  4852.6      .1       0  4968.3    .033       0
  5014.4    .033       0  5018.4    .033       0  5099.2     .05       0
Bank Sta=5014.4,5018.4
XS Rating Curve= 0 ,0
Exp/Cntr=0.3,0.1

Type RM Length L Ch R = 1 ,5188    ,73,73,73
BEGIN DESCRIPTION:
Mapping XS defccb10
END DESCRIPTION:
XS GIS Cut Line= 6
      2529027.45     13495082.58      2529640.48     13494790.77
      2529900.82     13494813.86      2530127.58     13494773.97
      2530224.15     13494736.18      2530746.96     13494295.26
#Sta/Elev= 30
  4048.9  179.25  4347.6  170.58  4680.5  160.99  4703.1  159.06  4763.4  160.87
  4789.8  160.52  4794.9  158.63  4829.3  159.66    4854  159.94  4859.1  158.02
  4904.5   160.3  4974.5  160.03  5000.6  158.53  5005.9  160.23  5040.6  159.62
  5126.9  160.06  5131.6  159.99  5132.9  159.97    5211  160.16  5260.2  159.38
  5265.5  158.04  5350.2  159.37  5356.7  158.19  5364.5  159.05    5371  157.73
  5378.8  158.86  5397.6  157.35  5397.9  156.85  5401.6  157.35  6011.2  163.35
#Mann= 9 ,-1 , 0
  4048.9     .07       0  4347.6     .05       0  4829.3     .07       0
  5040.6     .05       0  5126.9     .07       0  5131.6    .033       0
  5132.9     .05       0  5397.6     .05       0  5401.6     .05       0
Bank Sta=5397.6,5401.6
XS Rating Curve= 0 ,0
Exp/Cntr=0.3,0.1

Type RM Length L Ch R = 1 ,5115    ,273,273,273
BEGIN DESCRIPTION:
Mapping XS 68bd66e5
END DESCRIPTION:
XS GIS Cut Line= 5
      2529048.41     13495191.78      2529926.02     13494878.95
      2530188.46     13494815.96      2530413.11     13494666.89
      2530744.41     13494379.63
#Sta/Elev= 30
  4068.9  180.34  4182.9  176.69  4226.4  175.57  4431.6  168.48  4522.2  166.74
  4577.1  165.35  4799.2  158.11  4908.7  154.51  4925.2  152.76  4939.5  153.94
    4965  151.09  5028.4  148.25  5028.7  147.75  5032.4  148.25  5056.2  150.95
  5079.2  152.69  5126.4  153.09  5143.5  155.05  5174.4  150.64  5184.7  150.22
  5333.9   150.6    5349  150.81    5370  152.61    5376   154.7  5412.1  158.96
  5427.2  157.38  5544.7  158.17  5918.4  161.86  5939.7  163.07  5978.6  163.44
#Mann= 9 ,-1 , 0
  4068.9     .05       0  4182.9     .07       0  4226.4     .05       0
  4522.2     .07       0  4577.1     .05       0  4799.2     .07       0
  5028.4     .05       0  5032.4     .07       0  5056.2     .05       0
Bank Sta=5028.4,5032.4
XS Rating Curve= 0 ,0
Exp/Cntr=0.3,0.1

Type RM Length L Ch R = 1 ,4842    ,497,497,497
BEGIN DESCRIPTION:
Mapping XS 27c903ce
END DESCRIPTION:
XS GIS Cut Line= 3
      2529222.65     13495431.14      2530020.82     13495080.64
      2530719.66     13494547.21
#Sta/Elev= 30
  4196.8   174.1  4324.5  171.85  4597.8  165.13    4720  160.15  4887.4  155.14
  4917.8  153.41  4923.3  151.39  4941.2  152.53  4946.6  150.12  4963.9  150.17
  4998.8  146.31  5007.4  146.53  5014.7  146.07    5015  145.57  5018.7  146.07
  5045.5  148.47  5062.2  151.14  5107.4   151.8  5182.8  153.25  5203.7  155.38
  5224.8  151.33    5294  151.19  5438.6  150.79  5453.1  151.57  5475.8   155.4
  5496.7  156.68    5503   158.7  5517.5   157.1    5533  157.21  5947.7  162.51
#Mann= 7 ,-1 , 0
  4196.8     .05       0  5007.4     .12       0  5014.7     .05       0
  5018.7     .12       0  5107.4     .05       0    5294    .063       0
    5533     .05       0
Bank Sta=5014.7,5018.7
XS Rating Curve= 0 ,0
Exp/Cntr=0.3,0.1

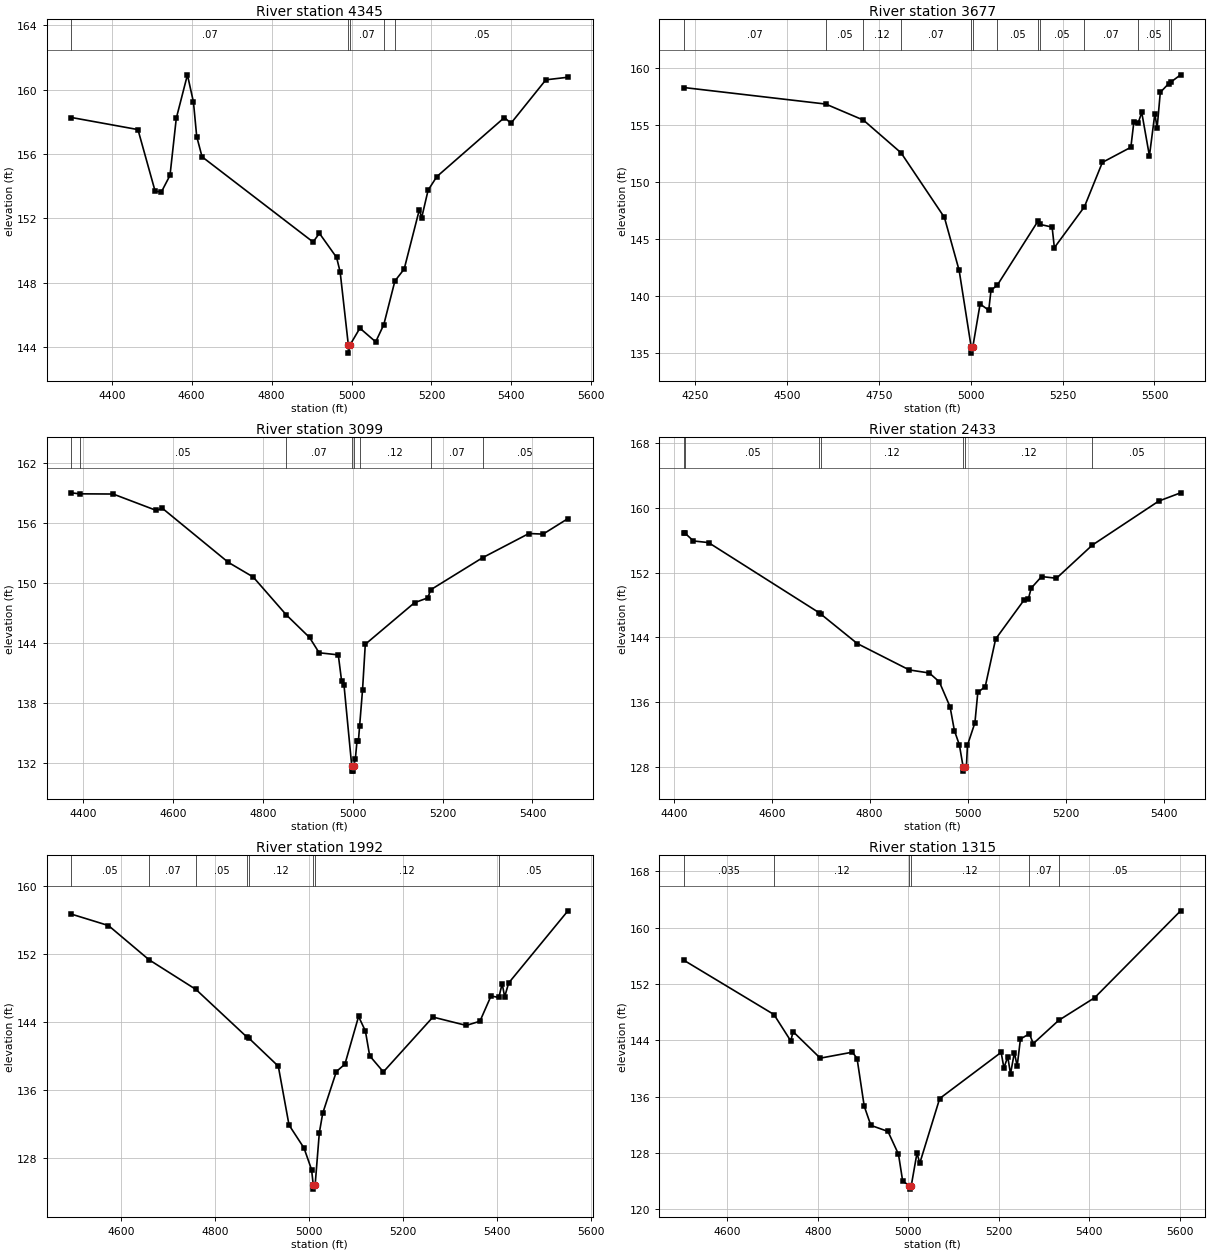
Type RM Length L Ch R = 1 ,4345    ,668,668,668
BEGIN DESCRIPTION:
Mapping XS ecb3b7ec
END DESCRIPTION:
XS GIS Cut Line= 3
      2529734.37     13495692.61      2530359.36     13495328.04
      2530606.76     13494872.31
#Sta/Elev= 30
  4299.3  158.27  4465.6  157.52  4508.6  153.69  4524.3  153.65  4545.8  154.68
  4561.5  158.22  4589.4  160.92  4604.5  159.22  4612.6  157.09    4626  155.83
  4903.8  150.54  4919.6  151.08  4962.6  149.58  4971.5  148.68    4992  144.14
  4992.2  143.64    4996  144.14  5020.9  145.19  5060.4  144.34  5080.7  145.41
  5108.5  148.12  5131.7  148.86  5169.7  152.55  5175.4  152.04  5191.6  153.76
  5213.4   154.6  5382.6  158.27  5398.8  157.91  5486.2  160.61  5541.4  160.77
#Mann= 5 ,-1 , 0
  4299.3     .07       0    4992     .05       0    4996     .07       0
  5080.7     .12       0  5108.5     .05       0
Bank Sta=4992,4996
XS Rating Curve= 0 ,0
Exp/Cntr=0.3,0.1

Type RM Length L Ch R = 1 ,3677    ,578,578,578
BEGIN DESCRIPTION:
Mapping XS 1953d0c8
END DESCRIPTION:
XS GIS Cut Line= 3
       2529825.5     13496122.31      2530606.76     13495913.97
      2530919.29     13495471.22
#Sta/Elev= 30
  4220.6  158.32  4605.7  156.87  4708.2  155.46  4810.7  152.58  4928.6   146.9
  4968.7  142.24  5001.6  135.47  5001.9  134.97  5005.6  135.47  5025.7  139.29
  5049.2  138.74  5055.3  140.49  5072.8  140.96  5183.4  146.59  5188.7  146.29
  5221.6  146.05  5227.7  144.24  5309.5  147.84  5358.3  151.74  5435.8  153.07
  5444.1  155.33  5455.5  155.19  5465.4  156.14  5486.3  152.31  5501.1  156.03
  5507.2  154.75  5515.9   157.9  5538.5  158.66  5546.2  158.84  5571.1  159.44
#Mann= 13 ,-1 , 0
  4220.6     .07       0  4605.7     .05       0  4708.2     .12       0
  4810.7     .07       0  5001.6     .05       0  5005.6     .07       0
  5072.8     .05       0  5183.4     .07       0  5188.7     .05       0
  5309.5     .07       0  5455.5     .05       0  5538.5     .07       0
  5546.2     .05       0
Bank Sta=5001.6,5005.6
XS Rating Curve= 0 ,0
Exp/Cntr=0.3,0.1

Type RM Length L Ch R = 1 ,3099    ,666,666,666
BEGIN DESCRIPTION:
Mapping XS b4277783
END DESCRIPTION:
XS GIS Cut Line= 3
      2530138.02     13496669.18      2530736.97     13496447.83
      2531140.27     13496213.65
#Sta/Elev= 30
    4374  159.05  4391.9  158.95  4466.7  158.93  4562.7  157.29  4576.1  157.51
  4722.9   152.1  4778.4  150.63  4851.9  146.85  4903.8  144.58  4925.2  143.05
  4967.8  142.84  4975.3  140.19  4980.6  139.78  4997.8  131.71    4998  131.21
  5001.5  131.21  5001.8  131.71  5005.7  132.39  5009.4  134.18  5012.5  134.18
  5015.2  135.68  5021.8  139.35  5027.9   143.9  5137.5  148.06    5167  148.54
  5173.4  149.35    5289  152.56  5392.1  154.98  5423.6  154.92  5478.9  156.47
#Mann= 8 ,-1 , 0
    4374     .07       0  4391.9     .05       0  4851.9     .07       0
  4997.8     .05       0  5001.8     .07       0  5015.2     .12       0
  5173.4     .07       0    5289     .05       0
Bank Sta=4997.8,5001.8
XS Rating Curve= 0 ,0
Exp/Cntr=0.3,0.1

Type RM Length L Ch R = 1 ,2433    ,441,441,441
BEGIN DESCRIPTION:
Mapping XS 7d03d360
END DESCRIPTION:
XS GIS Cut Line= 3
      2530586.46     13497026.99      2531148.95     13496901.99
      2531385.06     13496533.93
#Sta/Elev= 30
  4421.3  156.91  4423.4  156.84  4440.3   155.9    4471   155.7  4697.6     147
  4700.8  146.84  4774.7  143.22  4880.8  139.96  4921.8  139.58  4942.2  138.49
  4964.2  135.39    4973  132.46  4983.2  130.69  4990.9  127.95  4991.2  127.45
  4994.9  127.95  4997.5  127.95  4999.7  130.65  5014.9  133.43  5020.8  137.18
    5036   137.9  5057.2  143.78  5114.6  148.55  5123.9  148.71  5129.8  150.07
    5151   151.5  5181.4  151.29  5254.6  155.39  5390.2  160.83  5434.8  161.85
#Mann= 7 ,-1 , 0
  4421.3     .07       0  4423.4     .05       0  4697.6     .07       0
  4700.8     .12       0  4990.9     .05       0  4994.9     .12       0
  5254.6     .05       0
Bank Sta=4990.9,4994.9
XS Rating Curve= 0 ,0
Exp/Cntr=0.3,0.1

Type RM Length L Ch R = 1 ,1992    ,677,677,677
BEGIN DESCRIPTION:
Mapping XS b79b6720
END DESCRIPTION:
XS GIS Cut Line= 3
      2530681.24     13497344.76      2531147.86     13497253.61
      2531680.89     13497026.09
#Sta/Elev= 30
  4495.1  156.65  4573.7  155.31  4659.7   151.3  4759.7   147.8  4868.1   142.2
  4872.1  142.08  4934.6  138.79  4957.4  131.88  4989.2  129.18  5005.3  126.64
  5008.9  124.85  5009.2  124.35  5012.9  124.85  5021.8  130.97    5029  133.26
    5058  138.16  5076.2  139.03  5105.2  144.63  5119.7  142.92  5128.8  140.01
  5157.9  138.12  5263.2  144.56    5334  143.58  5363.1  144.07  5386.7  147.04
  5403.3  146.86  5410.3  148.48  5415.7  146.94  5424.1  148.56  5550.1  157.04
#Mann= 8 ,-1 , 0
  4495.1     .05       0  4659.7     .07       0  4759.7     .05       0
  4868.1     .07       0  4872.1     .12       0  5008.9     .05       0
  5012.9     .12       0  5403.3     .05       0
Bank Sta=5008.9,5012.9
XS Rating Curve= 0 ,0
Exp/Cntr=0.3,0.1

Type RM Length L Ch R = 1 ,1315    ,323,323,323
BEGIN DESCRIPTION:
Mapping XS ed76ff1d
END DESCRIPTION:
XS GIS Cut Line= 3
      2530739.21     13497756.16      2531218.39     13497846.44
      2531710.75     13497485.84
#Sta/Elev= 30
  4504.2  155.34  4702.8  147.66    4740  143.91  4745.1  145.23  4805.2  141.47
  4876.4  142.32  4886.6  141.42  4902.4  134.66  4917.1  131.93  4954.9  131.07
  4978.2  127.83  4987.5     124  5002.4  123.38  5002.7  122.88  5006.5  123.38
  5019.1     128  5025.3  126.56  5069.3  135.74  5205.2  142.29  5211.4  140.08
  5219.8  141.67    5226  139.25  5234.5  142.26  5240.7  140.34  5247.9  144.19
  5267.8  144.93  5276.2  143.53  5332.4  146.83  5412.1  150.05  5602.1  162.38
#Mann= 6 ,-1 , 0
  4504.2    .035       0  4702.8     .12       0  5002.4     .05       0
  5006.5     .12       0  5267.8     .07       0  5332.4     .05       0
Bank Sta=5002.4,5006.5
XS Rating Curve= 0 ,0
Exp/Cntr=0.3,0.1

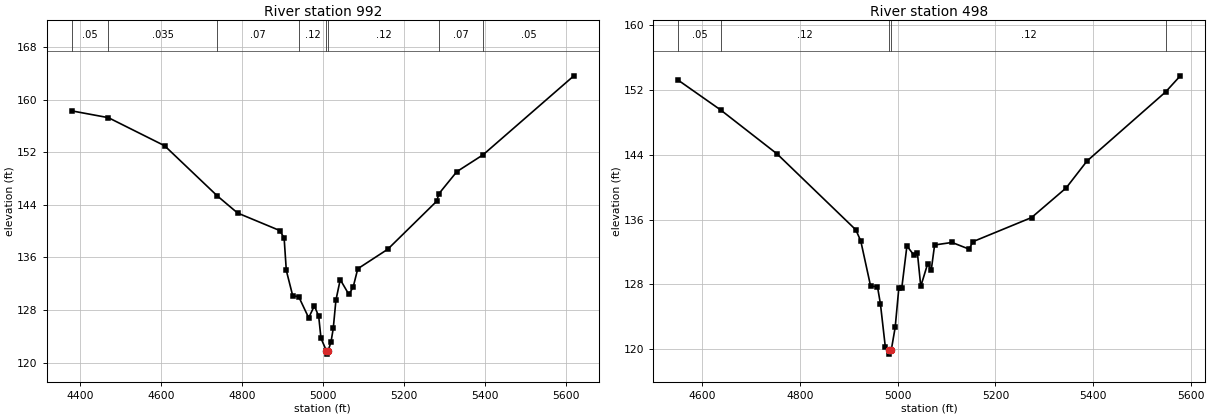
Type RM Length L Ch R = 1 ,992     ,494,494,494
BEGIN DESCRIPTION:
Mapping XS cd4bb11b
END DESCRIPTION:
XS GIS Cut Line= 4
      2530666.01     13498181.98      2531110.43     13498209.76
      2531520.15     13498056.98      2531796.64     13497828.88
#Sta/Elev= 30
  4379.1  158.27  4469.5  157.24  4608.5  152.97    4739  145.33  4788.9  142.74
  4893.3  140.07    4904  138.94  4909.4     134  4925.3  130.14    4940  130.02
  4964.7   126.8  4978.7  128.62  4989.4  127.05  4995.1  123.69  5008.6  121.78
  5008.9  121.28  5012.8  121.78    5020  123.18  5025.4  125.18    5032  129.48
  5042.7  132.61  5064.1  130.35  5074.7  131.49    5086  134.26  5160.1  137.23
  5280.9  144.52  5286.8  145.69  5330.9  149.03  5395.7  151.59  5620.1   163.6
#Mann= 8 ,-1 , 0
  4379.1     .05       0  4469.5    .035       0    4739     .07       0
    4940     .12       0  5008.6     .05       0  5012.8     .12       0
  5286.8     .07       0  5395.7     .05       0
Bank Sta=5008.6,5012.8
XS Rating Curve= 0 ,0
Exp/Cntr=0.3,0.1

Type RM Length L Ch R = 1 ,498     ,0,0,0
BEGIN DESCRIPTION:
TRIB 6 TO COLETO CREEK 1.0
END DESCRIPTION:
XS GIS Cut Line= 3
       2531023.9     13498526.99        2531475.       13498575.
       2531870.1     13498160.06
#Sta/Elev= 30
  4551.3  153.19    4638  149.52  4753.5  144.09  4914.4  134.73  4924.5  133.36
  4944.6  127.79  4958.7  127.71  4964.7   125.6  4974.8  120.23  4982.7  119.89
    4983  119.39  4986.9  119.89  4994.9   122.7  5002.4  127.57  5008.4  127.57
  5018.9  132.74  5033.1  131.61  5040.3   131.9  5047.2  127.75  5061.4  130.56
  5068.6  129.75  5075.5  132.86  5111.1  133.17  5146.3  132.34  5153.6  133.26
  5273.7  136.24  5344.5   139.9    5387  143.21  5547.8  151.74  5577.9  153.73
#Mann= 5 ,-1 , 0
  4551.3     .05       0    4638     .12       0  4982.7     .05       0
  4986.9     .12       0  5547.8     .07       0
Bank Sta=4982.7,4986.9
XS Rating Curve= 0 ,0
Exp/Cntr=0.3,0.1

Chan Stop Cuts=-1
Use User Specified Reach Order=0
Composite Channel Slope=5