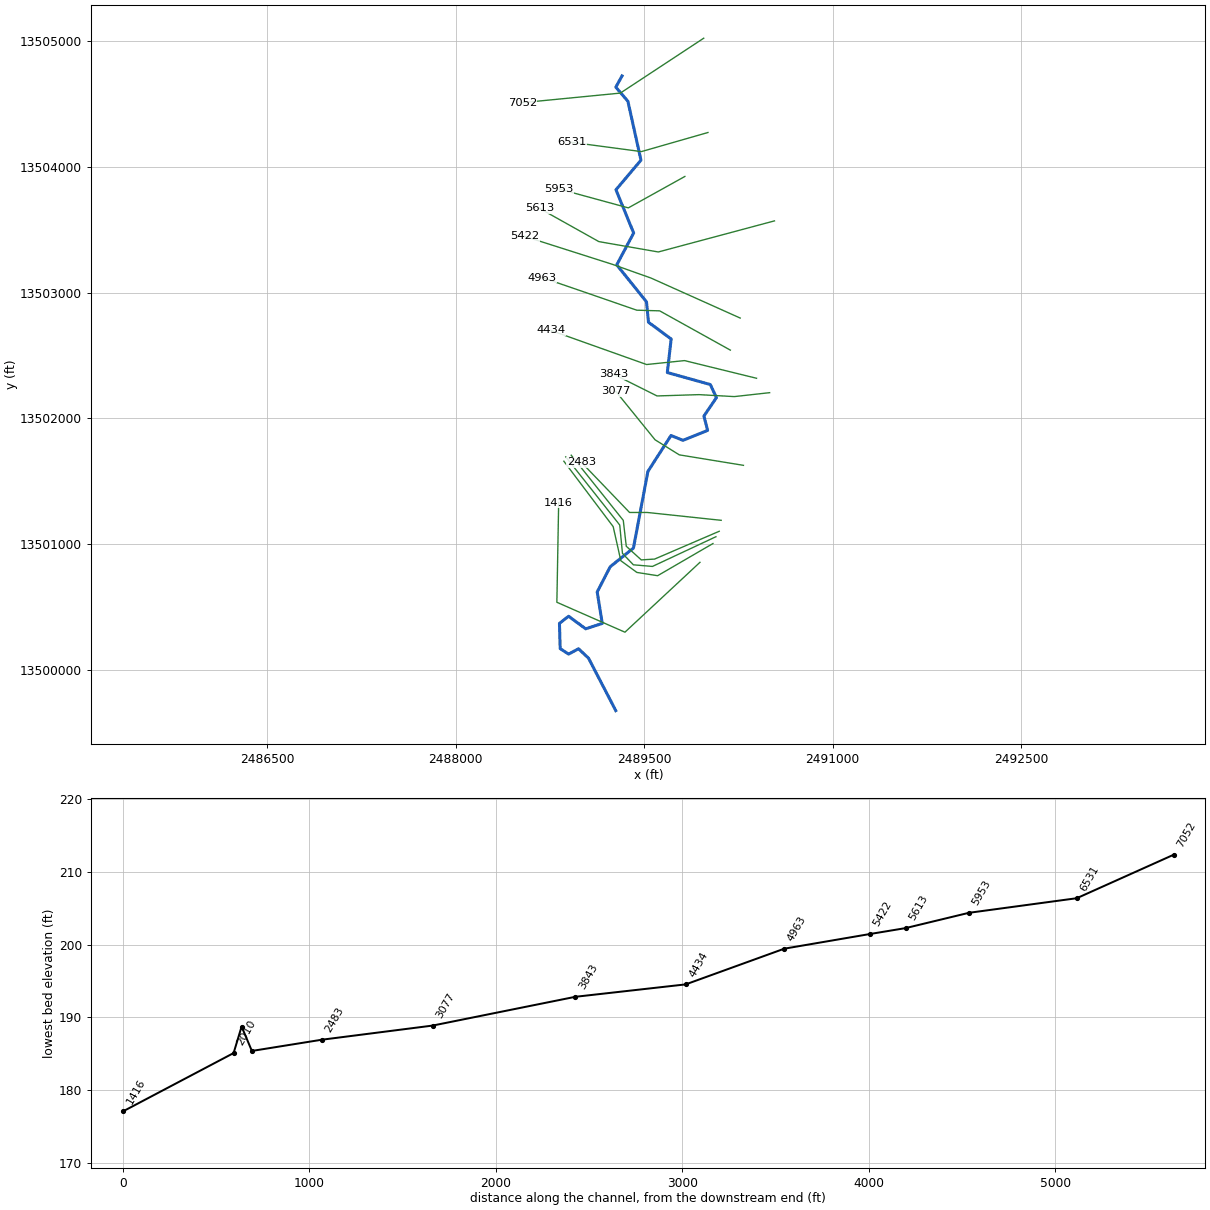
--- TRIB 6 TO EIGHTEENMILE CREEK.prj (project) ---

Proj Title=TRIB 6 TO EIGHTEENMILE CREEK Base Level Engineering
Current Plan=p01
Default Exp/Contr=0.3,0.1
English Units
Geom File=g01
Flow File=f01
Plan File=p01
Y Axis Title=Elevation
X Axis Title(PF)=Main Channel Distance
X Axis Title(XS)=Station
BEGIN DESCRIPTION:
TRIB 6 TO EIGHTEENMILE CREEK
END DESCRIPTION:
DSS Export Rating Curves= 0
DSS Export Rating Curve Sorted= 0
DSS Export Volume Flow Curves= 0
DXF OffsetX= 0
DXF OffsetY= 0
DXF ScaleX= 1
DXF ScaleY= 10

--- TRIB 6 TO EIGHTEENMILE CREEK.p01 (plan) ---

Plan Title=Multiple Run
Short Identifier=Multiple
Geom File=g01
Flow File=f01
Subcritical Flow
K Sum by GR= 0
Std Step Tol= 0.01
Critical Tol= 0.01
Num of Std Step Trials= 20
Max Error Tol= 0.3
Flow Tol Ratio= 0.001
Split Flow NTrial= 30
Split Flow Tol= 0.02
Split Flow Ratio= 0.02
Log Output Level= 0
Friction Slope Method= 1
Unsteady Friction Slope Method= 2
Unsteady Bridges Friction Slope Method= 1
Parabolic Critical Depth
Global Vel Dist=  1 , 1 , 1
Global Log Level= 0
CheckData=True
Encroach Param= -1, 0, 0, 0
BEGIN DESCRIPTION:
Multiple Run
END DESCRIPTION:

--- TRIB 6 TO EIGHTEENMILE CREEK.f01 (steady flow) ---

Flow Title=Multiple
Number of Profiles=7
Profile Names=10-year,25-year,50-year,1pct_min,100-year,1pct_plu,500-year
River Rch & RM= TRIB 6 TO EIGHTE,Reach-1,7052
     546     874    1167     756    1508    3008    2488
River Rch & RM= TRIB 6 TO EIGHTE,Reach-1,5613
     816    1334    1807    1185    2365    4718    4004
Boundary for River Rch & Prof#=TRIB 6 TO EIGHTE,Reach-1,1
Up Type=0
Dn Type=3
Dn Slope=0.005
Boundary for River Rch & Prof#=TRIB 6 TO EIGHTE,Reach-1,2
Up Type=0
Dn Type=3
Dn Slope=0.005
Boundary for River Rch & Prof#=TRIB 6 TO EIGHTE,Reach-1,3
Up Type=0
Dn Type=3
Dn Slope=0.005
Boundary for River Rch & Prof#=TRIB 6 TO EIGHTE,Reach-1,4
Up Type=0
Dn Type=3
Dn Slope=0.005
Boundary for River Rch & Prof#=TRIB 6 TO EIGHTE,Reach-1,5
Up Type=0
Dn Type=3
Dn Slope=0.005
Boundary for River Rch & Prof#=TRIB 6 TO EIGHTE,Reach-1,6
Up Type=0
Dn Type=3
Dn Slope=0.005
Boundary for River Rch & Prof#=TRIB 6 TO EIGHTE,Reach-1,7
Up Type=0
Dn Type=3
Dn Slope=0.005

--- TRIB 6 TO EIGHTEENMILE CREEK.g01 (geometry) ---

Geom Title=Existing Conditions
Program Version=4.10

River Reach=TRIB 6 TO EIGHTE,Reach-1
Reach XY= 30
        2489325.       13504725.       2489275.5     13504635.55
      2489371.44     13504523.53      2489475.53     13504054.57
      2489276.59     13503818.95      2489417.44       13503475.
      2489282.83     13503221.73      2489519.52     13502927.44
      2489535.35     13502764.88      2489715.88     13502631.76
      2489685.34     13502364.87      2490027.59     13502269.29
      2490075.85     13502164.95      2489976.67     13502018.94
       2490005.9     13501904.49      2489809.58     13501825.15
      2489714.63     13501864.02      2489530.54     13501577.42
       2489415.7     13500968.33      2489230.59     13500819.39
      2489127.23     13500619.07      2489167.65     13500368.61
      2489035.49     13500325.93       2488899.9     13500425.63
      2488826.98     13500369.38      2488832.69     13500168.43
      2488899.91     13500124.56      2488978.42     13500167.19
      2489058.54     13500091.82        2489275.       13499675.

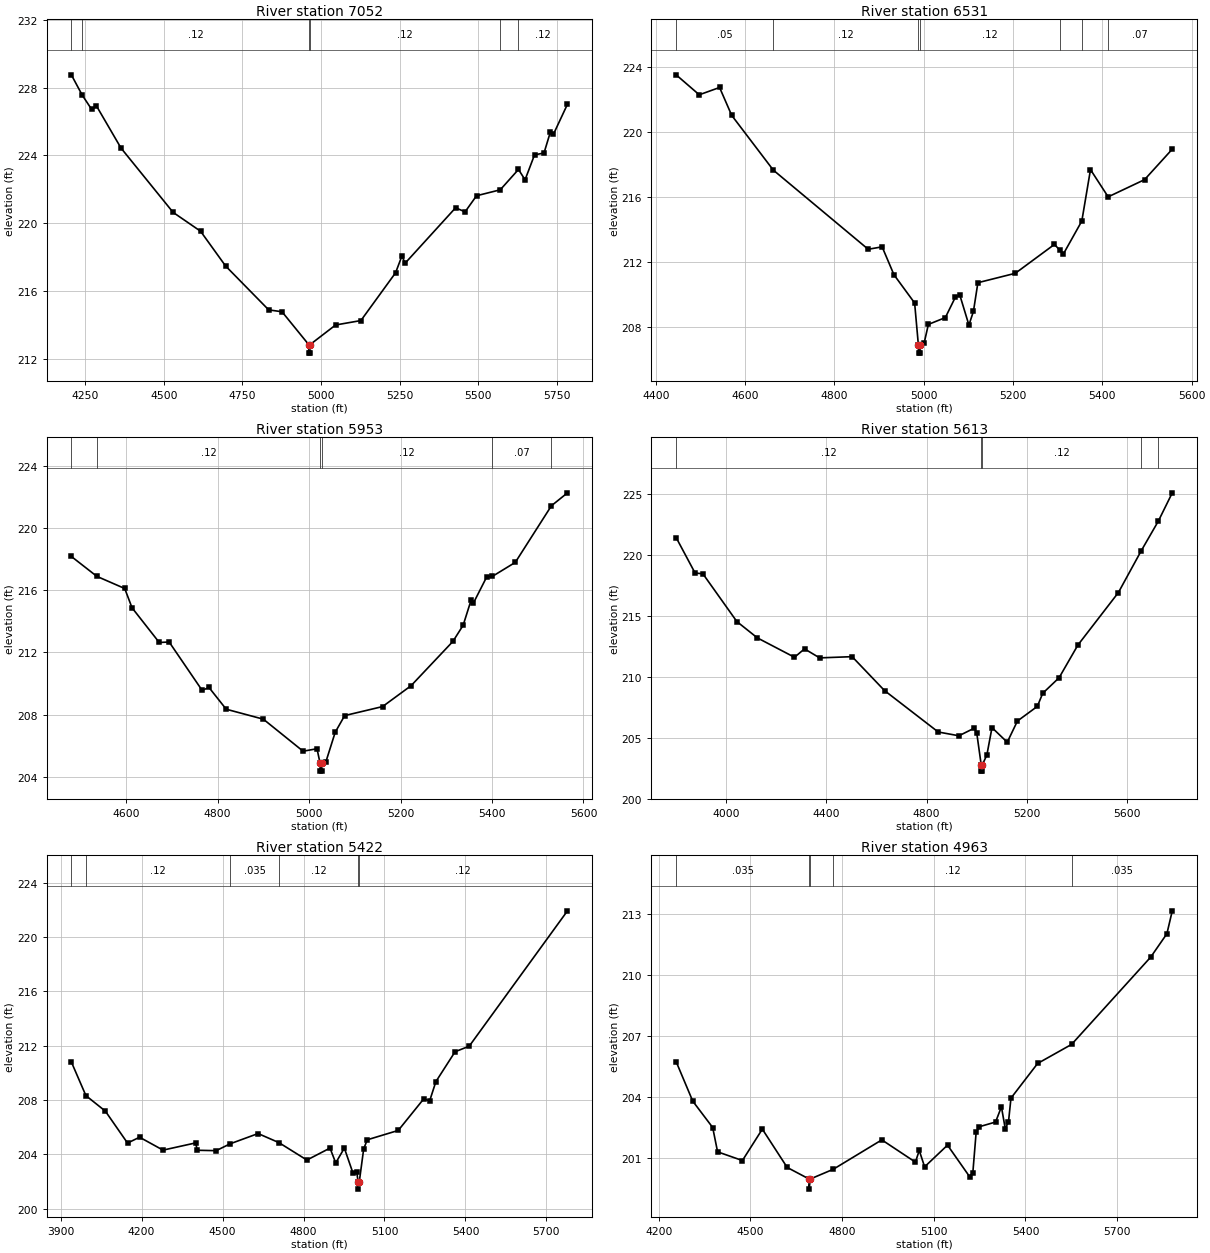
Type RM Length L Ch R = 1 ,7052    ,521,521,521
BEGIN DESCRIPTION:
TRIB 6 TO EIGHTEENMILE CREEK 12.0
END DESCRIPTION:
XS GIS Cut Line= 3
      2489974.99       13505025.      2489311.31     13504588.24
      2488530.63       13504512.
#Sta/Elev= 30
  4205.5  228.75  4240.2  227.55  4270.2  226.71  4285.3  226.92  4363.6  224.43
  4529.3  220.64  4616.6  219.53  4696.3  217.48  4833.5  214.89  4875.9  214.78
    4961  212.84  4961.3  212.34  4964.8  212.34    4965  212.84  5046.5     214
  5126.9  214.26  5237.4  217.08  5257.5  218.07  5267.6  217.64  5428.3  220.91
  5458.5  220.67    5495  221.62  5570.4  221.97  5628.4  223.17  5649.4  222.56
  5679.5  224.03  5709.7  224.14  5729.8  225.37  5739.8  225.25  5784.4  227.02
#Mann= 6 ,-1 , 0
  4205.5     .07       0  4240.2     .12       0    4961     .05       0
    4965     .12       0  5570.4     .07       0  5628.4     .12       0
Bank Sta=4961,4965
XS Rating Curve= 0 ,0
Exp/Cntr=0.3,0.1

Type RM Length L Ch R = 1 ,6531    ,578,578,578
BEGIN DESCRIPTION:
Mapping XS d3785532
END DESCRIPTION:
XS GIS Cut Line= 3
       2490008.5     13504274.67      2489479.02     13504122.77
      2488923.44     13504196.56
#Sta/Elev= 30
  4445.3  223.51  4497.1  222.28  4542.6  222.73  4569.8  221.01  4662.9  217.64
  4875.5  212.76  4906.7  212.91  4933.2  211.19  4979.5  209.45  4987.9  206.86
  4988.2  206.36  4991.7  206.36  4991.9  206.86  5000.7  206.97  5010.3  208.13
  5048.3  208.55  5070.8  209.81  5080.9  209.92  5101.1  208.09  5111.2  208.93
  5121.2   210.7    5205  211.28  5292.7  213.06  5304.8   212.7  5312.9  212.48
    5354   214.5  5373.4  217.67    5413  215.99  5494.5  217.05  5556.6  218.93
#Mann= 7 ,-1 , 0
  4445.3     .05       0  4662.9     .12       0  4987.9     .05       0
  4991.9     .12       0  5304.8     .07       0    5354     .12       0
    5413     .07       0
Bank Sta=4987.9,4991.9
XS Rating Curve= 0 ,0
Exp/Cntr=0.3,0.1

Type RM Length L Ch R = 1 ,5953    ,340,340,340
BEGIN DESCRIPTION:
TRIB 6 TO EIGHTEENMILE CREEK 10.0
END DESCRIPTION:
XS GIS Cut Line= 3
        2489825.       13503925.        2489375.       13503675.
      2488824.96     13503825.01
#Sta/Elev= 30
  4480.1  218.16  4535.9  216.88  4596.8   216.1  4612.8  214.86  4672.3  212.63
    4694  212.66  4766.1  209.55    4781  209.74  4818.7  208.34  4899.9   207.7
  4986.9  205.64  5017.3   205.8    5024  204.86  5024.2  204.36  5027.7  204.36
    5028  204.86  5036.3  204.92  5057.1  206.86  5077.8  207.93  5160.7  208.51
  5222.9  209.85  5314.5   212.7  5336.9  213.74  5354.2  215.35  5359.4  215.17
  5388.8  216.87  5400.8  216.88  5450.9  217.78  5529.9  221.42    5565  222.25
#Mann= 6 ,-1 , 0
  4480.1     .05       0  4535.9     .12       0    5024     .05       0
    5028     .12       0  5400.8     .07       0  5529.9     .12       0
Bank Sta=5024,5028
XS Rating Curve= 0 ,0
Exp/Cntr=0.3,0.1

Type RM Length L Ch R = 1 ,5613    ,191,191,191
BEGIN DESCRIPTION:
Mapping XS eda9a640
END DESCRIPTION:
XS GIS Cut Line= 4
      2490538.06     13503571.55      2489613.57     13503324.16
      2489140.48     13503406.62      2488667.37     13503671.39
#Sta/Elev= 30
    3801  221.42  3876.6  218.51  3907.7  218.45  4043.3  214.53  4125.1  213.19
  4273.2   211.6  4313.2  212.29  4373.5  211.55  4503.1  211.65  4632.3  208.87
  4846.6  205.47  4929.1  205.16    4990  205.78  5000.2  205.41  5018.2  202.76
  5018.5  202.26    5022  202.26  5022.2  202.76  5040.8  203.59  5061.1  205.83
    5122  204.63  5162.6  206.37    5242  207.57  5263.7  208.65  5328.8  209.92
  5404.1  212.61  5565.4  216.91  5656.1  220.32  5724.8  222.77  5780.4  225.09
#Mann= 5 ,-1 , 0
    3801     .12       0  5018.2     .05       0  5022.2     .12       0
  5656.1     .07       0  5724.8     .12       0
Bank Sta=5018.2,5022.2
XS Rating Curve= 0 ,0
Exp/Cntr=0.3,0.1

Type RM Length L Ch R = 1 ,5422    ,459,459,459
BEGIN DESCRIPTION:
Mapping XS 52ff6049
END DESCRIPTION:
XS GIS Cut Line= 4
      2490264.98     13502798.44      2489556.63     13503116.16
      2489249.34     13503225.53      2488548.07      13503448.9
#Sta/Elev= 30
  3939.6  210.81  3993.6  208.33  4065.6  207.19  4147.8  204.84  4192.4  205.27
  4279.3  204.32  4399.9  204.85  4406.5  204.31  4476.1  204.28  4528.6  204.79
  4631.6  205.54    4709  204.87  4812.4  203.59  4898.1  204.47  4919.3  203.38
  4951.2  204.47    4983  202.64  4997.4  202.71  5002.3  201.95  5002.5  201.45
  5006.3  201.95  5022.9  204.41  5036.1  205.08    5151  205.77  5246.1  208.11
  5267.1  207.93  5290.4  209.36  5361.5  211.56    5414  211.97  5778.1  221.93
#Mann= 6 ,-1 , 0
  3939.6     .07       0  3993.6     .12       0  4528.6    .035       0
    4709     .12       0  5002.3     .05       0  5006.3     .12       0
Bank Sta=5002.3,5006.3
XS Rating Curve= 0 ,0
Exp/Cntr=0.3,0.1

Type RM Length L Ch R = 1 ,4963    ,529,529,529
BEGIN DESCRIPTION:
Mapping XS ce83cbdd
END DESCRIPTION:
XS GIS Cut Line= 5
      2490186.88     13502543.22      2489624.34     13502855.74
      2489442.05     13502860.95       2489035.8     13503001.58
      2488688.39     13503120.83
#Sta/Elev= 30
  4257.2  205.73  4311.6  203.78  4376.8  202.48  4392.8  201.28    4474  200.85
  4539.2   202.4  4620.5  200.51  4692.1  199.94  4692.3  199.44  4696.1  199.94
  4771.3  200.42  4930.1  201.87  5040.1  200.77  5052.5  201.35  5070.1  200.54
    5145  201.61  5217.5  200.05  5227.9  200.26  5238.7  202.25  5249.3  202.52
  5302.2  202.75  5321.4   203.5  5333.9  202.42  5344.5  202.76  5352.6  203.93
  5439.8  205.64  5550.9  206.58  5809.9  210.89  5862.7  212.04  5880.3  213.17
#Mann= 5 ,-1 , 0
  4257.2    .035       0  4692.1     .05       0  4696.1    .035       0
  4771.3     .12       0  5550.9    .035       0
Bank Sta=4692.1,4696.1
XS Rating Curve= 0 ,0
Exp/Cntr=0.3,0.1

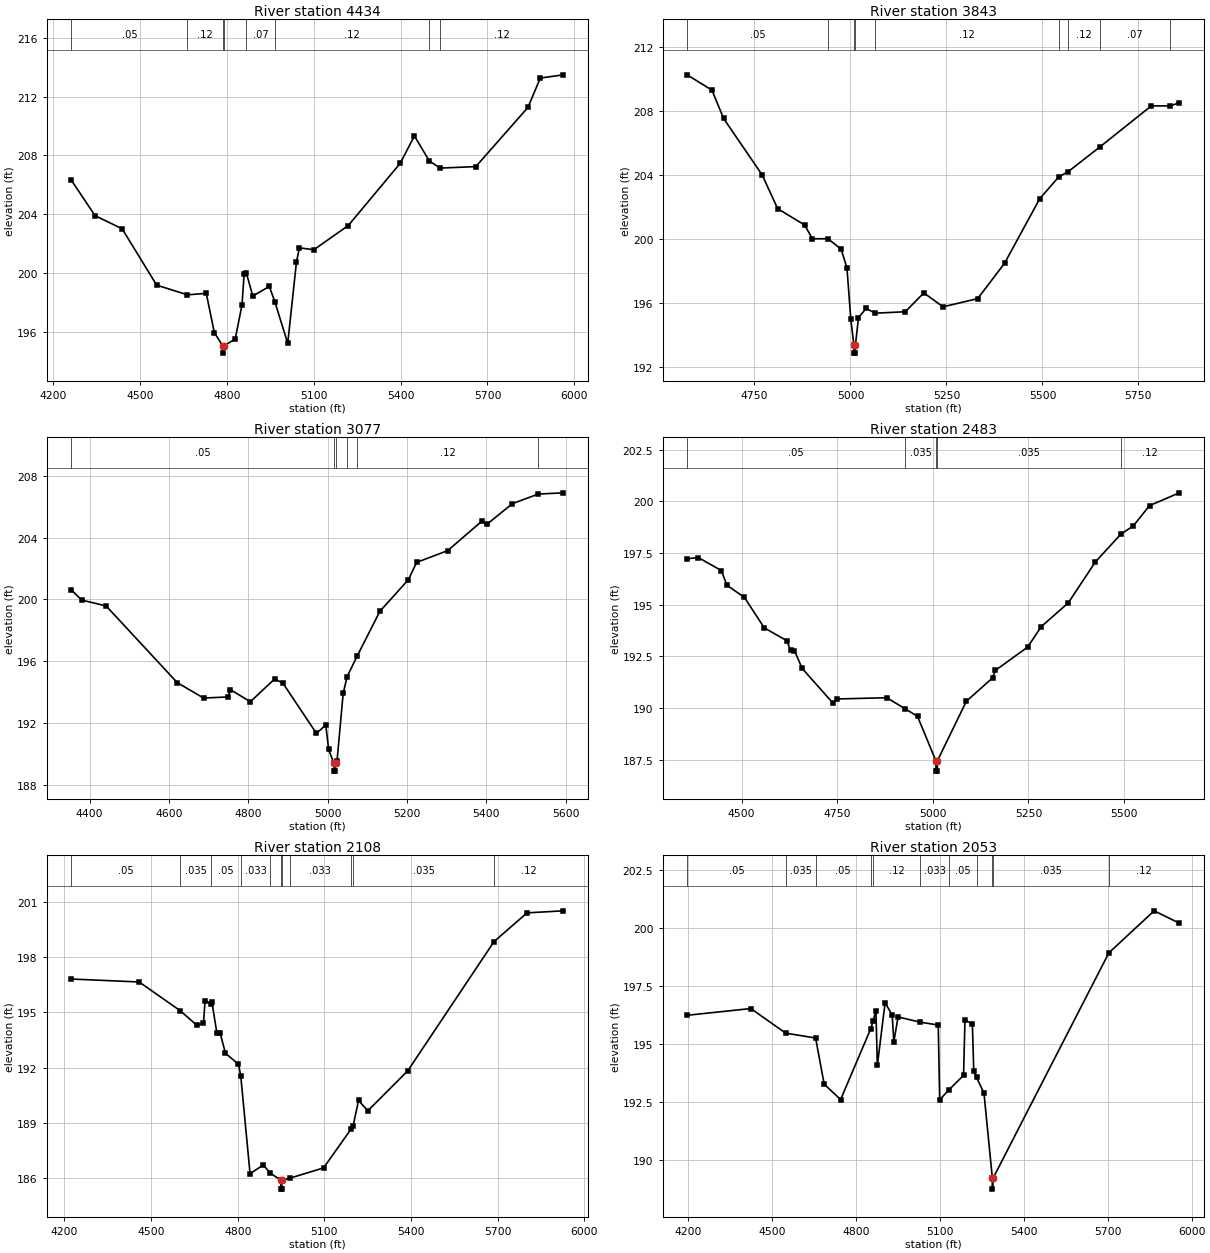
Type RM Length L Ch R = 1 ,4434    ,591,591,591
BEGIN DESCRIPTION:
Mapping XS 66e75819
END DESCRIPTION:
XS GIS Cut Line= 4
      2490395.22     13502319.27      2489822.26     13502459.91
      2489520.17     13502428.66      2488759.92     13502699.43
#Sta/Elev= 30
  4261.7  206.32  4343.9   203.9  4437.3  203.01  4556.9  199.17  4663.3  198.51
  4728.3  198.61  4756.2  195.93  4785.1  195.04  4785.3  194.54  4789.1  195.04
  4828.2  195.49  4851.7  197.82    4859   199.9  4866.6  200.01  4889.1  198.43
  4946.2  199.08  4965.2  198.04  5009.8  195.21  5039.9  200.74  5050.1  201.71
  5100.2  201.58  5219.1  203.23  5398.7  207.47  5447.5  209.33  5499.3  207.62
  5536.8  207.14  5659.8  207.24  5839.9  211.27  5882.7  213.27  5962.4  213.49
#Mann= 8 ,-1 , 0
  4261.7     .05       0  4663.3     .12       0  4785.1     .05       0
  4789.1     .12       0  4866.6     .07       0  4965.2     .12       0
  5499.3     .05       0  5536.8     .12       0
Bank Sta=4785.1,4789.1
XS Rating Curve= 0 ,0
Exp/Cntr=0.3,0.1

Type RM Length L Ch R = 1 ,3843    ,766,766,766
BEGIN DESCRIPTION:
Mapping XS 7a1914ce
END DESCRIPTION:
XS GIS Cut Line= 5
      2490499.33      13502204.7      2490218.09     13502173.45
      2489936.84     13502189.08      2489603.51     13502178.66
      2489260.45     13502350.19
#Sta/Elev= 30
  4574.6  210.26  4639.3   209.3  4669.5  207.53  4770.1  203.99  4810.4  201.88
  4880.7  200.86  4900.7     200  4941.3     200  4975.7  199.35  4990.9  198.17
  5000.9  194.95  5008.9  193.34  5009.1  192.84  5012.6  192.84  5012.9  193.34
  5020.9  195.06  5040.9  195.64  5064.2  195.34  5142.7  195.43  5191.1  196.61
  5241.1  195.74  5331.2  196.25  5401.2  198.46    5493  202.51  5542.4  203.87
  5567.1   204.2  5649.3  205.74  5783.7  208.32  5832.3  208.31  5856.3  208.51
#Mann= 9 ,-1 , 0
  4574.6     .05       0  4941.3     .07       0  5008.9     .05       0
  5012.9     .07       0  5064.2     .12       0  5542.4     .07       0
  5567.1     .12       0  5649.3     .07       0  5832.3     .12       0
Bank Sta=5008.9,5012.9
XS Rating Curve= 0 ,0
Exp/Cntr=0.3,0.1

Type RM Length L Ch R = 1 ,3077    ,594,594,594
BEGIN DESCRIPTION:
Mapping XS 0e4f4eb8
END DESCRIPTION:
XS GIS Cut Line= 4
      2490291.01     13501626.57      2489780.59     13501709.91
      2489587.88      13501829.7      2489275.37     13502215.14
#Sta/Elev= 30
    4354  200.62  4380.4  199.96  4441.8  199.58    4621  194.62  4687.5  193.62
  4748.9  193.69  4755.3  194.16  4805.3  193.38  4866.4  194.85    4887   194.6
    4972  191.33  4995.5  191.88  5002.7  190.29    5016  189.39  5016.3  188.89
  5019.8  188.89    5020  189.39  5023.9  189.57  5039.3  193.92  5049.3  195.01
  5074.6  196.34  5131.8  199.23  5203.7  201.28  5224.5   202.4  5302.8  203.16
  5388.1  205.05  5401.9  204.87  5465.9   206.2  5530.9  206.82  5594.3   206.9
#Mann= 6 ,-1 , 0
    4354     .05       0    5016     .05       0    5020     .05       0
  5049.3    .035       0  5074.6     .12       0  5530.9     .07       0
Bank Sta=5016,5020
XS Rating Curve= 0 ,0
Exp/Cntr=0.3,0.1

Type RM Length L Ch R = 1 ,2483    ,375,375,375
BEGIN DESCRIPTION:
Mapping XS d19505a8
END DESCRIPTION:
XS GIS Cut Line= 4
      2490113.94     13501189.07      2489525.38     13501251.58
      2489384.76     13501251.58      2489000.94     13501650.95
#Sta/Elev= 30
  4357.8  197.22  4386.9  197.28  4447.2  196.65  4461.8  195.94  4507.6  195.35
  4559.4  193.88  4618.2  193.26  4628.2  192.79  4638.3  192.78  4658.4  191.92
  4738.9  190.24  4749.7  190.44  4879.7   190.5  4928.3  189.96    4960   189.6
    5008  187.45  5008.3  186.95  5011.8  186.95    5012  187.45  5087.7  190.33
  5156.2  191.46  5163.4  191.82    5248  192.95  5283.5  193.94  5354.3  195.09
    5425  197.07  5492.1  198.42  5524.1  198.81  5566.5  199.79  5644.2  200.41
#Mann= 5 ,-1 , 0
  4357.8     .05       0  4928.3    .035       0    5008    .035       0
    5012    .035       0  5492.1     .12       0
Bank Sta=5008,5012
XS Rating Curve= 0 ,0
Exp/Cntr=0.3,0.1

Type RM Length L Ch R = 1 ,2108    ,55,55,55
BEGIN DESCRIPTION:
Mapping XS 42148c02
END DESCRIPTION:
XS GIS Cut Line= 6
      2490098.26     13501101.93       2489584.2     13500880.69
      2489477.92     13500874.18      2489358.63     13500982.63
      2489334.77     13501188.68       2488920.5     13501707.06
#Sta/Elev= 30
  4223.5  196.81  4458.6  196.65  4600.8  195.09  4657.7  194.31  4681.3   194.4
  4686.7  195.63  4706.5  195.47  4710.3  195.57  4727.8  193.87  4739.2  193.87
  4757.3  192.78  4802.4  192.19  4810.2  191.57  4842.5  186.25  4888.6  186.72
  4912.8  186.27  4948.7  185.91    4949  185.41  4952.5  185.41  4952.7  185.91
  4979.6     186  5096.9  186.56    5192  188.66  5199.2  188.83  5218.2  190.22
  5250.3  189.66  5388.6  191.83  5687.2  198.84  5801.6   200.4  5927.4  200.51
#Mann= 11 ,-1 , 0
  4223.5     .05       0  4600.8    .035       0  4706.5     .05       0
  4810.2    .033       0  4912.8     .12       0  4948.7    .033       0
  4952.7     .12       0  4979.6    .033       0    5192     .05       0
  5199.2    .035       0  5687.2     .12       0
Bank Sta=4948.7,4952.7
XS Rating Curve= 0 ,0
Exp/Cntr=0.3,0.1

Type RM Length L Ch R = 1 ,2053    ,43,43,43
BEGIN DESCRIPTION:
Mapping XS eb351308
END DESCRIPTION:
XS GIS Cut Line= 6
      2490072.24     13501058.55      2489566.85     13500822.13
      2489415.02     13500835.14      2489328.26     13500926.24
      2489306.58      13501151.8      2488877.13     13501694.04
#Sta/Elev= 30
  4195.5  196.25  4423.4  196.54    4548  195.48  4655.1  195.27  4685.7  193.28
  4744.5  192.62  4852.6  195.68  4860.4     196  4870.8  196.43  4875.8  194.09
  4903.6  196.79  4928.9  196.26  4934.8  195.11    4950  196.18  5029.9  195.95
  5093.6  195.83  5098.9  192.61    5132  193.04  5184.2  193.66  5189.2  196.03
  5215.7  195.89  5220.7  193.86  5230.7  193.57  5257.2   192.9    5287  189.26
  5287.2  188.76    5291  189.26    5704  198.94  5865.9  200.75  5955.7  200.22
#Mann= 11 ,-1 , 0
  4195.5     .05       0    4548    .035       0  4655.1     .05       0
  4852.6    .033       0  4860.4     .12       0  5029.9    .033       0
    5132     .05       0  5230.7    .035       0    5287     .05       0
    5291    .035       0    5704     .12       0
Bank Sta=5287,5291
XS Rating Curve= 0 ,0
Exp/Cntr=0.3,0.1

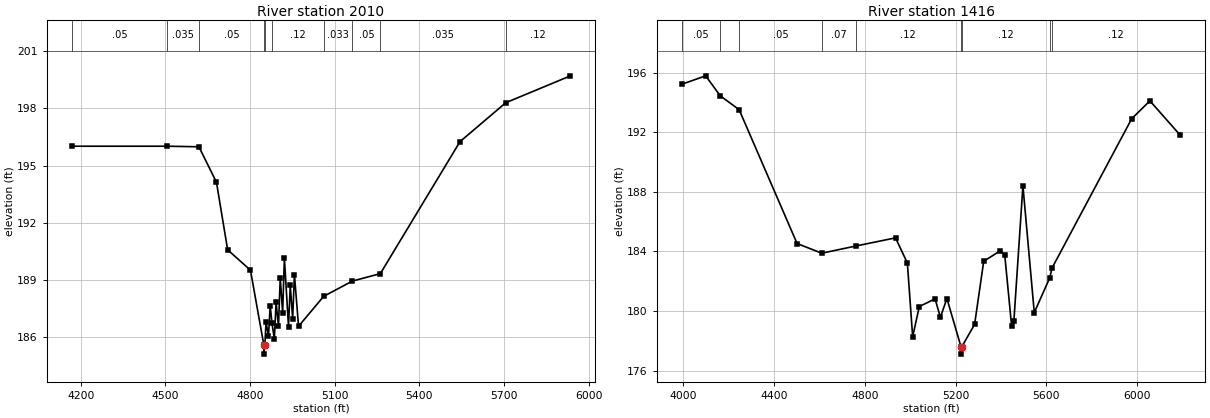
Type RM Length L Ch R = 1 ,2010    ,594,594,594
BEGIN DESCRIPTION:
Mapping XS 7d95a84f
END DESCRIPTION:
XS GIS Cut Line= 6
      2490048.34     13501004.31      2489608.06     13500748.38
      2489443.22     13500774.41      2489315.25     13500867.67
      2489254.52     13501138.79      2488861.95     13501659.32
#Sta/Elev= 30
  4167.5  196.02  4506.7  196.02  4618.6  195.99  4680.8  194.13  4720.4  190.59
  4801.3  189.52  4848.4  185.62  4848.6  185.12  4852.4  185.62  4856.6  186.82
  4865.1  186.05  4871.2  187.65  4877.6  186.74  4885.9  185.92  4892.1  187.84
  4900.6  186.57  4906.8  189.13  4915.3  187.29  4921.5  190.16  4936.1  186.56
  4942.3  188.72  4950.8  186.98    4957  189.29  4971.7  186.58  5060.7  188.15
  5162.6  188.95  5261.5  189.34  5543.8  196.26    5706   198.3  5935.2  199.71
#Mann= 10 ,-1 , 0
  4167.5     .05       0  4506.7    .035       0  4618.6     .05       0
  4848.4     .05       0  4852.4     .05       0  4877.6     .12       0
  5060.7    .033       0  5162.6     .05       0  5261.5    .035       0
    5706     .12       0
Bank Sta=4848.4,4852.4
XS Rating Curve= 0 ,0
Exp/Cntr=0.3,0.1

Type RM Length L Ch R = 1 ,1416    ,0,0,0
BEGIN DESCRIPTION:
TRIB 6 TO EIGHTEENMILE CREEK 1.0
END DESCRIPTION:
XS GIS Cut Line= 4
      2489944.92     13500854.85      2489348.06     13500299.04
      2488806.35     13500537.02      2488820.61     13501329.74
#Sta/Elev= 30
  3992.1  195.21  4098.2  195.78  4162.4  194.44  4245.7  193.51  4501.3  184.53
  4610.1  183.88  4759.4  184.36  4935.5  184.91  4987.7  183.22    5011  178.28
  5040.4   180.3  5109.9  180.82  5133.3  179.58  5162.1  180.84  5224.1  177.61
  5224.3  177.11  5228.1  177.61  5284.3  179.11  5324.4  183.34  5397.4  184.04
  5417.3  183.74  5447.3  179.03  5457.3   179.3  5497.3   188.4  5547.4   179.9
  5616.3  182.25  5625.2  182.87  5977.4  192.91  6057.4   194.1  6192.2  191.78
#Mann= 9 ,-1 , 0
  3992.1     .05       0  4162.4    .035       0  4245.7     .05       0
  4610.1     .07       0  4759.4     .12       0  5224.1     .05       0
  5228.1     .12       0  5616.3    .035       0  5625.2     .12       0
Bank Sta=5224.1,5228.1
XS Rating Curve= 0 ,0
Exp/Cntr=0.3,0.1

Chan Stop Cuts=-1
Use User Specified Reach Order=0
Composite Channel Slope=5