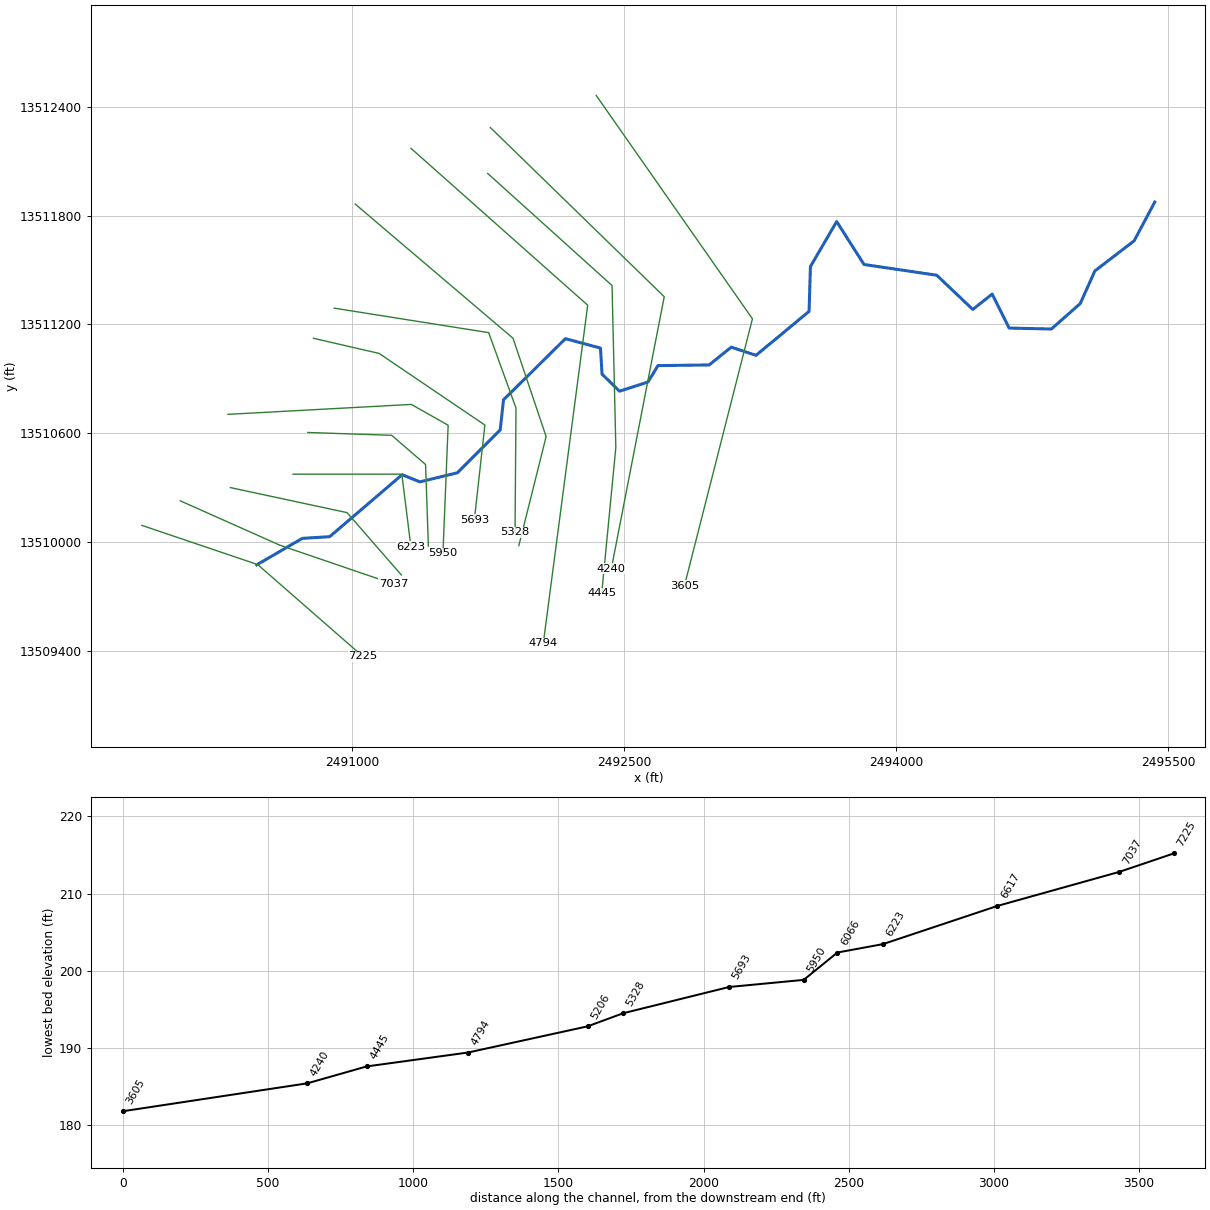
--- TRIB 6 TO FIFTEENMILE CREEK.prj (project) ---

Proj Title=TRIB 6 TO FIFTEENMILE CREEK Base Level Engineering
Current Plan=p01
Default Exp/Contr=0.3,0.1
English Units
Geom File=g01
Flow File=f01
Plan File=p01
BEGIN DESCRIPTION:
TRIB 6 TO FIFTEENMILE CREEK
END DESCRIPTION:

--- TRIB 6 TO FIFTEENMILE CREEK.p01 (plan) ---

Plan Title=Multiple Run
Short Identifier=Multiple
Geom File=g01
Flow File=f01
Subcritical Flow
K Sum by GR= 0
Std Step Tol= 0.01
Critical Tol= 0.01
Num of Std Step Trials= 20
Max Error Tol= 0.3
Flow Tol Ratio= 0.001
Split Flow NTrial= 30
Split Flow Tol= 0.02
Split Flow Ratio= 0.02
Log Output Level= 0
Friction Slope Method= 1
Unsteady Friction Slope Method= 2
Unsteady Bridges Friction Slope Method= 1
Parabolic Critical Depth
Global Vel Dist=  1 , 1 , 1
Global Log Level= 0
CheckData=True
Encroach Param= -1, 0, 0, 0
BEGIN DESCRIPTION:
Multiple Run
END DESCRIPTION:

--- TRIB 6 TO FIFTEENMILE CREEK.f01 (steady flow) ---

Flow Title=Multiple
Number of Profiles=7
Profile Names=10-year,25-year,50-year,1pct_min,100-year,1pct_plu,500-year
River Rch & RM= TRIB 6 TO FIFTEE,Reach-1,7225
     325     502     654     415     827    1650    1304
River Rch & RM= TRIB 6 TO FIFTEE,Reach-1,4240
     885    1454    1977    1301    2596    5179    4425
Boundary for River Rch & Prof#=TRIB 6 TO FIFTEE,Reach-1,1
Up Type=0
Dn Type=3
Dn Slope=0.005
Boundary for River Rch & Prof#=TRIB 6 TO FIFTEE,Reach-1,2
Up Type=0
Dn Type=3
Dn Slope=0.005
Boundary for River Rch & Prof#=TRIB 6 TO FIFTEE,Reach-1,3
Up Type=0
Dn Type=3
Dn Slope=0.005
Boundary for River Rch & Prof#=TRIB 6 TO FIFTEE,Reach-1,4
Up Type=0
Dn Type=3
Dn Slope=0.005
Boundary for River Rch & Prof#=TRIB 6 TO FIFTEE,Reach-1,5
Up Type=0
Dn Type=3
Dn Slope=0.005
Boundary for River Rch & Prof#=TRIB 6 TO FIFTEE,Reach-1,6
Up Type=0
Dn Type=3
Dn Slope=0.005
Boundary for River Rch & Prof#=TRIB 6 TO FIFTEE,Reach-1,7
Up Type=0
Dn Type=3
Dn Slope=0.005

--- TRIB 6 TO FIFTEENMILE CREEK.g01 (geometry) ---

Geom Title=Existing Conditions

River Reach=TRIB 6 TO FIFTEE,Reach-1
Reach XY= 30
      2490475.00     13509875.00      2490726.56     13510021.24
      2490877.45     13510030.47      2491276.45     13510371.90
      2491374.99     13510332.59      2491581.19     13510382.82
      2491817.18     13510618.81      2491835.48     13510784.80
      2492176.63     13511121.87      2492369.96     13511069.92
      2492378.55     13510926.45      2492474.89     13510832.31
      2492631.43     13510882.79      2492686.83     13510973.36
      2492969.14     13510977.07      2493090.34     13511075.04
      2493227.30     13511030.09      2493519.64     13511272.30
      2493527.07     13511519.15      2493671.65     13511767.42
      2493822.42     13511530.71      2494223.55     13511471.47
      2494421.73     13511282.84      2494528.62     13511367.51
      2494622.26     13511180.34      2494855.02     13511174.96
      2495014.24     13511315.32      2495094.78     13511495.09
      2495311.51     13511661.44      2495425.00     13511875.00

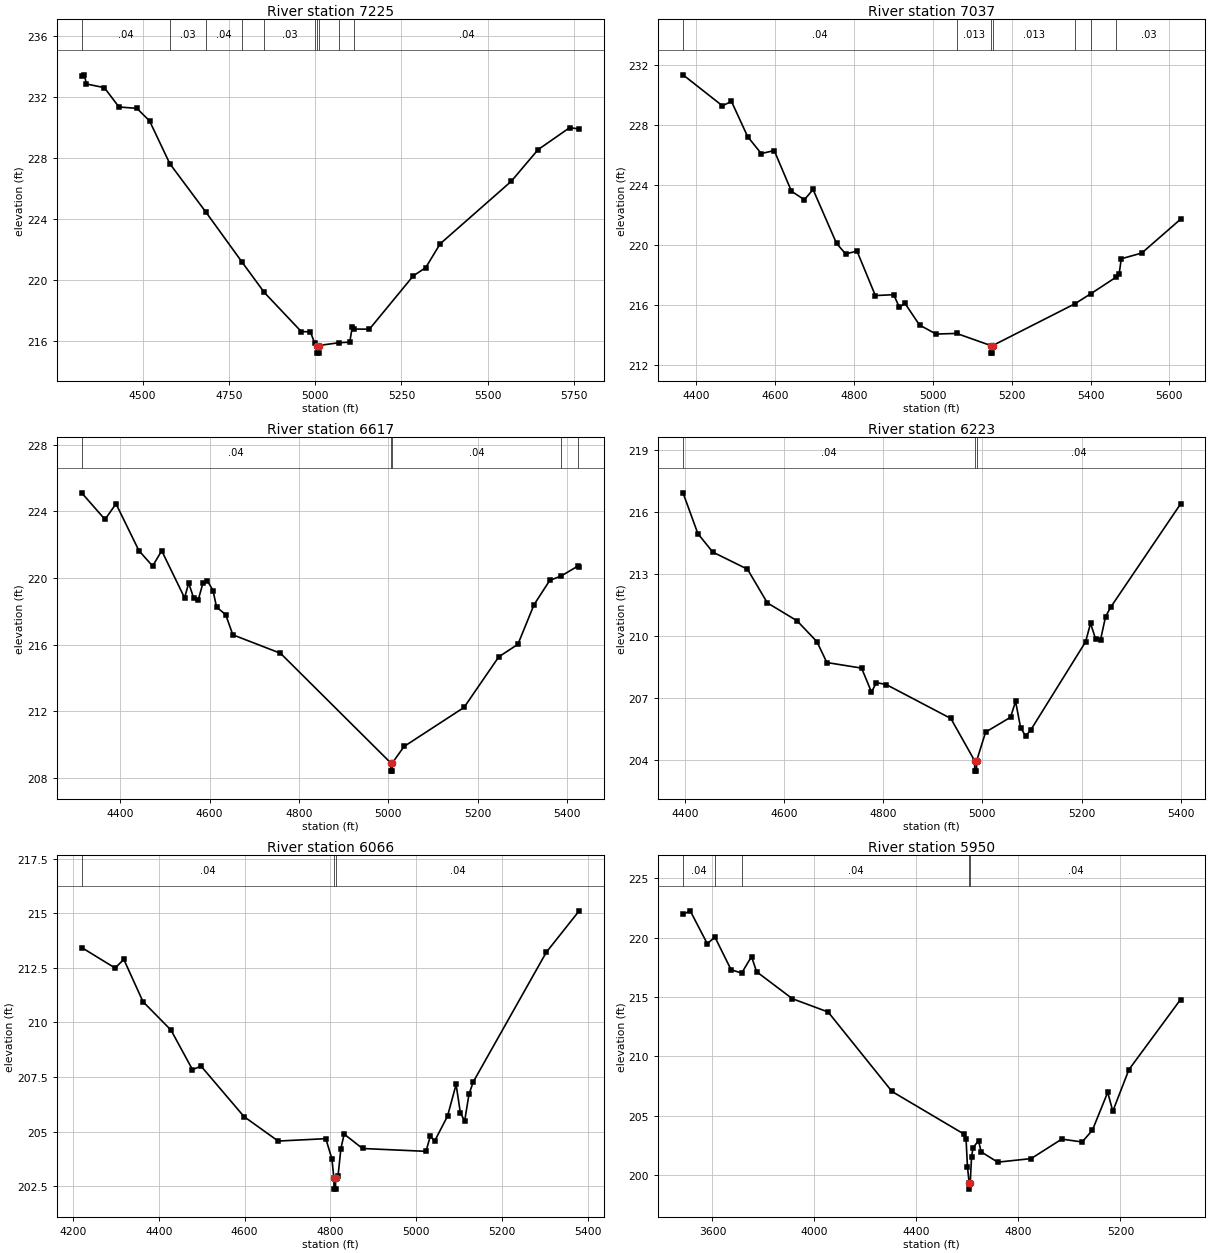
Type RM Length L Ch R = 1,7225,188,188,188
BEGIN DESCRIPTION:
TRIB 6 TO FIFTEENMILE CREEK 14.0
END DESCRIPTION:
XS GIS Cut Line= 3
      2489842.58     13510092.67      2490480.84     13509876.66
      2491059.44     13509371.21
#Sta/Elev= 30
  4323.3  233.40  4331.4  233.46  4336.7  232.86  4389.0  232.62  4431.4  231.35
  4483.3  231.26  4520.0  230.44  4578.8  227.63  4684.1  224.43  4788.9  221.15
  4852.7  219.18  4960.0  216.61  4986.2  216.60  4998.8  215.85  5006.3  215.70
  5006.5  215.20  5010.0  215.20  5010.3  215.70  5068.4  215.88  5100.3  215.92
  5107.9  216.94  5112.4  216.78  5157.3  216.77  5284.5  220.27  5320.6  220.81
  5362.3  222.37  5568.3  226.47  5646.1  228.55  5738.2  230.00  5765.4  229.90
#Mann=10,-1,0
  4323.3    0.04       0  4578.8    0.03       0  4684.1    0.04       0
  4788.9   0.013       0  4852.7    0.03       0  4998.8   0.013       0
  5006.3    0.03       0  5010.3   0.013       0  5068.4    0.12       0
  5112.4    0.04       0
Bank Sta=5006.3,5010.3
Exp/Cntr=0.3,0.1

Type RM Length L Ch R = 1,7037,420,420,420
BEGIN DESCRIPTION:
Mapping XS 453b3562
END DESCRIPTION:
XS GIS Cut Line= 3
      2490053.74     13510228.21      2490603.25     13509983.41
      2491228.02     13509769.94
#Sta/Elev= 30
  4366.4  231.33  4466.3  229.27  4489.3  229.56  4530.3  227.22  4564.8  226.09
  4597.7  226.29  4641.5  223.58  4674.3  223.02  4696.2  223.70  4755.8  220.11
  4779.0  219.41  4807.7  219.60  4854.2  216.64  4900.7  216.70  4915.1  215.86
  4929.4  216.12  4966.2  214.68  5008.1  214.08  5060.4  214.12  5147.5  213.31
  5147.7  212.81  5151.2  212.81  5151.5  213.31  5360.0  216.09  5401.1  216.77
  5465.0  217.87  5472.6  218.10  5477.9  219.09  5529.9  219.47  5628.2  221.72
#Mann=7,-1,0
  4366.4    0.04       0  5060.4   0.013       0  5147.5    0.04       0
  5151.5   0.013       0  5360.0    0.03       0  5401.1   0.013       0
  5465.0    0.03       0
Bank Sta=5147.5,5151.5
Exp/Cntr=0.3,0.1

Type RM Length L Ch R = 1,6617,394,394,394
BEGIN DESCRIPTION:
Mapping XS 732efa84
END DESCRIPTION:
XS GIS Cut Line= 3
      2490329.77     13510301.12      2490973.04     13510163.09
      2491272.51     13509819.36
#Sta/Elev= 30
  4313.7  225.12  4365.9  223.52  4390.6  224.46  4441.8  221.65  4472.5  220.72
  4492.9  221.64  4544.1  218.81  4553.3  219.70  4564.5  218.79  4574.7  218.69
  4585.0  219.68  4595.2  219.83  4607.8  219.25  4615.6  218.26  4636.1  217.80
  4652.1  216.59  4758.8  215.48  5005.4  208.90  5005.7  208.40  5009.2  208.40
  5009.4  208.90  5035.4  209.88  5169.8  212.23  5247.6  215.27  5290.3  216.02
  5326.4  218.40  5361.6  219.86  5386.9  220.12  5424.0  220.71  5427.5  220.64
#Mann=5,-1,0
  4313.7    0.04       0  5005.4    0.04       0  5009.4    0.04       0
  5386.9    0.03       0  5424.0    0.04       0
Bank Sta=5005.4,5009.4
Exp/Cntr=0.3,0.1

Type RM Length L Ch R = 1,6223,157,157,157
BEGIN DESCRIPTION:
TRIB 6 TO FIFTEENMILE CREEK 12.0
END DESCRIPTION:
XS GIS Cut Line= 3
      2490675.02     13510375.00      2491275.00     13510375.00
      2491325.00     13509974.99
#Sta/Elev= 30
  4396.4  216.94  4426.4  214.96  4456.4  214.07  4526.4  213.24  4566.4  211.61
  4626.4  210.74  4666.4  209.73  4686.4  208.72  4756.4  208.45  4776.4  207.29
  4786.4  207.75  4806.4  207.65  4936.4  206.01  4984.4  203.96  4984.6  203.46
  4988.1  203.46  4988.4  203.96  5006.5  205.35  5056.8  206.07  5066.9  206.84
  5077.0  205.57  5087.1  205.16  5097.2  205.44  5208.0  209.72  5218.1  210.62
  5228.2  209.86  5238.2  209.82  5248.3  210.94  5258.4  211.39  5399.5  216.40
#Mann=3,-1,0
  4396.4    0.04       0  4984.4    0.04       0  4988.4    0.04       0
Bank Sta=4984.4,4988.4
Exp/Cntr=0.3,0.1

Type RM Length L Ch R = 1,6066,116,116,116
BEGIN DESCRIPTION:
4848
END DESCRIPTION:
XS GIS Cut Line= 4
      2490757.00     13510604.81      2491218.99     13510589.24
      2491405.87     13510428.31      2491421.39     13509978.36
#Sta/Elev= 30
  4220.5  213.43  4298.5  212.49  4318.6  212.89  4363.4  210.95  4428.6  209.65
  4478.7  207.84  4498.7  208.00  4598.7  205.69  4678.3  204.57  4789.3  204.68
  4803.5  203.75  4808.1  202.87  4808.4  202.37  4811.9  202.37  4812.1  202.87
  4817.8  202.98  4824.4  204.22  4832.0  204.89  4874.8  204.23  5022.7  204.10
  5032.8  204.80  5042.8  204.57  5072.8  205.71  5092.8  207.16  5102.8  205.86
  5112.8  205.49  5122.8  206.71  5132.8  207.28  5302.9  213.21  5379.6  215.11
#Mann=3,-1,0
  4220.5    0.04       0  4808.1    0.04       0  4812.1    0.04       0
Bank Sta=4808.1,4812.1
Exp/Cntr=0.3,0.1

Type RM Length L Ch R = 1,5950,257,257,257
BEGIN DESCRIPTION:
Mapping XS 8a7cd44b
END DESCRIPTION:
XS GIS Cut Line= 4
      2490316.74     13510704.76      2491327.21     13510759.45
      2491530.33     13510644.86      2491501.71     13509939.60
#Sta/Elev= 30
  3484.5  221.96  3512.8  222.26  3579.7  219.49  3609.6  220.05  3673.0  217.30
  3714.6  217.02  3753.1  218.41  3773.2  217.13  3913.4  214.86  4053.6  213.74
  4304.0  207.05  4585.8  203.47  4594.3  203.09  4600.0  200.70  4606.7  199.33
  4607.0  198.83  4610.7  199.33  4616.0  201.54  4621.7  202.30  4643.3  202.92
  4653.5  201.97  4718.5  201.10  4849.6  201.40  4969.7  203.04  5049.8  202.80
  5089.8  203.79  5149.9  206.98  5169.9  205.39  5233.0  208.89  5435.5  214.79
#Mann=5,-1,0
  3484.5    0.04       0  3609.6    0.03       0  3714.6    0.04       0
  4606.7    0.04       0  4610.7    0.04       0
Bank Sta=4606.7,4610.7
Exp/Cntr=0.3,0.1

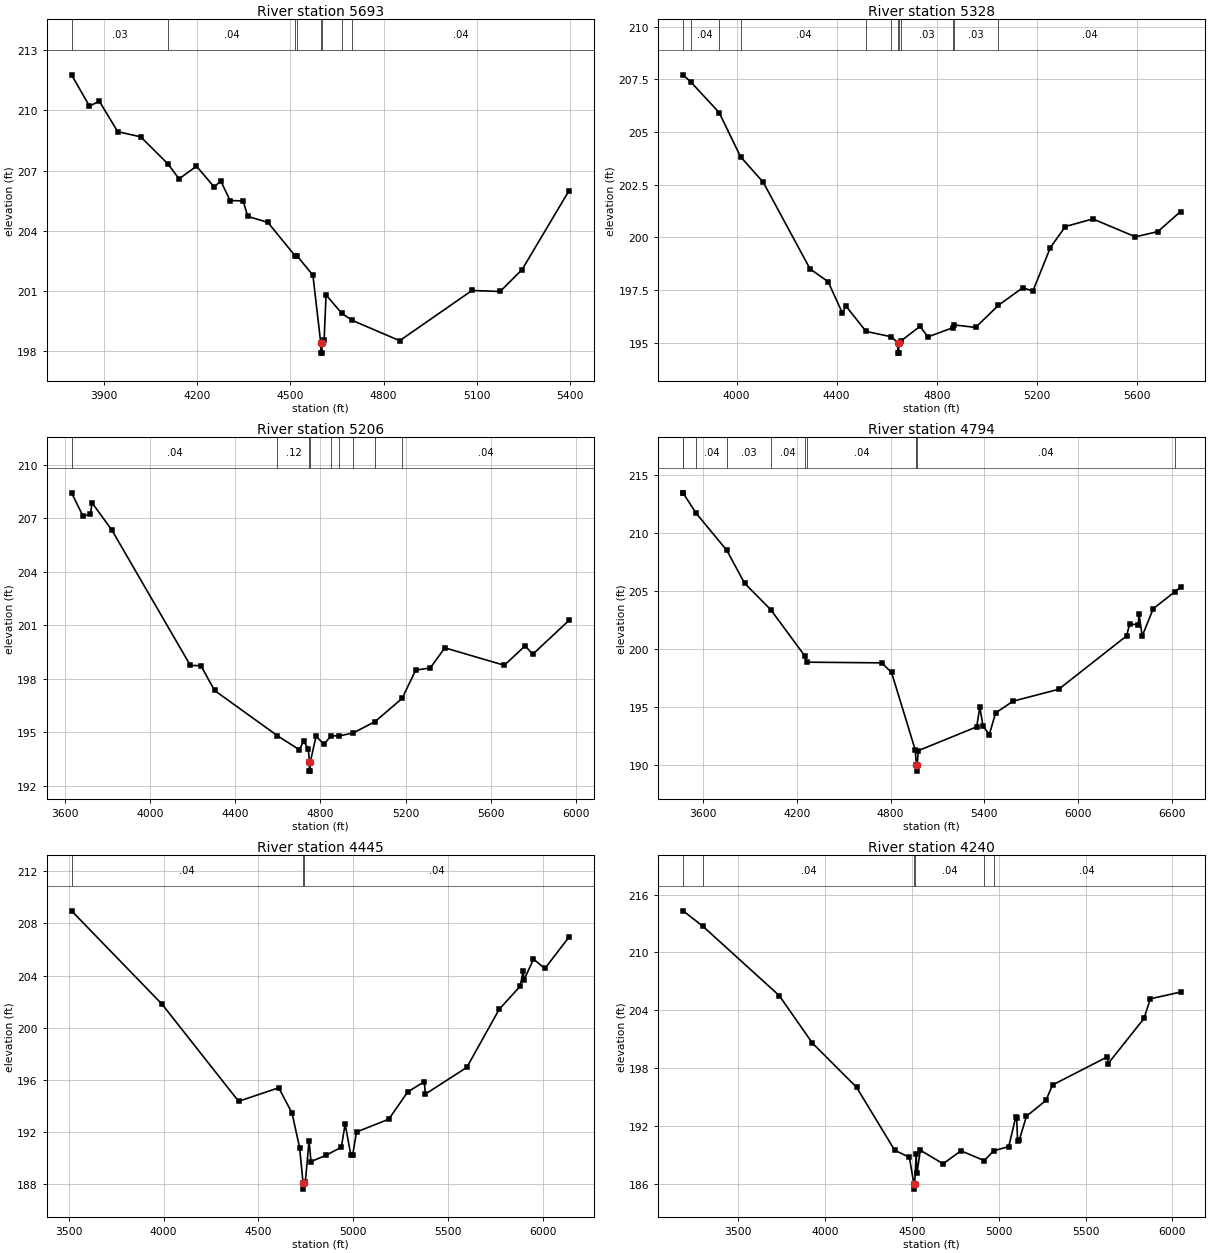
Type RM Length L Ch R = 1,5693,365,365,365
BEGIN DESCRIPTION:
TRIB 6 TO FIFTEENMILE CREEK 10.0
END DESCRIPTION:
XS GIS Cut Line= 4
      2490788.08     13511123.94      2491149.65     13511040.61
      2491732.86     13510645.77      2491675.00     13510125.02
#Sta/Elev= 30
  3796.8  211.77  3854.5  210.21  3886.0  210.46  3945.2  208.94  4019.4  208.68
  4106.2  207.34  4142.6  206.59  4198.5  207.22  4255.5  206.18  4276.5  206.49
  4306.4  205.51  4348.4  205.49  4363.3  204.72  4427.9  204.42  4515.9  202.75
  4523.0  202.73  4572.8  201.79  4598.0  198.41  4598.3  197.91  4601.8  197.91
  4602.0  198.41  4608.9  198.58  4615.0  200.81  4665.6  199.89  4699.4  199.54
  4851.7  198.53  5084.2  201.03  5174.8  200.98  5245.2  202.07  5396.1  206.00
#Mann=8,-1,0
  3796.8    0.03       0  4106.2    0.04       0  4515.9    0.03       0
  4523.0    0.04       0  4598.0    0.04       0  4602.0    0.04       0
  4665.6    0.03       0  4699.4    0.04       0
Bank Sta=4598,4602
Exp/Cntr=0.3,0.1

Type RM Length L Ch R = 1,5328,122,122,122
BEGIN DESCRIPTION:
4847
END DESCRIPTION:
XS GIS Cut Line= 4
      2490902.32     13511290.05      2491753.68     13511155.08
      2491904.23     13510739.78      2491899.03     13510054.54
#Sta/Elev= 30
  3785.9  207.72  3817.8  207.37  3930.0  205.93  4015.8  203.83  4106.5  202.62
  4293.5  198.51  4365.9  197.90  4423.1  196.41  4436.6  196.75  4517.8  195.54
  4617.7  195.29  4644.0  195.01  4644.3  194.51  4647.8  194.51  4648.0  195.01
  4657.4  195.09  4733.1  195.78  4765.0  195.28  4865.0  195.72  4868.8  195.85
  4955.5  195.73  5046.9  196.78  5144.4  197.62  5184.4  197.45  5254.4  199.52
  5314.4  200.52  5424.4  200.88  5594.4  200.03  5684.4  200.28  5774.9  201.23
#Mann=12,-1,0
  3785.9    0.03       0  3817.8    0.04       0  3930.0    0.03       0
  4015.8    0.04       0  4517.8    0.03       0  4617.7    0.12       0
  4644.0    0.03       0  4648.0    0.12       0  4657.4    0.03       0
  4865.0    0.04       0  4868.8    0.03       0  5046.9    0.04       0
Bank Sta=4644,4648
Exp/Cntr=0.3,0.1

Type RM Length L Ch R = 1,5206,412,412,412
BEGIN DESCRIPTION:
Mapping XS 5a3d2e1f
END DESCRIPTION:
XS GIS Cut Line= 4
      2491018.19     13511863.61      2491887.97     13511124.03
      2492070.26     13510582.36      2491919.85     13509980.70
#Sta/Elev= 30
  3632.5  208.44  3685.9  207.14  3721.0  207.23  3728.7  207.88  3821.0  206.36
  4190.0  198.75  4239.4  198.74  4303.1  197.35  4598.0  194.81  4700.7  194.02
  4721.5  194.51  4743.5  194.04  4748.1  193.32  4748.3  192.82  4751.8  192.82
  4752.1  193.32  4779.5  194.78  4816.3  194.33  4850.2  194.80  4889.1  194.80
  4953.3  194.96  5056.1  195.60  5183.0  196.90  5246.8  198.49  5315.1  198.61
  5383.6  199.74  5662.5  198.76  5759.8  199.85  5795.9  199.38  5965.9  201.28
#Mann=9,-1,0
  3632.5    0.04       0  4598.0    0.12       0  4748.1    0.04       0
  4752.1    0.12       0  4850.2    0.04       0  4889.1    0.12       0
  4953.3    0.04       0  5056.1    0.03       0  5183.0    0.04       0
Bank Sta=4748.1,4752.1
Exp/Cntr=0.3,0.1

Type RM Length L Ch R = 1,4794,349,349,349
BEGIN DESCRIPTION:
Mapping XS d114a713
END DESCRIPTION:
XS GIS Cut Line= 3
      2491325.47     13512170.91      2492299.43     13511306.32
      2492054.64     13509441.77
#Sta/Elev= 30
  3472.0  213.44  3473.3  213.40  3555.1  211.69  3752.2  208.47  3865.4  205.64
  4032.9  203.36  4252.5  199.34  4262.2  198.83  4743.5  198.77  4805.9  197.94
  4957.2  191.27  4965.3  189.93  4965.6  189.43  4969.3  189.93  4977.4  191.20
  5350.6  193.25  5370.7  194.95  5390.9  193.32  5431.3  192.58  5471.6  194.45
  5582.5  195.46  5875.0  196.49  6310.1  201.10  6328.9  202.12  6383.8  202.06
  6389.4  202.97  6409.6  201.08  6480.2  203.44  6617.7  204.90  6654.9  205.29
#Mann=10,-1,0
  3472.0    0.04       0  3473.3    0.03       0  3555.1    0.04       0
  3752.2    0.03       0  4032.9    0.04       0  4252.5    0.03       0
  4262.2    0.04       0  4965.3    0.04       0  4969.3    0.04       0
  6617.7   0.013       0
Bank Sta=4965.3,4969.3
Exp/Cntr=0.3,0.1

Type RM Length L Ch R = 1,4445,205,205,205
BEGIN DESCRIPTION:
4846
END DESCRIPTION:
XS GIS Cut Line= 4
      2491748.51     13512032.36      2492433.73     13511414.63
      2492454.49     13510521.75      2492376.76     13509718.58
#Sta/Elev= 30
  3514.8  208.96  3992.1  201.80  4395.7  194.36  4607.0  195.40  4677.1  193.46
  4717.1  190.81  4735.1  188.13  4735.3  187.63  4739.1  188.13  4747.1  188.15
  4767.1  191.35  4777.1  189.74  4857.1  190.23  4937.1  190.84  4957.1  192.62
  4987.1  190.26  4997.1  190.27  5017.1  192.01  5187.2  192.99  5287.2  195.08
  5374.8  195.87  5379.8  194.91  5598.5  196.96  5769.3  201.41  5879.8  203.18
  5895.5  204.35  5900.5  203.67  5950.1  205.26  6010.4  204.54  6137.4  206.95
#Mann=3,-1,0
  3514.8    0.04       0  4735.1    0.04       0  4739.1    0.04       0
Bank Sta=4735.1,4739.1
Exp/Cntr=0.3,0.1

Type RM Length L Ch R = 1,4240,635,635,635
BEGIN DESCRIPTION:
Mapping XS e4952227
END DESCRIPTION:
XS GIS Cut Line= 3
      2491762.94     13512285.52      2492721.30     13511353.20
      2492429.82     13509854.11
#Sta/Elev= 30
  3182.6  214.32  3297.1  212.71  3736.0  205.53  3926.9  200.60  4181.5  196.01
  4400.7  189.48  4485.6  188.74  4511.9  185.94  4512.1  185.44  4515.9  185.94
  4524.7  189.05  4529.8  187.12  4548.4  189.48  4679.7  188.07  4782.7  189.42
  4916.5  188.40  4971.4  189.42  5057.7  189.86  5098.1  192.92  5103.2  192.85
  5108.7  190.42  5118.9  190.57  5159.9  193.01  5271.7  194.64  5309.8  196.25
  5624.9  199.16  5630.0  198.47  5836.7  203.16  5872.7  205.19  6046.8  205.89
#Mann=6,-1,0
  3182.6    0.03       0  3297.1    0.04       0  4511.9    0.04       0
  4515.9    0.04       0  4916.5    0.05       0  4971.4    0.04       0
Bank Sta=4511.9,4515.9
Exp/Cntr=0.3,0.1

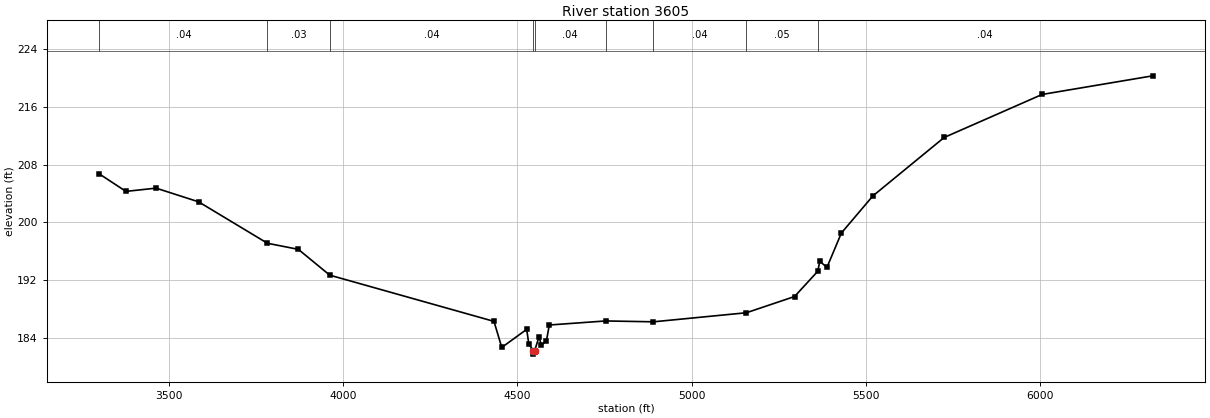
Type RM Length L Ch R = 1,3605,0,0,0
BEGIN DESCRIPTION:
Mapping XS 578c3961
END DESCRIPTION:
XS GIS Cut Line= 3
      2492346.29     13512462.59      2493207.39     13511231.38
      2492832.49     13509759.53
#Sta/Elev= 30
  3301.4  206.70  3377.7  204.29  3464.1  204.74  3586.1  202.85  3783.6  197.13
  3872.2  196.29  3962.2  192.73  4433.3  186.35  4455.6  182.75  4527.1  185.25
  4533.2  183.21  4546.0  182.33  4546.2  181.83  4550.0  182.33  4562.8  184.25
  4568.9  183.04  4583.7  183.67  4592.0  185.85  4753.6  186.41  4890.8  186.29
  5157.1  187.54  5295.4  189.78  5362.0  193.27  5367.7  194.65  5388.3  193.80
  5429.6  198.54  5519.9  203.66  5724.4  211.73  6005.5  217.67  6322.7  220.24
#Mann=9,-1,0
  3301.4    0.04       0  3783.6    0.03       0  3962.2    0.04       0
  4546.0    0.04       0  4550.0    0.04       0  4753.6    0.05       0
  4890.8    0.04       0  5157.1    0.05       0  5362.0    0.04       0
Bank Sta=4546,4550
Exp/Cntr=0.3,0.1

Chan Stop Cuts=-1