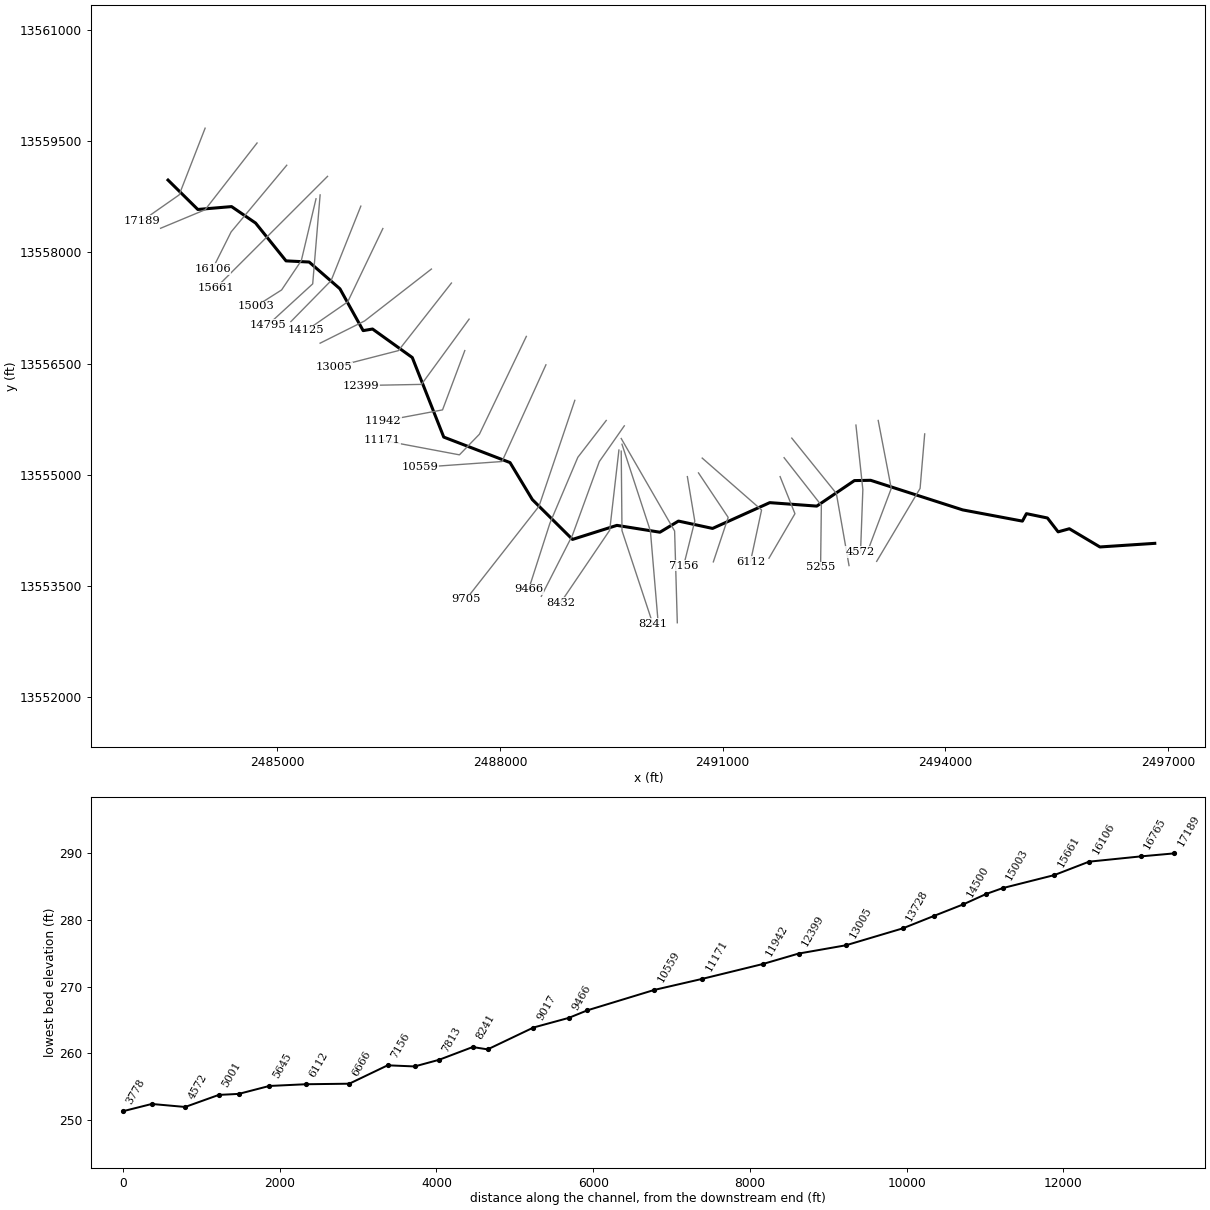
--- TRIB 6 TO FIVEMILE CREEK.prj (project) ---

Proj Title=TRIB 6 TO FIVEMILE CREEK Base Level Engineering
Current Plan=p01
Default Exp/Contr=0.3,0.1
English Units
Geom File=g01
Flow File=f01
Plan File=p01
BEGIN DESCRIPTION:
TRIB 6 TO FIVEMILE CREEK
END DESCRIPTION:

--- TRIB 6 TO FIVEMILE CREEK.p01 (plan) ---

Plan Title=Multiple Run
Short Identifier=Multiple
Geom File=g01
Flow File=f01
Subcritical Flow
K Sum by GR= 0
Std Step Tol= 0.01
Critical Tol= 0.01
Num of Std Step Trials= 20
Max Error Tol= 0.3
Flow Tol Ratio= 0.001
Split Flow NTrial= 30
Split Flow Tol= 0.02
Split Flow Ratio= 0.02
Log Output Level= 0
Friction Slope Method= 1
Unsteady Friction Slope Method= 2
Unsteady Bridges Friction Slope Method= 1
Parabolic Critical Depth
Global Vel Dist=  1 , 1 , 1
Global Log Level= 0
CheckData=True
Encroach Param= -1, 0, 0, 0
BEGIN DESCRIPTION:
Multiple Run
END DESCRIPTION:

--- TRIB 6 TO FIVEMILE CREEK.f01 (steady flow) ---

Flow Title=Multiple
Number of Profiles=7
Profile Names=10-year,25-year,50-year,1pct_min,100-year,1pct_plu,500-year
River Rch & RM= TRIB 6 TO FIVEMI,Reach-1,17189
     678    1097    1478     964    1924    3839    3229
River Rch & RM= TRIB 6 TO FIVEMI,Reach-1,12399
     765    1245    1681    1099    2192    4374    3694
River Rch & RM= TRIB 6 TO FIVEMI,Reach-1,9017
    1286    2149    2954    1962    3915    7812    6817
River Rch & RM= TRIB 6 TO FIVEMI,Reach-1,5645
    1342    2242    3081    2045    4080    8141    7095
River Rch & RM= TRIB 6 TO FIVEMI,Reach-1,2225
    1401    2340    3216    2134    4259    8497    7402
Boundary for River Rch & Prof#=TRIB 6 TO FIVEMI,Reach-1,1
Up Type=0
Dn Type=3
Dn Slope=0.005
Boundary for River Rch & Prof#=TRIB 6 TO FIVEMI,Reach-1,2
Up Type=0
Dn Type=3
Dn Slope=0.005
Boundary for River Rch & Prof#=TRIB 6 TO FIVEMI,Reach-1,3
Up Type=0
Dn Type=3
Dn Slope=0.005
Boundary for River Rch & Prof#=TRIB 6 TO FIVEMI,Reach-1,4
Up Type=0
Dn Type=3
Dn Slope=0.005
Boundary for River Rch & Prof#=TRIB 6 TO FIVEMI,Reach-1,5
Up Type=0
Dn Type=3
Dn Slope=0.005
Boundary for River Rch & Prof#=TRIB 6 TO FIVEMI,Reach-1,6
Up Type=0
Dn Type=3
Dn Slope=0.005
Boundary for River Rch & Prof#=TRIB 6 TO FIVEMI,Reach-1,7
Up Type=0
Dn Type=3
Dn Slope=0.005

--- TRIB 6 TO FIVEMILE CREEK.g01 (geometry) ---

Geom Title=Existing Conditions

River Reach=TRIB 6 TO FIVEMI,Reach-1
Reach XY= 30
      2483525.00     13558975.00      2483926.50     13558578.61
      2484381.47     13558617.31      2484705.23     13558395.41
      2485115.30     13557885.20      2485427.45     13557869.53
      2485842.05     13557508.50      2486154.87     13556944.42
      2486281.73     13556965.85      2486817.25     13556581.46
      2487241.44     13555508.21      2488134.79     13555164.48
      2488435.52     13554665.21      2488976.63     13554128.12
      2489575.00     13554317.44      2490154.97     13554225.06
      2490404.80     13554375.37      2490864.50     13554276.20
      2491635.48     13554624.06      2492269.06     13554577.26
      2492776.46     13554921.46      2492995.15     13554925.36
      2494235.50     13554526.22      2495040.89     13554374.85
      2495095.16     13554475.44      2495378.32     13554416.96
      2495522.16     13554230.09      2495673.37     13554271.87
      2496085.51     13554026.22      2496825.00     13554075.00

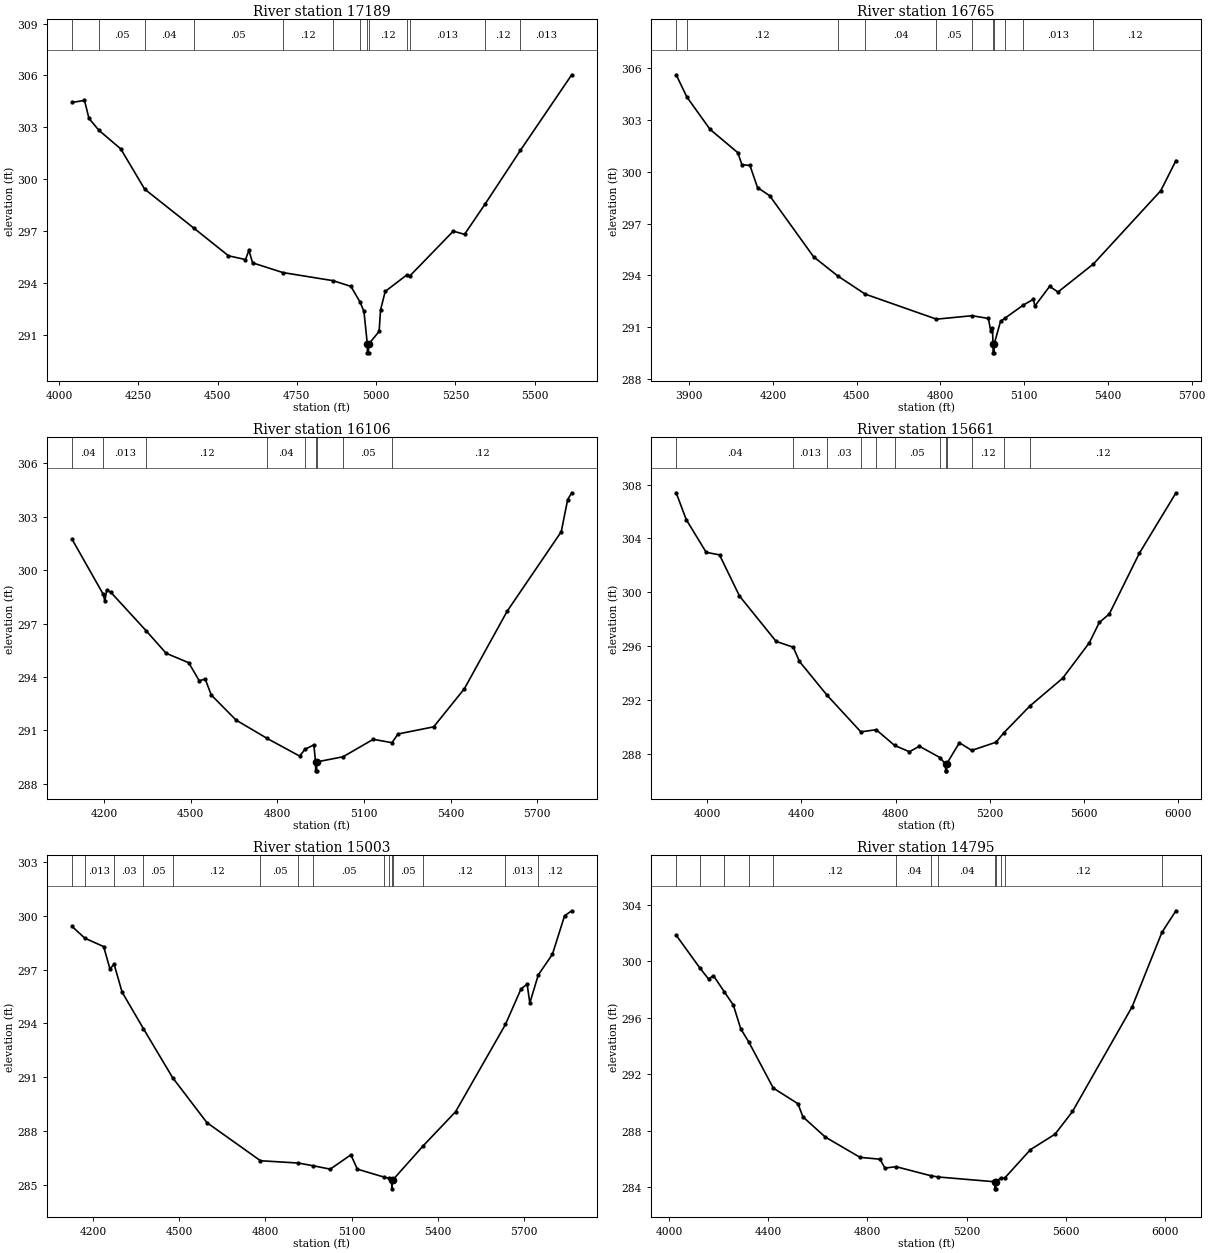
Type RM Length L Ch R = 1,17189,424,424,424
BEGIN DESCRIPTION:
TRIB 6 TO FIVEMILE CREEK 31.0
END DESCRIPTION:
XS GIS Cut Line= 3
      2484025.00     13559674.99      2483675.00     13558775.00
      2483174.98     13558424.99
#Sta/Elev= 30
  4041.0  304.44  4080.5  304.56  4094.6  303.52  4126.0  302.83  4194.7  301.76
  4270.3  299.43  4425.2  297.18  4534.5  295.58  4588.2  295.36  4598.9  295.89
  4610.8  295.17  4705.9  294.61  4864.5  294.14  4920.8  293.81  4949.6  292.90
  4961.8  292.36  4972.5  290.47  4972.7  289.97  4976.2  289.97  4976.5  290.47
  5009.7  291.21  5014.1  292.45  5028.9  293.52  5096.8  294.47  5105.8  294.40
  5243.4  297.00  5279.1  296.82  5344.2  298.58  5455.1  301.67  5617.0  306.04
#Mann=13,-1,0
  4041.0    0.04       0  4126.0    0.05       0  4270.3    0.04       0
  4425.2    0.05       0  4705.9    0.12       0  4864.5    0.05       0
  4949.6    0.12       0  4972.5    0.05       0  4976.5    0.12       0
  5096.8    0.12       0  5105.8   0.013       0  5344.2    0.12       0
  5455.1   0.013       0
Bank Sta=4972.5,4976.5
Exp/Cntr=0.3,0.1

Type RM Length L Ch R = 1,16765,659,659,659
BEGIN DESCRIPTION:
TRIB 6 TO FIVEMILE CREEK 30.0
END DESCRIPTION:
XS GIS Cut Line= 3
      2484725.00     13559475.00      2484025.00     13558575.00
      2483424.98     13558324.99
#Sta/Elev= 30
  3853.5  305.62  3891.9  304.33  3974.8  302.46  4074.3  301.11  4088.8  300.42
  4117.7  300.37  4144.9  299.09  4188.3  298.62  4345.8  295.08  4432.5  293.97
  4530.6  292.92  4785.9  291.47  4913.6  291.67  4972.0  291.51  4980.1  290.79
  4986.4  290.95  4988.5  290.02  4988.8  289.52  4992.3  289.52  4992.5  290.02
  5015.3  291.34  5032.5  291.54  5096.3  292.28  5132.9  292.62  5138.3  292.23
  5191.4  293.37  5221.2  293.04  5348.4  294.67  5589.5  298.91  5643.7  300.65
#Mann=11,-1,0
  3853.5    0.04       0  3891.9    0.12       0  4432.5    0.05       0
  4530.6    0.04       0  4785.9    0.05       0  4913.6    0.12       0
  4988.5    0.05       0  4992.5    0.12       0  5032.5    0.05       0
  5096.3   0.013       0  5348.4    0.12       0
Bank Sta=4988.5,4992.5
Exp/Cntr=0.3,0.1

Type RM Length L Ch R = 1,16106,445,445,445
BEGIN DESCRIPTION:
TRIB 6 TO FIVEMILE CREEK 29.0
END DESCRIPTION:
XS GIS Cut Line= 3
      2485125.03     13559175.04      2484375.00     13558275.00
      2484125.00     13557775.00
#Sta/Elev= 30
  4088.9  301.74  4196.9  298.65  4202.8  298.26  4209.4  298.90  4223.7  298.75
  4345.5  296.60  4415.0  295.33  4493.1  294.80  4529.6  293.79  4550.4  293.88
  4571.2  292.99  4657.1  291.58  4764.8  290.55  4877.1  289.56  4896.2  289.94
  4926.6  290.19  4932.4  289.23  4932.7  288.73  4936.2  288.73  4936.4  289.23
  5027.7  289.52  5132.3  290.50  5196.9  290.31  5218.2  290.80  5341.5  291.20
  5447.8  293.34  5595.9  297.69  5783.2  302.15  5805.5  303.96  5819.5  304.34
#Mann=9,-1,0
  4088.9    0.04       0  4196.9   0.013       0  4345.5    0.12       0
  4764.8    0.04       0  4896.2   0.013       0  4932.4    0.03       0
  4936.4   0.013       0  5027.7    0.05       0  5196.9    0.12       0
Bank Sta=4932.4,4936.4
Exp/Cntr=0.3,0.1

Type RM Length L Ch R = 1,15661,658,658,658
BEGIN DESCRIPTION:
TRIB 6 TO FIVEMILE CREEK 28.0
END DESCRIPTION:
XS GIS Cut Line= 3
      2485675.03     13559025.03      2484775.00     13558125.00
      2484174.98     13557524.98
#Sta/Elev= 30
  3869.0  307.40  3911.5  305.41  3996.3  302.97  4052.9  302.78  4137.7  299.72
  4293.3  296.34  4365.9  295.91  4392.3  294.85  4509.3  292.34  4652.8  289.61
  4717.9  289.77  4796.2  288.60  4859.0  288.13  4901.4  288.54  4988.4  287.70
  5012.6  287.21  5012.8  286.71  5016.3  286.71  5016.6  287.21  5071.1  288.80
  5123.6  288.23  5226.7  288.84  5258.8  289.52  5370.1  291.53  5509.5  293.60
  5622.7  296.24  5665.1  297.75  5707.5  298.38  5834.8  302.89  5990.4  307.39
#Mann=12,-1,0
  3869.0    0.04       0  4365.9   0.013       0  4509.3    0.03       0
  4652.8    0.05       0  4717.9    0.12       0  4796.2    0.05       0
  4988.4   0.013       0  5012.6    0.03       0  5016.6   0.013       0
  5123.6    0.12       0  5258.8    0.05       0  5370.1    0.12       0
Bank Sta=5012.6,5016.6
Exp/Cntr=0.3,0.1

Type RM Length L Ch R = 1,15003,208,208,208
BEGIN DESCRIPTION:
Mapping XS f517d935
END DESCRIPTION:
XS GIS Cut Line= 4
      2485519.69     13558722.45      2485321.76     13557889.07
      2485056.13     13557493.24      2484712.39     13557274.50
#Sta/Elev= 30
  4126.1  299.42  4170.8  298.76  4236.5  298.29  4258.4  297.04  4272.8  297.31
  4300.6  295.75  4374.8  293.71  4476.7  290.97  4596.0  288.46  4782.7  286.33
  4914.9  286.20  4965.9  286.05  5025.7  285.86  5097.7  286.66  5120.0  285.86
  5212.4  285.42  5229.5  285.35  5239.8  285.26  5240.0  284.76  5243.8  285.26
  5350.5  287.18  5462.4  289.07  5635.9  293.94  5690.4  295.93  5711.5  296.19
  5720.9  295.14  5750.4  296.71  5799.6  297.86  5841.9  300.01  5866.8  300.29
#Mann=15,-1,0
  4126.1    0.04       0  4170.8   0.013       0  4272.8    0.03       0
  4374.8    0.05       0  4476.7    0.12       0  4782.7    0.05       0
  4914.9    0.04       0  4965.9    0.05       0  5212.4     0.1       0
  5229.5    0.05       0  5239.8    0.05       0  5243.8    0.05       0
  5350.5    0.12       0  5635.9   0.013       0  5750.4    0.12       0
Bank Sta=5239.8,5243.8
Exp/Cntr=0.3,0.1

Type RM Length L Ch R = 1,14795,295,295,295
BEGIN DESCRIPTION:
TRIB 6 TO FIVEMILE CREEK 26.0
END DESCRIPTION:
XS GIS Cut Line= 3
      2485575.00     13558775.04      2485475.00     13557575.00
      2484875.03     13557025.03
#Sta/Elev= 30
  4027.5  301.86  4122.2  299.56  4158.0  298.76  4178.1  298.99  4221.4  297.86
  4258.3  296.91  4288.4  295.22  4320.5  294.30  4419.6  291.03  4519.2  289.92
  4539.3  288.99  4629.6  287.56  4770.1  286.12  4850.4  285.99  4870.5  285.36
  4915.3  285.46  5055.6  284.82  5085.5  284.73  5314.5  284.39  5314.7  283.89
  5318.2  283.89  5318.5  284.39  5338.9  284.67  5353.4  284.64  5458.3  286.67
  5557.3  287.76  5627.9  289.37  5869.0  296.80  5989.0  302.06  6045.6  303.59
#Mann=13,-1,0
  4027.5    0.04       0  4122.2   0.013       0  4221.4    0.03       0
  4320.5    0.05       0  4419.6    0.12       0  4915.3    0.04       0
  5055.6    0.05       0  5085.5    0.04       0  5314.5    0.04       0
  5318.5    0.04       0  5338.9     0.1       0  5353.4    0.12       0
  5989.0   0.013       0
Bank Sta=5314.5,5318.5
Exp/Cntr=0.3,0.1

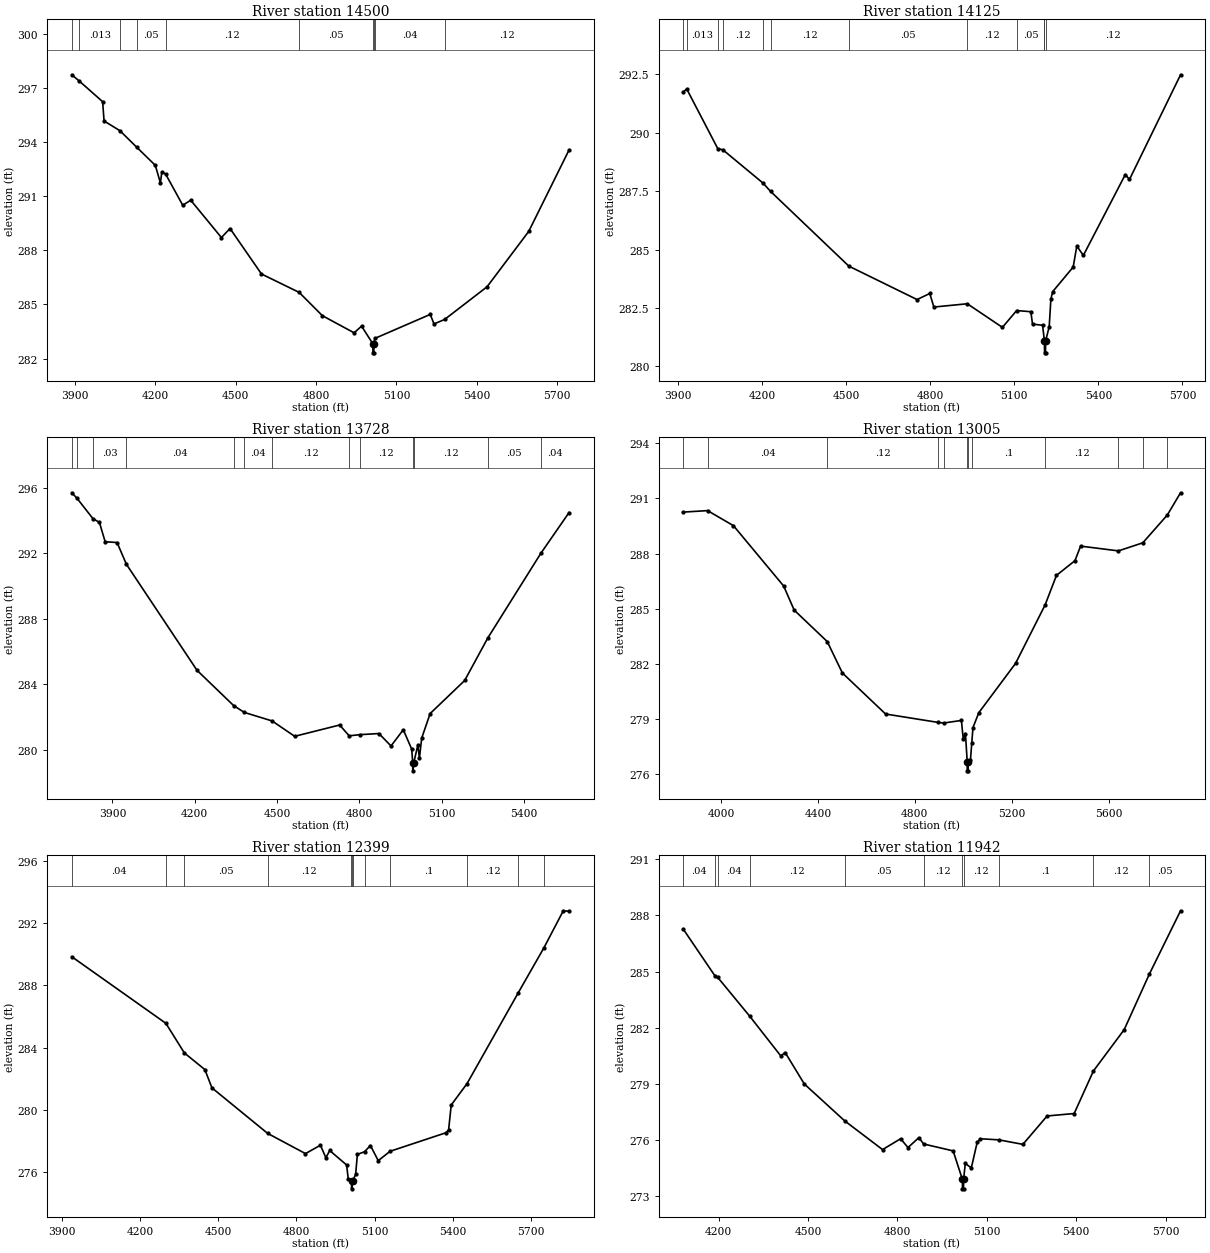
Type RM Length L Ch R = 1,14500,375,375,375
BEGIN DESCRIPTION:
Mapping XS a582dfab
END DESCRIPTION:
XS GIS Cut Line= 3
      2486123.86     13558623.49      2485722.80     13557618.24
      2485181.16     13557066.18
#Sta/Elev= 30
  3888.6  297.73  3916.5  297.38  4003.5  296.24  4008.9  295.17  4068.1  294.63
  4131.1  293.71  4200.2  292.71  4219.1  291.74  4224.5  292.34  4238.5  292.23
  4302.6  290.50  4332.3  290.78  4446.8  288.71  4479.1  289.21  4596.4  286.69
  4737.1  285.67  4823.7  284.38  4942.1  283.43  4970.0  283.80  5012.1  282.82
  5012.4  282.32  5015.9  282.32  5016.1  282.82  5019.6  283.12  5226.3  284.45
  5240.4  283.92  5280.0  284.17  5438.3  285.98  5593.9  289.05  5744.3  293.56
#Mann=10,-1,0
  3888.6    0.12       0  3916.5   0.013       0  4068.1    0.12       0
  4131.1    0.05       0  4238.5    0.12       0  4737.1    0.05       0
  5012.1    0.05       0  5016.1    0.05       0  5019.6    0.04       0
  5280.0    0.12       0
Bank Sta=5012.1,5016.1
Exp/Cntr=0.3,0.1

Type RM Length L Ch R = 1,14125,397,397,397
BEGIN DESCRIPTION:
Mapping XS e5d19b2e
END DESCRIPTION:
XS GIS Cut Line= 3
      2486420.72     13558321.36      2485946.76     13557331.78
      2485389.72     13556946.54
#Sta/Elev= 30
  3918.9  291.75  3931.0  291.87  4041.7  289.32  4059.8  289.27  4203.7  287.84
  4230.0  287.49  4509.6  284.29  4753.0  282.86  4798.3  283.12  4813.0  282.54
  4932.2  282.68  5057.6  281.67  5108.4  282.39  5159.0  282.34  5165.1  281.81
  5200.9  281.76  5206.8  281.17  5207.7  281.08  5207.9  280.58  5211.4  280.58
  5211.7  281.08  5224.6  281.70  5230.6  282.88  5237.1  283.20  5310.1  284.25
  5323.2  285.15  5346.5  284.75  5496.2  288.21  5511.1  288.00  5693.4  292.48
#Mann=12,-1,0
  3918.9    0.12       0  3931.0   0.013       0  4041.7    0.05       0
  4059.8    0.12       0  4203.7    0.05       0  4230.0    0.12       0
  4509.6    0.05       0  4932.2    0.12       0  5108.4    0.05       0
  5206.8    0.12       0  5207.7    0.05       0  5211.7    0.12       0
Bank Sta=5207.7,5211.7
Exp/Cntr=0.3,0.1

Type RM Length L Ch R = 1,13728,723,723,723
BEGIN DESCRIPTION:
TRIB 6 TO FIVEMILE CREEK 24.0
END DESCRIPTION:
XS GIS Cut Line= 3
      2487075.04     13557775.03      2486175.00     13557075.00
      2485575.04     13556775.02
#Sta/Elev= 30
  3752.3  295.71  3770.8  295.38  3829.2  294.13  3852.8  293.90  3873.6  292.72
  3917.0  292.67  3951.1  291.34  4208.4  284.86  4341.5  282.71  4380.3  282.29
  4481.6  281.77  4564.0  280.83  4727.8  281.52  4762.4  280.86  4801.5  280.93
  4870.8  281.00  4914.9  280.24  4959.6  281.23  4990.4  280.04  4993.9  279.22
  4994.2  278.72  4997.9  279.22  5012.7  280.31  5018.3  279.49  5026.7  280.72
  5057.4  282.22  5183.2  284.24  5267.1  286.83  5460.6  292.01  5563.3  294.50
#Mann=13,-1,0
  3752.3    0.03       0  3770.8    0.04       0  3829.2    0.03       0
  3951.1    0.04       0  4341.5    0.05       0  4380.3    0.04       0
  4481.6    0.12       0  4762.4    0.05       0  4801.5    0.12       0
  4993.9    0.05       0  4997.9    0.12       0  5267.1    0.05       0
  5460.6    0.04       0
Bank Sta=4993.9,4997.9
Exp/Cntr=0.3,0.1

Type RM Length L Ch R = 1,13005,606,606,606
BEGIN DESCRIPTION:
Mapping XS 9181575c
END DESCRIPTION:
XS GIS Cut Line= 3
      2487344.97     13557585.96      2486630.43     13556674.68
      2485765.75     13556452.03
#Sta/Elev= 30
  3845.2  290.26  3945.1  290.34  4051.9  289.52  4258.9  286.24  4302.3  284.93
  4438.7  283.22  4501.2  281.51  4679.3  279.28  4897.6  278.82  4918.8  278.79
  4992.1  278.93  4999.8  277.91  5008.8  278.22  5016.0  276.69  5016.2  276.19
  5019.7  276.19  5020.0  276.69  5029.5  276.79  5034.8  277.69  5039.8  278.54
  5063.8  279.35  5215.4  282.03  5337.3  285.21  5384.3  286.82  5460.6  287.62
  5483.8  288.41  5639.7  288.15  5740.5  288.59  5841.4  290.10  5896.1  291.31
#Mann=12,-1,0
  3845.2    0.03       0  3945.1    0.04       0  4438.7    0.12       0
  4897.6    0.05       0  4918.8    0.12       0  5016.0    0.05       0
  5020.0    0.12       0  5034.8     0.1       0  5337.3    0.12       0
  5639.7    0.04       0  5740.5    0.05       0  5841.4    0.04       0
Bank Sta=5016,5020
Exp/Cntr=0.3,0.1

Type RM Length L Ch R = 1,12399,457,457,457
BEGIN DESCRIPTION:
Mapping XS 53837921
END DESCRIPTION:
XS GIS Cut Line= 3
      2487583.14     13557099.27      2486941.09     13556219.05
      2486123.05     13556203.51
#Sta/Elev= 30
  3938.6  289.83  4299.4  285.56  4370.3  283.66  4449.1  282.59  4476.1  281.42
  4689.7  278.50  4835.1  277.20  4892.5  277.74  4913.4  276.93  4928.0  277.40
  4992.9  276.47  4999.1  275.59  5010.3  275.53  5011.8  275.44  5012.0  274.94
  5015.8  275.44  5027.5  275.86  5034.2  277.15  5061.6  277.32  5084.2  277.72
  5114.2  276.75  5159.9  277.35  5374.3  278.54  5384.3  278.73  5394.3  280.32
  5454.9  281.69  5651.5  287.52  5749.8  290.40  5824.3  292.78  5846.3  292.75
#Mann=12,-1,0
  3938.6    0.04       0  4299.4    0.12       0  4370.3    0.05       0
  4689.7    0.12       0  5010.3    0.05       0  5011.8    0.05       0
  5015.8    0.05       0  5061.6    0.12       0  5159.9     0.1       0
  5454.9    0.12       0  5651.5    0.04       0  5749.8    0.05       0
Bank Sta=5011.8,5015.8
Exp/Cntr=0.3,0.1

Type RM Length L Ch R = 1,11942,771,771,771
BEGIN DESCRIPTION:
TRIB 6 TO FIVEMILE CREEK 20.0
END DESCRIPTION:
XS GIS Cut Line= 3
      2487525.01     13556675.01      2487225.00     13555875.00
      2486424.96     13555724.99
#Sta/Elev= 30
  4081.7  287.26  4188.4  284.75  4197.3  284.68  4303.7  282.62  4408.3  280.49
  4423.5  280.66  4487.6  278.98  4622.9  277.01  4750.1  275.47  4810.6  276.05
  4835.5  275.58  4872.0  276.11  4887.9  275.77  4987.0  275.40  5018.1  273.87
  5018.3  273.37  5021.8  273.37  5022.1  273.87  5027.7  274.73  5048.0  274.49
  5067.5  275.85  5078.6  276.05  5141.1  275.99  5221.0  275.75  5302.4  277.27
  5393.1  277.40  5457.8  279.68  5561.0  281.89  5645.6  284.87  5750.1  288.25
#Mann=11,-1,0
  4081.7    0.04       0  4188.4    0.05       0  4197.3    0.04       0
  4303.7    0.12       0  4622.9    0.05       0  4887.9    0.12       0
  5018.1    0.05       0  5022.1    0.12       0  5141.1     0.1       0
  5457.8    0.12       0  5645.6    0.05       0
Bank Sta=5018.1,5022.1
Exp/Cntr=0.3,0.1

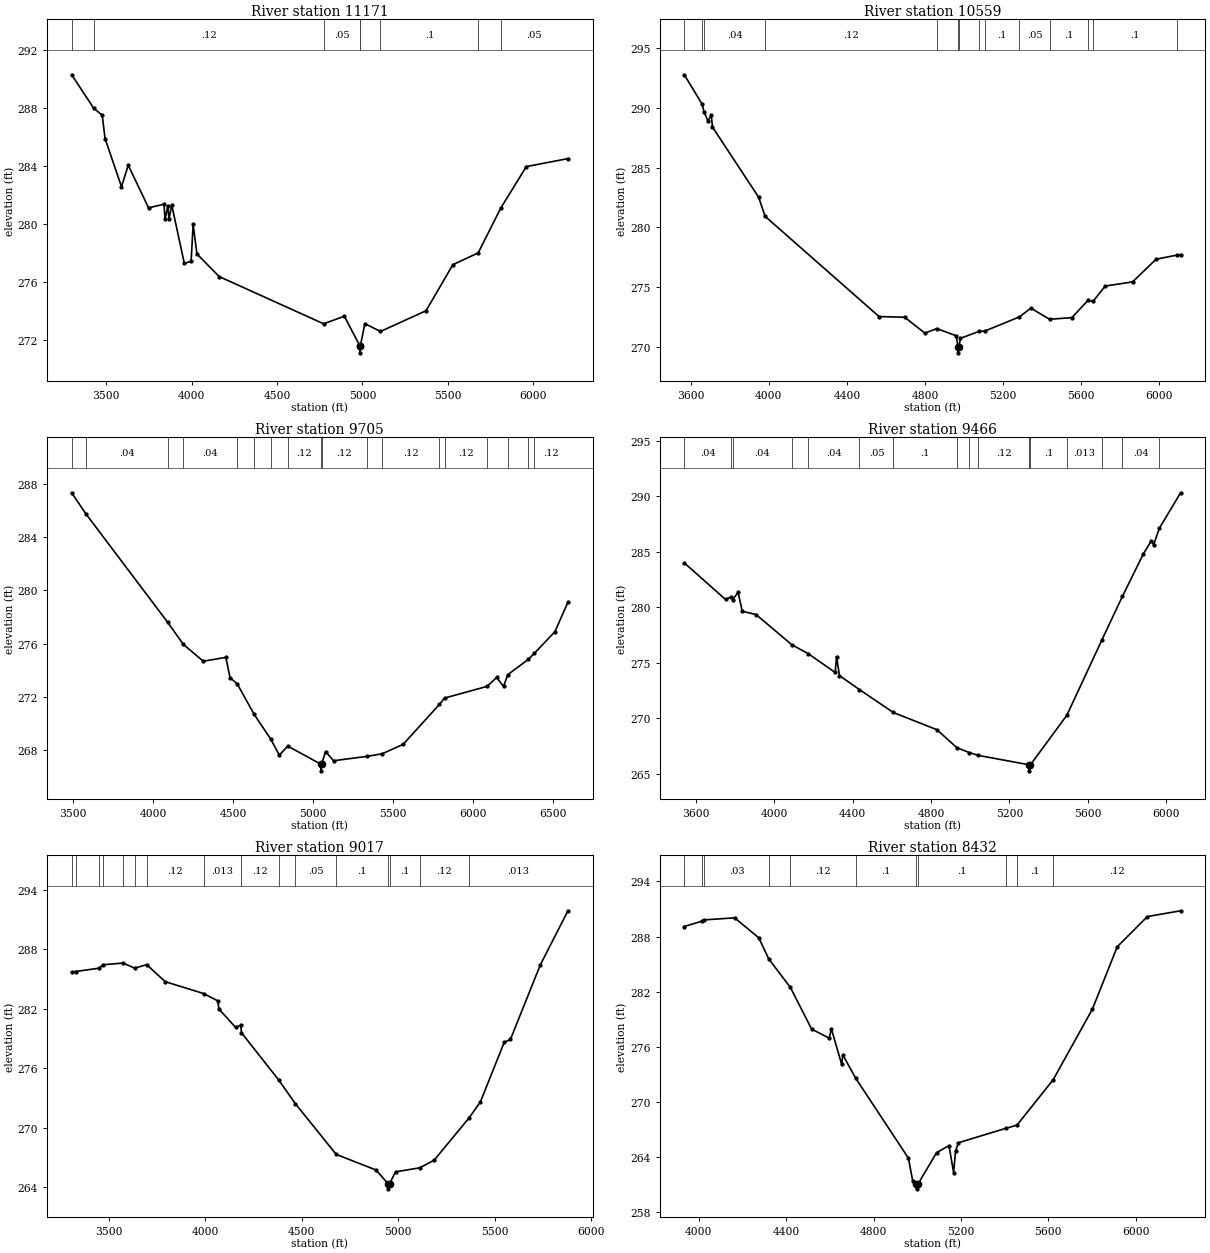
Type RM Length L Ch R = 1,11171,612,612,612
BEGIN DESCRIPTION:
Mapping XS 7f427b86
END DESCRIPTION:
XS GIS Cut Line= 4
      2488354.58     13556866.24      2487721.72     13555546.56
      2487452.63     13555268.78      2486415.27     13555464.10
#Sta/Elev= 30
  3297.2  290.29  3426.7  287.98  3476.0  287.51  3492.7  285.90  3588.9  282.59
  3628.6  284.06  3747.5  281.13  3838.1  281.38  3843.6  280.34  3860.7  281.28
  3866.3  280.34  3883.4  281.31  3956.9  277.30  3996.7  277.46  4008.4  280.00
  4030.5  277.96  4160.8  276.40  4772.4  273.15  4893.9  273.67  4983.7  271.65
  4984.0  271.15  4987.8  271.65  5014.0  273.16  5105.5  272.62  5372.2  274.05
  5529.5  277.22  5677.6  278.03  5809.1  281.10  5959.2  283.97  6203.1  284.52
#Mann=8,-1,0
  3297.2    0.05       0  3426.7    0.12       0  4772.4    0.05       0
  4983.7    0.05       0  4987.8    0.05       0  5105.5     0.1       0
  5677.6    0.12       0  5809.1    0.05       0
Bank Sta=4983.7,4987.8
Exp/Cntr=0.3,0.1

Type RM Length L Ch R = 1,10559,854,854,854
BEGIN DESCRIPTION:
Mapping XS 1dd05b6d
END DESCRIPTION:
XS GIS Cut Line= 3
      2488618.65     13556483.11      2488026.50     13555178.62
      2486919.78     13555100.02
#Sta/Elev= 30
  3567.4  292.77  3659.2  290.29  3668.3  289.65  3688.4  288.92  3705.9  289.37
  3711.4  288.40  3947.7  282.53  3981.2  280.92  4564.7  272.53  4696.1  272.47
  4799.4  271.14  4860.9  271.52  4960.0  270.92  4969.8  269.99  4970.1  269.49
  4974.0  269.99  4982.0  270.71  5078.0  271.29  5106.1  271.31  5284.0  272.50
  5342.4  273.23  5438.7  272.30  5552.9  272.44  5634.9  273.88  5660.4  273.79
  5723.3  275.08  5863.7  275.43  5984.0  277.33  6090.0  277.67  6109.5  277.71
#Mann=14,-1,0
  3567.4    0.04       0  3659.2   0.013       0  3668.3    0.04       0
  3981.2    0.12       0  4860.9    0.05       0  4969.8    0.05       0
  4974.0    0.05       0  5078.0    0.03       0  5106.1     0.1       0
  5284.0    0.05       0  5438.7     0.1       0  5634.9    0.05       0
  5660.4     0.1       0  6090.0    0.12       0
Bank Sta=4969.8,4974
Exp/Cntr=0.3,0.1

Type RM Length L Ch R = 1,9705,239,239,239
BEGIN DESCRIPTION:
Mapping XS 450e21a3
END DESCRIPTION:
XS GIS Cut Line= 3
      2489007.93     13556003.88      2488524.98     13554574.98
      2487543.27     13553321.70
#Sta/Elev= 30
  3491.7  287.33  3579.8  285.76  4092.4  277.58  4189.6  275.93  4313.9  274.67
  4454.9  274.96  4481.1  273.44  4526.4  272.96  4631.4  270.68  4736.5  268.79
  4788.9  267.61  4841.5  268.29  5048.4  266.93  5048.7  266.43  5052.8  266.93
  5077.7  267.88  5127.5  267.19  5338.4  267.52  5432.9  267.72  5562.3  268.42
  5788.8  271.42  5821.3  271.90  6087.3  272.78  6146.4  273.45  6189.8  272.77
  6215.4  273.65  6343.4  274.80  6381.0  275.25  6510.7  276.89  6592.0  279.11
#Mann=18,-1,0
  3491.7   0.013       0  3579.8    0.04       0  4092.4   0.013       0
  4189.6    0.04       0  4526.4    0.12       0  4631.4    0.05       0
  4736.5     0.1       0  4841.5    0.12       0  5048.4    0.05       0
  5052.8    0.12       0  5338.4     0.1       0  5432.9    0.12       0
  5788.8     0.1       0  5821.3    0.12       0  6087.3    0.05       0
  6215.4    0.12       0  6343.4    0.05       0  6381.0    0.12       0
Bank Sta=5048.4,5052.8
Exp/Cntr=0.3,0.1

Type RM Length L Ch R = 1,9466,449,449,449
BEGIN DESCRIPTION:
Mapping XS 5e003575
END DESCRIPTION:
XS GIS Cut Line= 4
      2489431.55     13555732.37      2489048.39     13555235.30
      2488671.84     13554345.25      2488385.66     13553454.21
#Sta/Elev= 30
  3542.4  284.00  3752.6  280.71  3780.7  280.94  3788.3  280.70  3816.8  281.34
  3837.8  279.65  3908.4  279.35  4090.0  276.64  4174.4  275.83  4311.5  274.14
  4318.4  275.57  4333.2  273.86  4435.3  272.60  4607.6  270.54  4830.2  268.99
  4932.6  267.36  4994.5  266.94  5040.9  266.68  5298.2  265.84  5300.4  265.79
  5300.8  265.29  5305.0  265.79  5492.5  270.29  5671.2  277.07  5775.6  280.99
  5882.4  284.81  5923.2  286.00  5934.9  285.64  5963.7  287.11  6072.3  290.31
#Mann=17,-1,0
  3542.4    0.04       0  3780.7   0.013       0  3788.3    0.04       0
  4090.0   0.013       0  4174.4    0.04       0  4435.3    0.05       0
  4607.6     0.1       0  4932.6   0.013       0  4994.5     0.1       0
  5040.9    0.12       0  5298.2     0.1       0  5300.4    0.05       0
  5305.0     0.1       0  5492.5   0.013       0  5671.2    0.05       0
  5775.6    0.04       0  5963.7   0.013       0
Bank Sta=5300.4,5305
Exp/Cntr=0.3,0.1

Type RM Length L Ch R = 1,9017,585,585,585
BEGIN DESCRIPTION:
Mapping XS e5eda4dc
END DESCRIPTION:
XS GIS Cut Line= 4
      2489674.89     13555659.88      2489338.33     13555178.34
      2488975.90     13554184.24      2488556.52     13553361.01
#Sta/Elev= 30
  3309.2  285.69  3329.7  285.75  3452.4  286.09  3470.6  286.43  3575.1  286.60
  3635.6  286.09  3697.8  286.44  3793.1  284.73  3992.3  283.53  4066.1  282.79
  4071.4  281.97  4157.8  280.12  4184.4  280.33  4188.4  279.58  4381.5  274.81
  4466.9  272.44  4678.9  267.32  4884.6  265.75  4948.5  264.35  4949.0  263.85
  4954.9  264.35  4985.9  265.56  5111.6  265.97  5186.1  266.74  5365.5  270.97
  5425.1  272.60  5548.8  278.62  5580.7  278.90  5736.4  286.45  5878.7  291.87
#Mann=16,-1,0
  3309.2   0.013       0  3329.7    0.05       0  3452.4    0.12       0
  3470.6    0.05       0  3575.1    0.12       0  3635.6    0.05       0
  3697.8    0.12       0  3992.3   0.013       0  4184.4    0.12       0
  4381.5   0.013       0  4466.9    0.05       0  4678.9     0.1       0
  4948.5    0.05       0  4954.9     0.1       0  5111.6    0.12       0
  5365.5   0.013       0
Bank Sta=4948.5,4954.9
Exp/Cntr=0.3,0.1

Type RM Length L Ch R = 1,8432,191,191,191
BEGIN DESCRIPTION:
Mapping XS 27f4fc77
END DESCRIPTION:
XS GIS Cut Line= 3
      2489602.39     13555333.66      2489478.13     13554251.55
      2488815.40     13553272.98
#Sta/Elev= 30
  3934.0  289.09  4016.4  289.68  4024.6  289.81  4164.2  290.03  4274.9  287.86
  4320.1  285.57  4419.6  282.46  4516.5  277.94  4597.0  276.95  4607.1  277.96
  4654.3  274.09  4659.3  275.13  4718.2  272.60  4959.4  263.91  4979.5  261.40
  4996.2  261.07  4996.7  260.57  5003.1  261.07  5088.4  264.51  5145.3  265.27
  5166.3  262.34  5175.2  264.66  5188.1  265.58  5404.2  267.14  5456.1  267.49
  5622.2  272.44  5801.3  280.10  5915.2  286.89  6053.0  290.17  6205.1  290.80
#Mann=11,-1,0
  3934.0    0.12       0  4016.4    0.05       0  4024.6    0.03       0
  4320.1    0.05       0  4419.6    0.12       0  4718.2     0.1       0
  4996.2    0.05       0  5003.1     0.1       0  5404.2    0.12       0
  5456.1     0.1       0  5622.2    0.12       0
Bank Sta=4996.2,5003.1
Exp/Cntr=0.3,0.1

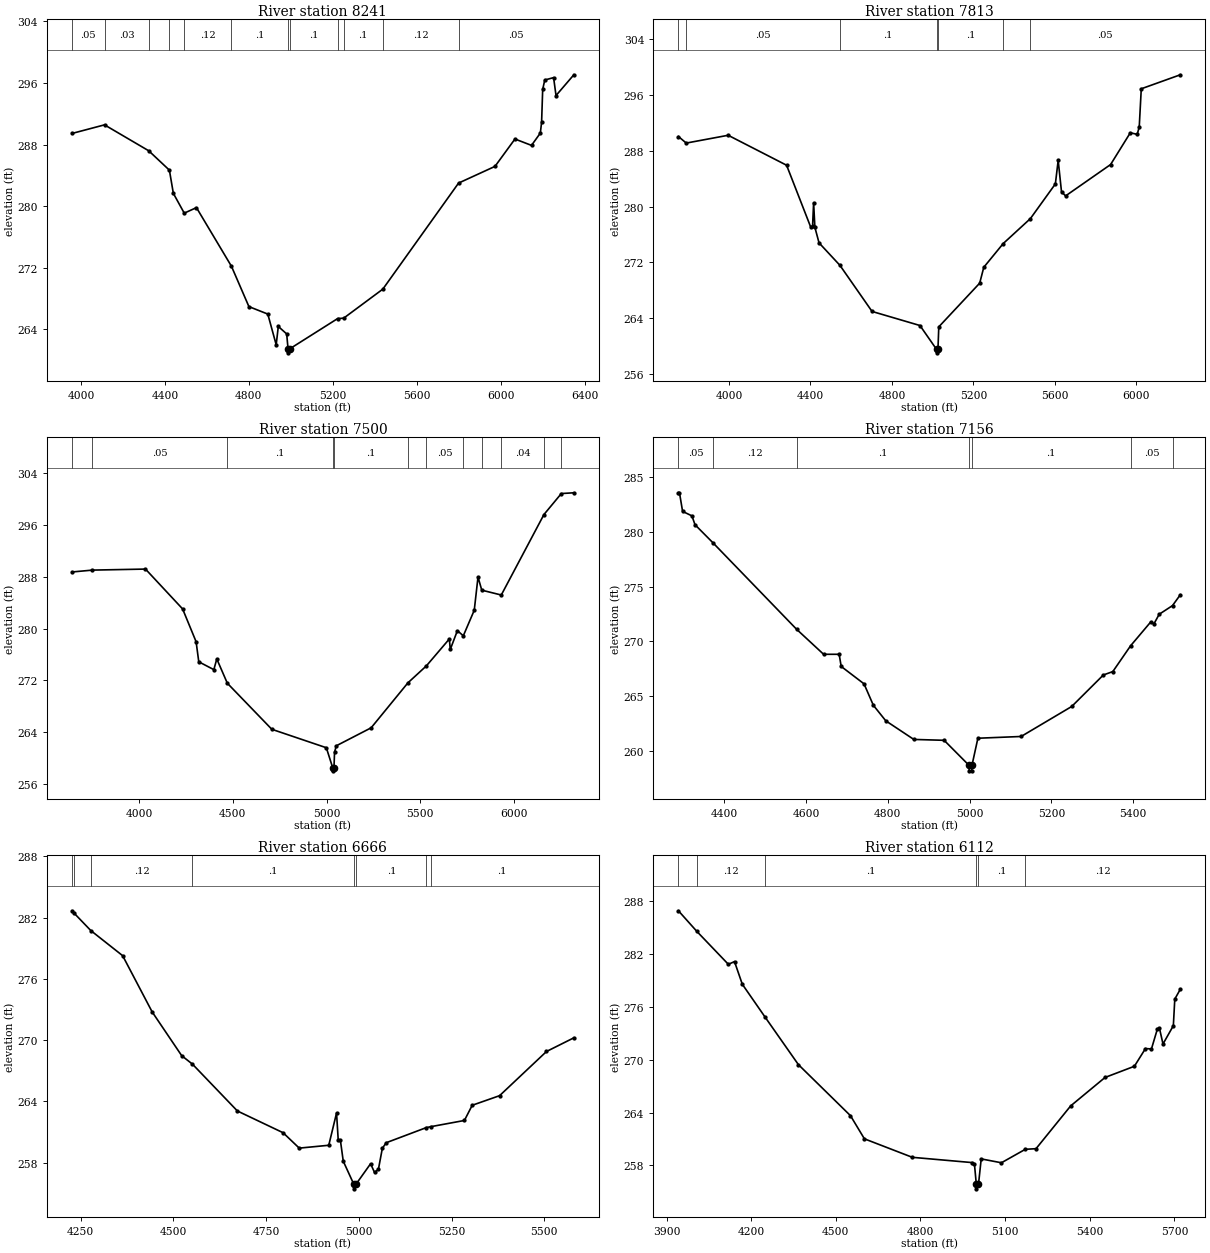
Type RM Length L Ch R = 1,8241,428,428,428
BEGIN DESCRIPTION:
Mapping XS 9f446d0a
END DESCRIPTION:
XS GIS Cut Line= 3
      2489633.46     13555318.13      2489643.81     13554246.37
      2490058.03     13552993.37
#Sta/Elev= 30
  3957.0  289.44  4112.2  290.56  4322.8  287.19  4421.3  284.67  4440.2  281.65
  4492.1  279.08  4550.2  279.80  4716.9  272.18  4800.2  266.93  4890.2  265.96
  4930.2  261.97  4940.2  264.35  4980.2  263.38  4986.7  261.42  4987.2  260.92
  4993.6  261.42  5222.7  265.37  5251.9  265.43  5438.2  269.20  5799.2  282.99
  5972.7  285.16  6067.9  288.72  6146.7  287.89  6188.8  289.49  6194.8  290.90
  6200.0  295.17  6209.9  296.39  6252.0  296.70  6263.5  294.37  6348.5  297.07
#Mann=12,-1,0
  3957.0    0.05       0  4112.2    0.03       0  4322.8    0.12       0
  4421.3    0.05       0  4492.1    0.12       0  4716.9     0.1       0
  4986.7    0.05       0  4993.6     0.1       0  5222.7    0.12       0
  5251.9     0.1       0  5438.2    0.12       0  5799.2    0.05       0
Bank Sta=4986.7,4993.6
Exp/Cntr=0.3,0.1

Type RM Length L Ch R = 1,7813,313,313,313
BEGIN DESCRIPTION:
Mapping XS 0c79bf02
END DESCRIPTION:
XS GIS Cut Line= 3
      2489643.82     13555411.32      2490026.96     13554241.19
      2490130.51     13553014.11
#Sta/Elev= 30
  3752.4  290.05  3790.9  289.11  3996.5  290.23  4283.2  285.93  4400.9  277.10
  4410.6  277.14  4415.8  280.56  4422.0  277.02  4442.4  274.79  4544.8  271.57
  4702.5  264.95  4937.6  262.93  5018.9  259.51  5019.4  259.01  5025.9  259.51
  5030.0  262.74  5230.7  269.01  5250.8  271.29  5346.0  274.69  5479.4  278.27
  5602.0  283.25  5615.8  286.63  5632.1  282.12  5652.2  281.53  5873.0  286.03
  5969.8  290.59  6003.5  290.36  6013.5  291.41  6023.5  296.90  6215.1  298.91
#Mann=7,-1,0
  3752.4    0.12       0  3790.9    0.05       0  4544.8     0.1       0
  5018.9    0.05       0  5025.9     0.1       0  5346.0    0.12       0
  5479.4    0.05       0
Bank Sta=5018.9,5025.9
Exp/Cntr=0.3,0.1

Type RM Length L Ch R = 1,7500,344,344,344
BEGIN DESCRIPTION:
Mapping XS 8312eb9e
END DESCRIPTION:
XS GIS Cut Line= 3
      2489633.46     13555488.99      2490353.15     13554241.19
      2490389.39     13553003.69
#Sta/Elev= 30
  3641.3  288.74  3750.4  289.03  4033.7  289.19  4231.9  283.03  4303.9  277.96
  4318.1  274.86  4398.5  273.65  4414.3  275.30  4470.5  271.55  4708.0  264.43
  4998.9  261.58  5032.6  258.51  5033.1  258.01  5039.7  258.51  5042.7  260.88
  5052.0  261.88  5238.0  264.66  5434.3  271.61  5532.8  274.23  5655.3  278.39
  5660.3  276.77  5698.2  279.67  5729.9  278.88  5788.3  282.83  5808.3  287.96
  5828.4  285.93  5932.5  285.18  6160.2  297.62  6253.0  300.86  6319.8  300.98
#Mann=12,-1,0
  3641.3    0.12       0  3750.4    0.05       0  4470.5     0.1       0
  5032.6    0.05       0  5039.7     0.1       0  5434.3    0.12       0
  5532.8    0.05       0  5729.9    0.04       0  5828.4    0.05       0
  5932.5    0.04       0  6160.2   0.013       0  6253.0    0.04       0
Bank Sta=5032.6,5039.7
Exp/Cntr=0.3,0.1

Type RM Length L Ch R = 1,7156,490,490,490
BEGIN DESCRIPTION:
TRIB 6 TO FIVEMILE CREEK 13.0
END DESCRIPTION:
XS GIS Cut Line= 3
      2490525.00     13554975.03      2490625.00     13554375.00
      2490474.99     13553774.97
#Sta/Elev= 30
  4288.4  283.59  4291.0  283.59  4298.6  281.89  4321.4  281.48  4329.0  280.67
  4372.3  279.04  4577.2  271.12  4643.3  268.83  4681.3  268.83  4686.3  267.72
  4742.1  266.13  4764.9  264.17  4795.3  262.75  4863.8  261.05  4937.9  260.97
  4998.8  258.68  4999.3  258.18  5005.4  258.18  5005.9  258.68  5020.4  261.16
  5126.1  261.32  5249.7  264.06  5327.1  266.94  5350.2  267.25  5393.7  269.61
  5443.0  271.79  5450.7  271.61  5463.6  272.49  5496.1  273.28  5515.2  274.27
#Mann=7,-1,0
  4288.4    0.05       0  4372.3    0.12       0  4577.2     0.1       0
  4998.8    0.05       0  5005.9     0.1       0  5393.7    0.05       0
  5496.1    0.12       0
Bank Sta=4998.8,5005.9
Exp/Cntr=0.3,0.1

Type RM Length L Ch R = 1,6666,554,554,554
BEGIN DESCRIPTION:
TRIB 6 TO FIVEMILE CREEK 12.0
END DESCRIPTION:
XS GIS Cut Line= 3
      2490674.99     13555025.01      2491075.00     13554425.00
      2490874.99     13553824.98
#Sta/Elev= 30
  4226.3  282.67  4232.8  282.41  4277.2  280.73  4363.0  278.27  4442.6  272.76
  4522.3  268.47  4551.3  267.64  4672.5  263.05  4795.7  260.92  4839.3  259.41
  4918.9  259.69  4939.9  262.85  4944.4  260.22  4950.1  260.22  4958.0  258.13
  4985.8  255.92  4986.3  255.42  4993.3  255.92  5031.7  257.88  5042.3  257.03
  5052.8  257.33  5063.4  259.39  5073.9  259.94  5181.9  261.42  5193.8  261.51
  5284.7  262.12  5305.8  263.61  5379.6  264.55  5506.1  268.88  5579.9  270.22
#Mann=8,-1,0
  4226.3    0.12       0  4232.8    0.05       0  4277.2    0.12       0
  4551.3     0.1       0  4985.8    0.05       0  4993.3     0.1       0
  5181.9    0.12       0  5193.8     0.1       0
Bank Sta=4985.8,4993.3
Exp/Cntr=0.3,0.1

Type RM Length L Ch R = 1,6112,467,467,467
BEGIN DESCRIPTION:
TRIB 6 TO FIVEMILE CREEK 11.0
END DESCRIPTION:
XS GIS Cut Line= 3
      2490725.01     13555224.99      2491525.00     13554525.00
      2491375.00     13553824.99
#Sta/Elev= 30
  3942.0  286.92  4007.6  284.57  4119.0  280.84  4140.8  281.15  4168.4  278.58
  4249.3  274.84  4367.2  269.45  4551.8  263.65  4601.2  261.02  4771.0  258.92
  4983.6  258.32  4991.2  258.15  4997.9  255.84  4998.4  255.34  5005.5  255.84
  5015.2  258.74  5086.8  258.30  5171.5  259.83  5209.5  259.90  5332.3  264.76
  5454.1  267.99  5558.1  269.26  5597.3  271.27  5618.6  271.23  5639.1  273.44
  5646.7  273.62  5659.5  271.79  5696.2  273.87  5701.3  276.89  5720.9  278.01
#Mann=6,-1,0
  3942.0    0.05       0  4007.6    0.12       0  4249.3     0.1       0
  4997.9    0.05       0  5005.5     0.1       0  5171.5    0.12       0
Bank Sta=4997.9,5005.5
Exp/Cntr=0.3,0.1

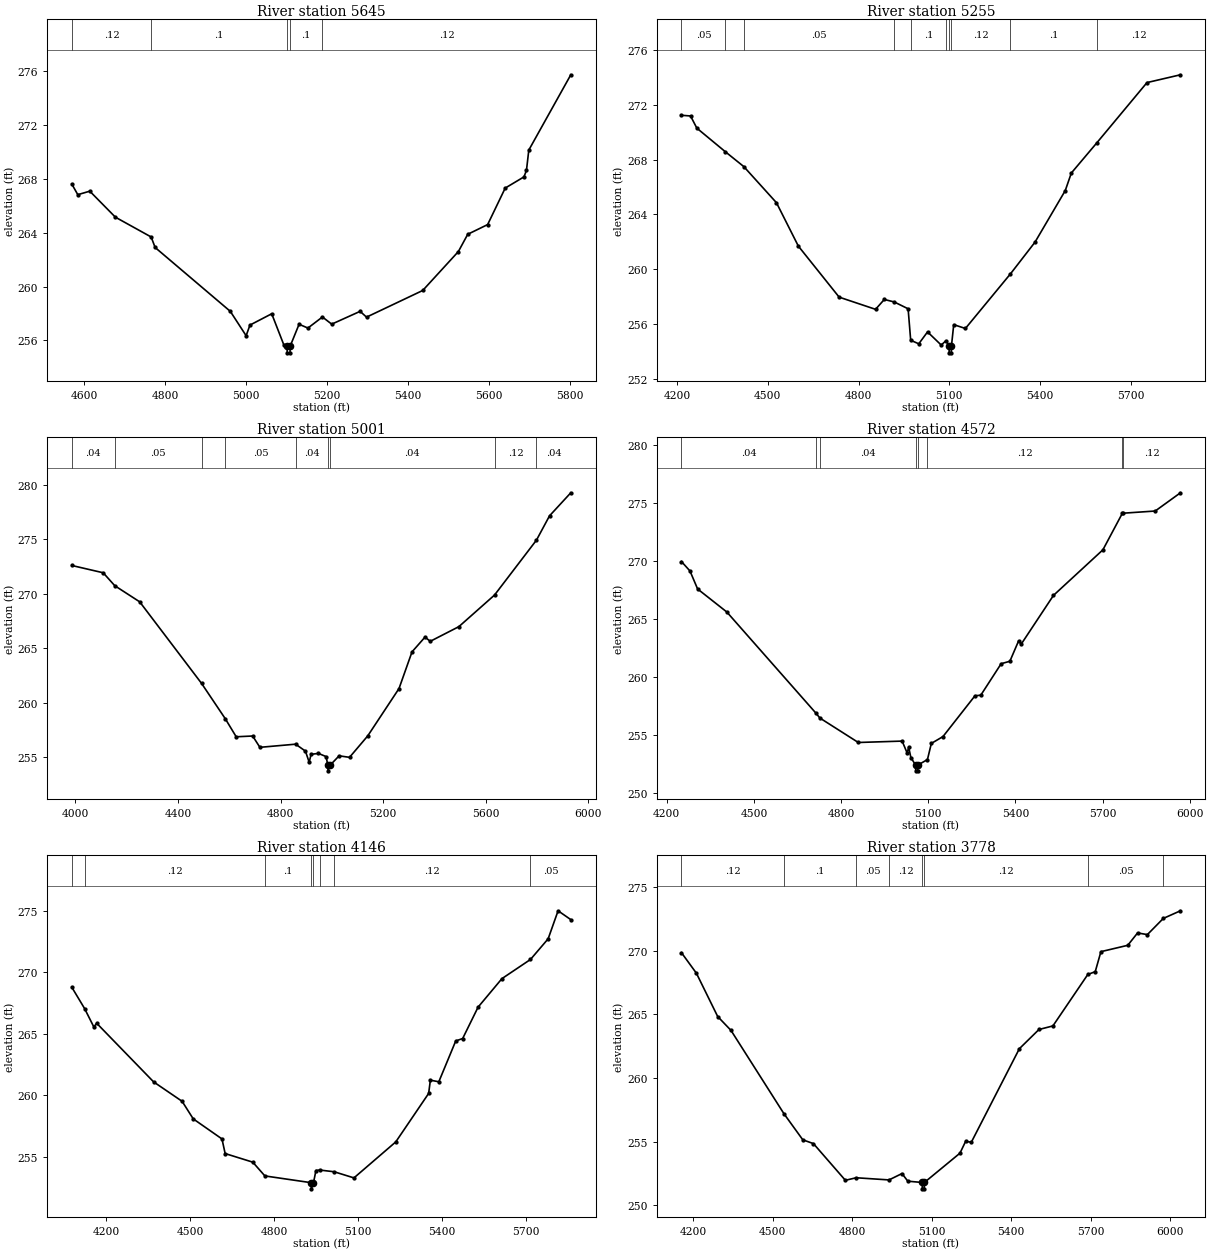
Type RM Length L Ch R = 1,5645,390,390,390
BEGIN DESCRIPTION:
TRIB 6 TO FIVEMILE CREEK 10.0
END DESCRIPTION:
XS GIS Cut Line= 3
      2491775.01     13554974.96      2491975.00     13554475.00
      2491625.00     13553875.00
#Sta/Elev= 30
  4569.2  267.61  4584.0  266.82  4613.6  267.08  4676.9  265.15  4765.3  263.68
  4775.1  262.90  4960.9  258.16  5000.0  256.35  5009.4  257.14  5063.2  257.98
  5092.9  255.69  5101.1  255.58  5101.6  255.08  5108.4  255.08  5108.9  255.58
  5130.8  257.20  5152.7  256.92  5188.5  257.74  5211.5  257.21  5281.7  258.16
  5297.5  257.73  5436.4  259.71  5524.5  262.60  5547.6  263.88  5596.8  264.60
  5640.2  267.31  5686.5  268.14  5692.7  268.62  5698.5  270.13  5802.3  275.72
#Mann=5,-1,0
  4569.2    0.12       0  4765.3     0.1       0  5101.1    0.05       0
  5108.9     0.1       0  5188.5    0.12       0
Bank Sta=5101.1,5108.9
Exp/Cntr=0.3,0.1

Type RM Length L Ch R = 1,5255,254,254,254
BEGIN DESCRIPTION:
Mapping XS ead7a7b2
END DESCRIPTION:
XS GIS Cut Line= 3
      2491828.79     13555230.09      2492331.00     13554588.09
      2492320.65     13553754.45
#Sta/Elev= 30
  4214.9  271.25  4244.9  271.20  4265.7  270.31  4360.2  268.58  4420.9  267.50
  4528.8  264.86  4601.1  261.69  4735.9  257.96  4856.2  257.07  4885.1  257.79
  4917.7  257.61  4963.8  257.11  4972.3  254.81  4999.0  254.55  5028.0  255.42
  5073.1  254.46  5089.2  254.78  5099.1  254.39  5099.6  253.89  5106.5  253.89
  5107.0  254.39  5114.5  255.95  5153.1  255.67  5301.9  259.66  5383.1  261.98
  5483.1  265.75  5503.1  267.03  5586.7  269.22  5753.1  273.64  5863.7  274.21
#Mann=10,-1,0
  4214.9    0.05       0  4360.2    0.12       0  4420.9    0.05       0
  4917.7    0.12       0  4972.3     0.1       0  5089.2    0.12       0
  5099.1    0.05       0  5107.0    0.12       0  5301.9     0.1       0
  5586.7    0.12       0
Bank Sta=5099.1,5107
Exp/Cntr=0.3,0.1

Type RM Length L Ch R = 1,5001,429,429,429
BEGIN DESCRIPTION:
Mapping XS 310a2f73
END DESCRIPTION:
XS GIS Cut Line= 3
      2491932.34     13555494.16      2492532.93     13554748.60
      2492703.80     13553775.16
#Sta/Elev= 30
  3985.8  272.61  4108.2  271.94  4153.4  270.75  4250.5  269.27  4491.9  261.77
  4584.2  258.53  4626.8  256.87  4691.0  256.94  4719.2  255.90  4858.5  256.19
  4896.8  255.55  4911.2  254.54  4919.1  255.26  4947.5  255.34  4977.3  255.05
  4984.3  254.24  4984.8  253.74  4992.3  254.24  5028.1  255.12  5068.7  254.98
  5139.7  256.95  5261.6  261.30  5312.3  264.67  5363.1  266.03  5383.4  265.64
  5495.1  266.99  5634.0  269.89  5797.6  274.94  5848.5  277.17  5931.5  279.29
#Mann=9,-1,0
  3985.8    0.04       0  4153.4    0.05       0  4491.9    0.12       0
  4584.2    0.05       0  4858.5    0.04       0  4984.3    0.04       0
  4992.3    0.04       0  5634.0    0.12       0  5797.6    0.04       0
Bank Sta=4984.3,4992.3
Exp/Cntr=0.3,0.1

Type RM Length L Ch R = 1,4572,426,426,426
BEGIN DESCRIPTION:
Mapping XS 7f4f77c0
END DESCRIPTION:
XS GIS Cut Line= 3
      2492796.99     13555670.24      2492890.19     13554800.37
      2492859.19     13553958.19
#Sta/Elev= 30
  4250.6  269.94  4279.9  269.13  4306.2  267.58  4406.7  265.60  4712.2  256.93
  4727.3  256.47  4859.3  254.37  5010.2  254.49  5027.5  253.46  5032.6  253.97
  5040.3  253.07  5056.4  252.43  5056.9  251.93  5064.0  251.93  5064.5  252.43
  5097.3  252.90  5110.7  254.29  5150.8  254.88  5260.9  258.39  5280.9  258.44
  5351.0  261.15  5381.0  261.36  5411.0  263.11  5421.0  262.87  5531.1  267.03
  5701.2  270.95  5767.9  274.08  5769.3  274.10  5881.3  274.29  5968.2  275.86
#Mann=8,-1,0
  4250.6    0.04       0  4712.2    0.12       0  4727.3    0.04       0
  5056.4    0.04       0  5064.5    0.04       0  5097.3    0.12       0
  5767.9    0.04       0  5769.3    0.12       0
Bank Sta=5056.4,5064.5
Exp/Cntr=0.3,0.1

Type RM Length L Ch R = 1,4146,368,368,368
BEGIN DESCRIPTION:
Mapping XS a461cd98
END DESCRIPTION:
XS GIS Cut Line= 3
      2493097.29     13555732.38      2493273.33     13554815.91
      2492973.30     13554019.26
#Sta/Elev= 30
  4076.0  268.78  4121.6  267.05  4154.8  265.55  4165.0  265.85  4368.6  261.08
  4470.5  259.50  4510.3  258.07  4613.0  256.44  4624.4  255.25  4723.2  254.55
  4766.5  253.43  4932.1  252.88  4932.6  252.38  4940.3  252.88  4949.1  253.87
  4962.1  253.91  5014.2  253.77  5085.0  253.27  5234.6  256.20  5352.1  260.14
  5358.3  261.22  5388.5  261.09  5449.0  264.41  5473.8  264.61  5528.9  267.16
  5614.2  269.48  5716.3  271.04  5779.5  272.72  5815.0  275.00  5860.5  274.28
#Mann=8,-1,0
  4076.0    0.04       0  4121.6    0.12       0  4766.5     0.1       0
  4932.1    0.05       0  4940.3     0.1       0  4962.1    0.05       0
  5014.2    0.12       0  5716.3    0.05       0
Bank Sta=4932.1,4940.3
Exp/Cntr=0.3,0.1

Type RM Length L Ch R = 1,3778,389,389,389
BEGIN DESCRIPTION:
Mapping XS 65f921ce
END DESCRIPTION:
XS GIS Cut Line= 3
      2493723.78     13555551.09      2493661.65     13554815.91
      2493076.58     13553832.15
#Sta/Elev= 30
  4155.9  269.83  4212.2  268.22  4292.5  264.82  4342.7  263.73  4542.4  257.19
  4613.6  255.14  4653.8  254.84  4774.2  251.96  4815.0  252.16  4938.8  251.99
  4987.8  252.49  5009.8  251.89  5064.1  251.79  5064.6  251.29  5071.8  251.29
  5072.3  251.79  5206.5  254.09  5227.9  255.02  5249.4  254.95  5430.5  262.29
  5504.5  263.80  5557.1  264.08  5688.8  268.12  5716.8  268.34  5738.2  269.91
  5839.5  270.41  5876.5  271.38  5913.5  271.25  5973.6  272.52  6038.3  273.12
#Mann=8,-1,0
  4155.9    0.12       0  4542.4     0.1       0  4815.0    0.05       0
  4938.8    0.12       0  5064.1    0.05       0  5072.3    0.12       0
  5688.8    0.05       0  5973.6    0.12       0
Bank Sta=5064.1,5072.3
Exp/Cntr=0.3,0.1