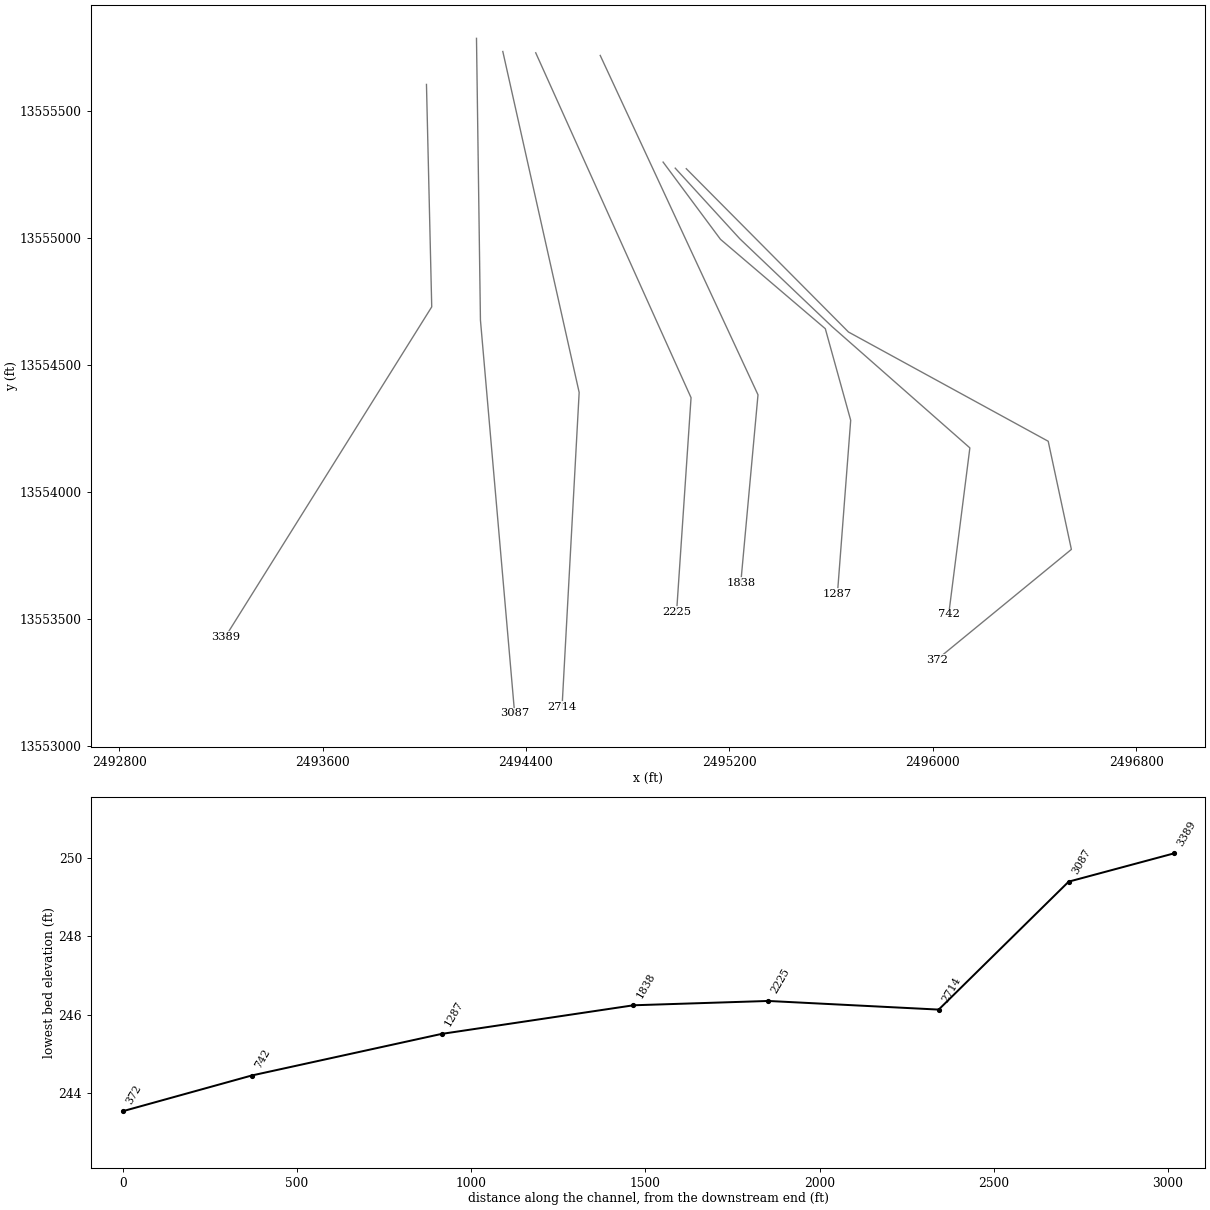
HEC-RAS study TRIB 6 TO FIVEMILE CREEK.prj: TRIB 6 TO FIVEMILE CREEK Base Level Engineering

--- TRIB 6 TO FIVEMILE CREEK.g01 (geometry) --- (continued)

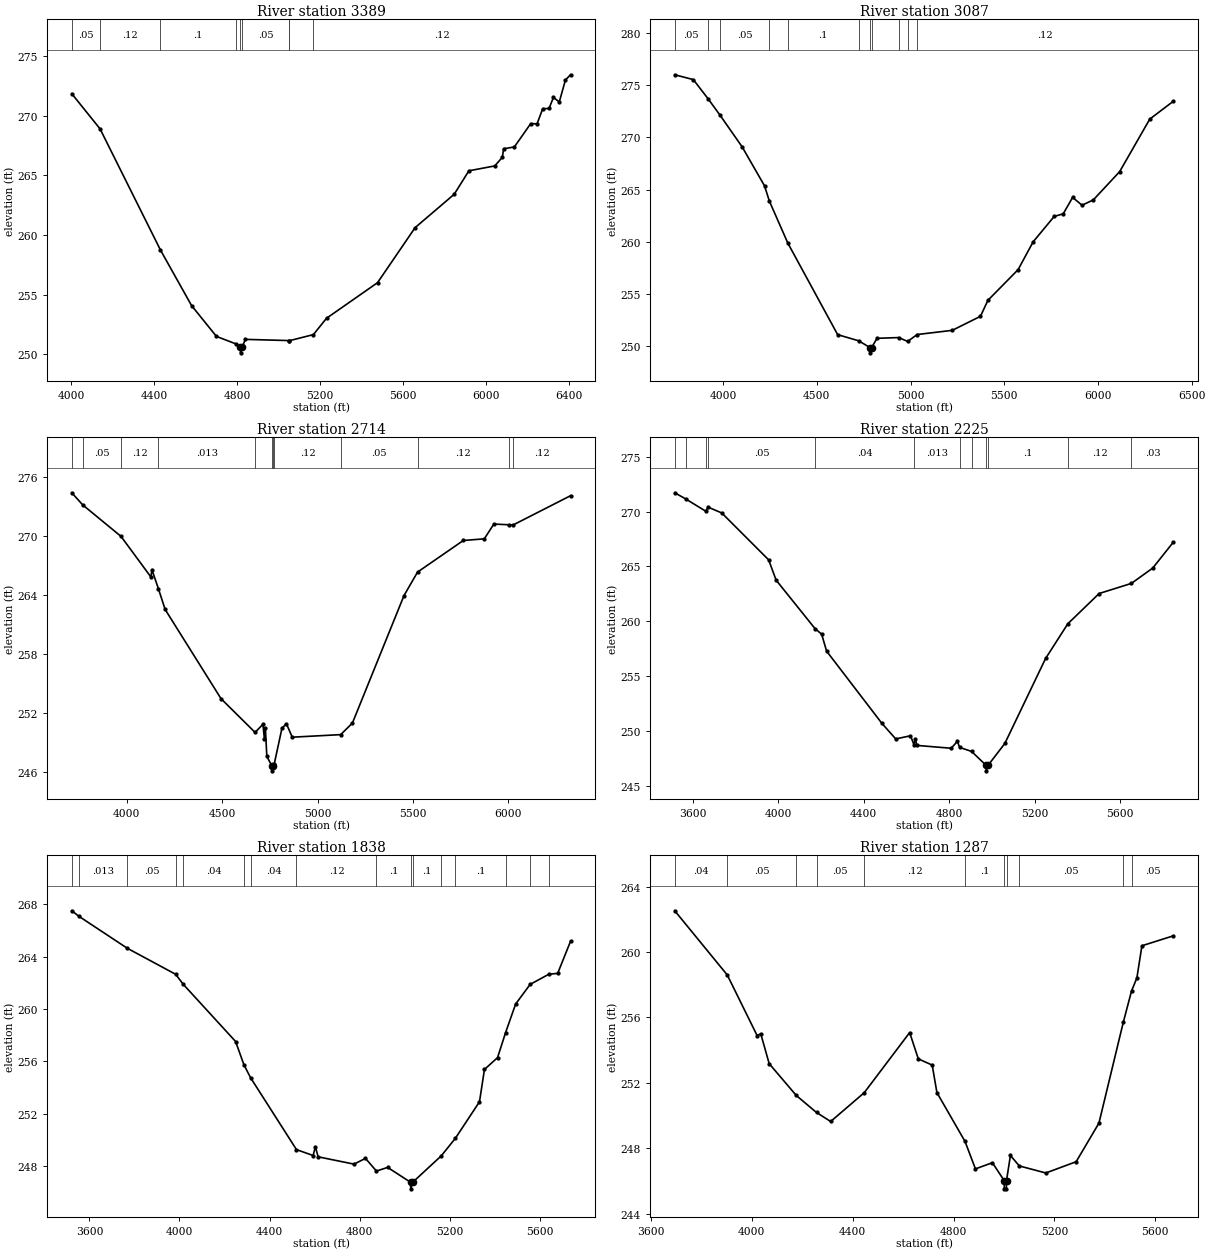
Type RM Length L Ch R = 1,3389,302,302,302
BEGIN DESCRIPTION:
Mapping XS 79ef9403
END DESCRIPTION:
XS GIS Cut Line= 3
      2494008.56     13555602.87      2494029.27     13554727.89
      2493216.91     13553429.15
#Sta/Elev= 30
  4001.9  271.86  4138.3  268.91  4429.6  258.75  4579.9  254.08  4700.0  251.49
  4792.8  250.87  4815.9  250.61  4816.4  250.11  4824.1  250.61  4840.0  251.24
  5049.7  251.14  5052.2  251.13  5168.0  251.64  5231.3  253.01  5477.7  256.00
  5659.0  260.62  5847.7  263.42  5918.6  265.39  6043.6  265.80  6080.2  266.53
  6086.1  267.24  6137.9  267.39  6216.9  269.35  6247.6  269.33  6274.7  270.60
  6305.4  270.62  6326.6  271.55  6354.9  271.17  6384.4  273.01  6409.0  273.45
#Mann=9,-1,0
  4001.9    0.05       0  4138.3    0.12       0  4429.6     0.1       0
  4792.8    0.05       0  4815.9    0.05       0  4824.1    0.05       0
  5049.7    0.12       0  5052.2    0.05       0  5168.0    0.12       0
Bank Sta=4815.9,4824.1
Exp/Cntr=0.3,0.1

Type RM Length L Ch R = 1,3087,373,373,373
BEGIN DESCRIPTION:
Mapping XS c60aeaa1
END DESCRIPTION:
XS GIS Cut Line= 3
      2494205.31     13555784.13      2494220.84     13554676.11
      2494355.37     13553128.97
#Sta/Elev= 30
  3741.8  275.97  3840.9  275.51  3919.2  273.69  3982.2  272.14  4101.0  269.09
  4221.0  265.35  4246.6  263.90  4345.2  259.88  4611.0  251.13  4723.4  250.54
  4783.9  249.89  4784.4  249.39  4792.3  249.89  4821.0  250.78  4936.5  250.85
  4984.6  250.48  5035.2  251.14  5222.4  251.54  5373.0  252.88  5412.8  254.41
  5573.8  257.34  5654.1  260.00  5766.6  262.43  5814.7  262.68  5864.9  264.25
  5915.0  263.50  5975.3  264.01  6115.8  266.71  6276.4  271.73  6402.9  273.45
#Mann=11,-1,0
  3741.8    0.05       0  3919.2    0.12       0  3982.2    0.05       0
  4246.6    0.12       0  4345.2     0.1       0  4723.4    0.05       0
  4783.9    0.05       0  4792.3    0.05       0  4936.5    0.12       0
  4984.6    0.05       0  5035.2    0.12       0
Bank Sta=4783.9,4792.3
Exp/Cntr=0.3,0.1

Type RM Length L Ch R = 1,2714,489,489,489
BEGIN DESCRIPTION:
Mapping XS 3ce58960
END DESCRIPTION:
XS GIS Cut Line= 3
      2494308.85     13555732.38      2494609.16     13554391.34
      2494541.85     13553153.93
#Sta/Elev= 30
  3712.0  274.39  3769.1  273.16  3969.8  269.96  4126.7  265.83  4131.9  266.58
  4165.9  264.64  4201.2  262.53  4494.2  253.46  4672.4  250.04  4713.6  250.86
  4721.4  249.39  4726.5  250.45  4734.1  247.60  4760.5  246.63  4761.0  246.13
  4768.9  246.63  4772.8  246.81  4813.2  250.45  4836.6  250.92  4867.3  249.55
  5121.2  249.81  5182.7  250.99  5453.1  263.95  5524.0  266.33  5763.6  269.54
  5873.8  269.71  5923.8  271.21  6001.7  271.14  6024.0  271.11  6325.5  274.09
#Mann=12,-1,0
  3712.0    0.12       0  3769.1    0.05       0  3969.8    0.12       0
  4165.9   0.013       0  4672.4    0.05       0  4760.5    0.05       0
  4768.9    0.05       0  4772.8    0.12       0  5121.2    0.05       0
  5524.0    0.12       0  6001.7    0.05       0  6024.0    0.12       0
Bank Sta=4760.5,4768.9
Exp/Cntr=0.3,0.1

Type RM Length L Ch R = 1,2225,387,387,387
BEGIN DESCRIPTION:
Mapping XS da290566
END DESCRIPTION:
XS GIS Cut Line= 3
      2494438.29     13555727.20      2495049.26     13554370.63
      2494992.42     13553528.35
#Sta/Elev= 30
  3516.4  271.72  3567.5  271.16  3661.2  270.04  3672.0  270.41  3736.2  269.88
  3955.5  265.60  3990.4  263.75  4172.2  259.33  4203.3  258.82  4226.5  257.27
  4483.9  250.71  4549.7  249.26  4618.7  249.55  4634.9  248.74  4641.9  249.24
  4648.5  248.67  4809.3  248.41  4838.0  249.05  4848.3  248.49  4904.4  248.12
  4972.4  246.85  4972.9  246.35  4981.3  246.85  5060.0  248.85  5250.4  256.60
  5354.5  259.77  5501.0  262.53  5651.5  263.45  5751.5  264.85  5848.4  267.23
#Mann=12,-1,0
  3516.4    0.12       0  3567.5    0.05       0  3661.2   0.013       0
  3672.0    0.05       0  4172.2    0.04       0  4634.9   0.013       0
  4848.3    0.12       0  4904.4     0.1       0  4972.4    0.05       0
  4981.3     0.1       0  5354.5    0.12       0  5651.5    0.03       0
Bank Sta=4972.4,4981.3
Exp/Cntr=0.3,0.1

Type RM Length L Ch R = 1,1838,551,551,551
BEGIN DESCRIPTION:
Mapping XS cdc31782
END DESCRIPTION:
XS GIS Cut Line= 3
      2494692.00     13555716.83      2495312.59     13554382.01
      2495244.88     13553642.44
#Sta/Elev= 30
  3521.8  267.51  3554.1  267.08  3767.6  264.65  3983.2  262.65  4016.0  261.90
  4249.3  257.51  4286.2  255.73  4316.1  254.73  4519.6  249.24  4593.5  248.79
  4603.6  249.47  4615.6  248.69  4774.9  248.13  4826.1  248.57  4874.7  247.60
  4924.4  247.88  5026.5  246.74  5027.0  246.24  5035.5  246.74  5162.4  248.76
  5225.4  250.11  5332.3  252.90  5354.3  255.37  5412.6  256.28  5448.2  258.19
  5492.9  260.38  5557.3  261.88  5640.8  262.66  5679.5  262.72  5736.5  265.17
#Mann=16,-1,0
  3521.8    0.12       0  3554.1   0.013       0  3767.6    0.05       0
  3983.2   0.013       0  4016.0    0.04       0  4286.2    0.05       0
  4316.1    0.04       0  4519.6    0.12       0  4874.7     0.1       0
  5026.5    0.05       0  5035.5     0.1       0  5162.4    0.12       0
  5225.4     0.1       0  5448.2    0.05       0  5557.3    0.03       0
  5640.8    0.05       0
Bank Sta=5026.5,5035.5
Exp/Cntr=0.3,0.1

Type RM Length L Ch R = 1,1287,545,545,545
BEGIN DESCRIPTION:
Mapping XS 0f876968
END DESCRIPTION:
XS GIS Cut Line= 5
      2494939.34     13555297.35      2495165.02     13554993.55
      2495577.35     13554641.99      2495677.17     13554281.75
      2495625.09     13553600.36
#Sta/Elev= 30
  3694.5  262.52  3902.9  258.59  4021.3  254.88  4035.5  255.00  4068.9  253.17
  4176.5  251.22  4256.7  250.18  4312.8  249.63  4445.8  251.39  4626.0  255.07
  4660.3  253.46  4715.4  253.08  4734.0  251.40  4845.5  248.41  4886.8  246.73
  4954.1  247.11  5000.9  246.01  5001.4  245.51  5009.5  245.51  5010.0  246.01
  5025.5  247.55  5060.9  246.91  5165.9  246.48  5286.2  247.17  5376.5  249.53
  5473.1  255.70  5505.7  257.61  5526.9  258.41  5547.0  260.38  5672.0  260.99
#Mann=11,-1,0
  3694.5    0.04       0  3902.9    0.05       0  4176.5    0.04       0
  4256.7    0.05       0  4445.8    0.12       0  4845.5     0.1       0
  5000.9    0.05       0  5010.0     0.1       0  5060.9    0.05       0
  5473.1    0.12       0  5505.7    0.05       0
Bank Sta=5000.9,5010
Exp/Cntr=0.3,0.1

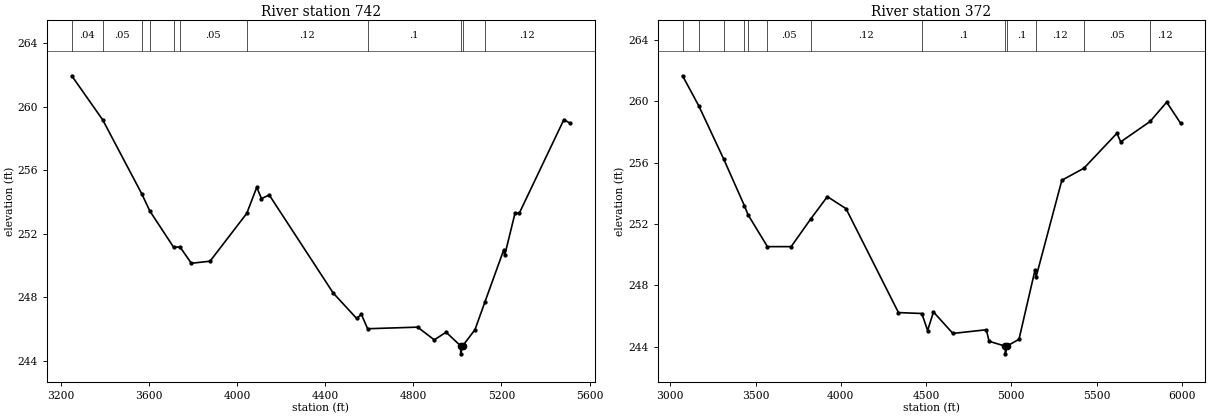
Type RM Length L Ch R = 1,742,370,370,370
BEGIN DESCRIPTION:
Mapping XS e25b54ff
END DESCRIPTION:
XS GIS Cut Line= 5
      2494987.04     13555273.53      2495240.97     13554995.73
      2495603.39     13554650.67      2496145.92     13554173.24
      2496062.75     13553518.67
#Sta/Elev= 30
  3250.7  261.95  3391.4  259.17  3569.1  254.50  3604.5  253.45  3712.9  251.16
  3741.8  251.18  3793.2  250.15  3878.1  250.28  4044.7  253.29  4090.1  254.93
  4111.5  254.22  4146.6  254.45  4436.9  248.28  4543.2  246.68  4565.0  246.93
  4593.1  246.03  4820.2  246.13  4895.5  245.33  4949.2  245.81  5015.2  244.95
  5015.7  244.45  5024.3  244.95  5080.2  245.97  5125.2  247.71  5210.4  250.98
  5215.4  250.67  5261.7  253.29  5281.9  253.32  5483.5  259.19  5510.0  258.98
#Mann=11,-1,0
  3250.7    0.04       0  3391.4    0.05       0  3569.1    0.03       0
  3604.5    0.05       0  3712.9    0.12       0  3741.8    0.05       0
  4044.7    0.12       0  4593.1     0.1       0  5015.2    0.05       0
  5024.3     0.1       0  5125.2    0.12       0
Bank Sta=5015.2,5024.3
Exp/Cntr=0.3,0.1

Type RM Length L Ch R = 1,372,0,0,0
BEGIN DESCRIPTION:
Mapping XS 0cd1223b
END DESCRIPTION:
XS GIS Cut Line= 5
      2495030.46     13555271.35      2495668.49     13554628.97
      2496454.08     13554199.28      2496545.23     13553773.94
      2496015.78     13553339.96
#Sta/Elev= 30
  3071.7  261.67  3167.2  259.70  3312.5  256.25  3434.3  253.20  3456.1  252.60
  3569.4  250.53  3708.7  250.53  3824.3  252.35  3920.9  253.79  4030.1  253.01
  4337.9  246.23  4475.0  246.17  4508.8  245.06  4543.2  246.27  4657.0  244.87
  4853.3  245.11  4869.4  244.36  4964.3  244.04  4964.8  243.54  4973.5  244.04
  5044.8  244.49  5138.5  248.99  5145.7  248.58  5296.2  254.86  5425.3  255.64
  5619.0  257.92  5641.3  257.36  5813.6  258.69  5911.1  259.95  5992.1  258.58
#Mann=13,-1,0
  3071.7    0.04       0  3167.2    0.05       0  3312.5    0.03       0
  3434.3    0.05       0  3456.1    0.12       0  3569.4    0.05       0
  3824.3    0.12       0  4475.0     0.1       0  4964.3    0.05       0
  4973.5     0.1       0  5145.7    0.12       0  5425.3    0.05       0
  5813.6    0.12       0
Bank Sta=4964.3,4973.5
Exp/Cntr=0.3,0.1

Chan Stop Cuts=-1