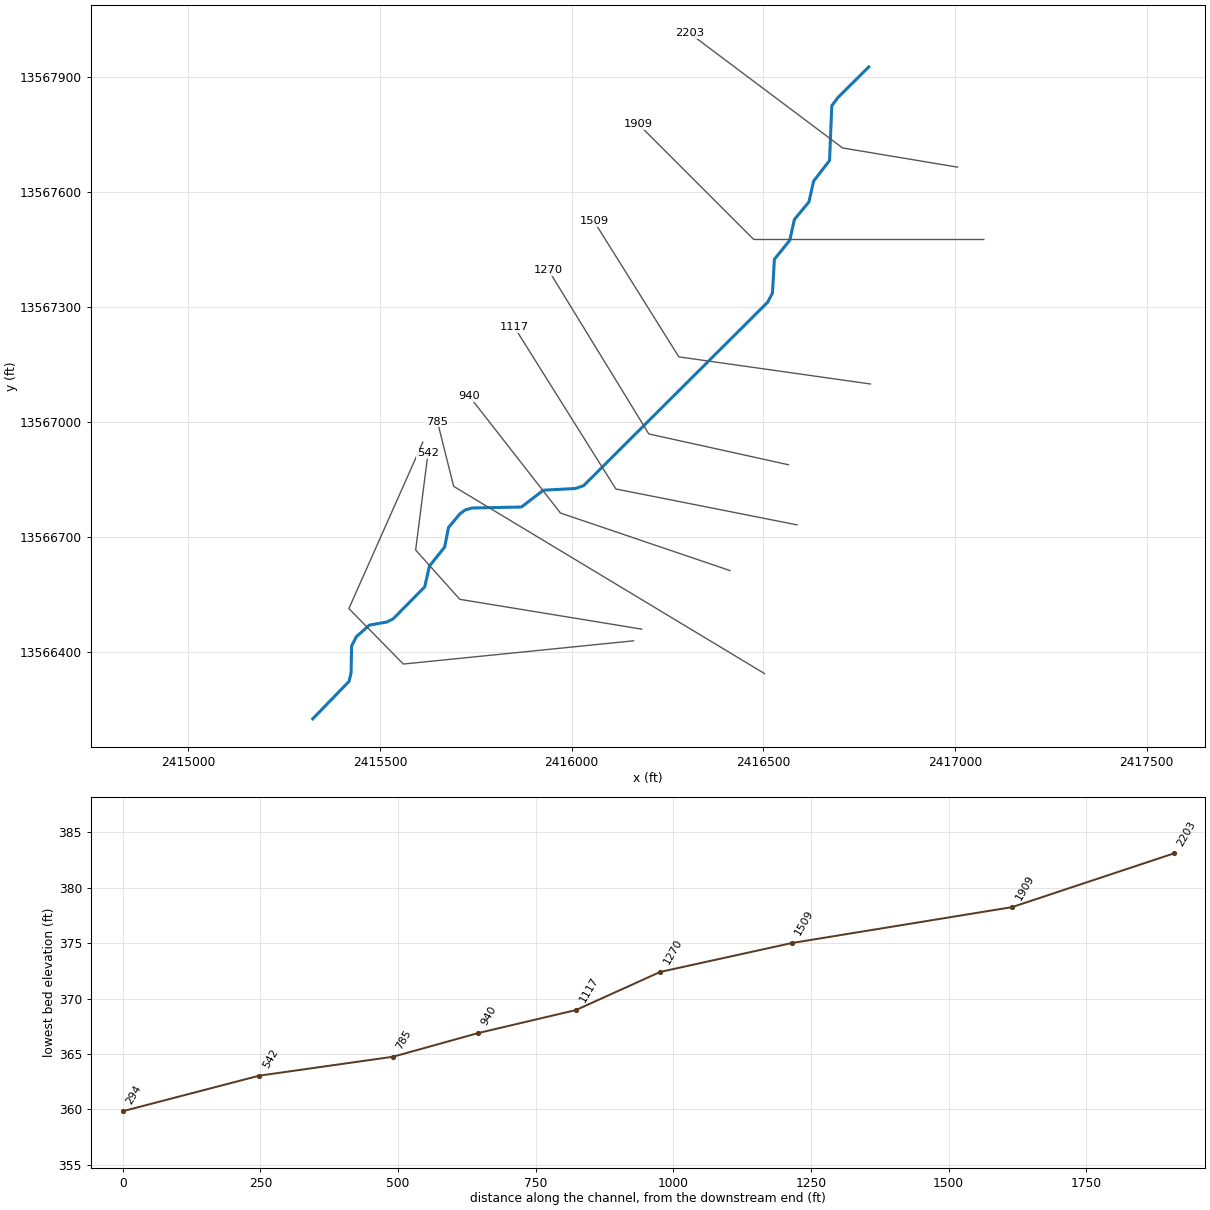
--- TRIB 6 TO SALT CREEK.prj (project) ---

Proj Title=TRIB 6 TO SALT CREEK Base Level Engineering
Current Plan=p01
Default Exp/Contr=0.3,0.1
English Units
Geom File=g01
Flow File=f01
Plan File=p01
BEGIN DESCRIPTION:
TRIB 6 TO SALT CREEK
END DESCRIPTION:

--- TRIB 6 TO SALT CREEK.p01 (plan) ---

Plan Title=Multiple Run
Short Identifier=Multiple
Geom File=g01
Flow File=f01
Subcritical Flow
K Sum by GR= 0
Std Step Tol= 0.01
Critical Tol= 0.01
Num of Std Step Trials= 20
Max Error Tol= 0.3
Flow Tol Ratio= 0.001
Split Flow NTrial= 30
Split Flow Tol= 0.02
Split Flow Ratio= 0.02
Log Output Level= 0
Friction Slope Method= 1
Unsteady Friction Slope Method= 2
Unsteady Bridges Friction Slope Method= 1
Parabolic Critical Depth
Global Vel Dist=  1 , 1 , 1
Global Log Level= 0
CheckData=True
Encroach Param= -1, 0, 0, 0
BEGIN DESCRIPTION:
Multiple Run
END DESCRIPTION:

--- TRIB 6 TO SALT CREEK.f01 (steady flow) ---

Flow Title=Multiple
Number of Profiles=7
Profile Names=10-year,25-year,50-year,1pct_min,100-year,1pct_plu,500-year
River Rch & RM= TRIB 6 TO SALT C,Reach-1,2203
     301     472     621     398     794    1583    1281
Boundary for River Rch & Prof#=TRIB 6 TO SALT C,Reach-1,1
Up Type=0
Dn Type=3
Dn Slope=0.005
Boundary for River Rch & Prof#=TRIB 6 TO SALT C,Reach-1,2
Up Type=0
Dn Type=3
Dn Slope=0.005
Boundary for River Rch & Prof#=TRIB 6 TO SALT C,Reach-1,3
Up Type=0
Dn Type=3
Dn Slope=0.005
Boundary for River Rch & Prof#=TRIB 6 TO SALT C,Reach-1,4
Up Type=0
Dn Type=3
Dn Slope=0.005
Boundary for River Rch & Prof#=TRIB 6 TO SALT C,Reach-1,5
Up Type=0
Dn Type=3
Dn Slope=0.005
Boundary for River Rch & Prof#=TRIB 6 TO SALT C,Reach-1,6
Up Type=0
Dn Type=3
Dn Slope=0.005
Boundary for River Rch & Prof#=TRIB 6 TO SALT C,Reach-1,7
Up Type=0
Dn Type=3
Dn Slope=0.005

--- TRIB 6 TO SALT CREEK.g01 (geometry) ---

Geom Title=Existing Conditions

River Reach=TRIB 6 TO SALT C,Reach-1
Reach XY= 30
      2416775.00     13567925.00      2416694.50     13567845.21
      2416678.49     13567823.55      2416672.75     13567680.93
      2416631.12     13567627.18      2416618.92     13567572.80
      2416581.08     13567527.20      2416568.88     13567472.82
      2416528.83     13567423.41      2416523.84     13567335.48
      2416511.60     13567311.70      2416031.17     13566832.86
      2416009.78     13566825.52      2415926.60     13566821.14
      2415869.06     13566777.27      2415740.04     13566774.66
      2415722.30     13566769.64      2415707.86     13566758.72
      2415678.85     13566723.61      2415668.89     13566672.84
      2415629.19     13566623.26      2415616.87     13566568.93
      2415534.68     13566485.78      2415518.92     13566477.55
      2415472.43     13566469.26      2415438.26     13566438.65
      2415426.10     13566414.67      2415424.87     13566345.06
      2415419.54     13566322.55      2415325.00     13566225.00

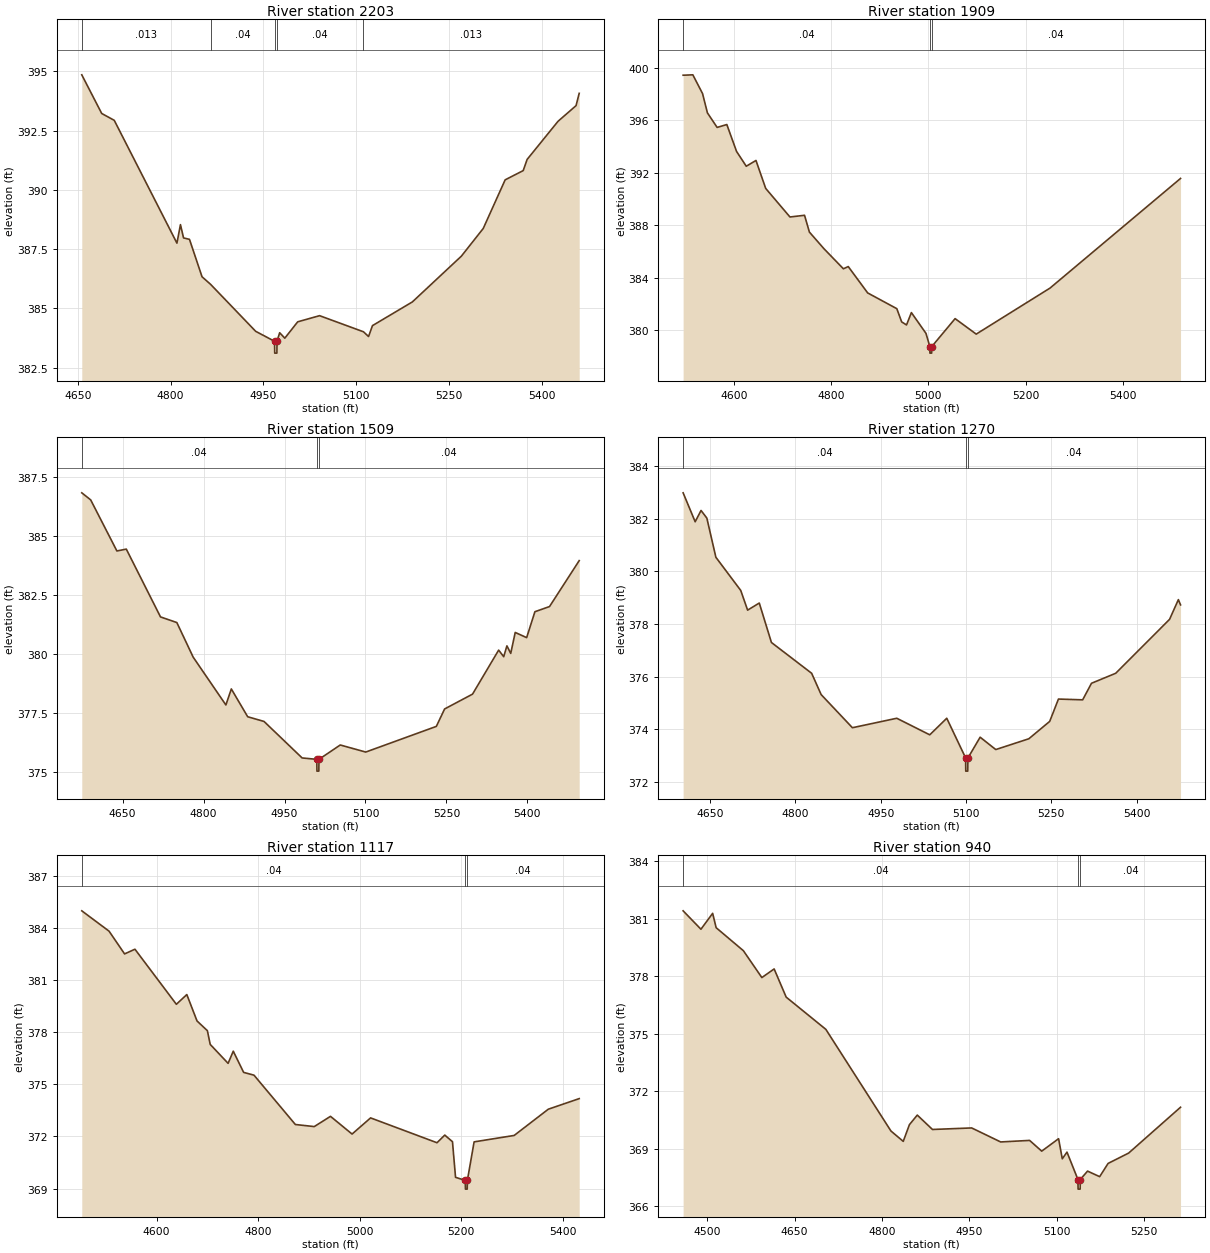
Type RM Length L Ch R = 1,2203,294,294,294
BEGIN DESCRIPTION:
TRIB 6 TO SALT CREEK 3.0
END DESCRIPTION:
XS GIS Cut Line= 3
      2417006.74     13567663.69      2416706.75     13567713.69
      2416306.77     13568013.67
#Sta/Elev= 30
  4656.4  394.85  4688.6  393.22  4708.9  392.93  4810.2  387.75  4815.9  388.53
  4820.9  387.97  4830.5  387.91  4850.8  386.33  4864.7  386.01  4937.5  384.03
  4968.0  383.61  4968.3  383.11  4971.8  383.11  4972.0  383.61  4976.3  383.97
  4984.6  383.74  5005.4  384.43  5040.8  384.69  5111.8  384.01  5120.0  383.81
  5126.3  384.27  5190.8  385.27  5270.0  387.20  5305.4  388.37  5340.8  390.42
  5370.0  390.81  5376.3  391.28  5426.3  392.89  5455.4  393.55  5460.5  394.07
#Mann=5,-1,0
  4656.4   0.013       0  4864.7    0.04       0  4968.0    0.04       0
  4972.0    0.04       0  5111.8   0.013       0
Bank Sta=4968,4972
Exp/Cntr=0.3,0.1

Type RM Length L Ch R = 1,1909,400,400,400
BEGIN DESCRIPTION:
TRIB 6 TO SALT CREEK 2.0
END DESCRIPTION:
XS GIS Cut Line= 3
      2417074.96     13567475.00      2416475.00     13567475.00
      2416175.02     13567774.98
#Sta/Elev= 30
  4495.0  399.45  4515.0  399.48  4535.0  398.05  4545.0  396.58  4565.0  395.47
  4585.0  395.69  4605.0  393.64  4625.0  392.51  4645.0  392.95  4665.0  390.82
  4715.0  388.64  4745.0  388.77  4755.0  387.49  4785.0  386.22  4825.0  384.69
  4835.0  384.86  4875.0  382.85  4935.0  381.65  4945.0  380.64  4955.0  380.41
  4965.0  381.35  4995.0  379.77  5003.0  378.76  5003.2  378.26  5006.7  378.26
  5007.0  378.76  5055.0  380.89  5098.5  379.71  5250.5  383.22  5519.2  391.58
#Mann=3,-1,0
  4495.0    0.04       0  5003.0    0.04       0  5007.0    0.04       0
Bank Sta=5003,5007
Exp/Cntr=0.3,0.1

Type RM Length L Ch R = 1,1509,239,239,239
BEGIN DESCRIPTION:
Mapping XS ec1d4a75
END DESCRIPTION:
XS GIS Cut Line= 3
      2416779.42     13567098.12      2416279.66     13567168.86
      2416058.31     13567522.57
#Sta/Elev= 30
  4574.2  386.84  4590.7  386.54  4639.3  384.37  4656.7  384.45  4720.1  381.57
  4750.4  381.33  4780.7  379.86  4841.3  377.83  4851.4  378.51  4881.7  377.33
  4912.0  377.13  4982.6  375.58  5009.8  375.52  5010.1  375.02  5013.6  375.02
  5013.8  375.52  5053.3  376.13  5100.5  375.83  5231.4  376.92  5246.7  377.66
  5298.5  378.29  5346.9  380.16  5356.3  379.88  5362.2  380.34  5369.3  380.02
  5377.6  380.91  5398.8  380.69  5414.1  381.79  5441.2  382.01  5496.2  383.96
#Mann=3,-1,0
  4574.2    0.04       0  5009.8    0.04       0  5013.8    0.04       0
Bank Sta=5009.8,5013.8
Exp/Cntr=0.3,0.1

Type RM Length L Ch R = 1,1270,153,153,153
BEGIN DESCRIPTION:
4855
END DESCRIPTION:
XS GIS Cut Line= 3
      2416565.74     13566887.46      2416201.37     13566967.84
      2415939.39     13567395.55
#Sta/Elev= 30
  4602.5  382.99  4623.7  381.89  4634.0  382.32  4644.2  382.03  4660.1  380.54
  4703.8  379.28  4715.9  378.53  4736.4  378.80  4757.8  377.30  4828.5  376.13
  4845.2  375.32  4900.2  374.06  4978.2  374.42  5036.2  373.79  5066.1  374.42
  5099.3  372.91  5099.5  372.41  5103.0  372.41  5103.3  372.91  5124.8  373.70
  5152.3  373.23  5210.4  373.64  5247.1  374.30  5262.5  375.15  5305.1  375.12
  5320.6  375.75  5363.2  376.13  5457.9  378.18  5473.4  378.93  5477.2  378.73
#Mann=3,-1,0
  4602.5    0.04       0  5099.3    0.04       0  5103.3    0.04       0
Bank Sta=5099.3,5103.3
Exp/Cntr=0.3,0.1

Type RM Length L Ch R = 1,1117,177,177,177
BEGIN DESCRIPTION:
Mapping XS d33a0bb7
END DESCRIPTION:
XS GIS Cut Line= 3
      2416587.72     13566730.73      2416115.36     13566824.29
      2415850.66     13567246.44
#Sta/Elev= 30
  4452.6  384.99  4506.3  383.82  4536.9  382.51  4557.3  382.78  4638.9  379.61
  4659.5  380.17  4679.6  378.65  4700.0  378.09  4705.6  377.30  4740.8  376.21
  4751.0  376.91  4771.4  375.69  4791.8  375.53  4873.3  372.69  4910.5  372.57
  4942.5  373.16  4985.0  372.14  5021.5  373.07  5152.3  371.64  5167.6  372.08
  5182.8  371.70  5188.8  369.65  5208.1  369.47  5208.3  368.97  5211.8  368.97
  5212.1  369.47  5225.4  371.69  5304.3  372.06  5371.5  373.57  5432.4  374.18
#Mann=3,-1,0
  4452.6    0.04       0  5208.1    0.04       0  5212.1    0.04       0
Bank Sta=5208.1,5212.1
Exp/Cntr=0.3,0.1

Type RM Length L Ch R = 1,940,155,155,155
BEGIN DESCRIPTION:
4854
END DESCRIPTION:
XS GIS Cut Line= 3
      2416412.98     13566611.53      2415970.97     13566761.55
      2415732.56     13567066.93
#Sta/Elev= 30
  4458.6  381.41  4489.2  380.45  4509.3  381.28  4515.3  380.53  4562.1  379.33
  4593.8  377.93  4614.9  378.38  4635.6  376.91  4703.7  375.23  4815.5  369.93
  4836.6  369.39  4847.2  370.26  4860.7  370.76  4886.8  370.01  4954.1  370.09
  5003.9  369.36  5053.6  369.44  5074.4  368.88  5103.4  369.53  5109.7  368.48
  5117.8  368.83  5136.6  367.40  5136.9  366.90  5140.4  366.90  5140.6  367.40
  5153.1  367.84  5173.9  367.55  5188.4  368.24  5223.7  368.78  5312.8  371.17
#Mann=3,-1,0
  4458.6    0.04       0  5136.6    0.04       0  5140.6    0.04       0
Bank Sta=5136.6,5140.6
Exp/Cntr=0.3,0.1

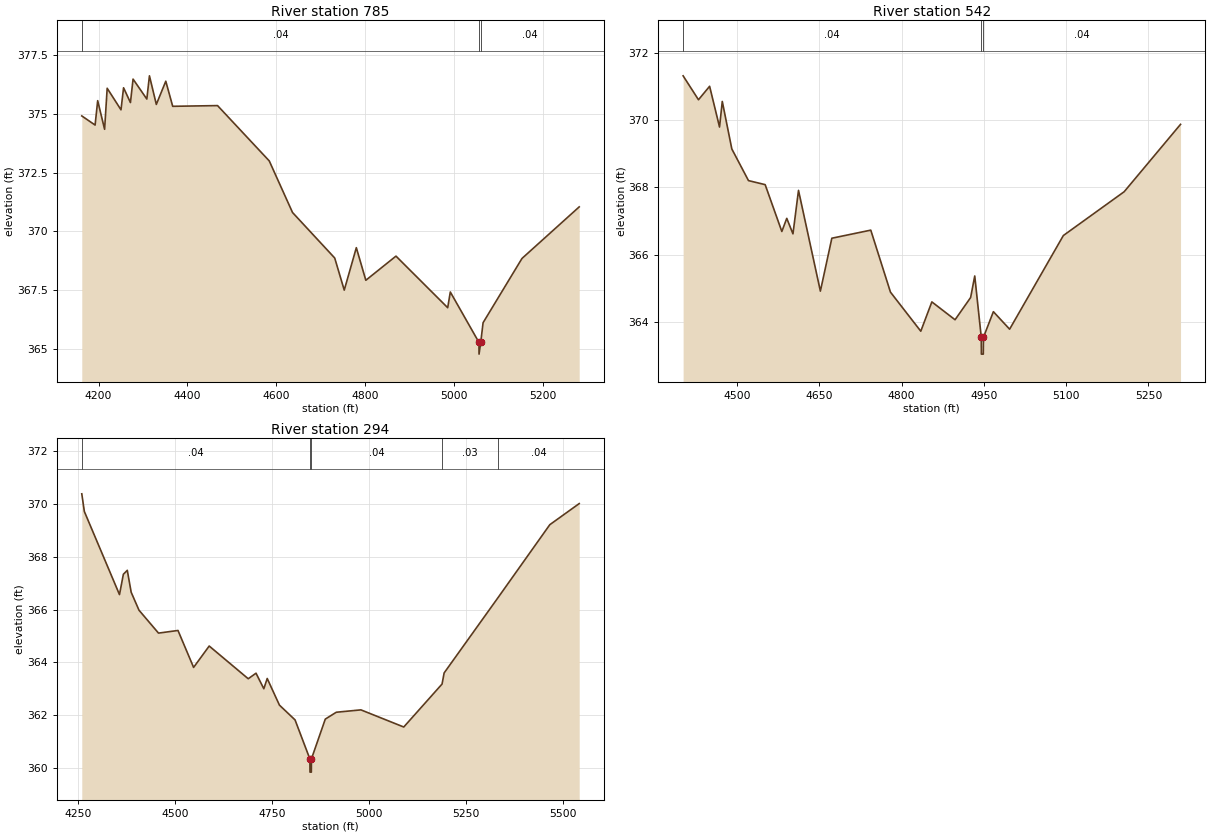
Type RM Length L Ch R = 1,785,243,243,243
BEGIN DESCRIPTION:
TRIB 6 TO SALT CREEK 1.0
END DESCRIPTION:
XS GIS Cut Line= 3
      2416503.04     13566342.92      2415692.34     13566831.20
      2415650.00     13566999.99
#Sta/Elev= 30
  4162.1  374.92  4192.1  374.53  4197.9  375.57  4213.5  374.35  4219.3  376.10
  4250.4  375.18  4256.2  376.12  4271.7  375.49  4277.6  376.49  4308.6  375.64
  4314.5  376.63  4330.0  375.41  4351.3  376.40  4366.9  375.33  4467.9  375.36
  4584.4  373.00  4636.8  370.80  4731.8  368.86  4753.3  367.49  4780.5  369.30
  4801.9  367.91  4869.8  368.94  4986.3  366.74  4992.2  367.41  5056.7  365.26
  5056.9  364.76  5060.7  365.26  5066.0  366.10  5153.6  368.84  5282.5  371.04
#Mann=3,-1,0
  4162.1    0.04       0  5056.7    0.04       0  5060.7    0.04       0
Bank Sta=5056.7,5060.7
Exp/Cntr=0.3,0.1

Type RM Length L Ch R = 1,542,248,248,248
BEGIN DESCRIPTION:
4853
END DESCRIPTION:
XS GIS Cut Line= 4
      2416182.65     13566458.80      2415708.42     13566536.50
      2415593.22     13566665.10      2415625.37     13566916.95
#Sta/Elev= 30
  4401.5  371.31  4429.5  370.60  4449.8  371.00  4467.9  369.79  4472.9  370.55
  4490.3  369.14  4520.7  368.20  4551.1  368.08  4581.5  366.69  4590.5  367.08
  4601.8  366.62  4611.9  367.91  4651.8  364.92  4672.7  366.49  4743.7  366.73
  4779.6  364.89  4834.9  363.73  4855.1  364.60  4897.4  364.07  4925.8  364.73
  4933.3  365.37  4945.2  363.55  4945.4  363.05  4948.9  363.05  4949.2  363.55
  4967.3  364.31  4996.9  363.79  5094.9  366.57  5205.8  367.87  5308.6  369.87
#Mann=3,-1,0
  4401.5    0.04       0  4945.2    0.04       0  4949.2    0.04       0
Bank Sta=4945.2,4949.2
Exp/Cntr=0.3,0.1

Type RM Length L Ch R = 1,294,0,0,0
BEGIN DESCRIPTION:
4852
END DESCRIPTION:
XS GIS Cut Line= 4
      2416161.56     13566428.27      2415561.07     13566367.72
      2415419.08     13566512.39      2415611.97     13566946.41
#Sta/Elev= 30
  4260.3  370.39  4266.9  369.72  4357.4  366.57  4367.4  367.34  4377.5  367.49
  4387.5  366.66  4407.6  365.98  4457.9  365.11  4508.1  365.21  4548.3  363.81
  4588.5  364.62  4689.0  363.38  4709.1  363.59  4729.2  363.00  4737.9  363.39
  4769.4  362.38  4809.6  361.82  4847.8  360.34  4848.1  359.84  4851.6  359.84
  4851.8  360.34  4887.5  361.85  4915.8  362.11  4979.3  362.20  5089.6  361.55
  5188.3  363.18  5193.6  363.60  5332.2  366.45  5465.8  369.22  5541.5  370.02
#Mann=5,-1,0
  4260.3    0.04       0  4847.8    0.04       0  4851.8    0.04       0
  5188.3    0.03       0  5332.2    0.04       0
Bank Sta=4847.8,4851.8
Exp/Cntr=0.3,0.1

Chan Stop Cuts=-1