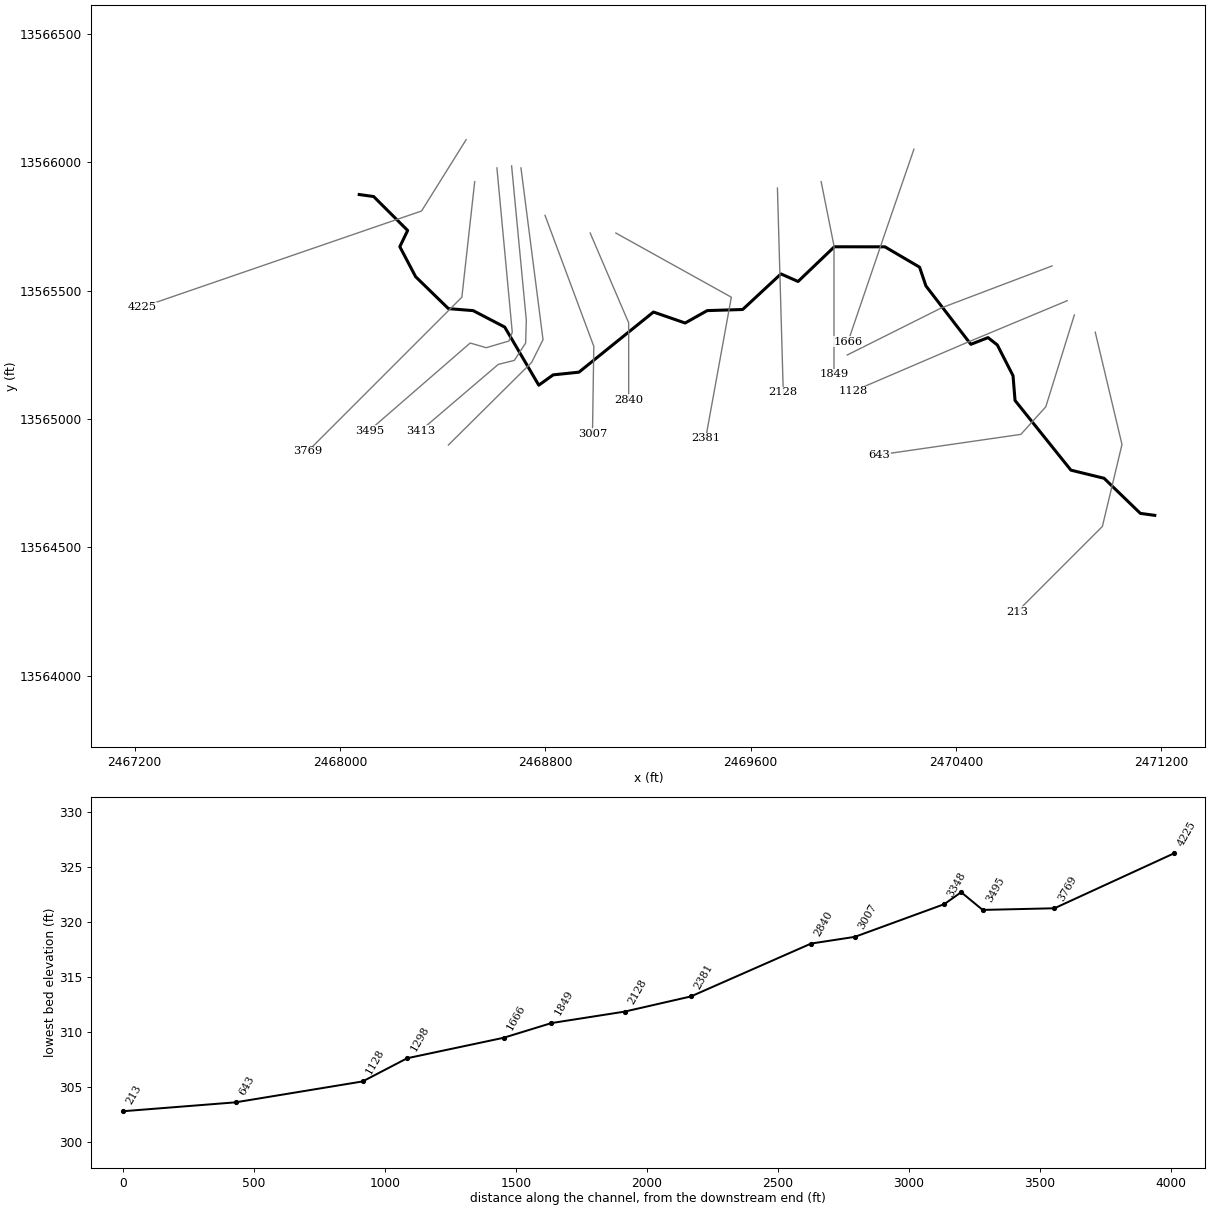
--- TRIB 6 TO SHILOH CREEK.prj (project) ---

Proj Title=TRIB 6 TO SHILOH CREEK Base Level Engineering
Current Plan=p01
Default Exp/Contr=0.3,0.1
English Units
Geom File=g01
Flow File=f01
Plan File=p01
BEGIN DESCRIPTION:
TRIB 6 TO SHILOH CREEK
END DESCRIPTION:

--- TRIB 6 TO SHILOH CREEK.p01 (plan) ---

Plan Title=Multiple Run
Short Identifier=Multiple
Geom File=g01
Flow File=f01
Subcritical Flow
K Sum by GR= 0
Std Step Tol= 0.01
Critical Tol= 0.01
Num of Std Step Trials= 20
Max Error Tol= 0.3
Flow Tol Ratio= 0.001
Split Flow NTrial= 30
Split Flow Tol= 0.02
Split Flow Ratio= 0.02
Log Output Level= 0
Friction Slope Method= 1
Unsteady Friction Slope Method= 2
Unsteady Bridges Friction Slope Method= 1
Parabolic Critical Depth
Global Vel Dist=  1 , 1 , 1
Global Log Level= 0
CheckData=True
Encroach Param= -1, 0, 0, 0
BEGIN DESCRIPTION:
Multiple Run
END DESCRIPTION:

--- TRIB 6 TO SHILOH CREEK.f01 (steady flow) ---

Flow Title=Multiple
Number of Profiles=7
Profile Names=10-year,25-year,50-year,1pct_min,100-year,1pct_plu,500-year
River Rch & RM= TRIB 6 TO SHILOH,Reach-1,4225
     459     731     973     629    1255    2504    2065
River Rch & RM= TRIB 6 TO SHILOH,Reach-1,2128
     493     787    1050     680    1356    2706    2237
Boundary for River Rch & Prof#=TRIB 6 TO SHILOH,Reach-1,1
Up Type=0
Dn Type=3
Dn Slope=0.005
Boundary for River Rch & Prof#=TRIB 6 TO SHILOH,Reach-1,2
Up Type=0
Dn Type=3
Dn Slope=0.005
Boundary for River Rch & Prof#=TRIB 6 TO SHILOH,Reach-1,3
Up Type=0
Dn Type=3
Dn Slope=0.005
Boundary for River Rch & Prof#=TRIB 6 TO SHILOH,Reach-1,4
Up Type=0
Dn Type=3
Dn Slope=0.005
Boundary for River Rch & Prof#=TRIB 6 TO SHILOH,Reach-1,5
Up Type=0
Dn Type=3
Dn Slope=0.005
Boundary for River Rch & Prof#=TRIB 6 TO SHILOH,Reach-1,6
Up Type=0
Dn Type=3
Dn Slope=0.005
Boundary for River Rch & Prof#=TRIB 6 TO SHILOH,Reach-1,7
Up Type=0
Dn Type=3
Dn Slope=0.005

--- TRIB 6 TO SHILOH CREEK.g01 (geometry) ---

Geom Title=Existing Conditions

River Reach=TRIB 6 TO SHILOH,Reach-1
Reach XY= 30
      2468075.00     13565875.00      2468131.21     13565867.24
      2468263.76     13565735.00      2468233.25     13565671.77
      2468294.77     13565554.91      2468422.57     13565430.52
      2468519.03     13565422.67      2468642.06     13565358.52
      2468774.69     13565132.22      2468830.88     13565172.43
      2468931.16     13565182.88      2469221.58     13565417.20
      2469345.04     13565374.42      2469430.94     13565422.73
      2469569.14     13565427.07      2469718.33     13565565.70
      2469785.00     13565536.24      2469926.46     13565671.46
      2470123.45     13565671.25      2470258.51     13565592.05
      2470283.18     13565518.98      2470458.30     13565291.38
      2470525.21     13565317.53      2470561.38     13565289.00
      2470622.67     13565169.03      2470630.54     13565072.58
      2470848.13     13564801.18      2470977.43     13564769.48
      2471118.79     13564632.76      2471175.00     13564625.00

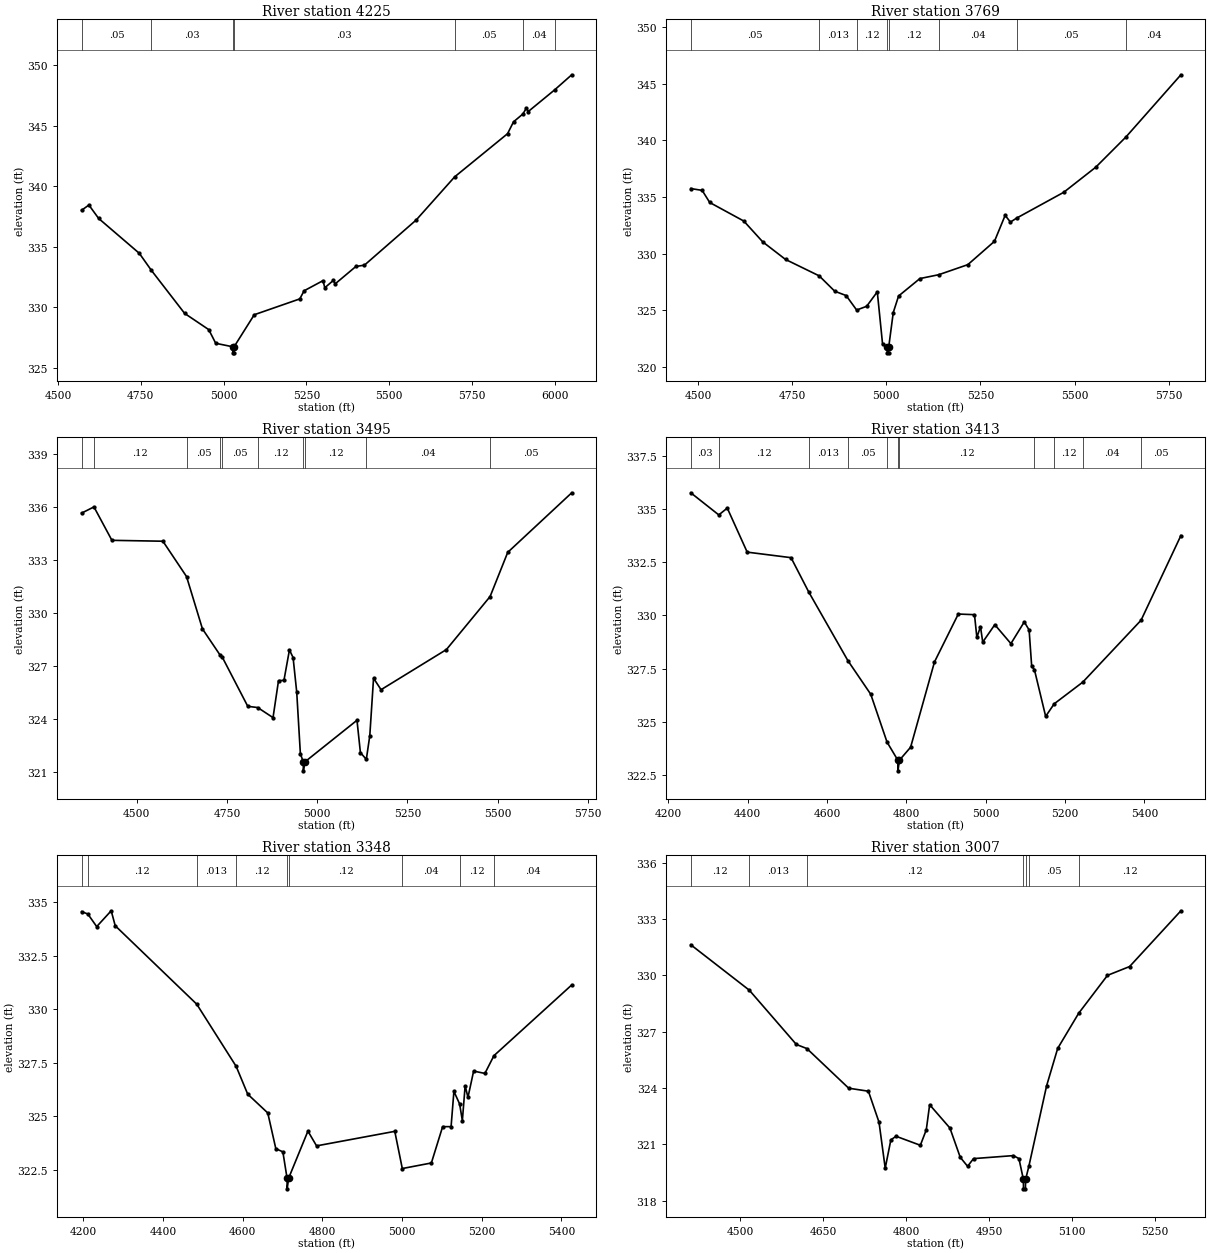
Type RM Length L Ch R = 1,4225,456,456,456
BEGIN DESCRIPTION:
TRIB 6 TO SHILOH CREEK 8.0
END DESCRIPTION:
XS GIS Cut Line= 3
      2468491.64     13566088.70      2468318.02     13565810.91
      2467228.84     13565436.28
#Sta/Elev= 30
  4571.3  338.01  4593.3  338.44  4622.8  337.33  4745.4  334.45  4781.6  333.05
  4882.3  329.48  4955.0  328.14  4976.1  327.01  5027.5  326.72  5027.7  326.22
  5031.2  326.22  5031.5  326.72  5092.4  329.37  5229.9  330.68  5242.8  331.35
  5300.0  332.19  5305.3  331.60  5331.2  332.21  5336.5  331.92  5399.1  333.36
  5425.0  333.47  5581.1  337.20  5697.3  340.77  5857.0  344.34  5875.0  345.32
  5903.3  345.97  5914.1  346.47  5919.4  346.17  5999.0  347.96  6050.7  349.21
#Mann=7,-1,0
  4571.3    0.05       0  4781.6    0.03       0  5027.5    0.03       0
  5031.5    0.03       0  5697.3    0.05       0  5903.3    0.04       0
  5999.0    0.05       0
Bank Sta=5027.5,5031.5
Exp/Cntr=0.3,0.1

Type RM Length L Ch R = 1,3769,274,274,274
BEGIN DESCRIPTION:
TRIB 6 TO SHILOH CREEK 7.0
END DESCRIPTION:
XS GIS Cut Line= 3
      2468525.00     13565924.98      2468475.00     13565475.00
      2467874.98     13564874.98
#Sta/Elev= 30
  4480.9  335.74  4511.1  335.58  4531.2  334.51  4621.7  332.87  4672.0  331.03
  4732.4  329.48  4821.8  328.03  4863.2  326.67  4893.4  326.29  4921.3  325.01
  4947.8  325.34  4976.1  326.62  4990.2  321.97  5002.4  321.73  5002.6  321.23
  5006.1  321.23  5006.4  321.73  5018.5  324.79  5032.6  326.25  5089.2  327.79
  5139.2  328.13  5216.5  329.02  5287.2  331.08  5315.5  333.37  5329.6  332.78
  5346.0  333.13  5471.1  335.41  5555.9  337.62  5636.1  340.29  5782.2  345.79
#Mann=8,-1,0
  4480.9    0.05       0  4821.8   0.013       0  4921.3    0.12       0
  5002.4    0.05       0  5006.4    0.12       0  5139.2    0.04       0
  5346.0    0.05       0  5636.1    0.04       0
Bank Sta=5002.4,5006.4
Exp/Cntr=0.3,0.1

Type RM Length L Ch R = 1,3495,82,82,82
BEGIN DESCRIPTION:
Mapping XS 9f8c21d9
END DESCRIPTION:
XS GIS Cut Line= 6
      2468611.55     13565978.71      2468671.44     13565338.12
      2468658.42     13565304.27      2468569.88     13565278.22
      2468507.38     13565296.45      2468114.18     13564955.34
#Sta/Elev= 30
  4347.2  335.66  4381.4  336.01  4431.2  334.12  4572.5  334.07  4638.0  332.07
  4682.1  329.11  4731.6  327.61  4736.6  327.53  4807.7  324.73  4835.3  324.66
  4877.7  324.09  4892.9  326.18  4908.0  326.20  4923.2  327.92  4933.3  327.49
  4943.4  325.53  4953.5  322.05  4961.6  321.58  4961.8  321.08  4965.6  321.58
  5110.4  323.94  5119.9  322.11  5136.3  321.73  5145.9  323.07  5156.3  326.32
  5177.1  325.67  5358.2  327.94  5479.3  330.94  5528.2  333.44  5705.6  336.81
#Mann=10,-1,0
  4347.2    0.03       0  4381.4    0.12       0  4638.0    0.05       0
  4731.6   0.013       0  4736.6    0.05       0  4835.3    0.12       0
  4961.6    0.05       0  4965.6    0.12       0  5136.3    0.04       0
  5479.3    0.05       0
Bank Sta=4961.6,4965.6
Exp/Cntr=0.3,0.1

Type RM Length L Ch R = 1,3413,65,65,65
BEGIN DESCRIPTION:
Mapping XS 2ffa9da7
END DESCRIPTION:
XS GIS Cut Line= 6
      2468668.84     13565986.59      2468726.13     13565385.00
      2468723.53     13565296.45      2468679.26     13565228.75
      2468616.76     13565213.12      2468314.64     13564955.28
#Sta/Elev= 30
  4256.7  335.76  4327.3  334.72  4348.7  335.04  4398.9  332.97  4509.4  332.71
  4553.9  331.10  4652.7  327.87  4710.3  326.29  4751.4  324.04  4778.6  323.19
  4778.9  322.69  4782.6  323.19  4810.8  323.80  4871.0  327.81  4931.0  330.06
  4971.8  330.03  4977.8  328.96  4986.9  329.47  4992.6  328.74  5023.0  329.56
  5063.6  328.67  5097.3  329.69  5109.5  329.31  5116.0  327.60  5122.8  327.45
  5151.2  325.25  5172.7  325.84  5244.8  326.86  5391.7  329.77  5492.1  333.75
#Mann=11,-1,0
  4256.7    0.03       0  4327.3    0.12       0  4553.9   0.013       0
  4652.7    0.05       0  4751.4    0.12       0  4778.6    0.05       0
  4782.6    0.12       0  5122.8    0.04       0  5172.7    0.12       0
  5244.8    0.04       0  5391.7    0.05       0
Bank Sta=4778.6,4782.6
Exp/Cntr=0.3,0.1

Type RM Length L Ch R = 1,3348,341,341,341
BEGIN DESCRIPTION:
Mapping XS 68ccd877
END DESCRIPTION:
XS GIS Cut Line= 4
      2468705.30     13565978.70      2468791.24     13565309.47
      2468746.96     13565220.93      2468422.46     13564899.03
#Sta/Elev= 30
  4195.3  334.57  4210.9  334.46  4233.2  333.87  4269.6  334.61  4279.7  333.91
  4484.4  330.24  4583.4  327.33  4612.4  326.03  4662.8  325.15  4683.0  323.48
  4700.7  323.33  4711.2  322.10  4711.5  321.60  4715.2  322.10  4763.6  324.30
  4785.3  323.61  4981.7  324.29  5000.6  322.55  5073.6  322.81  5101.9  324.51
  5123.1  324.51  5130.2  326.16  5144.6  325.57  5151.4  324.79  5158.4  326.42
  5165.5  325.88  5179.7  327.11  5208.0  327.00  5230.7  327.83  5426.1  331.14
#Mann=9,-1,0
  4195.3    0.03       0  4210.9    0.12       0  4484.4   0.013       0
  4583.4    0.12       0  4711.2    0.05       0  4715.2    0.12       0
  5000.6    0.04       0  5144.6    0.12       0  5230.7    0.04       0
Bank Sta=4711.2,4715.2
Exp/Cntr=0.3,0.1

Type RM Length L Ch R = 1,3007,167,167,167
BEGIN DESCRIPTION:
Mapping XS 8add7954
END DESCRIPTION:
XS GIS Cut Line= 3
      2468799.06     13565793.82      2468989.15     13565283.43
      2468983.94     13564942.31
#Sta/Elev= 30
  4410.7  331.63  4516.5  329.21  4601.5  326.32  4620.6  326.10  4696.1  323.99
  4731.7  323.83  4750.9  322.18  4762.1  319.73  4772.3  321.24  4781.7  321.43
  4825.6  320.95  4836.3  321.77  4842.4  323.11  4879.0  321.87  4897.7  320.31
  4911.0  319.83  4921.7  320.24  4993.8  320.40  5003.8  320.24  5011.8  319.13
  5012.0  318.63  5015.5  318.63  5015.8  319.13  5021.7  319.83  5053.8  324.12
  5073.8  326.11  5111.7  327.98  5163.8  330.00  5203.8  330.47  5296.5  333.44
#Mann=7,-1,0
  4410.7    0.12       0  4516.5   0.013       0  4620.6    0.12       0
  5011.8    0.05       0  5015.8    0.12       0  5021.7    0.05       0
  5111.7    0.12       0
Bank Sta=5011.8,5015.8
Exp/Cntr=0.3,0.1

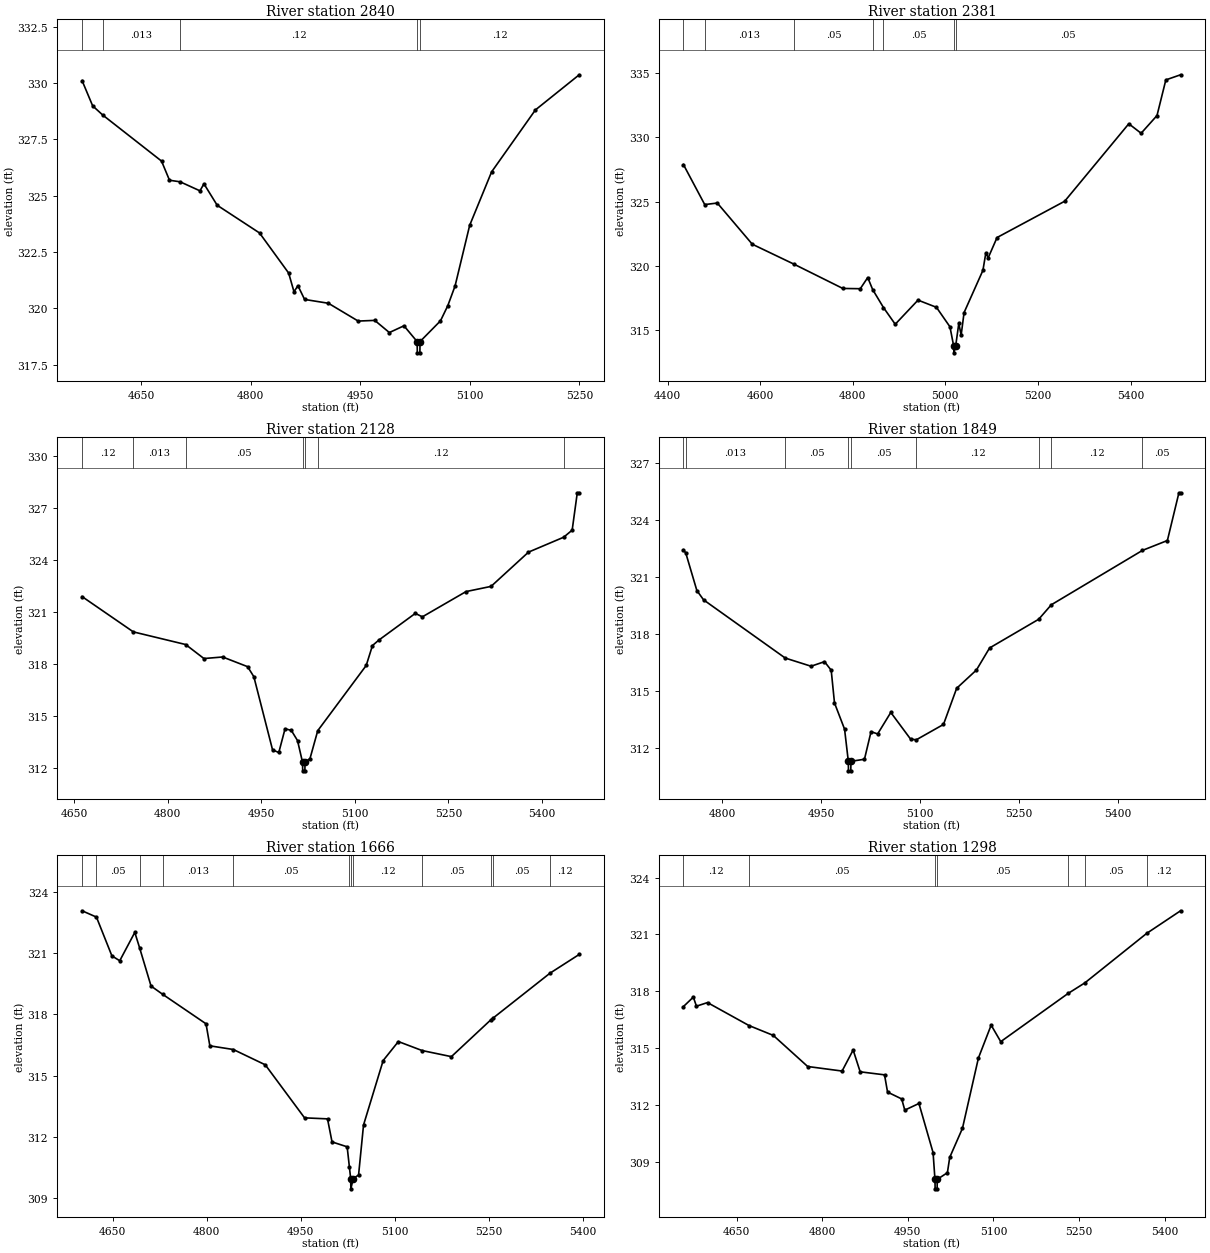
Type RM Length L Ch R = 1,2840,459,459,459
BEGIN DESCRIPTION:
TRIB 6 TO SHILOH CREEK 5.0
END DESCRIPTION:
XS GIS Cut Line= 3
      2468974.99     13565725.03      2469125.00     13565375.00
      2469125.00     13565075.02
#Sta/Elev= 30
  4568.9  330.10  4583.4  328.98  4597.3  328.57  4677.7  326.53  4688.6  325.68
  4703.2  325.61  4730.3  325.21  4735.8  325.52  4753.9  324.57  4811.9  323.34
  4851.8  321.56  4859.1  320.73  4864.5  321.00  4873.6  320.39  4906.2  320.22
  4947.0  319.43  4969.7  319.46  4989.7  318.92  5009.7  319.22  5027.7  318.52
  5028.0  318.02  5031.5  318.02  5031.7  318.52  5059.7  319.44  5069.7  320.11
  5079.7  320.99  5099.7  323.68  5129.7  326.05  5189.7  328.80  5249.7  330.36
#Mann=5,-1,0
  4568.9    0.12       0  4597.3   0.013       0  4703.2    0.12       0
  5027.7    0.05       0  5031.7    0.12       0
Bank Sta=5027.7,5031.7
Exp/Cntr=0.3,0.1

Type RM Length L Ch R = 1,2381,253,253,253
BEGIN DESCRIPTION:
TRIB 6 TO SHILOH CREEK 4.0
END DESCRIPTION:
XS GIS Cut Line= 3
      2469075.03     13565724.98      2469525.00     13565475.00
      2469424.99     13564924.96
#Sta/Elev= 30
  4434.2  327.89  4480.2  324.77  4507.4  324.89  4582.9  321.68  4673.2  320.12
  4778.5  318.23  4816.2  318.21  4832.3  319.08  4843.0  318.14  4866.3  316.74
  4891.7  315.44  4940.9  317.32  4980.7  316.76  5009.9  315.24  5018.1  313.71
  5018.3  313.21  5022.1  313.71  5029.0  315.50  5034.1  314.60  5040.4  316.35
  5081.1  319.64  5087.4  321.00  5092.5  320.62  5111.6  322.20  5257.7  325.03
  5396.2  331.07  5422.8  330.33  5457.1  331.71  5476.2  334.49  5508.0  334.89
#Mann=7,-1,0
  4434.2    0.12       0  4480.2   0.013       0  4673.2    0.05       0
  4843.0    0.12       0  4866.3    0.05       0  5018.1    0.05       0
  5022.1    0.05       0
Bank Sta=5018.1,5022.1
Exp/Cntr=0.3,0.1

Type RM Length L Ch R = 1,2128,279,279,279
BEGIN DESCRIPTION:
4856
END DESCRIPTION:
XS GIS Cut Line= 2
      2469704.64     13565900.19      2469727.40     13565103.72
#Sta/Elev= 30
  4662.9  321.90  4745.1  319.86  4828.9  319.13  4858.2  318.32  4888.2  318.41
  4928.2  317.85  4938.2  317.27  4968.2  313.04  4978.2  312.89  4988.2  314.26
  4998.2  314.17  5008.2  313.58  5016.2  312.33  5016.5  311.83  5020.0  311.83
  5020.2  312.33  5028.2  312.54  5040.6  314.15  5118.3  317.92  5128.3  319.07
  5138.3  319.38  5197.0  320.93  5208.3  320.73  5278.3  322.19  5318.4  322.49
  5378.4  324.47  5434.7  325.33  5448.4  325.74  5456.6  327.90  5459.7  327.90
#Mann=7,-1,0
  4662.9    0.12       0  4745.1   0.013       0  4828.9    0.05       0
  5016.2    0.05       0  5020.2    0.05       0  5040.6    0.12       0
  5434.7    0.05       0
Bank Sta=5016.2,5020.2
Exp/Cntr=0.3,0.1

Type RM Length L Ch R = 1,1849,183,183,183
BEGIN DESCRIPTION:
TRIB 6 TO SHILOH CREEK 3.0
END DESCRIPTION:
XS GIS Cut Line= 3
      2469875.00     13565924.99      2469925.00     13565675.00
      2469925.00     13565175.04
#Sta/Elev= 30
  4740.8  322.41  4744.4  322.24  4761.2  320.27  4771.4  319.78  4895.4  316.72
  4934.6  316.29  4955.0  316.53  4965.2  316.08  4970.2  314.36  4985.5  312.98
  4991.2  311.29  4991.4  310.79  4994.9  310.79  4995.2  311.29  5015.7  311.40
  5025.7  312.85  5035.7  312.73  5055.7  313.86  5085.7  312.46  5094.3  312.42
  5135.7  313.23  5155.7  315.13  5185.7  316.09  5205.7  317.25  5280.3  318.76
  5299.4  319.52  5437.8  322.38  5475.7  322.90  5493.2  325.41  5495.7  325.41
#Mann=9,-1,0
  4740.8    0.04       0  4744.4   0.013       0  4895.4    0.05       0
  4991.2    0.05       0  4995.2    0.05       0  5094.3    0.12       0
  5280.3    0.05       0  5299.4    0.12       0  5437.8    0.05       0
Bank Sta=4991.2,4995.2
Exp/Cntr=0.3,0.1

Type RM Length L Ch R = 1,1666,368,368,368
BEGIN DESCRIPTION:
Mapping XS 92fda171
END DESCRIPTION:
XS GIS Cut Line= 3
      2470236.56     13566051.69      2470128.91     13565739.16
      2469979.81     13565302.25
#Sta/Elev= 30
  4601.4  323.08  4624.3  322.77  4648.9  320.87  4661.4  320.63  4685.4  322.02
  4693.0  321.27  4711.3  319.39  4729.6  318.99  4798.9  317.54  4805.0  316.46
  4842.4  316.28  4893.3  315.53  4955.9  312.93  4992.5  312.88  4999.7  311.75
  5023.8  311.51  5027.4  310.51  5029.4  309.95  5029.7  309.45  5033.4  309.95
  5042.0  310.13  5049.9  312.58  5081.2  315.74  5105.4  316.67  5143.1  316.23
  5189.9  315.93  5253.3  317.75  5255.9  317.81  5347.0  320.02  5393.6  320.94
#Mann=12,-1,0
  4601.4    0.04       0  4624.3    0.05       0  4693.0    0.04       0
  4729.6   0.013       0  4842.4    0.05       0  5027.4    0.12       0
  5029.4    0.05       0  5033.4    0.12       0  5143.1    0.05       0
  5253.3    0.12       0  5255.9    0.05       0  5347.0    0.12       0
Bank Sta=5029.4,5033.4
Exp/Cntr=0.3,0.1

Type RM Length L Ch R = 1,1298,170,170,170
BEGIN DESCRIPTION:
Mapping XS c5fc5b10
END DESCRIPTION:
XS GIS Cut Line= 3
      2470774.70     13565596.79      2470344.19     13565433.61
      2469976.58     13565249.80
#Sta/Elev= 30
  4556.6  317.20  4574.0  317.70  4579.4  317.22  4598.8  317.41  4671.5  316.20
  4714.1  315.68  4774.4  314.04  4834.7  313.80  4854.1  314.91  4866.4  313.76
  4909.1  313.60  4914.4  312.69  4939.2  312.33  4944.6  311.74  4969.4  312.09
  4994.2  309.50  4997.5  308.09  4997.8  307.59  5001.3  307.59  5001.5  308.09
  5019.3  308.44  5023.4  309.25  5045.7  310.78  5073.7  314.49  5096.0  316.22
  5112.8  315.35  5230.8  317.89  5260.3  318.45  5368.7  321.06  5428.0  322.25
#Mann=7,-1,0
  4556.6    0.12       0  4671.5    0.05       0  4997.5    0.05       0
  5001.5    0.05       0  5230.8    0.12       0  5260.3    0.05       0
  5368.7    0.12       0
Bank Sta=4997.5,5001.5
Exp/Cntr=0.3,0.1

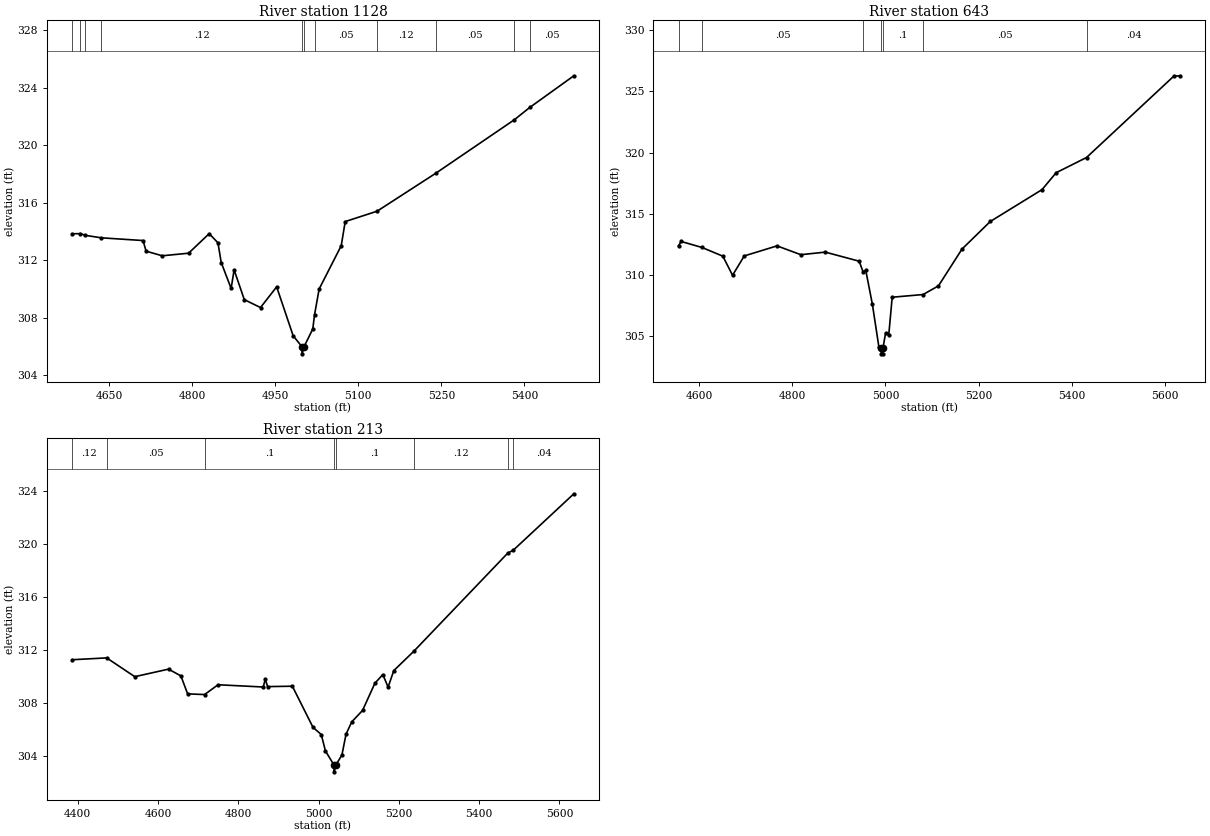
Type RM Length L Ch R = 1,1128,485,485,485
BEGIN DESCRIPTION:
Mapping XS de8c1a3e
END DESCRIPTION:
XS GIS Cut Line= 3
      2470833.78     13565461.39      2470434.46     13565294.72
      2469998.51     13565107.88
#Sta/Elev= 30
  4582.5  313.83  4597.6  313.84  4606.7  313.72  4635.3  313.55  4710.8  313.36
  4716.3  312.62  4745.5  312.30  4793.1  312.48  4830.4  313.84  4846.2  313.20
  4852.1  311.83  4870.0  310.03  4875.4  311.32  4893.8  309.25  4923.1  308.70
  4952.3  310.14  4982.1  306.74  4997.9  305.98  4998.2  305.48  5001.9  305.98
  5017.6  307.21  5020.7  308.18  5029.1  309.99  5069.0  313.00  5076.2  314.68
  5133.8  315.40  5239.5  318.03  5381.9  321.76  5409.9  322.62  5489.5  324.82
#Mann=11,-1,0
  4582.5    0.05       0  4597.6    0.12       0  4606.7    0.05       0
  4635.3    0.12       0  4997.9    0.05       0  5001.9    0.12       0
  5020.7    0.05       0  5133.8    0.12       0  5239.5    0.05       0
  5381.9    0.12       0  5409.9    0.05       0
Bank Sta=4997.9,5001.9
Exp/Cntr=0.3,0.1

Type RM Length L Ch R = 1,643,430,430,430
BEGIN DESCRIPTION:
Mapping XS c5c24a09
END DESCRIPTION:
XS GIS Cut Line= 4
      2470861.53     13565405.78      2470750.44     13565048.19
      2470653.21     13564940.55      2470101.16     13564860.69
#Sta/Elev= 30
  4555.9  312.40  4561.5  312.75  4606.2  312.26  4651.0  311.55  4671.9  309.99
  4697.0  311.57  4767.3  312.39  4818.5  311.67  4870.9  311.88  4943.7  311.14
  4952.1  310.27  4957.9  310.39  4972.1  307.62  4986.2  304.10  4991.0  304.08
  4991.2  303.58  4994.7  303.58  4995.0  304.08  5000.4  305.28  5007.2  305.11
  5014.6  308.20  5081.0  308.42  5114.0  309.13  5164.5  312.13  5225.2  314.38
  5336.3  316.98  5366.6  318.36  5431.8  319.60  5619.2  326.24  5633.2  326.27
#Mann=7,-1,0
  4555.9    0.12       0  4606.2    0.05       0  4952.1     0.1       0
  4991.0    0.05       0  4995.0     0.1       0  5081.0    0.05       0
  5431.8    0.04       0
Bank Sta=4991,4995
Exp/Cntr=0.3,0.1

Type RM Length L Ch R = 1,213,0,0,0
BEGIN DESCRIPTION:
LGII4579
END DESCRIPTION:
XS GIS Cut Line= 4
      2470943.03     13565338.66      2471047.19     13564901.19
      2470970.80     13564581.74      2470637.44     13564248.38
#Sta/Elev= 30
  4386.2  311.24  4472.3  311.38  4542.4  309.96  4626.4  310.53  4657.2  310.02
  4674.0  308.66  4716.3  308.61  4749.7  309.35  4862.3  309.18  4867.4  309.78
  4873.1  309.21  4934.8  309.24  4986.2  306.13  5006.8  305.59  5017.1  304.35
  5038.8  303.27  5039.0  302.77  5042.8  303.27  5058.2  304.04  5068.5  305.62
  5082.8  306.55  5109.6  307.41  5140.4  309.47  5160.1  310.12  5173.2  309.17
  5187.4  310.42  5236.9  311.87  5471.3  319.30  5484.7  319.51  5635.8  323.78
#Mann=8,-1,0
  4386.2    0.12       0  4472.3    0.05       0  4716.3     0.1       0
  5038.8    0.05       0  5042.8     0.1       0  5236.9    0.12       0
  5471.3    0.05       0  5484.7    0.04       0
Bank Sta=5038.8,5042.8
Exp/Cntr=0.3,0.1

Chan Stop Cuts=-1