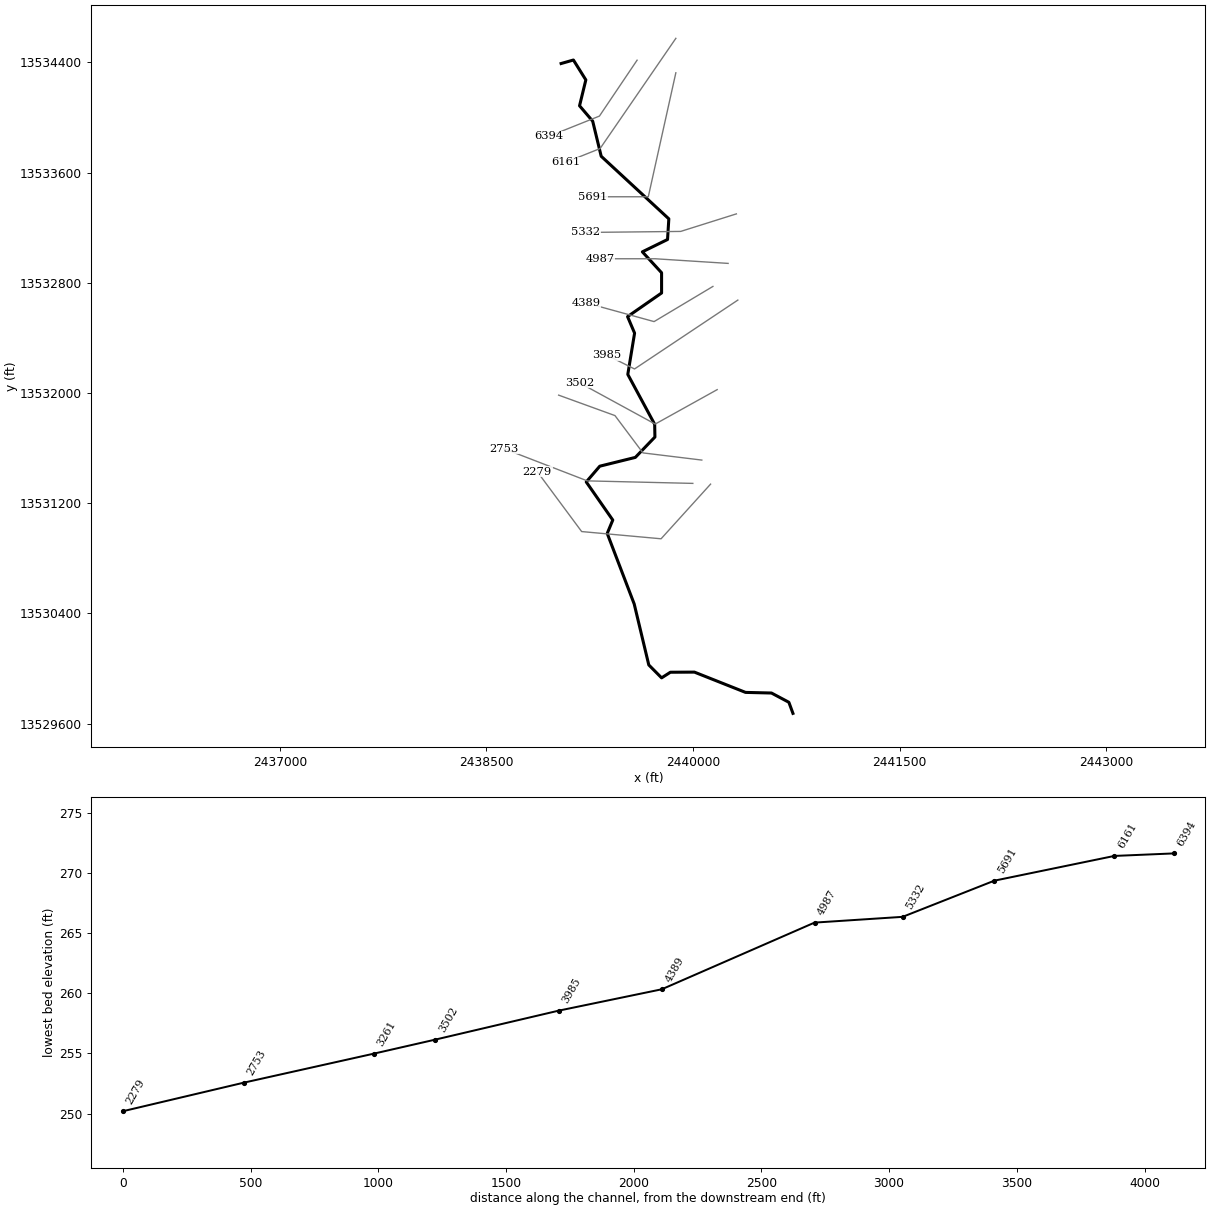
--- TRIB 6 TO SMITH CREEK.prj (project) ---

Proj Title=TRIB 6 TO SMITH CREEK Base Level Engineering
Current Plan=p01
Default Exp/Contr=0.3,0.1
English Units
Geom File=g01
Flow File=f01
Plan File=p01
BEGIN DESCRIPTION:
TRIB 6 TO SMITH CREEK
END DESCRIPTION:

--- TRIB 6 TO SMITH CREEK.p01 (plan) ---

Plan Title=Multiple Run
Short Identifier=Multiple
Geom File=g01
Flow File=f01
Subcritical Flow
K Sum by GR= 0
Std Step Tol= 0.01
Critical Tol= 0.01
Num of Std Step Trials= 20
Max Error Tol= 0.3
Flow Tol Ratio= 0.001
Split Flow NTrial= 30
Split Flow Tol= 0.02
Split Flow Ratio= 0.02
Log Output Level= 0
Friction Slope Method= 1
Unsteady Friction Slope Method= 2
Unsteady Bridges Friction Slope Method= 1
Parabolic Critical Depth
Global Vel Dist=  1 , 1 , 1
Global Log Level= 0
CheckData=True
Encroach Param= -1, 0, 0, 0
BEGIN DESCRIPTION:
Multiple Run
END DESCRIPTION:

--- TRIB 6 TO SMITH CREEK.f01 (steady flow) ---

Flow Title=Multiple
Number of Profiles=7
Profile Names=10-year,25-year,50-year,1pct_min,100-year,1pct_plu,500-year
River Rch & RM= TRIB 6 TO SMITH ,Reach-1,6394
     701    1133    1524     992    1979    3948    3300
River Rch & RM= TRIB 6 TO SMITH ,Reach-1,5332
     918    1507    2047    1343    2680    5348    4552
River Rch & RM= TRIB 6 TO SMITH ,Reach-1,2753
    1029    1699    2316    1525    3043    6071    5204
Boundary for River Rch & Prof#=TRIB 6 TO SMITH ,Reach-1,1
Up Type=0
Dn Type=3
Dn Slope=0.005
Boundary for River Rch & Prof#=TRIB 6 TO SMITH ,Reach-1,2
Up Type=0
Dn Type=3
Dn Slope=0.005
Boundary for River Rch & Prof#=TRIB 6 TO SMITH ,Reach-1,3
Up Type=0
Dn Type=3
Dn Slope=0.005
Boundary for River Rch & Prof#=TRIB 6 TO SMITH ,Reach-1,4
Up Type=0
Dn Type=3
Dn Slope=0.005
Boundary for River Rch & Prof#=TRIB 6 TO SMITH ,Reach-1,5
Up Type=0
Dn Type=3
Dn Slope=0.005
Boundary for River Rch & Prof#=TRIB 6 TO SMITH ,Reach-1,6
Up Type=0
Dn Type=3
Dn Slope=0.005
Boundary for River Rch & Prof#=TRIB 6 TO SMITH ,Reach-1,7
Up Type=0
Dn Type=3
Dn Slope=0.005

--- TRIB 6 TO SMITH CREEK.g01 (geometry) ---

Geom Title=Existing Conditions

River Reach=TRIB 6 TO SMITH ,Reach-1
Reach XY= 30
      2439042.11     13534392.11      2439131.46     13534417.62
      2439221.66     13534273.28      2439175.94     13534085.48
      2439271.44     13533973.53      2439333.14     13533718.94
      2439824.03     13533264.71      2439814.68     13533114.83
      2439631.97     13533025.24      2439771.47     13532873.53
      2439771.48     13532726.46      2439524.55     13532554.98
      2439575.50     13532435.17      2439526.19     13532135.50
      2439721.33     13531773.41      2439723.04     13531680.89
      2439581.05     13531533.12      2439322.70     13531469.20
      2439224.53     13531354.84      2439417.17     13531078.40
      2439376.86     13530981.13      2439572.73     13530469.06
      2439678.61     13530026.47      2439771.57     13529932.79
      2439835.43     13529973.61      2440009.78     13529974.48
      2440380.94     13529827.26      2440569.07     13529822.76
      2440695.47     13529755.50      2440725.00     13529675.00

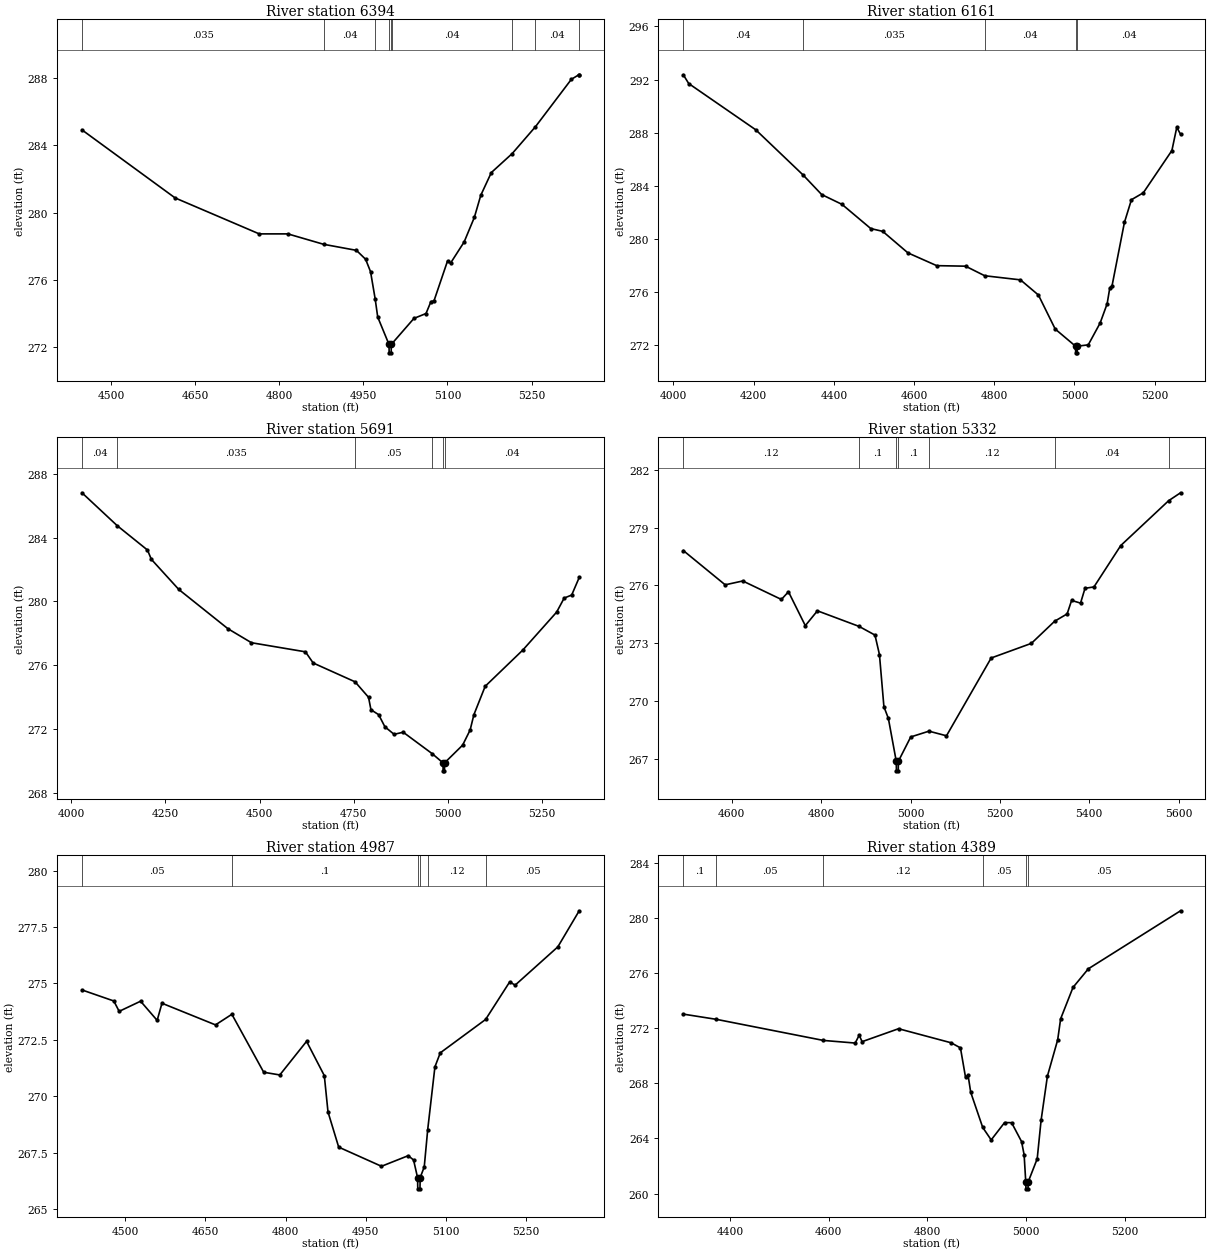
Type RM Length L Ch R = 1,6394,233,233,233
BEGIN DESCRIPTION:
Mapping XS b4755bed
END DESCRIPTION:
XS GIS Cut Line= 3
      2439593.73     13534416.47      2439320.27     13534010.63
      2438951.36     13533863.06
#Sta/Elev= 30
  4448.2  284.92  4614.3  280.87  4764.3  278.73  4815.3  278.73  4879.1  278.11
  4937.6  277.75  4954.0  277.22  4962.8  276.48  4971.0  274.87  4975.6  273.78
  4995.7  272.15  4996.0  271.65  4999.6  271.65  4999.8  272.15  5001.6  272.22
  5040.2  273.70  5061.7  273.99  5070.5  274.70  5075.9  274.74  5100.1  277.12
  5105.5  276.99  5129.7  278.25  5147.9  279.71  5159.4  281.03  5178.2  282.38
  5215.4  283.51  5256.9  285.11  5320.9  287.93  5334.2  288.20  5334.9  288.20
#Mann=9,-1,0
  4448.2   0.035       0  4879.1    0.04       0  4971.0    0.12       0
  4995.7    0.05       0  4999.8    0.12       0  5001.6    0.04       0
  5215.4    0.05       0  5256.9    0.04       0  5334.2    0.05       0
Bank Sta=4995.7,4999.8
Exp/Cntr=0.3,0.1

Type RM Length L Ch R = 1,6161,470,470,470
BEGIN DESCRIPTION:
TRIB 6 TO SMITH CREEK 10.0
END DESCRIPTION:
XS GIS Cut Line= 3
      2439875.00     13534575.00      2439325.00     13533775.00
      2439074.99     13533674.99
#Sta/Elev= 30
  4024.6  292.36  4038.1  291.70  4205.3  288.22  4323.7  284.81  4369.6  283.35
  4420.4  282.61  4492.1  280.79  4521.9  280.58  4584.8  278.96  4656.5  278.00
  4728.5  277.96  4776.3  277.24  4865.5  276.93  4910.2  275.79  4952.1  273.23
  5002.8  271.94  5003.1  271.44  5006.7  271.44  5006.9  271.94  5034.5  272.04
  5064.1  273.68  5081.6  275.13  5088.3  276.34  5093.7  276.46  5124.7  281.25
  5142.2  282.96  5171.8  283.48  5243.1  286.66  5255.3  288.41  5264.7  287.88
#Mann=5,-1,0
  4024.6    0.04       0  4323.7   0.035       0  4776.3    0.04       0
  5002.8    0.04       0  5006.9    0.04       0
Bank Sta=5002.8,5006.9
Exp/Cntr=0.3,0.1

Type RM Length L Ch R = 1,5691,359,359,359
BEGIN DESCRIPTION:
TRIB 6 TO SMITH CREEK 9.0
END DESCRIPTION:
XS GIS Cut Line= 3
      2439875.00     13534325.02      2439675.00     13533425.00
      2439274.97     13533425.00
#Sta/Elev= 30
  4028.0  286.81  4122.1  284.74  4202.2  283.22  4212.4  282.64  4285.4  280.75
  4416.0  278.29  4478.7  277.41  4622.2  276.84  4642.7  276.14  4754.1  274.96
  4789.9  273.99  4796.3  273.21  4816.8  272.90  4833.4  272.14  4857.8  271.67
  4882.1  271.80  4958.9  270.46  4987.9  269.88  4988.2  269.38  4991.8  269.38
  4992.1  269.88  5040.0  270.99  5060.0  271.94  5070.0  272.90  5100.0  274.68
  5200.0  276.95  5290.0  279.33  5310.0  280.21  5330.0  280.40  5350.0  281.50
#Mann=6,-1,0
  4028.0    0.04       0  4122.1   0.035       0  4754.1    0.05       0
  4958.9    0.04       0  4987.9    0.04       0  4992.1    0.04       0
Bank Sta=4987.9,4992.1
Exp/Cntr=0.3,0.1

Type RM Length L Ch R = 1,5332,345,345,345
BEGIN DESCRIPTION:
4858
END DESCRIPTION:
XS GIS Cut Line= 3
      2440314.35     13533300.71      2439910.03     13533173.42
      2439221.25     13533165.94
#Sta/Elev= 30
  4491.6  277.81  4585.3  276.03  4624.6  276.23  4711.1  275.27  4726.9  275.67
  4764.6  273.91  4791.7  274.68  4885.0  273.87  4920.5  273.42  4930.5  272.41
  4940.5  269.70  4950.5  269.09  4968.1  266.87  4968.5  266.37  4972.6  266.37
  4972.9  266.87  5000.5  268.13  5041.3  268.43  5080.5  268.19  5180.5  272.23
  5270.5  272.99  5322.6  274.14  5350.5  274.52  5360.5  275.22  5380.5  275.08
  5390.5  275.85  5410.5  275.92  5470.5  278.07  5577.7  280.40  5604.3  280.81
#Mann=7,-1,0
  4491.6    0.12       0  4885.0     0.1       0  4968.1    0.05       0
  4972.9     0.1       0  5041.3    0.12       0  5322.6    0.04       0
  5577.7    0.05       0
Bank Sta=4968.1,4972.9
Exp/Cntr=0.3,0.1

Type RM Length L Ch R = 1,4987,598,598,598
BEGIN DESCRIPTION:
TRIB 6 TO SMITH CREEK 8.0
END DESCRIPTION:
XS GIS Cut Line= 3
      2440254.43     13532941.33      2439725.00     13532975.00
      2439325.00     13532975.00
#Sta/Elev= 30
  4419.0  274.71  4478.6  274.22  4488.6  273.76  4528.7  274.21  4559.7  273.36
  4568.7  274.12  4668.9  273.16  4699.5  273.63  4759.1  271.06  4789.2  270.94
  4839.3  272.43  4872.5  270.91  4879.4  269.30  4899.4  267.74  4979.5  266.89
  5029.5  267.36  5039.5  267.17  5047.0  266.39  5047.4  265.89  5051.5  265.89
  5051.9  266.39  5059.5  266.86  5066.0  268.52  5079.5  271.30  5089.5  271.92
  5174.3  273.40  5219.5  275.07  5229.5  274.92  5309.5  276.62  5349.5  278.22
#Mann=6,-1,0
  4419.0    0.05       0  4699.5     0.1       0  5047.0    0.05       0
  5051.9     0.1       0  5066.0    0.12       0  5174.3    0.05       0
Bank Sta=5047,5051.9
Exp/Cntr=0.3,0.1

Type RM Length L Ch R = 1,4389,404,404,404
BEGIN DESCRIPTION:
Mapping XS 6eae97e8
END DESCRIPTION:
XS GIS Cut Line= 3
      2440144.08     13532774.10      2439716.97     13532518.87
      2439224.82     13532654.28
#Sta/Elev= 30
  4305.6  273.02  4372.8  272.64  4589.7  271.11  4654.0  270.92  4662.2  271.49
  4668.0  271.02  4741.9  271.96  4848.5  270.94  4867.4  270.57  4877.7  268.44
  4882.9  268.58  4888.2  267.35  4912.5  264.80  4929.7  263.89  4956.9  265.15
  4971.1  265.14  4991.3  263.77  4996.5  262.81  4999.8  260.84  5000.2  260.34
  5004.4  260.34  5004.7  260.84  5023.0  262.52  5030.9  265.32  5043.7  268.52
  5064.5  271.15  5070.5  272.68  5095.6  274.96  5126.7  276.31  5313.6  280.52
#Mann=6,-1,0
  4305.6     0.1       0  4372.8    0.05       0  4589.7    0.12       0
  4912.5    0.05       0  4999.8    0.05       0  5004.7    0.05       0
Bank Sta=4999.8,5004.7
Exp/Cntr=0.3,0.1

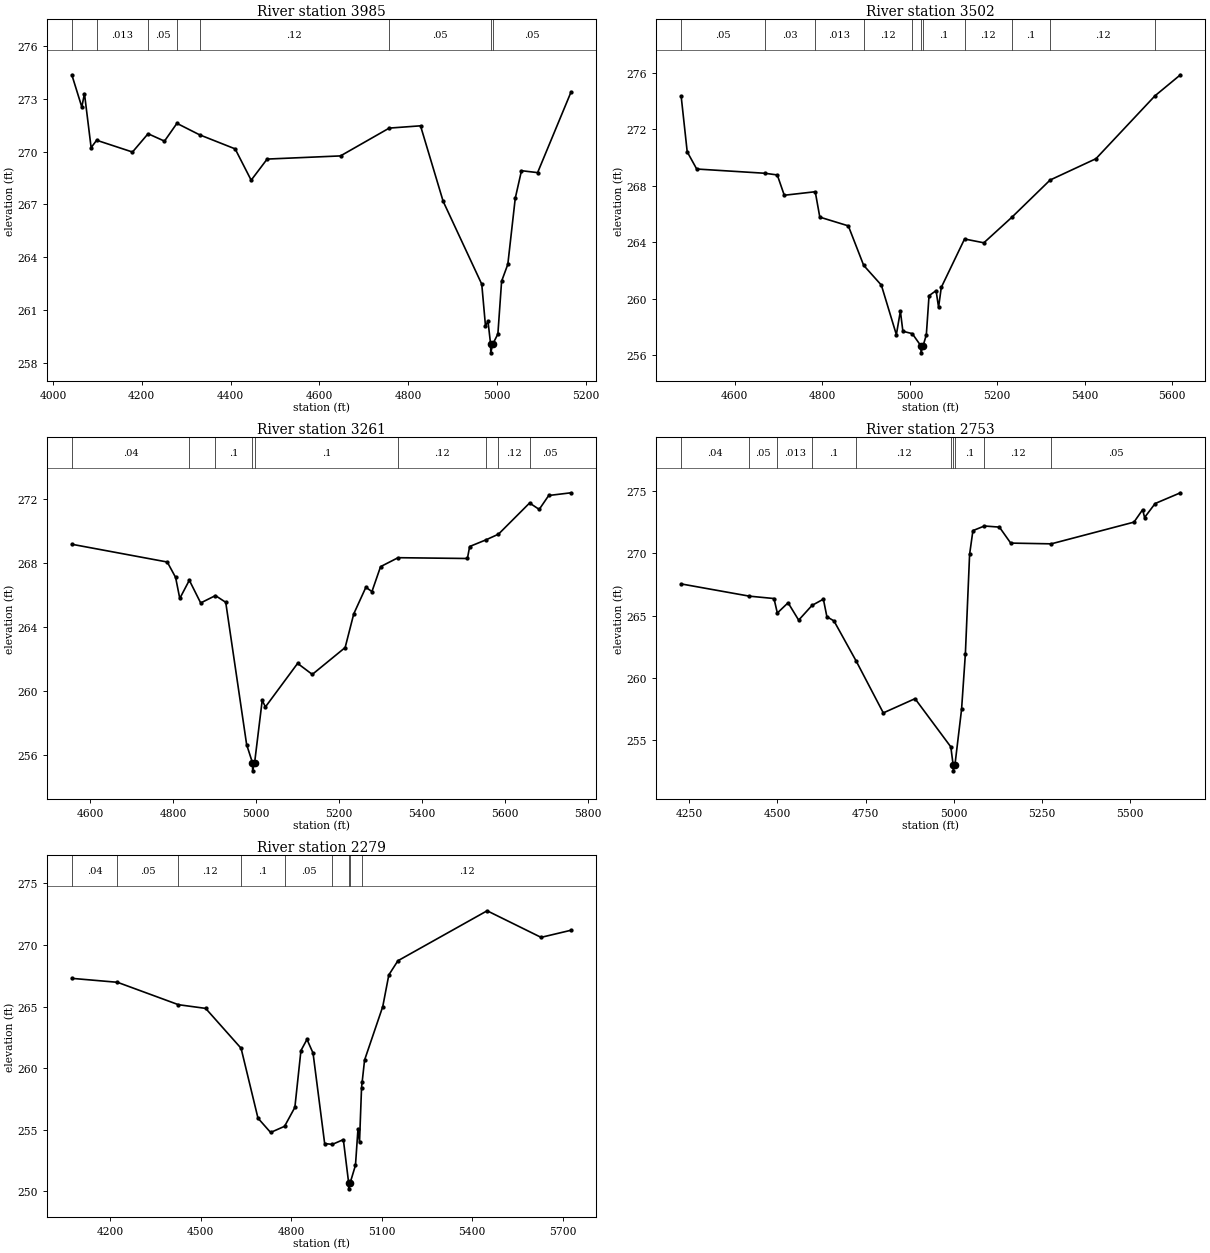
Type RM Length L Ch R = 1,3985,483,483,483
BEGIN DESCRIPTION:
TRIB 6 TO SMITH CREEK 6.0
END DESCRIPTION:
XS GIS Cut Line= 3
      2440324.97     13532674.98      2439575.00     13532175.00
      2439374.96     13532275.02
#Sta/Elev= 30
  4042.3  274.36  4064.8  272.53  4070.8  273.29  4085.8  270.22  4098.2  270.64
  4179.0  269.97  4214.1  271.01  4251.1  270.59  4279.1  271.60  4330.1  270.95
  4410.3  270.15  4446.4  268.37  4482.4  269.57  4647.7  269.75  4757.5  271.33
  4828.0  271.46  4879.0  267.17  4966.0  262.46  4974.4  260.08  4980.0  260.36
  4985.9  259.06  4986.3  258.56  4990.8  259.06  5002.3  259.63  5010.7  262.63
  5024.7  263.59  5041.5  267.35  5055.5  268.91  5091.8  268.80  5167.3  273.39
#Mann=8,-1,0
  4042.3    0.05       0  4098.2   0.013       0  4214.1    0.05       0
  4279.1   0.013       0  4330.1    0.12       0  4757.5    0.05       0
  4985.9    0.05       0  4990.8    0.05       0
Bank Sta=4985.9,4990.8
Exp/Cntr=0.3,0.1

Type RM Length L Ch R = 1,3502,241,241,241
BEGIN DESCRIPTION:
TRIB 6 TO SMITH CREEK 5.0
END DESCRIPTION:
XS GIS Cut Line= 3
      2440175.03     13532025.02      2439725.00     13531775.00
      2439175.01     13532074.99
#Sta/Elev= 30
  4477.9  274.34  4491.7  270.40  4513.4  269.18  4668.9  268.88  4697.6  268.76
  4713.6  267.32  4784.4  267.57  4794.8  265.77  4860.0  265.15  4895.1  262.35
  4935.5  260.95  4969.8  257.44  4979.0  259.11  4984.7  257.68  5006.2  257.51
  5025.8  256.65  5026.2  256.15  5030.9  256.65  5038.3  257.42  5044.5  260.20
  5060.6  260.56  5066.3  259.38  5072.5  260.79  5125.7  264.22  5169.8  263.95
  5233.8  265.76  5321.3  268.40  5426.0  269.91  5561.0  274.37  5619.2  275.86
#Mann=11,-1,0
  4477.9    0.05       0  4668.9    0.03       0  4784.4   0.013       0
  4895.1    0.12       0  5006.2     0.1       0  5025.8    0.05       0
  5030.9     0.1       0  5125.7    0.12       0  5233.8     0.1       0
  5321.3    0.12       0  5561.0    0.05       0
Bank Sta=5025.8,5030.9
Exp/Cntr=0.3,0.1

Type RM Length L Ch R = 1,3261,508,508,508
BEGIN DESCRIPTION:
Mapping XS 18a0d77b
END DESCRIPTION:
XS GIS Cut Line= 4
      2440063.38     13531513.66      2439636.24     13531565.75
      2439433.12     13531836.58      2439024.27     13531985.02
#Sta/Elev= 30
  4555.3  269.15  4785.4  268.04  4805.5  267.08  4815.6  265.76  4838.6  266.90
  4866.0  265.48  4901.6  265.94  4926.4  265.52  4976.8  256.62  4990.9  255.48
  4991.3  254.98  4996.0  255.48  5014.3  259.38  5022.2  258.98  5099.7  261.70
  5135.1  261.01  5214.3  262.69  5235.1  264.80  5264.3  266.46  5278.9  266.19
  5299.7  267.75  5341.9  268.31  5509.1  268.26  5514.5  269.01  5553.3  269.42
  5583.9  269.78  5659.0  271.73  5682.2  271.33  5705.1  272.20  5759.1  272.37
#Mann=9,-1,0
  4555.3    0.04       0  4838.6   0.013       0  4901.6     0.1       0
  4990.9    0.05       0  4996.0     0.1       0  5341.9    0.12       0
  5553.3    0.05       0  5583.9    0.12       0  5659.0    0.05       0
Bank Sta=4990.9,4996
Exp/Cntr=0.3,0.1

Type RM Length L Ch R = 1,2753,474,474,474
BEGIN DESCRIPTION:
Mapping XS 7a15405b
END DESCRIPTION:
XS GIS Cut Line= 3
      2439998.24     13531344.39      2439232.60     13531362.62
      2438625.85     13531596.99
#Sta/Elev= 30
  4226.8  267.54  4420.3  266.56  4490.1  266.37  4499.6  265.21  4530.1  266.03
  4560.1  264.64  4598.0  265.82  4630.2  266.32  4640.2  264.91  4660.2  264.58
  4723.5  261.35  4800.2  257.21  4890.2  258.35  4991.7  254.49  4998.2  253.07
  4998.6  252.57  5003.5  253.07  5022.2  257.49  5033.0  261.94  5045.0  269.91
  5054.4  271.81  5087.0  272.18  5129.5  272.09  5161.6  270.81  5276.6  270.75
  5511.3  272.49  5535.9  273.49  5541.3  272.86  5571.3  273.98  5643.1  274.84
#Mann=10,-1,0
  4226.8    0.04       0  4420.3    0.05       0  4499.6   0.013       0
  4598.0     0.1       0  4723.5    0.12       0  4991.7     0.1       0
  4998.2    0.05       0  5003.5     0.1       0  5087.0    0.12       0
  5276.6    0.05       0
Bank Sta=4998.2,5003.5
Exp/Cntr=0.3,0.1

Type RM Length L Ch R = 1,2279,0,0,0
BEGIN DESCRIPTION:
4857
END DESCRIPTION:
XS GIS Cut Line= 4
      2440127.15     13531339.14      2439767.78     13530942.33
      2439191.29     13530994.74      2438869.70     13531428.50
#Sta/Elev= 30
  4073.3  267.29  4224.5  266.97  4426.5  265.15  4516.7  264.85  4634.1  261.61
  4690.1  255.93  4731.9  254.77  4778.2  255.27  4812.3  256.81  4832.4  261.42
  4852.4  262.33  4872.5  261.22  4911.0  253.87  4936.4  253.80  4972.9  254.19
  4990.4  250.69  4990.8  250.19  4995.7  250.69  5013.1  252.11  5021.4  255.06
  5026.5  254.00  5033.2  258.41  5035.4  258.90  5043.2  260.65  5103.5  265.00
  5123.6  267.57  5153.7  268.72  5449.3  272.78  5628.0  270.62  5727.5  271.20
#Mann=9,-1,0
  4073.3    0.04       0  4224.5    0.05       0  4426.5    0.12       0
  4634.1     0.1       0  4778.2    0.05       0  4936.4   0.013       0
  4990.4    0.03       0  4995.7   0.013       0  5035.4    0.12       0
Bank Sta=4990.4,4995.7
Exp/Cntr=0.3,0.1

Chan Stop Cuts=-1