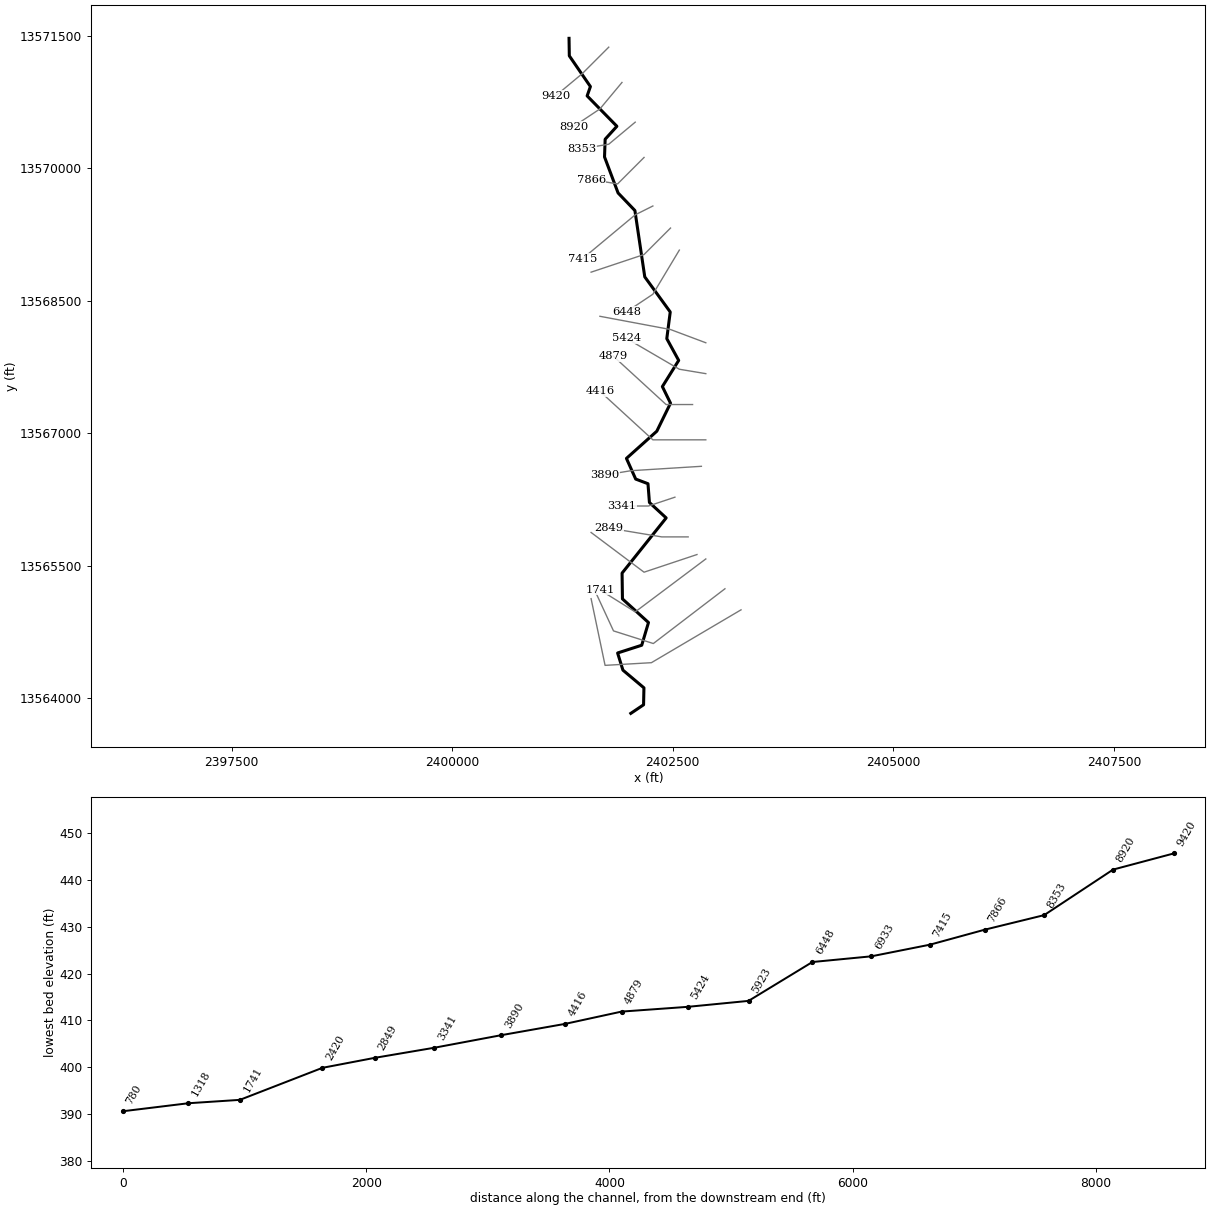
--- TRIB 6 TO THOMAS CREEK.prj (project) ---

Proj Title=TRIB 6 TO THOMAS CREEK Base Level Engineering
Current Plan=p01
Default Exp/Contr=0.3,0.1
English Units
Geom File=g01
Flow File=f01
Plan File=p01
BEGIN DESCRIPTION:
TRIB 6 TO THOMAS CREEK
END DESCRIPTION:

--- TRIB 6 TO THOMAS CREEK.p01 (plan) ---

Plan Title=Multiple Run
Short Identifier=Multiple
Geom File=g01
Flow File=f01
Subcritical Flow
K Sum by GR= 0
Std Step Tol= 0.01
Critical Tol= 0.01
Num of Std Step Trials= 20
Max Error Tol= 0.3
Flow Tol Ratio= 0.001
Split Flow NTrial= 30
Split Flow Tol= 0.02
Split Flow Ratio= 0.02
Log Output Level= 0
Friction Slope Method= 1
Unsteady Friction Slope Method= 2
Unsteady Bridges Friction Slope Method= 1
Parabolic Critical Depth
Global Vel Dist=  1 , 1 , 1
Global Log Level= 0
CheckData=True
Encroach Param= -1, 0, 0, 0
BEGIN DESCRIPTION:
Multiple Run
END DESCRIPTION:

--- TRIB 6 TO THOMAS CREEK.f01 (steady flow) ---

Flow Title=Multiple
Number of Profiles=7
Profile Names=10-year,25-year,50-year,1pct_min,100-year,1pct_plu,500-year
River Rch & RM= TRIB 6 TO THOMAS,Reach-1,9420
     608     993    1345     884    1763    3518    3000
River Rch & RM= TRIB 6 TO THOMAS,Reach-1,5923
     948    1584    2178    1449    2891    5768    5052
Boundary for River Rch & Prof#=TRIB 6 TO THOMAS,Reach-1,1
Up Type=0
Dn Type=3
Dn Slope=0.005
Boundary for River Rch & Prof#=TRIB 6 TO THOMAS,Reach-1,2
Up Type=0
Dn Type=3
Dn Slope=0.005
Boundary for River Rch & Prof#=TRIB 6 TO THOMAS,Reach-1,3
Up Type=0
Dn Type=3
Dn Slope=0.005
Boundary for River Rch & Prof#=TRIB 6 TO THOMAS,Reach-1,4
Up Type=0
Dn Type=3
Dn Slope=0.005
Boundary for River Rch & Prof#=TRIB 6 TO THOMAS,Reach-1,5
Up Type=0
Dn Type=3
Dn Slope=0.005
Boundary for River Rch & Prof#=TRIB 6 TO THOMAS,Reach-1,6
Up Type=0
Dn Type=3
Dn Slope=0.005
Boundary for River Rch & Prof#=TRIB 6 TO THOMAS,Reach-1,7
Up Type=0
Dn Type=3
Dn Slope=0.005

--- TRIB 6 TO THOMAS CREEK.g01 (geometry) ---

Geom Title=Existing Conditions

River Reach=TRIB 6 TO THOMAS,Reach-1
Reach XY= 30
      2401325.00     13571475.00      2401328.17     13571276.65
      2401567.18     13570928.41      2401530.12     13570822.71
      2401867.42     13570478.35      2401734.30     13570331.67
      2401727.17     13570130.98      2401880.83     13569722.70
      2402071.46     13569523.54      2402183.24     13568771.77
      2402471.86     13568373.97      2402432.81     13568071.59
      2402567.66     13567824.90      2402382.77     13567528.41
      2402475.05     13567340.34      2402319.53     13567022.55
      2401975.53     13566714.53      2402080.45     13566480.25
      2402219.59     13566427.71      2402236.11     13566214.68
      2402425.79     13566040.08      2401926.05     13565414.57
      2401930.36     13565122.30      2402225.31     13564854.66
      2402148.83     13564597.31      2401875.42     13564509.36
      2401935.63     13564315.00      2402173.81     13564114.52
      2402169.65     13563922.30      2402025.00     13563825.00

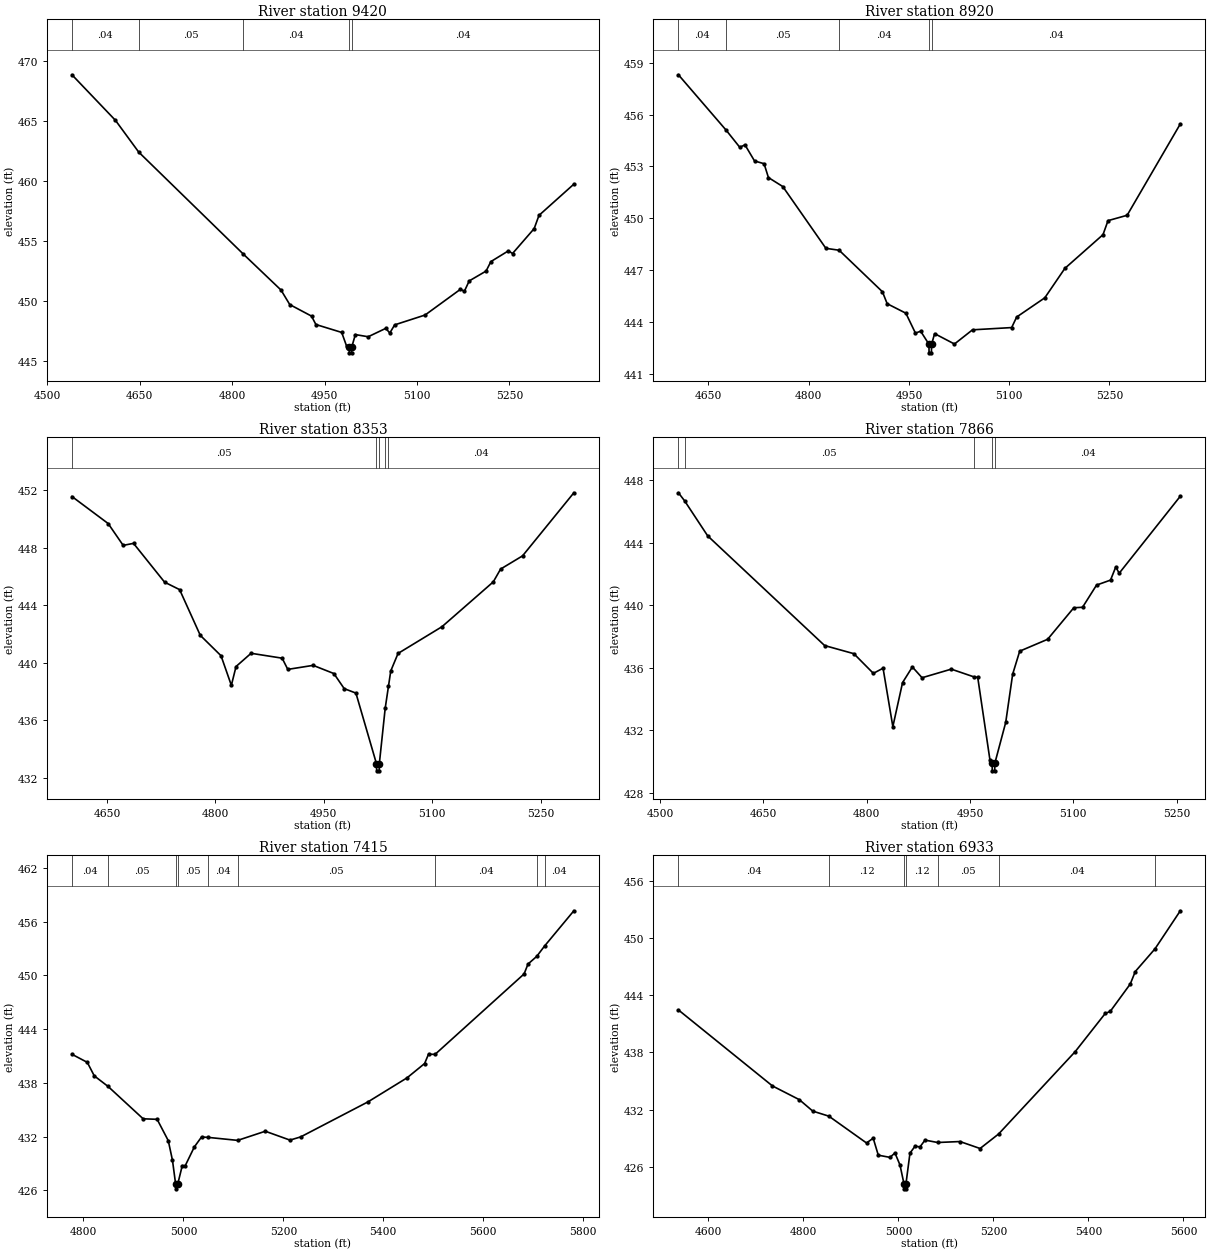
Type RM Length L Ch R = 1,9420,500,500,500
BEGIN DESCRIPTION:
TRIB 6 TO THOMAS CREEK 18.0
END DESCRIPTION:
XS GIS Cut Line= 3
      2401775.01     13571375.01      2401475.00     13571075.00
      2401174.99     13570824.99
#Sta/Elev= 30
  4539.8  468.85  4610.5  465.05  4648.2  462.41  4817.9  453.92  4879.2  450.92
  4893.4  449.71  4928.7  448.75  4935.8  448.05  4977.7  447.39  4985.6  446.26
  4990.1  446.19  4990.3  445.69  4993.8  445.69  4994.1  446.19  4999.9  447.21
  5020.7  447.03  5049.3  447.73  5055.8  447.34  5063.7  448.02  5113.1  448.84
  5170.4  450.98  5176.9  450.82  5184.7  451.68  5212.1  452.50  5219.9  453.29
  5248.5  454.19  5255.0  453.96  5290.2  456.04  5298.0  457.14  5354.6  459.74
#Mann=5,-1,0
  4539.8    0.04       0  4648.2    0.05       0  4817.9    0.04       0
  4990.1    0.04       0  4994.1    0.04       0
Bank Sta=4990.1,4994.1
Exp/Cntr=0.3,0.1

Type RM Length L Ch R = 1,8920,567,567,567
BEGIN DESCRIPTION:
TRIB 6 TO THOMAS CREEK 17.0
END DESCRIPTION:
XS GIS Cut Line= 3
      2401925.01     13570975.01      2401675.00     13570675.00
      2401374.98     13570474.99
#Sta/Elev= 30
  4605.0  458.30  4676.6  455.09  4696.8  454.11  4704.6  454.25  4718.9  453.32
  4733.2  453.16  4739.7  452.36  4761.2  451.84  4825.7  448.27  4845.5  448.16
  4910.3  445.76  4917.4  445.07  4945.4  444.52  4959.7  443.37  4967.5  443.48
  4979.9  442.73  4980.1  442.23  4983.6  442.23  4983.9  442.73  4988.4  443.34
  5018.1  442.74  5045.1  443.56  5103.7  443.69  5111.2  444.30  5153.3  445.41
  5183.3  447.11  5240.4  449.06  5247.9  449.87  5276.5  450.18  5356.1  455.46
#Mann=5,-1,0
  4605.0    0.04       0  4676.6    0.05       0  4845.5    0.04       0
  4979.9    0.04       0  4983.9    0.04       0
Bank Sta=4979.9,4983.9
Exp/Cntr=0.3,0.1

Type RM Length L Ch R = 1,8353,487,487,487
BEGIN DESCRIPTION:
TRIB 6 TO THOMAS CREEK 16.0
END DESCRIPTION:
XS GIS Cut Line= 3
      2402074.97     13570524.97      2401775.00     13570275.00
      2401475.01     13570225.00
#Sta/Elev= 30
  4601.4  451.58  4651.5  449.70  4672.3  448.18  4686.6  448.32  4729.6  445.62
  4750.4  445.10  4779.0  441.92  4807.7  440.50  4822.0  438.44  4828.5  439.75
  4849.3  440.67  4892.3  440.33  4900.1  439.55  4935.2  439.83  4963.9  439.26
  4978.2  438.21  4994.4  437.90  5022.8  432.99  5023.1  432.49  5026.6  432.49
  5026.8  432.99  5034.9  436.84  5039.4  438.36  5042.6  439.44  5052.7  440.66
  5113.5  442.52  5184.5  445.64  5194.6  446.53  5225.0  447.45  5296.0  451.84
#Mann=5,-1,0
  4601.4    0.05       0  5022.8    0.05       0  5026.8    0.05       0
  5034.9    0.12       0  5039.4    0.04       0
Bank Sta=5022.8,5026.8
Exp/Cntr=0.3,0.1

Type RM Length L Ch R = 1,7866,451,451,451
BEGIN DESCRIPTION:
TRIB 6 TO THOMAS CREEK 15.0
END DESCRIPTION:
XS GIS Cut Line= 3
      2402175.03     13570125.03      2401875.00     13569825.00
      2401575.05     13569874.99
#Sta/Elev= 30
  4526.9  447.19  4535.8  446.68  4569.4  444.43  4739.1  437.41  4781.5  436.89
  4809.8  435.63  4823.9  435.96  4838.1  432.22  4852.2  435.04  4866.4  436.04
  4880.5  435.35  4922.9  435.90  4956.1  435.40  4961.3  435.37  4979.1  430.06
  4982.2  429.89  4982.4  429.39  4985.9  429.39  4986.2  429.89  5001.9  432.49
  5012.0  435.58  5022.2  437.05  5062.7  437.81  5100.7  439.83  5113.4  439.86
  5133.7  441.28  5154.0  441.60  5161.6  442.44  5166.6  442.04  5255.3  446.97
#Mann=5,-1,0
  4526.9    0.04       0  4535.8    0.05       0  4956.1    0.04       0
  4982.2    0.04       0  4986.2    0.04       0
Bank Sta=4982.2,4986.2
Exp/Cntr=0.3,0.1

Type RM Length L Ch R = 1,7415,482,482,482
BEGIN DESCRIPTION:
TRIB 6 TO THOMAS CREEK 14.0
END DESCRIPTION:
XS GIS Cut Line= 3
      2402274.99     13569574.99      2402075.00     13569475.00
      2401475.01     13568975.01
#Sta/Elev= 30
  4776.9  441.20  4807.6  440.30  4821.6  438.79  4849.2  437.61  4919.4  434.00
  4947.4  433.94  4969.7  431.56  4978.1  429.37  4984.5  426.68  4984.8  426.18
  4988.5  426.68  4997.7  428.77  5003.7  428.77  5022.0  430.87  5036.3  431.97
  5050.1  431.92  5108.6  431.59  5163.9  432.61  5213.3  431.62  5234.8  431.98
  5369.5  435.89  5447.6  438.57  5482.8  440.17  5490.6  441.21  5503.7  441.19
  5681.9  450.17  5689.7  451.27  5707.2  452.13  5722.8  453.28  5781.5  457.22
#Mann=9,-1,0
  4776.9    0.04       0  4849.2    0.05       0  4984.5    0.05       0
  4988.5    0.05       0  5050.1    0.04       0  5108.6    0.05       0
  5503.7    0.04       0  5707.2    0.05       0  5722.8    0.04       0
Bank Sta=4984.5,4988.5
Exp/Cntr=0.3,0.1

Type RM Length L Ch R = 1,6933,485,485,485
BEGIN DESCRIPTION:
TRIB 6 TO THOMAS CREEK 13.0
END DESCRIPTION:
XS GIS Cut Line= 3
      2402475.02     13569325.02      2402175.00     13569025.00
      2401575.04     13568825.01
#Sta/Elev= 30
  4536.8  442.45  4734.8  434.48  4791.4  433.04  4819.7  431.84  4853.6  431.31
  4932.8  428.50  4946.9  429.00  4957.6  427.22  4982.2  426.99  4992.7  427.45
  5003.3  426.19  5011.8  424.19  5012.0  423.69  5015.5  423.69  5015.8  424.19
  5024.3  427.43  5034.9  428.16  5045.4  428.09  5056.0  428.80  5082.5  428.55
  5129.7  428.65  5171.9  427.92  5210.9  429.44  5372.2  438.08  5435.4  442.08
  5446.0  442.30  5488.1  445.17  5498.7  446.48  5540.2  448.86  5593.5  452.85
#Mann=7,-1,0
  4536.8    0.04       0  4853.6    0.12       0  5011.8    0.05       0
  5015.8    0.12       0  5082.5    0.05       0  5210.9    0.04       0
  5540.2    0.05       0
Bank Sta=5011.8,5015.8
Exp/Cntr=0.3,0.1

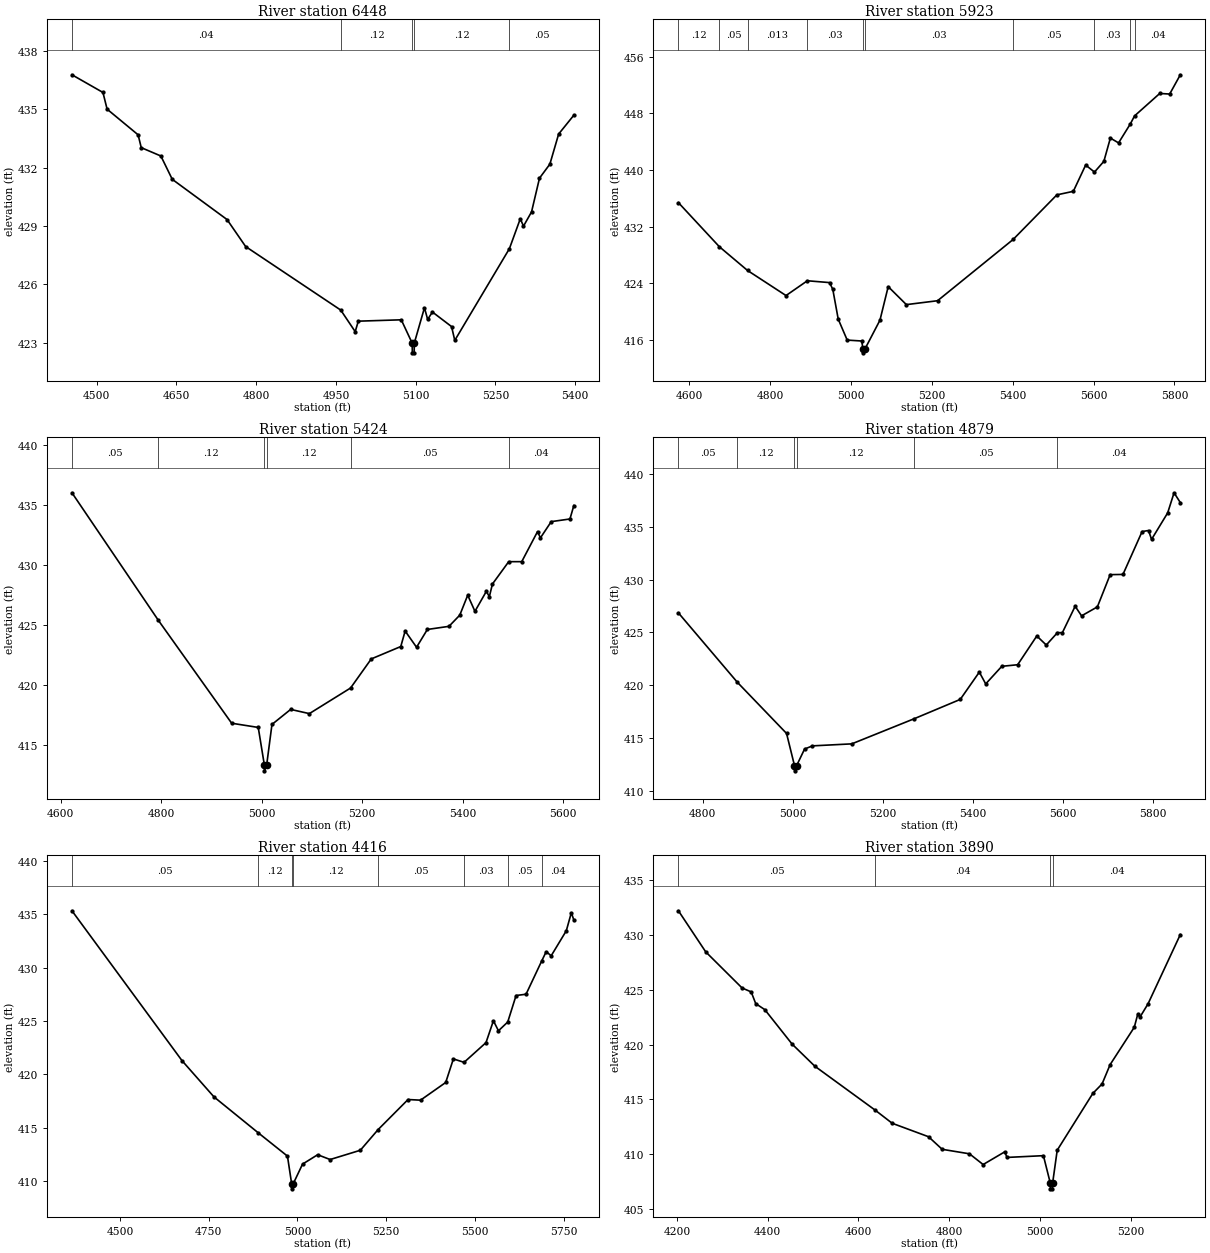
Type RM Length L Ch R = 1,6448,525,525,525
BEGIN DESCRIPTION:
TRIB 6 TO THOMAS CREEK 12.0
END DESCRIPTION:
XS GIS Cut Line= 3
      2402575.02     13569075.03      2402275.00     13568575.00
      2401974.99     13568374.99
#Sta/Elev= 30
  4453.7  436.78  4512.0  435.87  4519.8  435.01  4578.1  433.69  4584.0  433.03
  4620.9  432.60  4642.3  431.40  4745.3  429.33  4780.3  427.94  4959.1  424.67
  4986.3  423.56  4992.1  424.10  5072.9  424.17  5093.4  422.97  5093.7  422.47
  5097.2  422.47  5097.4  422.97  5116.5  424.79  5122.5  424.19  5131.5  424.57
  5167.5  423.82  5173.5  423.11  5276.2  427.83  5296.7  429.37  5302.7  428.99
  5317.8  429.72  5332.8  431.46  5352.3  432.18  5368.8  433.73  5397.4  434.70
#Mann=5,-1,0
  4453.7    0.04       0  4959.1    0.12       0  5093.4    0.05       0
  5097.4    0.12       0  5276.2    0.05       0
Bank Sta=5093.4,5097.4
Exp/Cntr=0.3,0.1

Type RM Length L Ch R = 1,5923,499,499,499
BEGIN DESCRIPTION:
TRIB 6 TO THOMAS CREEK 11.0
END DESCRIPTION:
XS GIS Cut Line= 3
      2402875.01     13568025.00      2402475.00     13568175.00
      2401674.95     13568325.01
#Sta/Elev= 30
  4573.2  435.37  4674.4  429.15  4744.2  425.79  4839.3  422.25  4892.1  424.34
  4947.0  424.08  4955.0  423.12  4968.4  418.92  4990.6  415.96  5026.7  415.83
  5029.5  414.66  5029.8  414.16  5034.1  414.66  5071.6  418.77  5092.0  423.51
  5136.9  420.97  5214.1  421.52  5400.9  430.17  5509.1  436.47  5549.8  436.97
  5580.3  440.68  5602.1  439.69  5625.3  441.20  5641.4  444.49  5661.7  443.81
  5691.0  446.51  5701.2  447.62  5763.5  450.79  5788.1  450.71  5814.4  453.43
#Mann=10,-1,0
  4573.2    0.12       0  4674.4    0.05       0  4744.2   0.013       0
  4892.1    0.03       0  5029.5    0.03       0  5034.1    0.03       0
  5400.9    0.05       0  5602.1    0.03       0  5691.0    0.05       0
  5701.2    0.04       0
Bank Sta=5029.5,5034.1
Exp/Cntr=0.3,0.1

Type RM Length L Ch R = 1,5424,545,545,545
BEGIN DESCRIPTION:
TRIB 6 TO THOMAS CREEK 10.0
END DESCRIPTION:
XS GIS Cut Line= 3
      2402874.97     13567675.00      2402575.00     13567725.00
      2401975.03     13568074.98
#Sta/Elev= 30
  4622.4  436.02  4794.5  425.40  4940.2  416.85  4993.1  416.50  5005.2  413.39
  5005.5  412.89  5009.9  413.39  5020.4  416.75  5057.6  418.00  5094.8  417.65
  5176.8  419.78  5218.0  422.20  5276.7  423.23  5285.4  424.52  5308.1  423.17
  5329.6  424.65  5372.6  424.91  5394.1  425.84  5409.9  427.50  5424.3  426.16
  5447.1  427.83  5452.9  427.37  5459.1  428.43  5491.5  430.29  5517.4  430.29
  5548.8  432.79  5554.6  432.27  5576.1  433.62  5613.3  433.84  5621.1  434.96
#Mann=6,-1,0
  4622.4    0.05       0  4794.5    0.12       0  5005.2    0.05       0
  5009.9    0.12       0  5176.8    0.05       0  5491.5    0.04       0
Bank Sta=5005.2,5009.9
Exp/Cntr=0.3,0.1

Type RM Length L Ch R = 1,4879,463,463,463
BEGIN DESCRIPTION:
TRIB 6 TO THOMAS CREEK 9.0
END DESCRIPTION:
XS GIS Cut Line= 3
      2402724.96     13567325.00      2402425.00     13567325.00
      2401825.00     13567875.00
#Sta/Elev= 30
  4746.1  426.86  4877.0  420.27  4986.1  415.42  5003.7  412.37  5004.0  411.87
  5008.5  412.37  5026.1  413.94  5043.6  414.24  5130.8  414.43  5269.6  416.82
  5371.6  418.65  5413.9  421.24  5428.1  420.12  5463.8  421.79  5499.0  421.94
  5541.5  424.67  5562.5  423.81  5587.4  424.99  5598.2  424.98  5626.6  427.49
  5640.8  426.58  5675.9  427.43  5704.3  430.49  5732.7  430.51  5775.2  434.58
  5789.4  434.68  5796.2  433.84  5831.9  436.35  5846.1  438.26  5860.0  437.33
#Mann=6,-1,0
  4746.1    0.05       0  4877.0    0.12       0  5003.7    0.05       0
  5008.5    0.12       0  5269.6    0.05       0  5587.4    0.04       0
Bank Sta=5003.7,5008.5
Exp/Cntr=0.3,0.1

Type RM Length L Ch R = 1,4416,526,526,526
BEGIN DESCRIPTION:
TRIB 6 TO THOMAS CREEK 8.0
END DESCRIPTION:
XS GIS Cut Line= 3
      2402875.00     13566925.00      2402275.00     13566925.00
      2401675.03     13567474.97
#Sta/Elev= 30
  4364.7  435.34  4674.7  421.28  4764.7  417.88  4889.0  414.52  4971.8  412.32
  4983.5  409.75  4983.9  409.25  4988.4  409.75  5014.3  411.57  5056.9  412.45
  5092.0  412.00  5177.1  412.87  5227.2  414.81  5311.5  417.63  5346.7  417.57
  5417.6  419.23  5439.2  421.44  5469.4  421.12  5531.1  422.97  5552.0  425.02
  5566.2  424.08  5592.3  424.90  5615.8  427.39  5643.9  427.51  5687.9  430.62
  5700.6  431.50  5714.8  431.12  5757.4  433.47  5771.5  435.16  5778.6  434.47
#Mann=8,-1,0
  4364.7    0.05       0  4889.0    0.12       0  4983.5    0.05       0
  4988.4    0.12       0  5227.2    0.05       0  5469.4    0.03       0
  5592.3    0.05       0  5687.9    0.04       0
Bank Sta=4983.5,4988.4
Exp/Cntr=0.3,0.1

Type RM Length L Ch R = 1,3890,549,549,549
BEGIN DESCRIPTION:
TRIB 6 TO THOMAS CREEK 7.0
END DESCRIPTION:
XS GIS Cut Line= 3
      2402824.97     13566625.00      2402025.00     13566575.00
      2401724.97     13566524.99
#Sta/Elev= 30
  4203.3  432.23  4263.4  428.48  4343.5  425.18  4363.6  424.82  4373.6  423.75
  4393.6  423.20  4453.8  420.05  4503.9  418.03  4636.7  414.02  4674.2  412.82
  4754.3  411.59  4784.4  410.44  4844.5  410.03  4874.6  409.05  4922.2  410.21
  4927.2  409.70  5007.4  409.86  5022.7  407.33  5023.0  406.83  5027.2  406.83
  5027.6  407.33  5037.8  410.36  5116.3  415.55  5136.6  416.41  5154.4  418.18
  5207.6  421.59  5215.2  422.78  5220.3  422.53  5238.0  423.74  5309.0  430.06
#Mann=4,-1,0
  4203.3    0.05       0  4636.7    0.04       0  5022.7    0.04       0
  5027.6    0.04       0
Bank Sta=5022.7,5027.6
Exp/Cntr=0.3,0.1

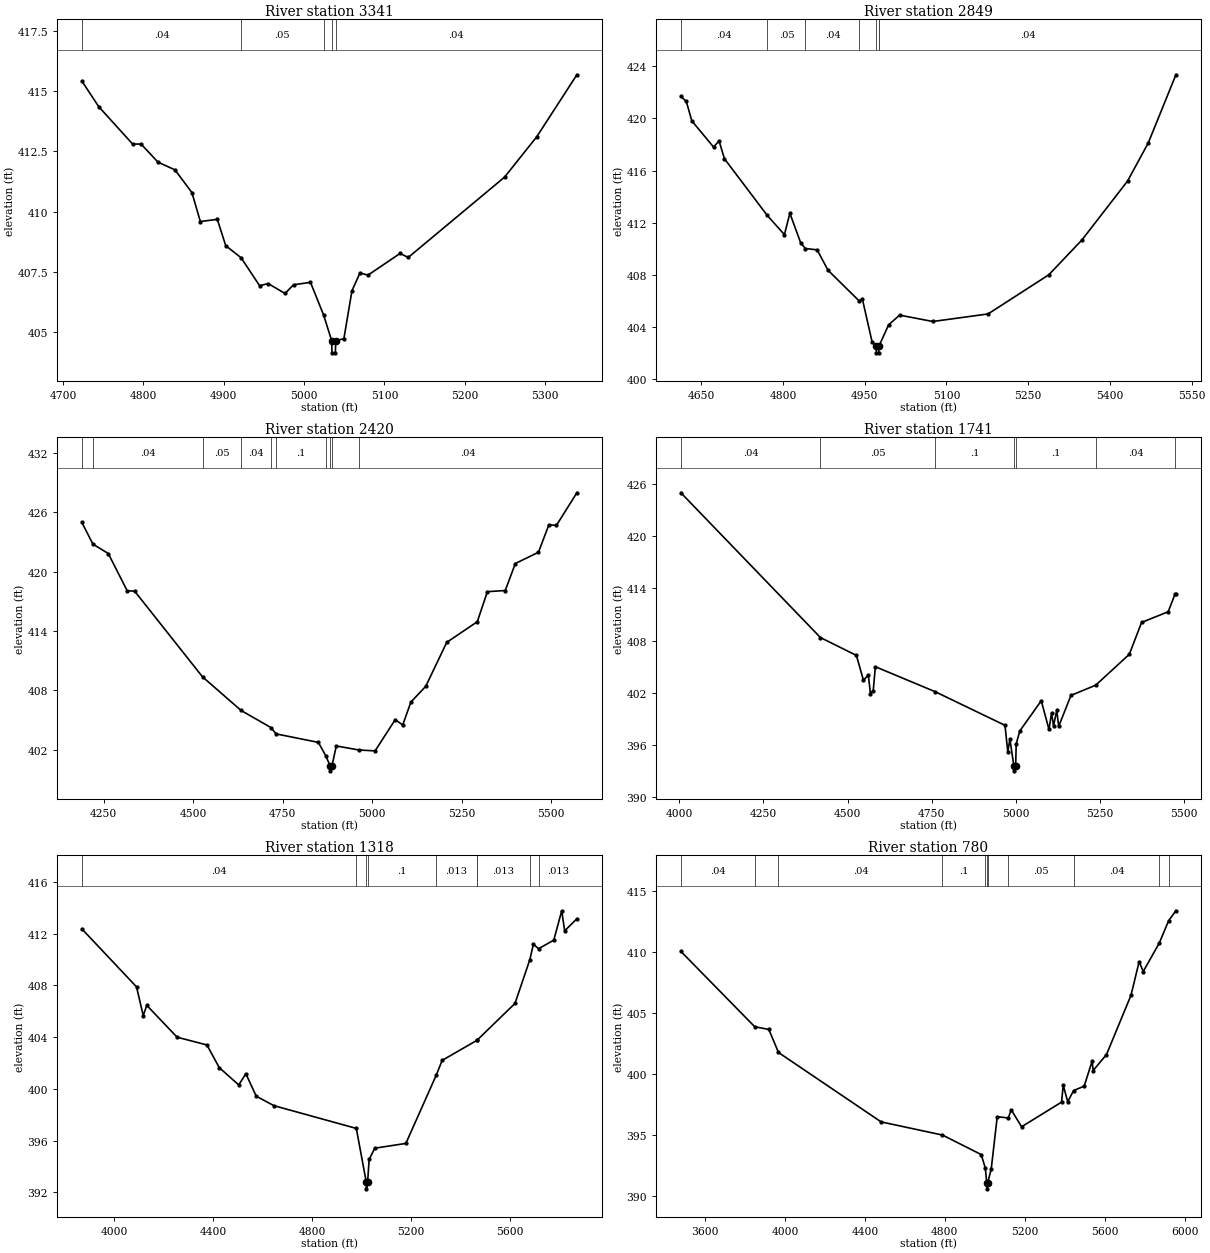
Type RM Length L Ch R = 1,3341,492,492,492
BEGIN DESCRIPTION:
TRIB 6 TO THOMAS CREEK 6.0
END DESCRIPTION:
XS GIS Cut Line= 3
      2402524.95     13566274.98      2402225.00     13566175.00
      2401924.98     13566175.00
#Sta/Elev= 30
  4723.3  415.41  4744.3  414.35  4786.5  412.80  4797.0  412.80  4818.1  412.05
  4839.2  411.73  4860.3  410.79  4870.8  409.59  4891.9  409.68  4902.4  408.59
  4921.5  408.09  4944.6  406.93  4955.2  407.02  4976.2  406.61  4986.8  406.97
  5007.9  407.07  5024.2  405.72  5034.3  404.65  5034.7  404.15  5038.9  404.15
  5039.3  404.65  5049.5  404.74  5059.5  406.72  5069.5  407.46  5079.5  407.37
  5119.5  408.27  5129.5  408.10  5249.5  411.43  5289.5  413.10  5339.5  415.67
#Mann=5,-1,0
  4723.3    0.04       0  4921.5    0.05       0  5024.2    0.04       0
  5034.3    0.05       0  5039.3    0.04       0
Bank Sta=5034.3,5039.3
Exp/Cntr=0.3,0.1

Type RM Length L Ch R = 1,2849,429,429,429
BEGIN DESCRIPTION:
TRIB 6 TO THOMAS CREEK 5.0
END DESCRIPTION:
XS GIS Cut Line= 3
      2402675.01     13565825.00      2402375.00     13565825.00
      2401774.99     13565925.00
#Sta/Elev= 30
  4612.8  421.70  4622.8  421.31  4632.8  419.82  4672.8  417.80  4682.8  418.28
  4692.8  416.90  4771.4  412.54  4802.8  411.07  4812.8  412.71  4832.8  410.42
  4841.4  410.00  4862.8  409.90  4882.8  408.33  4940.2  405.96  4945.8  406.12
  4963.5  402.85  4971.1  402.48  4971.5  401.98  4975.8  401.98  4976.1  402.48
  4976.2  402.49  4993.9  404.13  5014.2  404.88  5075.0  404.39  5176.4  404.97
  5287.9  407.98  5348.7  410.66  5432.4  415.19  5470.4  418.12  5521.1  423.36
#Mann=7,-1,0
  4612.8    0.04       0  4771.4    0.05       0  4841.4    0.04       0
  4940.2    0.05       0  4971.1    0.04       0  4976.1    0.05       0
  4976.2    0.04       0
Bank Sta=4971.1,4976.1
Exp/Cntr=0.3,0.1

Type RM Length L Ch R = 1,2420,679,679,679
BEGIN DESCRIPTION:
TRIB 6 TO THOMAS CREEK 4.0
END DESCRIPTION:
XS GIS Cut Line= 3
      2402774.97     13565624.99      2402175.00     13565425.00
      2401575.02     13565874.99
#Sta/Elev= 30
  4189.3  424.99  4220.1  422.80  4263.1  421.84  4315.8  418.08  4336.8  418.03
  4526.3  409.36  4634.0  405.96  4717.3  404.23  4731.6  403.59  4849.8  402.73
  4870.1  401.40  4882.8  400.35  4883.1  399.85  4887.8  400.35  4899.8  402.37
  4962.8  401.96  5008.2  401.87  5064.4  405.03  5085.3  404.49  5108.2  406.81
  5149.8  408.41  5208.2  412.85  5293.6  414.94  5321.7  417.98  5371.7  418.10
  5399.8  420.83  5464.4  421.97  5493.6  424.76  5514.4  424.68  5571.7  427.99
#Mann=10,-1,0
  4189.3    0.05       0  4220.1    0.04       0  4526.3    0.05       0
  4634.0    0.04       0  4717.3    0.05       0  4731.6     0.1       0
  4870.1    0.05       0  4882.8    0.04       0  4887.8    0.05       0
  4962.8    0.04       0
Bank Sta=4882.8,4887.8
Exp/Cntr=0.3,0.1

Type RM Length L Ch R = 1,1741,423,423,423
BEGIN DESCRIPTION:
TRIB 6 TO THOMAS CREEK 3.0
END DESCRIPTION:
XS GIS Cut Line= 3
      2402875.04     13565575.03      2402075.00     13564975.00
      2401675.04     13565224.98
#Sta/Elev= 30
  4004.5  425.02  4419.4  408.35  4526.4  406.29  4547.3  403.42  4561.8  404.03
  4568.1  401.88  4576.4  402.25  4582.7  404.99  4760.7  402.11  4968.1  398.24
  4976.4  395.19  4982.7  396.65  4994.7  393.50  4995.1  393.00  4999.8  393.50
  5001.4  396.11  5012.2  397.60  5075.9  401.07  5098.9  397.77  5106.6  399.68
  5112.4  398.17  5121.9  399.95  5127.8  398.13  5164.3  401.69  5237.7  402.86
  5337.7  406.42  5374.2  410.09  5453.3  411.32  5473.9  413.38  5476.2  413.38
#Mann=7,-1,0
  4004.5    0.04       0  4419.4    0.05       0  4760.7     0.1       0
  4994.7    0.05       0  4999.8     0.1       0  5237.7    0.04       0
  5473.9   0.013       0
Bank Sta=4994.7,4999.8
Exp/Cntr=0.3,0.1

Type RM Length L Ch R = 1,1318,538,538,538
BEGIN DESCRIPTION:
Mapping XS b7de3ca5
END DESCRIPTION:
XS GIS Cut Line= 4
      2403091.90     13565237.16      2402280.25     13564616.49
      2401828.86     13564759.72      2401616.18     13565219.81
#Sta/Elev= 30
  3868.1  412.37  4089.2  407.89  4116.3  405.67  4130.8  406.46  4253.3  404.00
  4373.9  403.40  4423.8  401.65  4502.7  400.31  4531.4  401.18  4573.4  399.44
  4644.7  398.71  4978.2  396.95  5018.7  392.78  5019.1  392.28  5023.8  392.78
  5030.1  394.55  5052.7  395.42  5178.6  395.79  5301.8  401.08  5325.5  402.21
  5465.5  403.75  5465.7  403.75  5620.0  406.61  5680.0  409.99  5694.3  411.18
  5715.5  410.84  5776.9  411.50  5809.0  413.77  5820.9  412.22  5870.3  413.15
#Mann=9,-1,0
  3868.1    0.04       0  4978.2     0.1       0  5018.7    0.05       0
  5023.8     0.1       0  5301.8   0.013       0  5465.5    0.04       0
  5465.7   0.013       0  5680.0    0.04       0  5715.5   0.013       0
Bank Sta=5018.7,5023.8
Exp/Cntr=0.3,0.1

Type RM Length L Ch R = 1,780,0,0,0
BEGIN DESCRIPTION:
TRIB 6 TO THOMAS CREEK 1.0
END DESCRIPTION:
XS GIS Cut Line= 4
      2403274.19     13564998.44      2402258.55     13564399.48
      2401733.38     13564369.10      2401574.99     13565125.02
#Sta/Elev= 30
  3479.0  410.04  3848.7  403.86  3919.2  403.64  3967.5  401.75  4481.1  396.06
  4788.3  394.98  4982.2  393.38  5002.7  392.27  5009.7  391.07  5010.1  390.57
  5014.8  391.07  5032.3  392.20  5062.3  396.49  5117.5  396.38  5132.4  397.05
  5184.2  395.66  5384.3  397.68  5392.6  399.07  5415.0  397.71  5444.6  398.63
  5497.5  398.99  5537.2  401.04  5542.3  400.27  5609.1  401.58  5731.7  406.44
  5772.6  409.20  5793.0  408.39  5873.8  410.74  5919.9  412.55  5956.5  413.37
#Mann=11,-1,0
  3479.0    0.04       0  3848.7    0.05       0  3967.5    0.04       0
  4788.3     0.1       0  5002.7   0.013       0  5009.7    0.05       0
  5014.8   0.013       0  5117.5    0.05       0  5444.6    0.04       0
  5873.8   0.013       0  5919.9    0.04       0
Bank Sta=5009.7,5014.8
Exp/Cntr=0.3,0.1

Chan Stop Cuts=-1