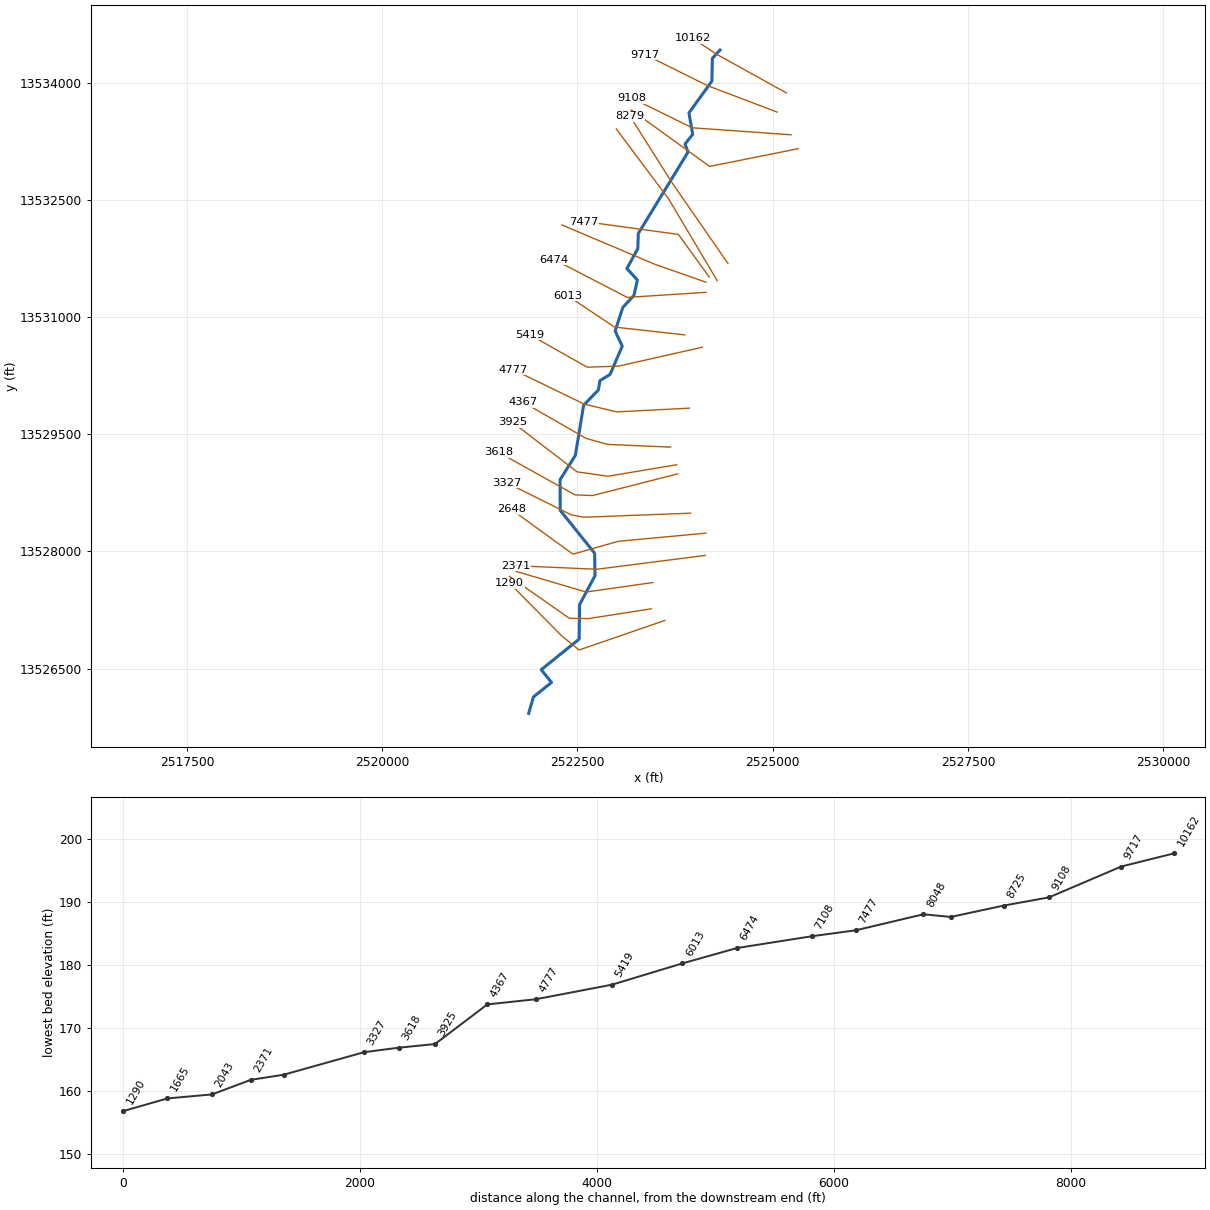
--- TRIB 6 TO TWELVEMILE CREEK.prj (project) ---

Proj Title=TRIB 6 TO TWELVEMILE CREEK Base Level Engineering
Current Plan=p01
Default Exp/Contr=0.3,0.1
English Units
Geom File=g01
Flow File=f01
Plan File=p01
BEGIN DESCRIPTION:
TRIB 6 TO TWELVEMILE CREEK
END DESCRIPTION:

--- TRIB 6 TO TWELVEMILE CREEK.p01 (plan) ---

Plan Title=Multiple Run
Short Identifier=Multiple
Geom File=g01
Flow File=f01
Subcritical Flow
K Sum by GR= 0
Std Step Tol= 0.01
Critical Tol= 0.01
Num of Std Step Trials= 20
Max Error Tol= 0.3
Flow Tol Ratio= 0.001
Split Flow NTrial= 30
Split Flow Tol= 0.02
Split Flow Ratio= 0.02
Log Output Level= 0
Friction Slope Method= 1
Unsteady Friction Slope Method= 2
Unsteady Bridges Friction Slope Method= 1
Parabolic Critical Depth
Global Vel Dist=  1 , 1 , 1
Global Log Level= 0
CheckData=True
Encroach Param= -1, 0, 0, 0
BEGIN DESCRIPTION:
Multiple Run
END DESCRIPTION:

--- TRIB 6 TO TWELVEMILE CREEK.f01 (steady flow) ---

Flow Title=Multiple
Number of Profiles=7
Profile Names=10-year,25-year,50-year,1pct_min,100-year,1pct_plu,500-year
River Rch & RM= TRIB 6 TO TWELVE,Reach-1,10162
     514     813    1078     693    1383    2760    2248
River Rch & RM= TRIB 6 TO TWELVE,Reach-1,9717
     747    1204    1616    1049    2093    4176    3474
River Rch & RM= TRIB 6 TO TWELVE,Reach-1,2648
    1004    1645    2234    1466    2925    5837    4962
River Rch & RM= TRIB 6 TO TWELVE,Reach-1,2371
    1097    1807    2463    1621    3235    6454    5523
Boundary for River Rch & Prof#=TRIB 6 TO TWELVE,Reach-1,1
Up Type=0
Dn Type=3
Dn Slope=0.005
Boundary for River Rch & Prof#=TRIB 6 TO TWELVE,Reach-1,2
Up Type=0
Dn Type=3
Dn Slope=0.005
Boundary for River Rch & Prof#=TRIB 6 TO TWELVE,Reach-1,3
Up Type=0
Dn Type=3
Dn Slope=0.005
Boundary for River Rch & Prof#=TRIB 6 TO TWELVE,Reach-1,4
Up Type=0
Dn Type=3
Dn Slope=0.005
Boundary for River Rch & Prof#=TRIB 6 TO TWELVE,Reach-1,5
Up Type=0
Dn Type=3
Dn Slope=0.005
Boundary for River Rch & Prof#=TRIB 6 TO TWELVE,Reach-1,6
Up Type=0
Dn Type=3
Dn Slope=0.005
Boundary for River Rch & Prof#=TRIB 6 TO TWELVE,Reach-1,7
Up Type=0
Dn Type=3
Dn Slope=0.005

--- TRIB 6 TO TWELVEMILE CREEK.g01 (geometry) ---

Geom Title=Existing Conditions

River Reach=TRIB 6 TO TWELVE,Reach-1
Reach XY= 30
      2524325.00     13534425.00      2524227.02     13534319.16
      2524221.25     13534026.55      2523927.06     13533619.14
      2523975.39     13533345.13      2523876.67     13533218.95
      2523915.85     13533118.27      2523278.55     13532073.53
      2523272.76     13531880.93      2523132.29     13531624.91
      2523267.20     13531478.42      2523222.93     13531280.86
      2523080.83     13531127.30      2522982.33     13530824.90
      2523072.86     13530630.97      2522917.25     13530268.55
      2522788.26     13530188.65      2522767.14     13530068.83
      2522578.61     13529873.50      2522472.75     13529230.93
      2522277.06     13528919.14      2522278.75     13528526.55
      2522719.54     13527977.45      2522724.61     13527690.16
      2522527.07     13527319.14      2522521.47     13526876.45
      2522035.95     13526485.00      2522167.52     13526321.42
      2521935.52     13526134.79      2521875.00     13525925.00

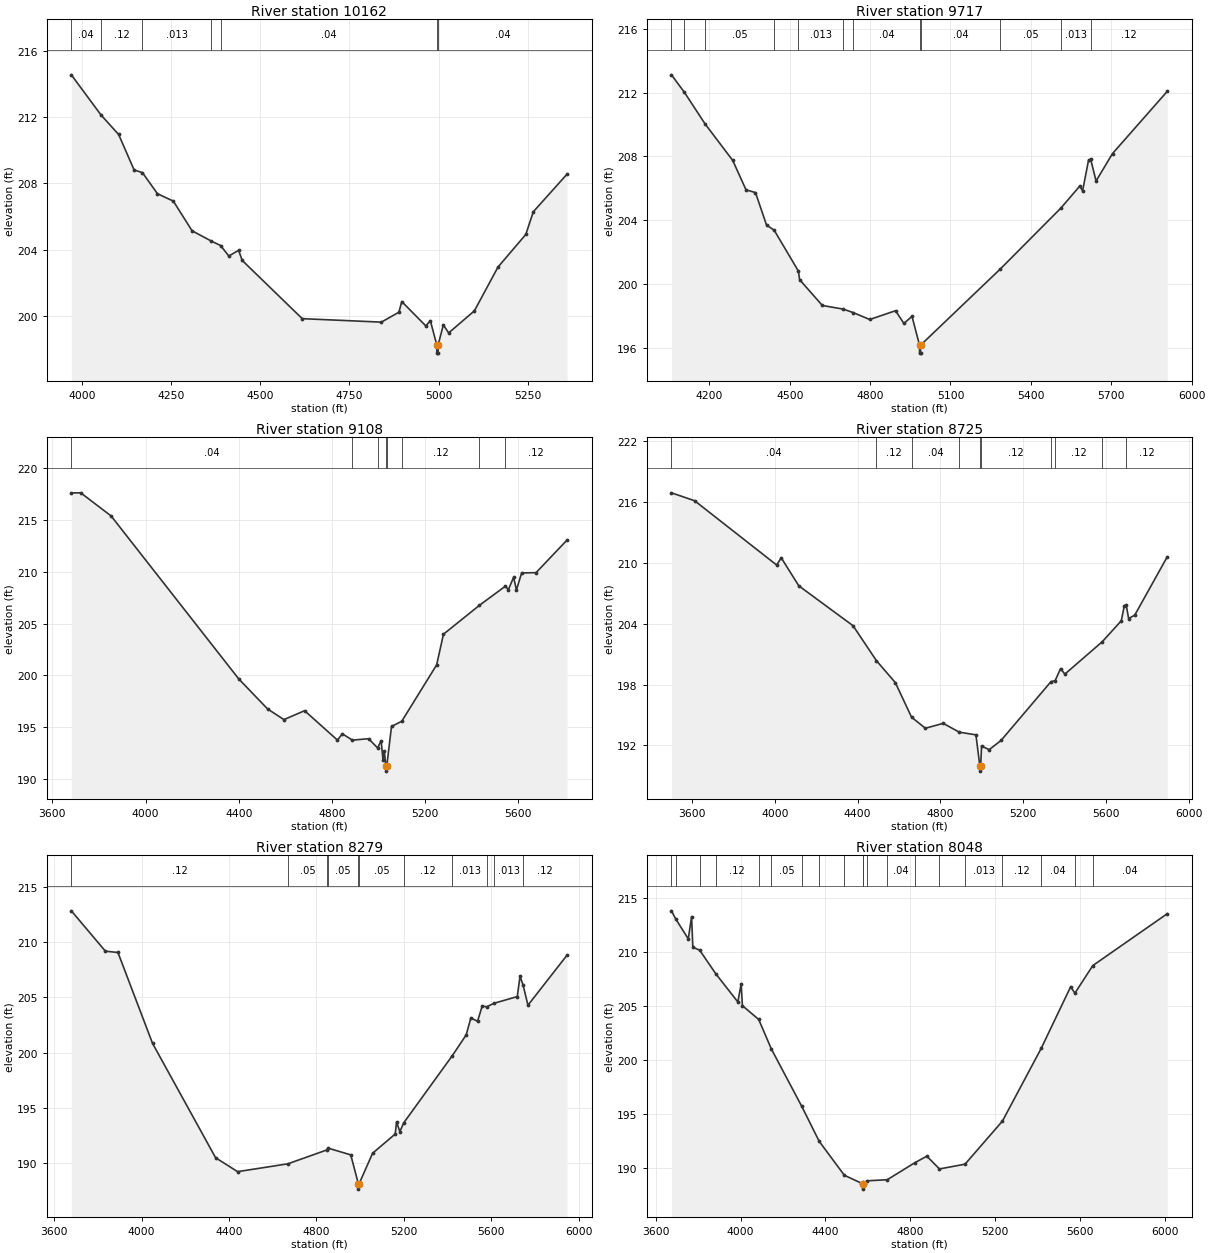
Type RM Length L Ch R = 1,10162,445,445,445
BEGIN DESCRIPTION:
TRIB 6 TO TWELVEMILE CREEK 19.0
END DESCRIPTION:
XS GIS Cut Line= 3
      2525174.98     13533875.01      2524275.00     13534375.00
      2523975.00     13534575.00
#Sta/Elev= 30
  3970.1  214.54  4053.6  212.11  4102.8  210.94  4146.2  208.80  4169.5  208.64
  4211.5  207.37  4256.1  206.92  4308.7  205.13  4362.7  204.51  4388.7  204.24
  4411.6  203.61  4439.1  203.95  4449.4  203.34  4617.6  199.83  4839.5  199.62
  4888.7  200.22  4896.7  200.86  4964.2  199.39  4976.8  199.71  4994.8  198.25
  4995.0  197.75  4998.5  197.75  4998.8  198.25  5013.2  199.45  5028.2  198.97
  5100.3  200.30  5166.4  202.94  5244.5  204.91  5265.6  206.28  5360.2  208.55
#Mann=7,-1,0
  3970.1    0.04       0  4053.6    0.12       0  4169.5   0.013       0
  4362.7    0.12       0  4388.7    0.04       0  4994.8    0.04       0
  4998.8    0.04       0
Bank Sta=4994.8,4998.8
Exp/Cntr=0.3,0.1

Type RM Length L Ch R = 1,9717,609,609,609
BEGIN DESCRIPTION:
Mapping XS 63334d77
END DESCRIPTION:
XS GIS Cut Line= 3
      2525056.50     13533629.72      2524166.46     13533968.61
      2523362.11     13534367.06
#Sta/Elev= 30
  4058.7  213.12  4107.1  212.02  4184.2  210.04  4287.3  207.75  4336.8  205.91
  4372.3  205.73  4413.4  203.70  4442.1  203.37  4532.6  200.80  4536.9  200.27
  4621.8  198.65  4700.1  198.42  4737.5  198.20  4798.6  197.77  4894.9  198.32
  4926.2  197.52  4956.3  197.97  4984.4  196.16  4984.6  195.66  4988.1  195.66
  4988.4  196.16  5286.0  200.94  5511.9  204.76  5582.4  206.14  5593.0  205.84
  5615.3  207.78  5623.2  207.82  5643.2  206.46  5704.6  208.18  5908.7  212.08
#Mann=12,-1,0
  4058.7    0.05       0  4107.1    0.04       0  4184.2    0.05       0
  4442.1    0.12       0  4532.6   0.013       0  4700.1    0.12       0
  4737.5    0.04       0  4984.4    0.04       0  4988.4    0.04       0
  5286.0    0.05       0  5511.9   0.013       0  5623.2    0.12       0
Bank Sta=4984.4,4988.4
Exp/Cntr=0.3,0.1

Type RM Length L Ch R = 1,9108,383,383,383
BEGIN DESCRIPTION:
Mapping XS e50059ae
END DESCRIPTION:
XS GIS Cut Line= 3
      2525235.26     13533339.26      2523969.09     13533428.64
      2523199.11     13533808.05
#Sta/Elev= 30
  3681.3  217.61  3721.7  217.62  3852.0  215.39  4400.1  199.66  4523.6  196.77
  4593.8  195.74  4682.5  196.60  4823.6  193.76  4844.4  194.37  4887.9  193.76
  4957.2  193.90  4996.1  193.00  5010.9  193.71  5019.0  191.86  5024.6  192.69
  5031.2  191.27  5031.5  190.77  5035.2  191.27  5055.5  195.08  5099.5  195.58
  5249.2  201.02  5278.5  203.98  5433.0  206.77  5544.1  208.61  5557.2  208.28
  5579.5  209.47  5591.7  208.25  5614.1  209.89  5675.9  209.92  5809.0  213.07
#Mann=8,-1,0
  3681.3    0.04       0  4887.9    0.12       0  4996.1   0.013       0
  5031.2    0.03       0  5035.2   0.013       0  5099.5    0.12       0
  5433.0   0.013       0  5544.1    0.12       0
Bank Sta=5031.2,5035.2
Exp/Cntr=0.3,0.1

Type RM Length L Ch R = 1,8725,446,446,446
BEGIN DESCRIPTION:
Mapping XS 9ac52b5b
END DESCRIPTION:
XS GIS Cut Line= 3
      2525324.60     13533160.52      2524192.53     13532933.36
      2523188.53     13533658.47
#Sta/Elev= 30
  3501.4  216.91  3613.2  216.13  4009.1  209.79  4031.4  210.50  4116.0  207.74
  4378.1  203.80  4491.0  200.35  4582.1  198.19  4660.5  194.78  4727.0  193.69
  4813.3  194.17  4891.2  193.30  4971.2  193.04  4990.1  189.96  4990.3  189.46
  4994.1  189.96  4998.4  191.93  5035.4  191.58  5092.6  192.49  5333.2  198.28
  5353.4  198.38  5379.7  199.57  5400.5  199.03  5580.9  202.22  5672.9  204.29
  5687.6  205.79  5696.7  205.83  5708.4  204.51  5737.9  204.85  5894.5  210.59
#Mann=10,-1,0
  3501.4    0.04       0  4491.0    0.12       0  4660.5    0.04       0
  4891.2    0.12       0  4990.1    0.05       0  4994.1    0.12       0
  5333.2   0.013       0  5353.4    0.12       0  5580.9   0.013       0
  5696.7    0.12       0
Bank Sta=4990.1,4994.1
Exp/Cntr=0.3,0.1

Type RM Length L Ch R = 1,8279,231,231,231
BEGIN DESCRIPTION:
Mapping XS aadf8ba8
END DESCRIPTION:
XS GIS Cut Line= 3
      2524427.11     13531689.62      2523715.87     13532717.38
      2523172.18     13533577.60
#Sta/Elev= 30
  3678.7  212.84  3834.5  209.19  3892.0  209.07  4050.1  200.85  4338.6  190.50
  4439.2  189.24  4669.3  189.95  4849.4  191.22  4853.1  191.37  4956.8  190.76
  4991.3  188.16  4991.5  187.66  4995.3  188.16  5056.8  190.91  5160.3  192.65
  5166.2  193.74  5181.5  192.86  5198.8  193.65  5421.8  199.75  5485.0  201.62
  5506.2  203.16  5536.7  202.84  5557.9  204.22  5579.0  204.16  5612.7  204.48
  5718.4  205.08  5730.9  206.90  5744.7  206.15  5767.3  204.30  5946.2  208.83
#Mann=11,-1,0
  3678.7    0.12       0  4669.3    0.05       0  4849.4   0.013       0
  4853.1    0.05       0  4991.3    0.05       0  4995.3    0.05       0
  5198.8    0.12       0  5421.8   0.013       0  5579.0    0.12       0
  5612.7   0.013       0  5744.7    0.12       0
Bank Sta=4991.3,4995.3
Exp/Cntr=0.3,0.1

Type RM Length L Ch R = 1,8048,571,571,571
BEGIN DESCRIPTION:
Mapping XS ceed2c61
END DESCRIPTION:
XS GIS Cut Line= 3
      2524289.37     13531469.83      2523667.46     13532516.29
      2522997.13     13533413.78
#Sta/Elev= 30
  3674.4  213.85  3694.5  213.10  3753.7  211.25  3769.3  213.32  3775.2  210.48
  3807.3  210.21  3883.8  208.01  3987.5  205.41  4003.1  207.09  4008.9  205.07
  4085.8  203.79  4145.6  201.05  4287.8  195.78  4371.2  192.50  4489.8  189.36
  4575.8  188.58  4576.0  188.08  4579.8  188.58  4596.7  188.85  4691.9  188.95
  4822.3  190.53  4878.6  191.13  4938.1  189.95  5058.6  190.39  5235.0  194.38
  5417.9  201.12  5556.9  206.83  5576.5  206.22  5661.1  208.78  6011.9  213.58
#Mann=20,-1,0
  3674.4   0.013       0  3694.5    0.12       0  3807.3   0.013       0
  3883.8    0.12       0  4085.8    0.12       0  4145.6    0.05       0
  4287.8    0.12       0  4371.2   0.013       0  4489.8    0.04       0
  4575.8    0.05       0  4579.8    0.04       0  4596.7   0.013       0
  4691.9    0.04       0  4822.3   0.013       0  4938.1    0.05       0
  5058.6   0.013       0  5235.0    0.12       0  5417.9    0.04       0
  5576.5   0.013       0  5661.1    0.04       0
Bank Sta=4575.8,4579.8
Exp/Cntr=0.3,0.1

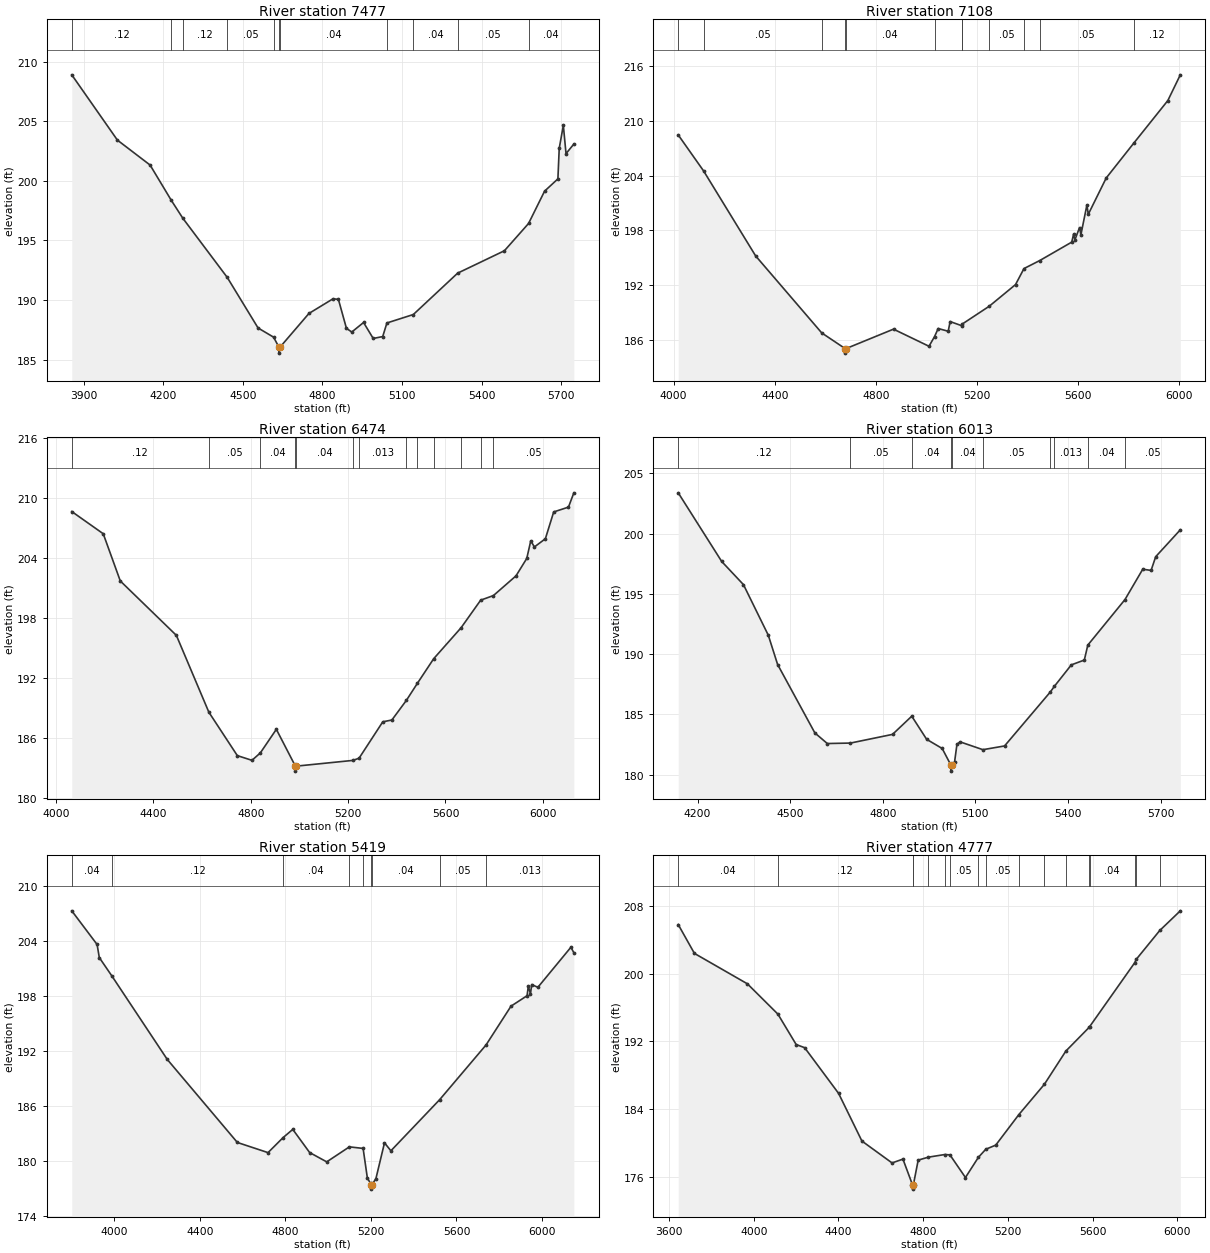
Type RM Length L Ch R = 1,7477,369,369,369
BEGIN DESCRIPTION:
Mapping XS 1f19bb34
END DESCRIPTION:
XS GIS Cut Line= 3
      2524187.32     13531515.71      2523792.37     13532062.56
      2522585.76     13532227.50
#Sta/Elev= 30
  3855.0  208.89  4027.1  203.41  4150.2  201.32  4230.4  198.35  4273.5  196.86
  4441.1  191.89  4557.2  187.65  4615.6  186.88  4635.9  186.04  4636.2  185.54
  4639.9  186.04  4749.0  188.87  4839.8  190.10  4860.0  190.05  4890.3  187.62
  4910.4  187.31  4954.8  188.11  4991.2  186.77  5027.0  186.93  5042.8  188.07
  5142.4  188.78  5309.4  192.25  5485.7  194.13  5576.8  196.42  5637.1  199.13
  5687.3  200.16  5692.3  202.72  5707.8  204.65  5717.9  202.28  5747.4  203.08
#Mann=11,-1,0
  3855.0    0.12       0  4230.4    0.05       0  4273.5    0.12       0
  4441.1    0.05       0  4615.6    0.04       0  4635.9    0.04       0
  4639.9    0.04       0  5042.8   0.013       0  5142.4    0.04       0
  5309.4    0.05       0  5576.8    0.04       0
Bank Sta=4635.9,4639.9
Exp/Cntr=0.3,0.1

Type RM Length L Ch R = 1,7108,634,634,634
BEGIN DESCRIPTION:
Mapping XS 153bf69a
END DESCRIPTION:
XS GIS Cut Line= 3
      2524143.96     13531450.58      2523488.55     13531680.62
      2522299.62     13532183.96
#Sta/Elev= 30
  4018.4  208.44  4118.9  204.50  4324.6  195.22  4585.9  186.81  4678.3  185.10
  4678.6  184.60  4682.3  185.10  4869.8  187.22  5010.1  185.35  5032.0  186.40
  5046.5  187.29  5086.1  186.99  5093.8  188.05  5140.1  187.59  5142.3  187.79
  5248.2  189.72  5352.4  192.09  5385.8  193.84  5448.4  194.72  5574.7  196.73
  5581.9  197.59  5587.3  196.98  5605.5  198.32  5611.0  197.54  5634.7  200.79
  5640.1  199.77  5711.1  203.74  5819.3  207.52  5954.8  212.20  6004.1  215.01
#Mann=12,-1,0
  4018.4    0.12       0  4118.9    0.05       0  4585.9    0.04       0
  4678.3    0.04       0  4682.3    0.04       0  5032.0   0.013       0
  5140.1    0.05       0  5142.3    0.04       0  5248.2    0.05       0
  5385.8    0.04       0  5448.4    0.05       0  5819.3    0.12       0
Bank Sta=4678.3,4682.3
Exp/Cntr=0.3,0.1

Type RM Length L Ch R = 1,6474,461,461,461
BEGIN DESCRIPTION:
Mapping XS fbfb0f44
END DESCRIPTION:
XS GIS Cut Line= 3
      2524143.98     13531320.38      2523136.99     13531255.27
      2522201.12     13531740.54
#Sta/Elev= 30
  4064.2  208.67  4193.5  206.45  4263.6  201.73  4494.1  196.29  4627.6  188.61
  4744.6  184.27  4804.7  183.80  4839.1  184.54  4904.9  186.90  4983.1  183.22
  4983.4  182.72  4987.1  183.22  5218.8  183.79  5244.8  184.01  5342.3  187.65
  5379.7  187.83  5439.2  189.79  5484.6  191.50  5551.6  193.96  5664.0  197.05
  5744.6  199.81  5797.0  200.27  5889.8  202.24  5934.0  203.98  5950.5  205.74
  5965.4  205.13  6010.5  205.95  6044.7  208.63  6105.4  209.11  6127.5  210.54
#Mann=13,-1,0
  4064.2    0.12       0  4627.6    0.05       0  4839.1    0.04       0
  4983.1    0.04       0  4987.1    0.04       0  5218.8    0.05       0
  5244.8   0.013       0  5439.2    0.04       0  5484.6    0.05       0
  5551.6    0.04       0  5664.0    0.05       0  5744.6    0.12       0
  5797.0    0.05       0
Bank Sta=4983.1,4987.1
Exp/Cntr=0.3,0.1

Type RM Length L Ch R = 1,6013,594,594,594
BEGIN DESCRIPTION:
TRIB 6 TO TWELVEMILE CREEK 10.0
END DESCRIPTION:
XS GIS Cut Line= 3
      2523875.00     13530775.00      2522975.00     13530875.00
      2522374.96     13531275.03
#Sta/Elev= 30
  4137.2  203.38  4278.1  197.68  4348.5  195.76  4429.0  191.56  4459.2  189.13
  4579.9  183.45  4620.2  182.57  4695.3  182.61  4831.5  183.33  4893.8  184.84
  4942.1  182.92  4992.4  182.16  5020.6  180.78  5020.9  180.28  5024.6  180.78
  5032.7  181.07  5040.2  182.50  5050.3  182.71  5124.3  182.06  5194.5  182.37
  5343.1  186.86  5355.9  187.32  5410.8  189.10  5452.9  189.50  5464.2  190.74
  5584.6  194.52  5642.2  197.04  5669.2  196.94  5684.2  198.08  5763.9  200.31
#Mann=10,-1,0
  4137.2    0.12       0  4695.3    0.05       0  4893.8    0.04       0
  5020.6    0.04       0  5024.6    0.04       0  5124.3    0.05       0
  5343.1    0.04       0  5355.9   0.013       0  5464.2    0.04       0
  5584.6    0.05       0
Bank Sta=5020.6,5024.6
Exp/Cntr=0.3,0.1

Type RM Length L Ch R = 1,5419,642,642,642
BEGIN DESCRIPTION:
Mapping XS 17f79b83
END DESCRIPTION:
XS GIS Cut Line= 4
      2524100.58     13530617.26      2523024.14     13530374.20
      2522624.84     13530361.18      2521888.49     13530777.00
#Sta/Elev= 30
  3800.3  207.32  3918.8  203.64  3929.1  202.21  3987.9  200.20  4246.9  191.08
  4574.9  182.00  4718.4  180.89  4789.2  182.54  4834.2  183.43  4913.0  180.90
  4993.0  179.88  5098.9  181.52  5163.2  181.35  5183.1  178.11  5201.1  177.40
  5201.4  176.90  5205.1  177.40  5223.1  178.05  5263.2  181.96  5293.2  181.09
  5521.7  186.69  5738.3  192.66  5855.1  196.90  5930.2  198.04  5936.0  199.09
  5946.1  198.24  5951.9  199.26  5980.7  198.96  6135.3  203.34  6149.0  202.74
#Mann=9,-1,0
  3800.3    0.04       0  3987.9    0.12       0  4789.2    0.04       0
  5098.9    0.05       0  5163.2    0.04       0  5201.1    0.04       0
  5205.1    0.04       0  5521.7    0.05       0  5738.3   0.013       0
Bank Sta=5201.1,5205.1
Exp/Cntr=0.3,0.1

Type RM Length L Ch R = 1,4777,410,410,410
BEGIN DESCRIPTION:
Mapping XS 63a22a29
END DESCRIPTION:
XS GIS Cut Line= 4
      2523931.26     13529836.00      2523002.44     13529788.26
      2522585.78     13529888.08      2521675.12     13530330.41
#Sta/Elev= 30
  3643.6  205.79  3720.0  202.39  3970.3  198.80  4114.2  195.23  4200.6  191.64
  4240.6  191.27  4400.9  185.88  4511.0  180.26  4653.3  177.68  4704.7  178.13
  4749.9  175.09  4750.1  174.59  4753.9  175.09  4776.7  178.01  4824.8  178.36
  4902.4  178.67  4926.6  178.63  4999.9  175.96  5061.0  178.34  5095.8  179.29
  5142.9  179.78  5252.4  183.39  5372.5  186.95  5474.0  190.87  5584.9  193.69
  5585.7  193.73  5798.9  201.28  5806.5  201.69  5917.4  205.09  6014.5  207.41
#Mann=17,-1,0
  3643.6    0.04       0  4114.2    0.12       0  4749.9    0.05       0
  4753.9    0.12       0  4824.8    0.05       0  4902.4    0.04       0
  4926.6    0.05       0  5061.0    0.12       0  5095.8    0.05       0
  5252.4    0.04       0  5372.5    0.05       0  5474.0    0.04       0
  5584.9    0.05       0  5585.7    0.04       0  5798.9   0.013       0
  5806.5    0.04       0  5917.4    0.05       0
Bank Sta=4749.9,4753.9
Exp/Cntr=0.3,0.1

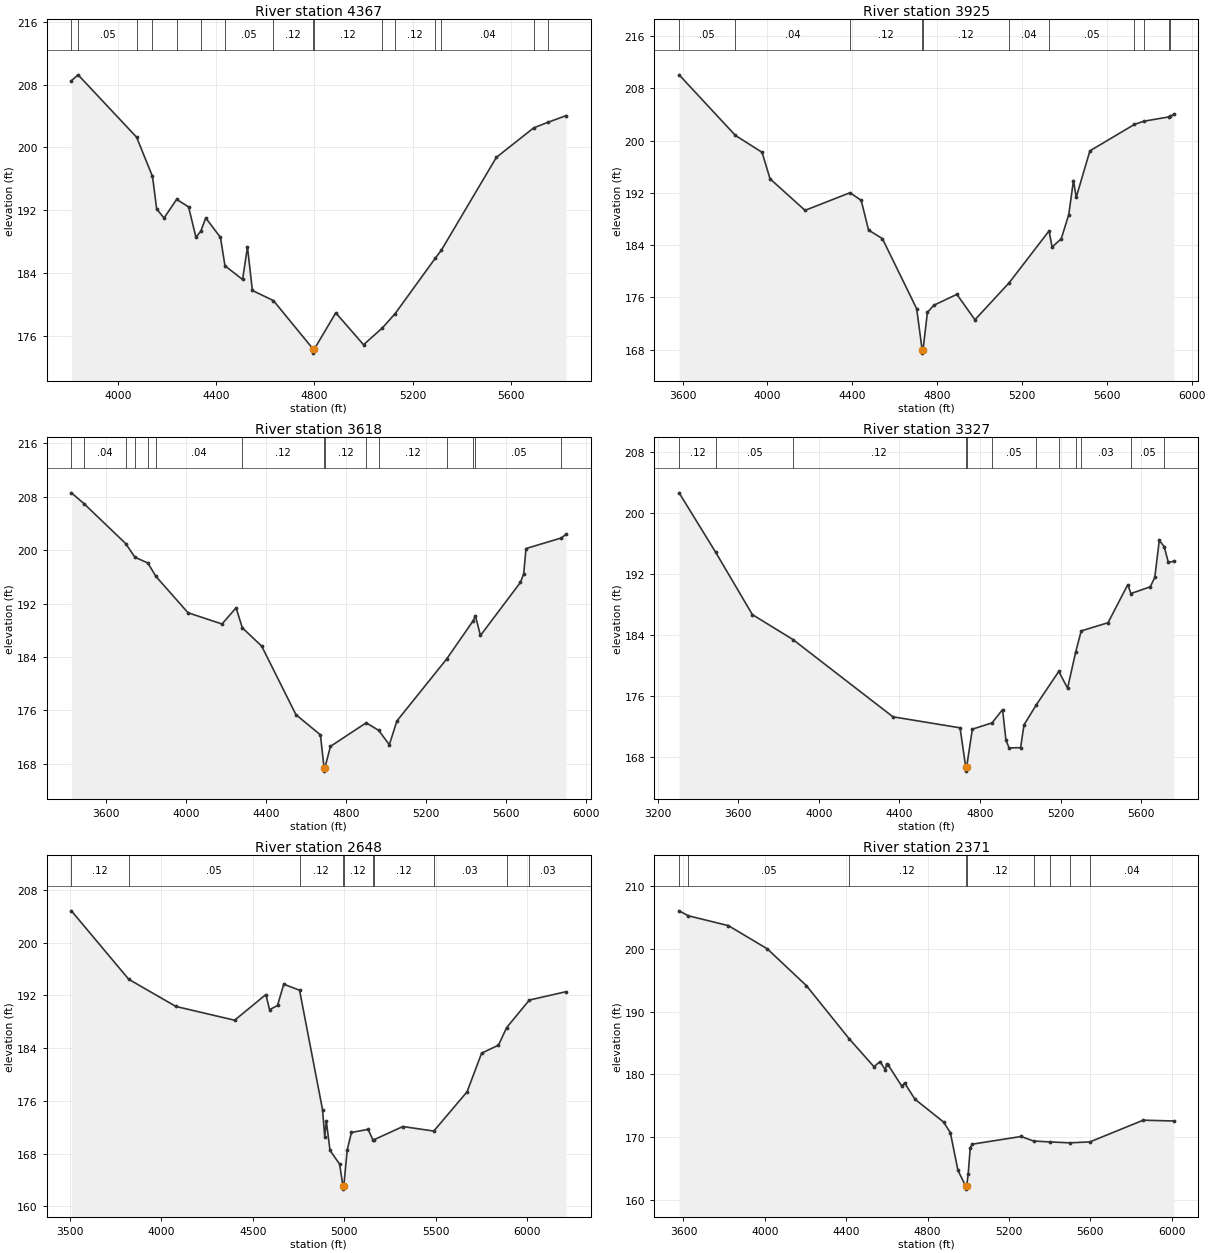
Type RM Length L Ch R = 1,4367,442,442,442
BEGIN DESCRIPTION:
Mapping XS 24be71d0
END DESCRIPTION:
XS GIS Cut Line= 4
      2523692.55     13529336.87      2522885.26     13529371.59
      2522607.48     13529449.72      2521809.43     13529909.46
#Sta/Elev= 30
  3808.5  208.51  3835.9  209.26  4074.6  201.30  4139.3  196.30  4156.4  192.15
  4186.4  191.00  4237.8  193.38  4286.5  192.42  4316.5  188.54  4336.3  189.33
  4356.6  191.01  4416.6  188.52  4434.9  184.91  4506.7  183.16  4526.7  187.31
  4546.7  181.76  4632.6  180.47  4795.0  174.27  4795.2  173.77  4799.0  174.27
  4886.9  178.91  5000.2  174.84  5077.1  176.99  5129.1  178.81  5291.9  185.84
  5317.4  186.89  5541.8  198.73  5693.9  202.49  5753.3  203.22  5826.1  204.05
#Mann=16,-1,0
  3808.5    0.04       0  3835.9    0.05       0  4074.6    0.04       0
  4139.3    0.03       0  4237.8    0.04       0  4336.3    0.03       0
  4434.9    0.05       0  4632.6    0.12       0  4795.0    0.05       0
  4799.0    0.12       0  5077.1    0.04       0  5129.1    0.12       0
  5291.9    0.05       0  5317.4    0.04       0  5693.9    0.05       0
  5753.3    0.04       0
Bank Sta=4795,4799
Exp/Cntr=0.3,0.1

Type RM Length L Ch R = 1,3925,307,307,307
BEGIN DESCRIPTION:
Mapping XS 500c5b50
END DESCRIPTION:
XS GIS Cut Line= 4
      2523770.68     13529111.18      2522889.60     13528963.61
      2522494.63     13529020.03      2521670.01     13529653.69
#Sta/Elev= 30
  3583.3  210.08  3848.8  200.80  3974.4  198.22  4012.0  194.16  4177.1  189.33
  4389.1  192.03  4441.9  190.86  4476.5  186.31  4541.9  185.00  4703.5  174.26
  4729.3  167.97  4729.6  167.47  4733.4  167.97  4754.0  173.71  4784.3  174.80
  4893.0  176.47  4978.2  172.58  5139.7  178.25  5327.8  186.19  5341.8  183.71
  5385.1  184.97  5420.5  188.68  5442.7  193.90  5455.8  191.34  5520.2  198.44
  5729.8  202.48  5773.4  202.97  5892.6  203.64  5898.3  203.72  5915.6  204.02
#Mann=11,-1,0
  3583.3    0.05       0  3848.8    0.04       0  4389.1    0.12       0
  4729.3    0.05       0  4733.4    0.12       0  5139.7    0.04       0
  5327.8    0.05       0  5729.8    0.04       0  5773.4    0.05       0
  5892.6    0.04       0  5898.3    0.05       0
Bank Sta=4729.3,4733.4
Exp/Cntr=0.3,0.1

Type RM Length L Ch R = 1,3618,291,291,291
BEGIN DESCRIPTION:
Mapping XS dd5aa705
END DESCRIPTION:
XS GIS Cut Line= 4
      2523783.67     13528993.98      2522694.28     13528716.21
      2522468.59     13528724.89      2521490.44     13529270.23
#Sta/Elev= 30
  3428.1  208.60  3490.5  206.99  3699.0  201.00  3745.5  198.94  3809.7  198.09
  3849.8  196.09  4010.3  190.63  4180.1  188.94  4250.4  191.36  4281.7  188.37
  4378.2  185.63  4549.4  175.35  4671.7  172.32  4689.7  167.39  4689.9  166.89
  4693.8  167.39  4721.7  170.60  4900.2  174.13  4962.5  173.00  5015.8  170.85
  5053.5  174.41  5301.3  183.67  5434.0  189.41  5445.6  190.19  5470.7  187.22
  5670.7  195.19  5686.7  196.47  5698.2  200.25  5874.0  201.83  5898.1  202.38
#Mann=15,-1,0
  3428.1    0.05       0  3490.5    0.04       0  3699.0    0.05       0
  3745.5    0.04       0  3809.7    0.05       0  3849.8    0.04       0
  4281.7    0.12       0  4689.7    0.05       0  4693.8    0.12       0
  4900.2    0.05       0  4962.5    0.12       0  5301.3    0.05       0
  5434.0    0.04       0  5445.6    0.05       0  5874.0    0.04       0
Bank Sta=4689.7,4693.8
Exp/Cntr=0.3,0.1

Type RM Length L Ch R = 1,3327,679,679,679
BEGIN DESCRIPTION:
Mapping XS 05f412c6
END DESCRIPTION:
XS GIS Cut Line= 4
      2523948.58     13528490.51      2522581.44     13528438.43
      2522420.85     13528468.81      2521592.97     13528880.58
#Sta/Elev= 30
  3306.0  202.61  3488.2  194.80  3669.8  186.67  3871.0  183.41  4367.8  173.29
  4701.0  171.85  4729.4  166.68  4729.6  166.18  4733.5  166.68  4762.1  171.67
  4860.0  172.50  4912.2  174.24  4929.0  170.23  4944.6  169.22  5001.7  169.25
  5018.6  172.24  5079.8  174.86  5191.2  179.23  5235.0  177.04  5274.7  181.71
  5302.6  184.53  5436.0  185.61  5533.7  190.58  5549.8  189.43  5645.6  190.31
  5668.0  191.54  5690.4  196.38  5714.8  195.57  5735.2  193.51  5762.2  193.65
#Mann=12,-1,0
  3306.0    0.12       0  3488.2    0.05       0  3871.0    0.12       0
  4729.4    0.05       0  4733.5    0.12       0  4860.0    0.05       0
  5079.8    0.03       0  5191.2    0.05       0  5274.7    0.12       0
  5302.6    0.03       0  5549.8    0.05       0  5714.8    0.03       0
Bank Sta=4729.4,4733.5
Exp/Cntr=0.3,0.1

Type RM Length L Ch R = 1,2648,277,277,277
BEGIN DESCRIPTION:
Mapping XS ae3e2834
END DESCRIPTION:
XS GIS Cut Line= 4
      2524143.90     13528234.44      2523024.14     13528130.27
      2522442.55     13527965.34      2521652.65     13528538.24
#Sta/Elev= 30
  3507.7  204.83  3821.4  194.44  4079.1  190.32  4400.4  188.23  4571.2  192.13
  4591.3  189.82  4634.9  190.47  4668.9  193.70  4755.4  192.78  4880.9  174.68
  4893.2  170.54  4901.7  172.95  4921.9  168.47  4974.4  166.40  4992.4  163.10
  4992.8  162.60  4997.5  163.10  5016.0  168.56  5039.2  171.20  5130.3  171.67
  5156.4  170.09  5161.0  170.08  5320.3  172.10  5489.4  171.41  5671.4  177.37
  5751.1  183.24  5843.1  184.44  5888.0  187.12  6012.0  191.29  6212.6  192.56
#Mann=10,-1,0
  3507.7    0.12       0  3821.4    0.05       0  4755.4    0.12       0
  4992.4    0.05       0  4997.5    0.12       0  5156.4   0.013       0
  5161.0    0.12       0  5489.4    0.03       0  5888.0    0.05       0
  6012.0    0.03       0
Bank Sta=4992.4,4997.5
Exp/Cntr=0.3,0.1

Type RM Length L Ch R = 1,2371,328,328,328
BEGIN DESCRIPTION:
Mapping XS 7827efe9
END DESCRIPTION:
XS GIS Cut Line= 3
      2524135.30     13527948.85      2522749.84     13527771.77
      2521715.15     13527816.90
#Sta/Elev= 30
  3578.5  205.99  3624.2  205.20  3820.8  203.64  4012.3  199.95  4204.7  194.10
  4414.4  185.68  4536.5  181.24  4566.8  182.05  4593.4  180.69  4598.4  181.69
  4607.1  181.48  4673.1  178.16  4687.7  178.64  4738.2  176.07  4879.3  172.44
  4912.4  170.75  4949.9  164.75  4987.5  162.29  4987.9  161.79  4992.6  162.29
  5000.1  164.21  5010.1  168.34  5020.1  168.93  5260.3  170.15  5321.4  169.43
  5401.1  169.29  5499.6  169.14  5598.2  169.29  5860.9  172.74  6010.9  172.61
#Mann=9,-1,0
  3578.5   0.013       0  3624.2    0.05       0  4414.4    0.12       0
  4987.5    0.05       0  4992.6    0.12       0  5321.4   0.013       0
  5401.1    0.04       0  5499.6    0.05       0  5598.2    0.04       0
Bank Sta=4987.5,4992.6
Exp/Cntr=0.3,0.1

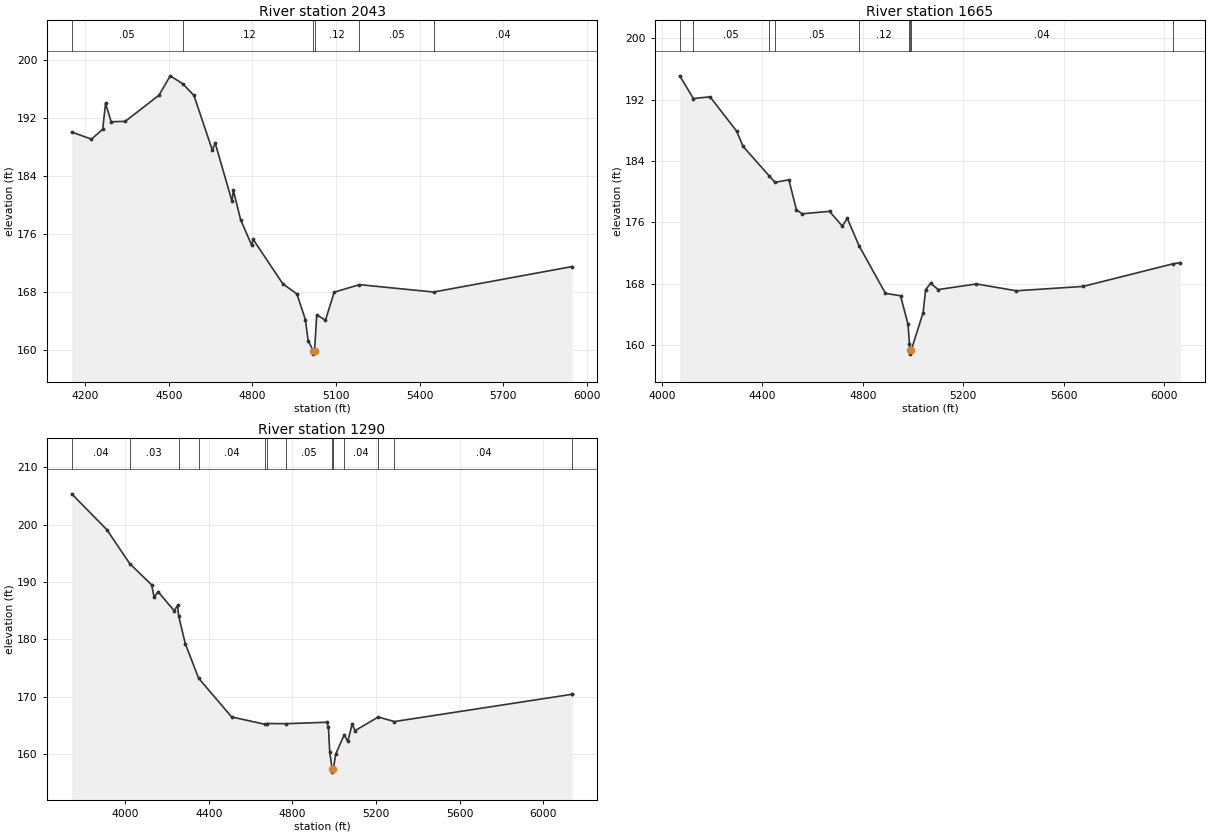
Type RM Length L Ch R = 1,2043,378,378,378
BEGIN DESCRIPTION:
Mapping XS 14b2f2ac
END DESCRIPTION:
XS GIS Cut Line= 3
      2523465.16     13527601.63      2522610.95     13527480.10
      2521715.12     13527743.99
#Sta/Elev= 30
  4151.6  190.09  4222.5  189.11  4262.9  190.47  4273.0  194.05  4293.2  191.51
  4343.7  191.56  4464.9  195.17  4505.3  197.84  4549.9  196.75  4590.1  195.15
  4655.9  187.64  4666.9  188.52  4726.8  180.57  4731.8  182.06  4757.8  178.00
  4797.6  174.49  4802.7  175.30  4909.3  169.16  4959.8  167.77  4990.1  164.24
  5000.2  161.33  5018.0  159.97  5018.4  159.47  5023.2  159.97  5031.0  164.89
  5062.3  164.14  5093.6  168.01  5184.4  169.05  5450.3  168.03  5948.3  171.55
#Mann=6,-1,0
  4151.6    0.05       0  4549.9    0.12       0  5018.0    0.05       0
  5023.2    0.12       0  5184.4    0.05       0  5450.3    0.04       0
Bank Sta=5018,5023.2
Exp/Cntr=0.3,0.1

Type RM Length L Ch R = 1,1665,375,375,375
BEGIN DESCRIPTION:
Mapping XS cc07eabe
END DESCRIPTION:
XS GIS Cut Line= 4
      2523444.28     13527264.82      2522642.20     13527139.82
      2522395.67     13527143.29      2521630.19     13527680.17
#Sta/Elev= 30
  4071.0  195.12  4125.4  192.16  4191.7  192.38  4297.6  187.90  4323.3  185.91
  4427.2  182.07  4450.2  181.23  4505.5  181.56  4535.8  177.63  4559.0  177.13
  4667.4  177.45  4718.0  175.53  4738.2  176.52  4785.7  172.91  4890.0  166.76
  4950.0  166.44  4980.0  162.72  4985.7  160.11  4987.4  159.33  4987.8  158.83
  4992.6  159.33  5040.0  164.24  5050.0  167.23  5070.0  168.07  5100.0  167.25
  5252.3  167.98  5411.1  167.09  5677.3  167.66  6034.0  170.60  6064.3  170.76
#Mann=9,-1,0
  4071.0    0.04       0  4125.4    0.05       0  4427.2    0.12       0
  4450.2    0.05       0  4785.7    0.12       0  4985.7    0.04       0
  4987.4    0.04       0  4992.6    0.04       0  6034.0   0.013       0
Bank Sta=4987.4,4992.6
Exp/Cntr=0.3,0.1

Type RM Length L Ch R = 1,1290,0,0,0
BEGIN DESCRIPTION:
Mapping XS e29de19d
END DESCRIPTION:
XS GIS Cut Line= 4
      2523617.91     13527115.52      2522520.67     13526737.04
      2522294.98     13526921.07      2521632.35     13527590.64
#Sta/Elev= 30
  3744.8  205.40  3913.4  199.11  4022.3  193.21  4126.6  189.52  4139.3  187.34
  4157.8  188.32  4234.5  184.99  4251.4  185.91  4256.0  184.10  4287.9  179.24
  4351.5  173.21  4509.5  166.44  4668.0  165.16  4680.7  165.29  4771.0  165.26
  4964.4  165.51  4972.2  164.76  4978.6  160.28  4990.4  157.30  4990.8  156.80
  4995.6  157.30  5007.3  159.95  5048.1  163.35  5064.8  162.15  5085.6  165.17
  5100.0  164.05  5210.7  166.43  5287.8  165.63  6138.3  170.40  6138.7  170.40
#Mann=13,-1,0
  3744.8    0.04       0  4022.3    0.03       0  4256.0    0.12       0
  4351.5    0.04       0  4668.0    0.05       0  4680.7    0.12       0
  4771.0    0.05       0  4990.4    0.05       0  4995.6    0.05       0
  5048.1    0.04       0  5210.7    0.05       0  5287.8    0.04       0
  6138.3   0.013       0
Bank Sta=4990.4,4995.6
Exp/Cntr=0.3,0.1

Chan Stop Cuts=-1