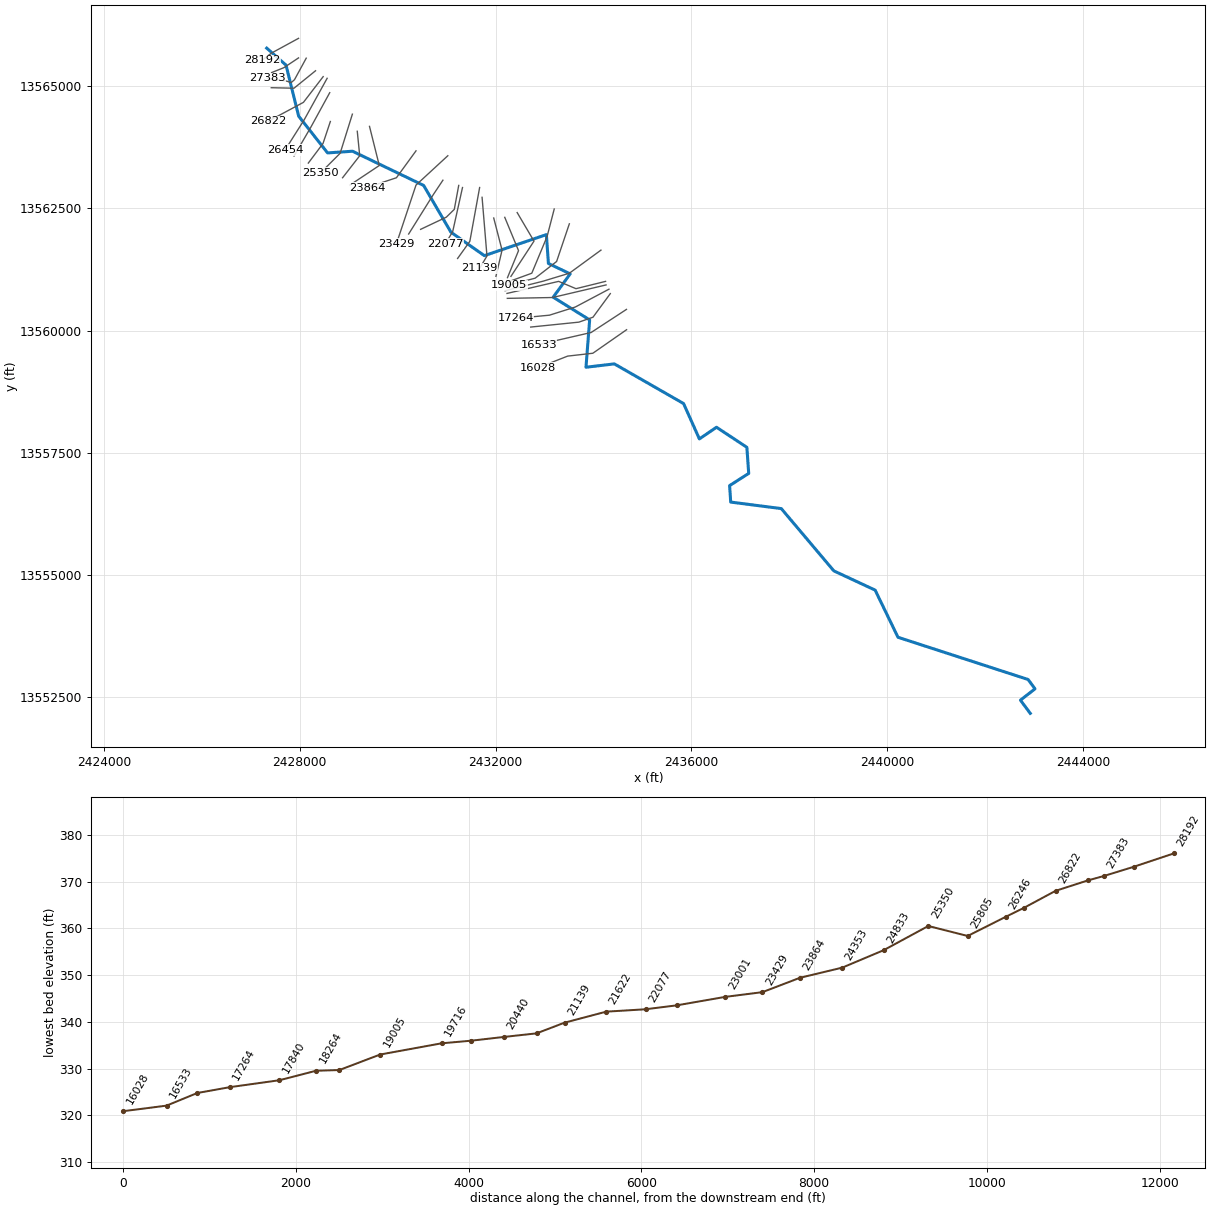
--- TRIB 6 TO YORKTOWN CREEK.prj (project) ---

Proj Title=TRIB 6 TO YORKTOWN CREEK Base Level Engineering
Current Plan=p01
Default Exp/Contr=0.3,0.1
English Units
Geom File=g01
Flow File=f01
Plan File=p01
Y Axis Title=Elevation
X Axis Title(PF)=Main Channel Distance
X Axis Title(XS)=Station
BEGIN DESCRIPTION:
TRIB 6 TO YORKTOWN CREEK
END DESCRIPTION:
DSS Export Rating Curves= 0
DSS Export Rating Curve Sorted= 0
DSS Export Volume Flow Curves= 0
DXF OffsetX= 0
DXF OffsetY= 0
DXF ScaleX= 1
DXF ScaleY= 10

--- TRIB 6 TO YORKTOWN CREEK.p01 (plan) ---

Plan Title=Multiple Run
Short Identifier=Multiple
Geom File=g01
Flow File=f01
Subcritical Flow
K Sum by GR= 0
Std Step Tol= 0.01
Critical Tol= 0.01
Num of Std Step Trials= 20
Max Error Tol= 0.3
Flow Tol Ratio= 0.001
Split Flow NTrial= 30
Split Flow Tol= 0.02
Split Flow Ratio= 0.02
Log Output Level= 0
Friction Slope Method= 1
Unsteady Friction Slope Method= 2
Unsteady Bridges Friction Slope Method= 1
Parabolic Critical Depth
Global Vel Dist=  1 , 1 , 1
Global Log Level= 0
CheckData=True
Encroach Param= -1, 0, 0, 0
BEGIN DESCRIPTION:
Multiple Run
END DESCRIPTION:

--- TRIB 6 TO YORKTOWN CREEK.f01 (steady flow) ---

Flow Title=Multiple
Number of Profiles=7
Profile Names=10-year,25-year,50-year,1pct_min,100-year,1pct_plu,500-year
River Rch & RM= TRIB 6 TO YORKTO,Reach-1,28192
     678    1108    1502     986    1968    3927    3348
River Rch & RM= TRIB 6 TO YORKTO,Reach-1,26454
     927    1539    2109    1399    2791    5568    4843
River Rch & RM= TRIB 6 TO YORKTO,Reach-1,23001
     989    1648    2263    1503    3000    5985    5226
River Rch & RM= TRIB 6 TO YORKTO,Reach-1,22438
    1304    2199    3042    2035    4060    8100    7168
River Rch & RM= TRIB 6 TO YORKTO,Reach-1,18533
    1401    2370    3286    2202    4393    8765    7785
River Rch & RM= TRIB 6 TO YORKTO,Reach-1,17840
    1550    2634    3662    2459    4907    9790    8738
River Rch & RM= TRIB 6 TO YORKTO,Reach-1,15819
    1641    2791    3884    2609    5206   10387    9278
River Rch & RM= TRIB 6 TO YORKTO,Reach-1,12827
    1763    3004    4186    2815    5617   11207   10032
River Rch & RM= TRIB 6 TO YORKTO,Reach-1,10902
    1885    3221    4494    3026    6037   12046   10809
River Rch & RM= TRIB 6 TO YORKTO,Reach-1,9095
    1908    3255    4537    3051    6087   12145   10871
River Rch & RM= TRIB 6 TO YORKTO,Reach-1,4432
    2012    3442    4807    3238    6461   12891   11579
River Rch & RM= TRIB 6 TO YORKTO,Reach-1,3811
    2110    3617    5058    3411    6806   13579   12226
Boundary for River Rch & Prof#=TRIB 6 TO YORKTO,Reach-1,1
Up Type=0
Dn Type=3
Dn Slope=0.005
Boundary for River Rch & Prof#=TRIB 6 TO YORKTO,Reach-1,2
Up Type=0
Dn Type=3
Dn Slope=0.005
Boundary for River Rch & Prof#=TRIB 6 TO YORKTO,Reach-1,3
Up Type=0
Dn Type=3
Dn Slope=0.005
Boundary for River Rch & Prof#=TRIB 6 TO YORKTO,Reach-1,4
Up Type=0
Dn Type=3
Dn Slope=0.005
Boundary for River Rch & Prof#=TRIB 6 TO YORKTO,Reach-1,5
Up Type=0
Dn Type=3
Dn Slope=0.005
Boundary for River Rch & Prof#=TRIB 6 TO YORKTO,Reach-1,6
Up Type=0
Dn Type=3
Dn Slope=0.005
Boundary for River Rch & Prof#=TRIB 6 TO YORKTO,Reach-1,7
Up Type=0
Dn Type=3
Dn Slope=0.005

--- TRIB 6 TO YORKTOWN CREEK.g01 (geometry) ---

Geom Title=Existing Conditions
Program Version=4.10

River Reach=TRIB 6 TO YORKTO,Reach-1
Reach XY= 30
        2427325.       13565775.      2427719.15     13565427.29
      2427978.07      13564383.3      2428568.55     13563632.74
       2429078.4     13563667.17      2430531.19     13562967.18
      2431088.62     13562011.78      2431771.58     13561532.79
      2433038.24      13561961.9      2433080.45     13561372.53
      2433524.77     13561159.79      2433177.84     13560683.01
      2433922.95     13560219.14      2433848.12     13559251.16
      2434427.45     13559319.55      2435842.05     13558508.51
      2436164.68     13557785.82      2436514.67     13558024.13
      2437135.06     13557614.39      2437172.93     13557080.85
      2436782.67     13556831.52      2436804.42     13556494.58
      2437838.22     13556361.38      2438911.76     13555088.11
      2439755.65     13554695.05       2440222.7     13553730.83
      2442881.06     13552867.52      2443021.99     13552676.43
      2442724.78     13552445.06        2442925.       13552175.

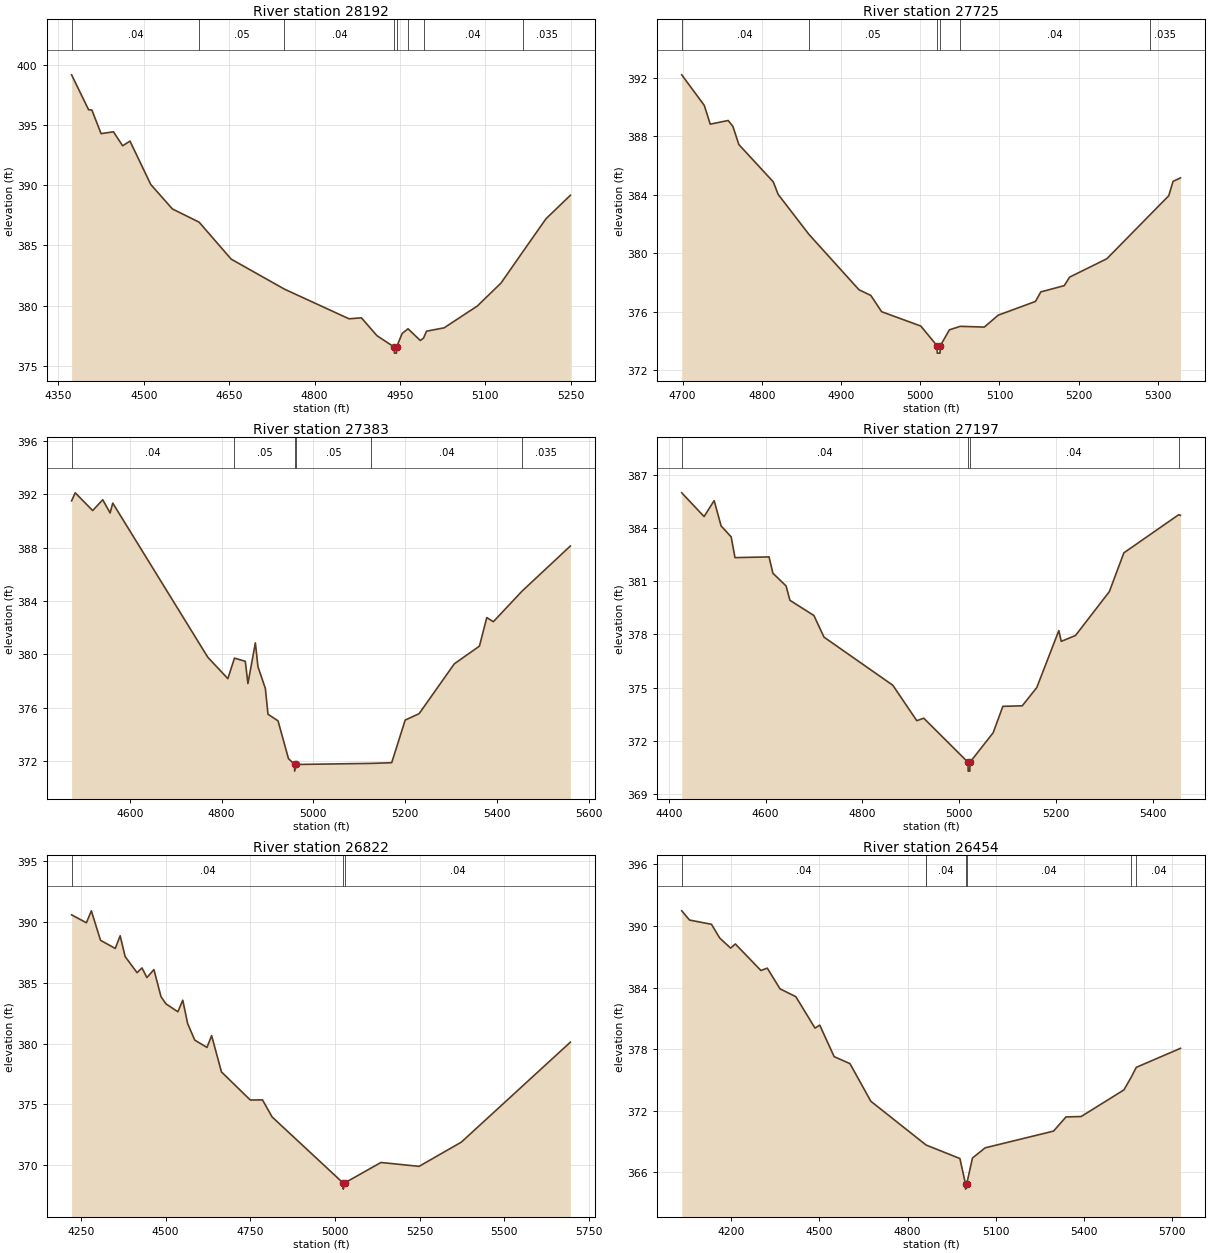
Type RM Length L Ch R = 1 ,28192   ,467,467,467
BEGIN DESCRIPTION:
TRIB 6 TO YORKTOWN CREEK 53.0
END DESCRIPTION:
XS GIS Cut Line= 3
      2427975.03     13565975.02        2427425.       13565675.
      2427225.03     13565525.02
#Sta/Elev= 30
  4373.1  399.16    4403  396.26  4408.7  396.24  4424.9  394.28  4446.7  394.43
  4462.8  393.27  4475.7  393.66  4512.2  390.06  4550.2  388.03  4597.2  386.93
  4653.6  383.86  4747.2  381.37  4860.6  378.91  4882.4  378.99  4909.9   377.5
  4940.2  376.56  4940.5  376.06    4944  376.06  4944.2  376.56  4954.1   377.7
  4964.4  378.08  4985.9  377.11  4991.6  377.31  4996.8  377.88  5027.8  378.16
  5086.1  379.97  5127.8  381.88  5166.2  384.48  5206.9  387.22  5249.6  389.16
#Mann= 8 ,-1 , 0
  4373.1     .04       0  4597.2     .05       0  4747.2     .04       0
  4940.2     .04       0  4944.2     .04       0  4964.4     .05       0
  4991.6     .04       0  5166.2    .035       0
Bank Sta=4940.2,4944.2
XS Rating Curve= 0 ,0
Exp/Cntr=0.3,0.1

Type RM Length L Ch R = 1 ,27725   ,342,342,342
BEGIN DESCRIPTION:
TRIB 6 TO YORKTOWN CREEK 52.0
END DESCRIPTION:
XS GIS Cut Line= 3
      2427974.97     13565574.98        2427675.       13565375.
      2427424.98     13565274.99
#Sta/Elev= 30
  4698.8  392.19  4727.3   390.1  4734.8  388.82  4757.4  389.07  4763.4  388.67
  4770.9  387.43  4814.4  384.88  4820.5  384.03  4859.3   381.3  4922.6  377.51
  4937.6  377.12  4951.2  376.01  5000.7  375.03  5021.3  373.68  5021.5  373.18
    5025  373.18  5025.3  373.68  5036.8  374.77  5050.5  375.01  5080.9  374.96
  5098.4  375.77  5145.5  376.71  5152.2  377.36  5181.8  377.79  5188.6  378.37
  5235.7  379.63  5289.6   382.6  5313.8  383.93  5319.2  384.91  5328.6  385.15
#Mann= 6 ,-1 , 0
  4698.8     .04       0  4859.3     .05       0  5021.3     .05       0
  5025.3     .05       0  5050.5     .04       0  5289.6    .035       0
Bank Sta=5021.3,5025.3
XS Rating Curve= 0 ,0
Exp/Cntr=0.3,0.1

Type RM Length L Ch R = 1 ,27383   ,186,186,186
BEGIN DESCRIPTION:
Mapping XS 8f75b7ed
END DESCRIPTION:
XS GIS Cut Line= 5
      2428132.22     13565569.83      2427892.63     13565129.71
      2427824.92     13565069.81      2427738.98     13565098.46
      2427338.94     13565155.61
#Sta/Elev= 30
  4473.5  391.51  4481.4  392.11  4519.4  390.78  4541.3  391.59  4557.4   390.6
  4563.1  391.34  4770.2  379.77  4813.8  378.17  4828.2  379.71  4851.8  379.47
  4857.5   377.8  4873.7  380.85  4879.4  379.06  4895.5  377.43  4901.2   375.5
  4923.1     375  4945.8  372.17    4959  371.73  4959.3  371.23    4963  371.73
  5124.9  371.81  5170.6  371.86    5200  375.06  5230.3  375.54    5307  379.28
  5361.7  380.61  5377.7  382.75    5392  382.44  5454.4  384.73  5559.7  388.12
#Mann= 6 ,-1 , 0
  4473.5     .04       0  4828.2     .05       0    4959     .05       0
    4963     .05       0  5124.9     .04       0  5454.4    .035       0
Bank Sta=4959,4963
XS Rating Curve= 0 ,0
Exp/Cntr=0.3,0.1

Type RM Length L Ch R = 1 ,27197   ,375,375,375
BEGIN DESCRIPTION:
Mapping XS e8704494
END DESCRIPTION:
XS GIS Cut Line= 3
      2428322.28     13565311.97      2427882.21     13564955.23
      2427418.03      13564965.6
#Sta/Elev= 30
  4426.5     386  4472.7  384.66  4493.5  385.56  4507.9  384.13  4528.7  383.51
  4536.6  382.34    4607  382.38  4614.9  381.46  4642.2  380.74  4650.1  379.93
  4699.7  379.07  4720.5  377.85  4862.8  375.13  4912.3  373.13  4926.7  373.27
  5018.2  370.78  5018.5  370.28    5022  370.28  5022.2  370.78  5070.2  372.45
  5090.2  373.94  5130.3  373.97  5160.3     375  5205.9  378.22  5210.9  377.61
  5240.3  377.94  5310.3  380.42  5340.3  382.61  5453.4  384.76  5457.3  384.73
#Mann= 4 ,-1 , 0
  4426.5     .04       0  5018.2     .04       0  5022.2     .04       0
  5453.4    .035       0
Bank Sta=5018.2,5022.2
XS Rating Curve= 0 ,0
Exp/Cntr=0.3,0.1

Type RM Length L Ch R = 1 ,26822   ,368,368,368
BEGIN DESCRIPTION:
Mapping XS d43310e0
END DESCRIPTION:
XS GIS Cut Line= 3
      2428478.56      13565192.2      2428074.92     13564666.17
      2427361.37     13564283.35
#Sta/Elev= 30
  4222.6  390.57  4266.3  389.92  4280.9   390.9    4308  388.48  4351.5  387.81
    4366  388.85  4380.6  387.15  4415.9  385.82  4430.4  386.21  4444.9  385.42
  4465.7  386.07  4486.6  383.85  4501.1  383.26  4536.4  382.61  4550.9  383.56
  4565.4  381.63  4586.3  380.28  4622.4  379.68  4636.1  380.65  4665.1  377.67
  4750.3  375.36  4786.3  375.37  4814.7  373.97  5024.5  368.54  5024.8  368.04
  5028.5  368.54  5136.1  370.23  5248.7  369.91  5373.5   371.9  5695.4  380.11
#Mann= 3 ,-1 , 0
  4222.6     .04       0  5024.5     .04       0  5028.5     .04       0
Bank Sta=5024.5,5028.5
XS Rating Curve= 0 ,0
Exp/Cntr=0.3,0.1

Type RM Length L Ch R = 1 ,26454   ,208,208,208
BEGIN DESCRIPTION:
Mapping XS 767aa7df
END DESCRIPTION:
XS GIS Cut Line= 3
      2428559.28     13565158.33      2428090.54      13564309.4
      2427699.95     13563692.26
#Sta/Elev= 30
  4030.4  391.48    4057  390.58  4131.8  390.17  4159.9  388.83  4197.1  387.85
  4213.2  388.25  4300.3  385.67    4322   385.9  4365.6  383.88  4419.4  383.12
  4484.7  380.06  4500.8  380.35    4550  377.28  4603.9   376.6  4674.9  372.94
  4861.4  368.72  4863.8  368.67  4978.6  367.36  4997.8  364.88    4998  364.38
  5001.8  364.88  5021.5  367.41  5064.5   368.4  5297.8  370.03  5340.2  371.41
  5391.9  371.45  5537.7  374.04  5563.3  375.32  5579.9  376.24  5730.5  378.09
#Mann= 7 ,-1 , 0
  4030.4     .04       0  4861.4    .013       0  4863.8     .04       0
  4997.8     .04       0  5001.8     .04       0  5563.3    .013       0
  5579.9     .04       0
Bank Sta=4997.8,5001.8
XS Rating Curve= 0 ,0
Exp/Cntr=0.3,0.1

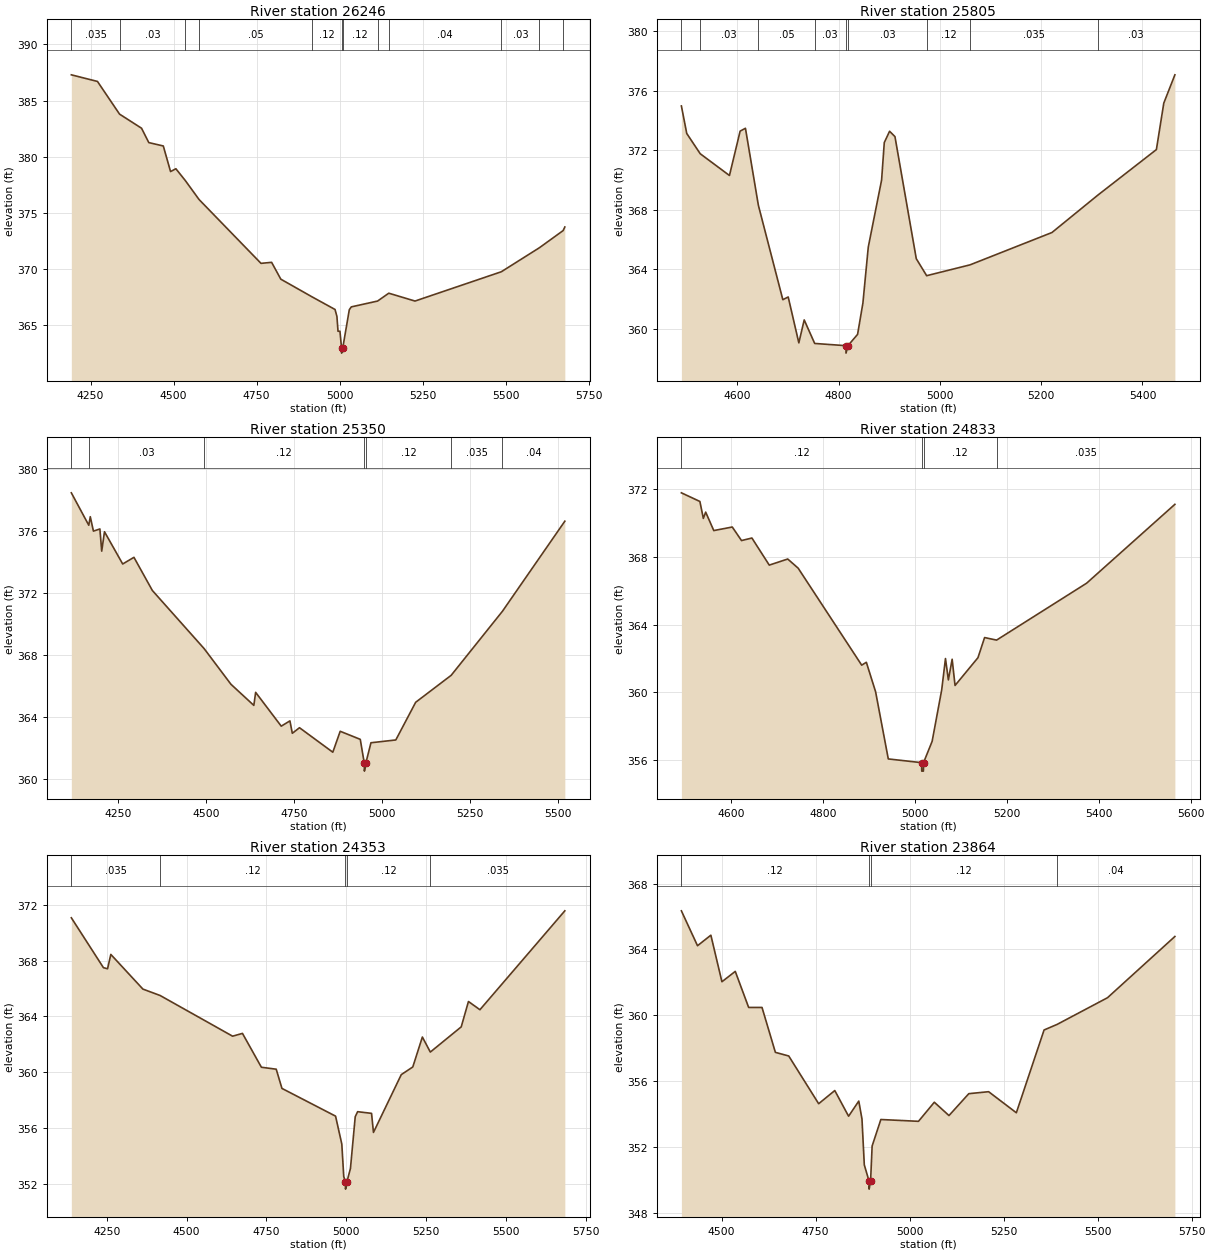
Type RM Length L Ch R = 1 ,26246   ,441,441,441
BEGIN DESCRIPTION:
Mapping XS 4cc490b3
END DESCRIPTION:
XS GIS Cut Line= 3
      2428612.23     13564864.05      2428226.83     13564159.22
      2427883.38     13563569.46
#Sta/Elev= 30
  4192.1  387.29  4270.8   386.7  4337.2  383.79  4403.5  382.53  4425.3  381.25
    4469  380.95  4490.8  378.67  4506.9  378.92  4535.2  377.87  4576.6  376.18
  4763.1  370.49  4795.1  370.58  4822.8  369.08  4916.5  367.51    4986  366.38
  4991.7  365.76    4995  364.44  5000.8  364.44  5005.5  362.99  5005.8  362.49
  5009.5  362.99    5029  366.36    5035  366.61  5114.1  367.13  5147.9  367.83
  5226.8  367.13  5486.6  369.74  5601.3  371.88  5672.8  373.41  5677.9  373.73
#Mann= 12 ,-1 , 0
  4192.1    .035       0  4337.2     .03       0  4535.2    .013       0
  4576.6     .05       0  4916.5     .12       0  5005.5     .05       0
  5009.5     .12       0  5114.1    .013       0  5147.9     .04       0
  5486.6     .03       0  5601.3     .04       0  5672.8    .013       0
Bank Sta=5005.5,5009.5
XS Rating Curve= 0 ,0
Exp/Cntr=0.3,0.1

Type RM Length L Ch R = 1 ,25805   ,455,455,455
BEGIN DESCRIPTION:
TRIB 6 TO YORKTOWN CREEK 48.0
END DESCRIPTION:
XS GIS Cut Line= 3
      2428625.01     13564275.03        2428475.       13563825.
      2428174.99     13563424.98
#Sta/Elev= 30
  4489.6  374.98  4500.2  373.13  4526.8  371.77  4584.5  370.31  4605.6  373.29
  4616.1  373.48  4641.6  368.31  4689.9  361.97  4700.5  362.15  4721.5  359.07
  4732.1  360.61  4752.8  359.03  4814.4  358.88  4814.7  358.38  4818.5  358.88
  4837.5  359.64    4848  361.74  4858.6   365.5  4884.9     370  4890.2  372.52
  4900.7  373.28  4911.3  372.92  4953.4  364.72  4973.9  363.58  5059.7  364.31
  5221.3  366.48  5311.5  368.98  5427.5  372.05  5442.1  375.17    5464  377.07
#Mann= 9 ,-1 , 0
  4489.6     .05       0  4526.8     .03       0  4641.6     .05       0
  4752.8     .03       0  4814.4     .05       0  4818.5     .03       0
  4973.9     .12       0  5059.7    .035       0  5311.5     .03       0
Bank Sta=4814.4,4818.5
XS Rating Curve= 0 ,0
Exp/Cntr=0.3,0.1

Type RM Length L Ch R = 1 ,25350   ,517,517,517
BEGIN DESCRIPTION:
TRIB 6 TO YORKTOWN CREEK 47.0
END DESCRIPTION:
XS GIS Cut Line= 3
      2429074.99     13564424.97        2428825.       13563625.
        2428425.       13563225.
#Sta/Elev= 30
  4116.5  378.47  4166.1  376.38  4170.4  376.93  4179.3     376  4197.7  376.14
  4202.9  374.71  4210.8  375.96  4262.6  373.88  4294.6  374.31    4347  372.17
  4494.3  368.42  4570.6  366.12  4635.6  364.76  4640.8   365.6  4713.6  363.42
  4738.3  363.76  4745.1  362.96  4765.5  363.32  4860.3  361.74  4881.3  363.09
  4938.4  362.57  4949.9  361.02  4950.2  360.52    4954  361.02  4968.8  362.35
  5039.5  362.53    5096  364.96    5197   366.7  5342.8  370.83  5520.3  376.64
#Mann= 7 ,-1 , 0
  4116.5    .035       0  4166.1     .03       0  4494.3     .12       0
  4949.9     .05       0    4954     .12       0    5197    .035       0
  5342.8     .04       0
Bank Sta=4949.9,4954
XS Rating Curve= 0 ,0
Exp/Cntr=0.3,0.1

Type RM Length L Ch R = 1 ,24833   ,480,480,480
BEGIN DESCRIPTION:
TRIB 6 TO YORKTOWN CREEK 46.0
END DESCRIPTION:
XS GIS Cut Line= 3
        2429175.       13564075.        2429225.       13563575.
      2428874.99     13563124.99
#Sta/Elev= 30
  4492.5  371.78  4532.7  371.27  4540.2  370.27  4545.3  370.64  4562.9  369.55
  4603.1  369.76  4623.2  368.96  4645.8  369.11  4683.5  367.51  4723.6  367.87
  4746.3  367.33  4884.4   361.6  4894.5  361.77  4914.6  360.03  4942.2  356.06
  5014.6  355.84  5014.9  355.34  5018.5  355.34  5018.8  355.84  5037.5   357.1
  5058.3  360.14  5066.5  361.99  5072.8  360.73    5081  361.95  5087.3   360.4
  5137.1  362.04  5151.5  363.23  5177.6  363.08  5373.2  366.44  5565.1   371.1
#Mann= 4 ,-1 , 0
  4492.5     .12       0  5014.6     .05       0  5018.8     .12       0
  5177.6    .035       0
Bank Sta=5014.6,5018.8
XS Rating Curve= 0 ,0
Exp/Cntr=0.3,0.1

Type RM Length L Ch R = 1 ,24353   ,489,489,489
BEGIN DESCRIPTION:
TRIB 6 TO YORKTOWN CREEK 45.0
END DESCRIPTION:
XS GIS Cut Line= 3
        2429425.       13564175.        2429625.       13563375.
      2429025.03     13562975.02
#Sta/Elev= 30
  4139.3  371.08  4239.8   367.5  4252.7  367.42    4263  368.45  4363.5  365.96
  4417.5   365.5  4644.4  362.58  4675.3  362.78  4734.6  360.35    4781  360.21
    4799  358.83  4966.9  356.84  4986.5  354.83  4992.5  352.51  4997.9   352.1
  4998.1   351.6  5002.1   352.1  5013.5  353.08  5028.5   356.8    5036  357.16
  5079.6  357.04  5085.6  355.67  5172.7  359.82  5208.8  360.37  5238.8  362.52
  5263.7  361.44  5360.5  363.25  5383.1  365.07  5419.1  364.48    5685  371.58
#Mann= 5 ,-1 , 0
  4139.3    .035       0  4417.5     .12       0  4997.9     .05       0
  5002.1     .12       0  5263.7    .035       0
Bank Sta=4997.9,5002.1
XS Rating Curve= 0 ,0
Exp/Cntr=0.3,0.1

Type RM Length L Ch R = 1 ,23864   ,435,435,435
BEGIN DESCRIPTION:
TRIB 6 TO YORKTOWN CREEK 44.0
END DESCRIPTION:
XS GIS Cut Line= 3
      2430374.98     13563674.98        2429975.       13563125.
        2429375.       13562925.
#Sta/Elev= 30
  4392.9  366.34  4435.8  364.22  4471.3  364.86  4500.7  362.03  4536.2  362.66
  4571.8  360.47  4607.3  360.47  4642.9  357.74  4678.4  357.52    4758  354.62
  4800.9  355.42  4837.6  353.86  4864.7  354.78  4873.2  353.69  4879.4   350.9
  4891.9  349.93  4892.2  349.43  4896.1  349.93  4900.2  352.05  4923.4  353.66
  5023.5  353.55  5065.6  354.71  5104.6   353.9  5157.3  355.23    5210  355.35
  5283.8  354.07  5357.5   359.1  5392.3  359.44  5526.2  361.06  5705.4  364.78
#Mann= 4 ,-1 , 0
  4392.9     .12       0  4891.9     .05       0  4896.1     .12       0
  5392.3     .04       0
Bank Sta=4891.9,4896.1
XS Rating Curve= 0 ,0
Exp/Cntr=0.3,0.1

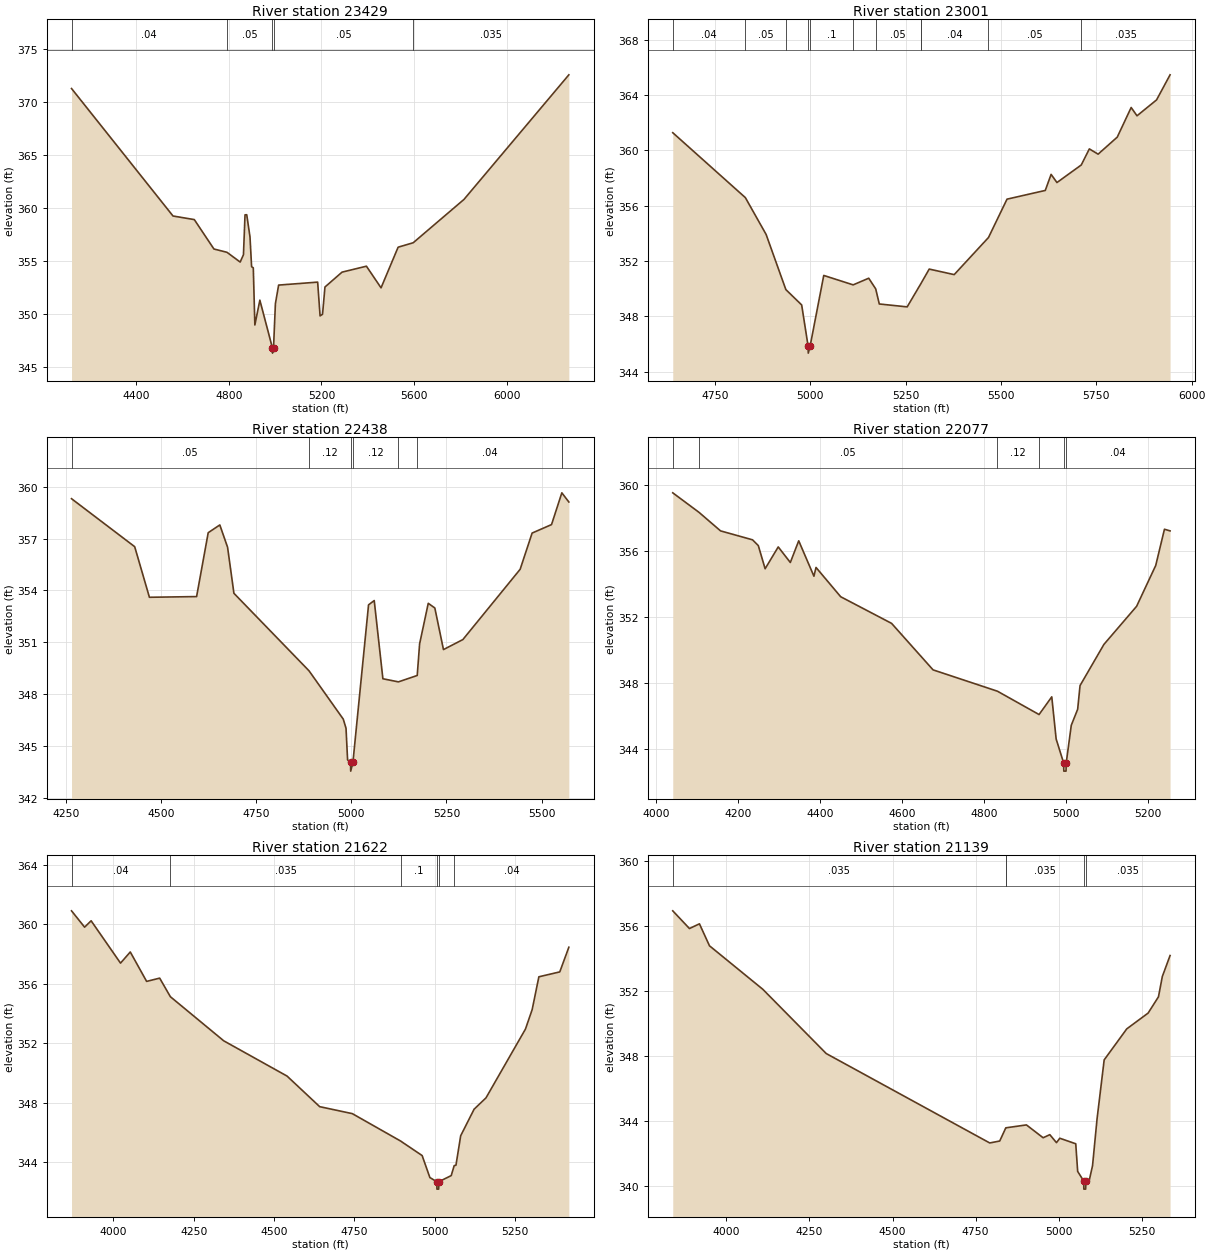
Type RM Length L Ch R = 1 ,23429   ,428,428,428
BEGIN DESCRIPTION:
TRIB 6 TO YORKTOWN CREEK 43.0
END DESCRIPTION:
XS GIS Cut Line= 3
      2431024.99     13563574.99        2430375.       13562975.
        2429975.     13561774.99
#Sta/Elev= 30
  4119.8  371.28  4558.4  359.27  4650.5  358.93  4735.3  356.16  4791.6  355.85
  4848.7  354.93  4862.9  355.62  4869.7  359.38  4877.1  359.39  4891.2  357.29
  4898.1  354.49  4905.4  354.39  4912.2     349  4933.8  351.34    4988  346.85
  4988.4  346.35  4992.9  346.85    5001  351.01  5014.9  352.76  5183.6  353.04
  5194.1  349.86  5204.7  350.01  5215.2  352.58    5289  353.98  5394.4  354.54
  5457.6   352.5  5531.4  356.33  5596.6  356.75    5816  360.83  6269.3  372.57
#Mann= 5 ,-1 , 0
  4119.8     .04       0  4791.6     .05       0    4988     .05       0
  4992.9     .05       0  5596.6    .035       0
Bank Sta=4988,4992.9
XS Rating Curve= 0 ,0
Exp/Cntr=0.3,0.1

Type RM Length L Ch R = 1 ,23001   ,563,563,563
BEGIN DESCRIPTION:
TRIB 6 TO YORKTOWN CREEK 42.0
END DESCRIPTION:
XS GIS Cut Line= 3
      2430924.98     13563074.97        2430725.       13562775.
      2430225.01     13561975.01
#Sta/Elev= 30
  4639.5  361.27  4829.9  356.58  4884.3  353.92    4936  349.94  4977.5  348.83
  4994.4  345.85  4994.8  345.35  4999.6  345.85  5035.4  350.96  5112.5  350.28
  5153.3  350.76  5171.6  349.99    5181   348.9  5254.1  348.69  5289.9  350.36
  5311.9  351.42  5377.4  351.02  5467.3   353.7  5515.9  356.47  5616.2   357.1
  5631.5  358.26  5646.8  357.67  5710.6  358.94  5731.7   360.1  5754.7  359.72
  5804.9  360.95  5841.4  363.09  5856.7  362.49    5908  363.64  5943.4  365.45
#Mann= 11 ,-1 , 0
  4639.5     .04       0  4829.9     .05       0    4936      .1       0
  4994.4     .05       0  4999.6      .1       0  5112.5     .12       0
  5171.6     .05       0  5289.9     .12       0  5289.9     .04       0
  5467.3     .05       0  5710.6    .035       0
Bank Sta=4994.4,4999.6
XS Rating Curve= 0 ,0
Exp/Cntr=0.3,0.1

Type RM Length L Ch R = 1 ,22438   ,361,361,361
BEGIN DESCRIPTION:
Mapping XS 8c3d65b7
END DESCRIPTION:
XS GIS Cut Line= 4
      2431247.67     13562968.28      2431157.38     13562478.67
      2430994.19     13562318.94      2430469.31     13562070.32
#Sta/Elev= 30
  4264.8  359.31  4430.8  356.53  4469.5   353.6  4593.5  353.64    4624  357.34
  4654.5  357.79  4674.9   356.5  4691.6  353.83    4889  349.34    4979  346.54
  4986.2  346.01  4990.3  344.18    4998  344.03  4998.5  343.53  5004.3  344.03
  5045.4  353.16  5060.3  353.41  5083.1  348.88  5123.9   348.7  5173.3  349.07
  5179.6   350.9  5202.3  353.25  5219.6  352.98  5242.3  350.57  5293.3  351.15
  5443.8  355.22  5475.3  357.32  5526.3  357.81  5553.4  359.65  5571.8  359.12
#Mann= 7 ,-1 , 0
  4264.8     .05       0    4889     .12       0    4998     .05       0
  5004.3     .12       0  5123.9      .1       0  5173.3     .04       0
  5553.4     .05       0
Bank Sta=4998,5004.3
XS Rating Curve= 0 ,0
Exp/Cntr=0.3,0.1

Type RM Length L Ch R = 1 ,22077   ,455,455,455
BEGIN DESCRIPTION:
TRIB 6 TO YORKTOWN CREEK 40.0
END DESCRIPTION:
XS GIS Cut Line= 3
      2431325.01     13562925.05        2431125.       13562025.
      2430974.97     13561774.96
#Sta/Elev= 30
  4041.2  359.51  4105.3  358.33  4157.8  357.21  4235.9  356.67    4250  356.32
  4266.6  354.92  4298.6  356.24  4328.1   355.3  4348.6  356.61  4385.7  354.47
  4390.8     355    4451  353.23  4575.2  351.62  4676.4  348.81  4833.5  347.52
  4935.1  346.11  4966.1  347.18  4976.8  344.63    4995  343.19  4995.5  342.69
  5000.9  342.69  5001.4  343.19  5013.7  345.46  5029.3  346.43  5035.1  347.86
  5093.4  350.35  5173.1  352.65  5219.8  355.12  5241.1  357.31  5254.8  357.21
#Mann= 6 ,-1 , 0
  4041.2     .04       0  4105.3     .05       0  4833.5     .12       0
  4935.1     .04       0    4995     .04       0  5001.4     .04       0
Bank Sta=4995,5001.4
XS Rating Curve= 0 ,0
Exp/Cntr=0.3,0.1

Type RM Length L Ch R = 1 ,21622   ,483,483,483
BEGIN DESCRIPTION:
TRIB 6 TO YORKTOWN CREEK 39.0
END DESCRIPTION:
XS GIS Cut Line= 3
        2431675.       13562925.        2431475.       13561825.
      2431225.03     13561475.04
#Sta/Elev= 30
  3869.9  360.91  3910.6  359.81  3930.9  360.24  4022.4  357.39  4052.8  358.14
  4103.7  356.16  4144.3  356.38  4177.6  355.13  4343.8  352.16  4540.7  349.79
  4642.4  347.73    4744  347.26    4894  345.42  4961.3  344.44  4985.4  342.96
  5006.9  342.68  5007.4  342.18  5012.8  342.18  5013.3  342.68  5051.8  343.09
  5061.1  343.76  5066.6  343.79  5081.3  345.77  5123.1  347.56    5160  348.32
  5282.9  352.95  5303.8  354.26  5324.7  356.47  5389.8   356.8    5418  358.46
#Mann= 6 ,-1 , 0
  3869.9     .04       0  4177.6    .035       0    4894      .1       0
  5006.9     .05       0  5013.3      .1       0  5061.1     .04       0
Bank Sta=5006.9,5013.3
XS Rating Curve= 0 ,0
Exp/Cntr=0.3,0.1

Type RM Length L Ch R = 1 ,21139   ,324,324,324
BEGIN DESCRIPTION:
TRIB 6 TO YORKTOWN CREEK 38.0
END DESCRIPTION:
XS GIS Cut Line= 3
        2431725.     13562725.04        2431825.       13561525.
      2431675.02     13561275.04
#Sta/Elev= 30
  3839.1  356.94  3889.3  355.85  3919.4  356.14  3949.5  354.79  4110.1  352.11
  4300.7  348.16  4792.4  342.66  4822.5  342.78  4840.5  343.58  4840.7  343.59
  4902.8  343.77    4953  342.98  4973.1  343.17  4993.1  342.68  5003.2  342.95
  5051.1  342.61  5056.9  340.91    5075  340.32  5075.5  339.82    5081  339.82
  5081.5  340.32  5091.9  340.38  5101.6  341.26  5115.2  344.14  5136.6  347.77
  5204.6  349.68  5268.8  350.65  5299.9  351.65  5311.5   352.9  5334.8  354.19
#Mann= 5 ,-1 , 0
  3839.1    .035       0  4840.5      .1       0  4840.7    .035       0
    5075    .035       0  5081.5    .035       0
Bank Sta=5075,5081.5
XS Rating Curve= 0 ,0
Exp/Cntr=0.3,0.1

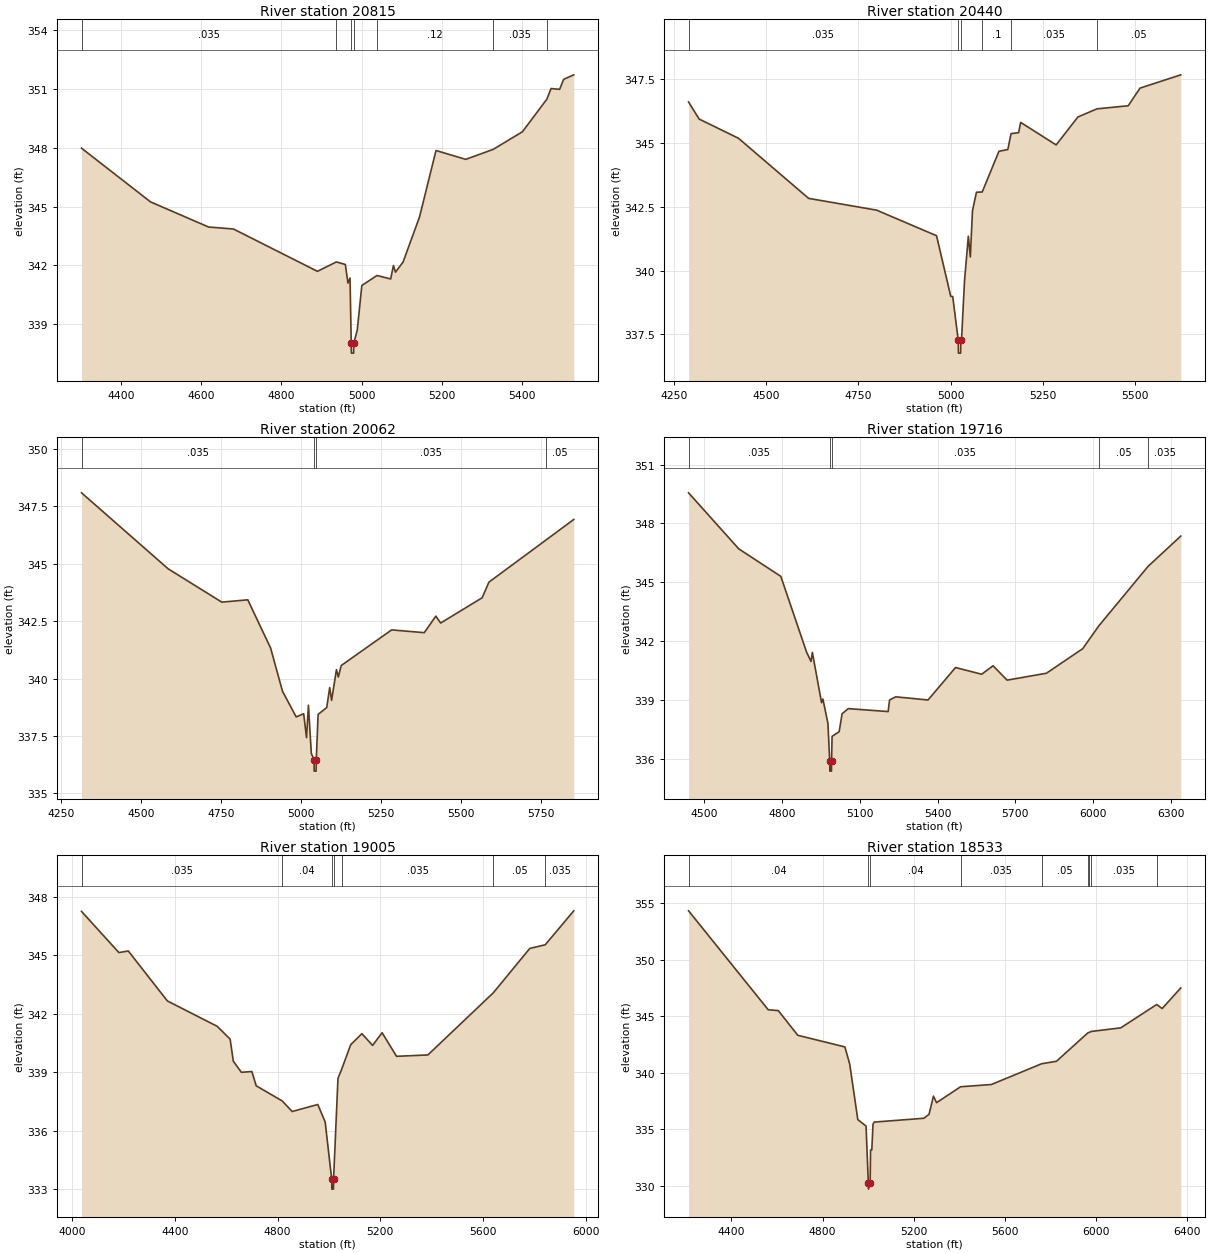
Type RM Length L Ch R = 1 ,20815   ,375,375,375
BEGIN DESCRIPTION:
Mapping XS 6e7421f7
END DESCRIPTION:
XS GIS Cut Line= 3
      2431962.94     13562301.58      2432133.08     13561645.33
      2432008.07     13561110.59
#Sta/Elev= 30
  4301.6  347.98  4473.7  345.24  4618.3  343.96  4680.3  343.86  4889.8   341.7
  4936.8  342.18  4959.2  342.05  4965.8   341.1    4971  341.36  4973.9  338.03
  4974.4  337.53  4979.9  337.53  4980.4  338.03    4989  338.71  5000.4  340.98
  5038.3  341.49  5072.3  341.31  5079.2     342  5084.3  341.66  5103.1  342.17
  5144.2  344.47  5185.3  347.86  5259.5  347.41  5328.1  347.92  5400.9  348.82
  5461.7  350.48    5472  351.02  5493.4  350.98  5503.6  351.49  5528.7  351.72
#Mann= 7 ,-1 , 0
  4301.6    .035       0  4936.8      .1       0  4973.9     .05       0
  4980.4      .1       0  5038.3     .12       0  5328.1    .035       0
  5461.7    .013       0
Bank Sta=4973.9,4980.4
XS Rating Curve= 0 ,0
Exp/Cntr=0.3,0.1

Type RM Length L Ch R = 1 ,20440   ,378,378,378
BEGIN DESCRIPTION:
Mapping XS 181278b9
END DESCRIPTION:
XS GIS Cut Line= 3
      2432188.63     13562315.47      2432469.88     13561634.92
       2432244.2     13561082.85
#Sta/Elev= 30
  4290.1  346.59  4318.8  345.92  4425.2  345.17  4615.2  342.82  4799.2  342.36
  4961.5  341.36    5000  338.99  5005.4  338.98  5020.3  337.27  5020.8  336.77
  5026.7  336.77  5027.2  337.27  5029.1  337.27  5037.2  339.58  5047.6  341.34
    5053  340.53  5058.8  342.33  5069.6  343.06  5085.2  343.07  5130.5  344.66
  5154.5  344.73  5163.3  345.35  5183.9  345.39  5189.3  345.79  5285.4  344.91
  5344.2     346  5395.8  346.32  5480.5  346.44  5512.5  347.13  5622.9  347.65
#Mann= 6 ,-1 , 0
  4290.1    .035       0  5020.3    .035       0  5027.2    .035       0
  5085.2      .1       0  5163.3    .035       0  5395.8     .05       0
Bank Sta=5020.3,5027.2
XS Rating Curve= 0 ,0
Exp/Cntr=0.3,0.1

Type RM Length L Ch R = 1 ,20062   ,346,346,346
BEGIN DESCRIPTION:
Mapping XS a848add2
END DESCRIPTION:
XS GIS Cut Line= 3
      2432442.13     13562412.65      2432785.86     13561829.36
      2432314.59     13561108.59
#Sta/Elev= 30
  4314.8  348.09  4585.6  344.78  4753.1  343.33  4834.4  343.43  4905.7  341.33
  4942.8  339.45  4985.7  338.33    5009  338.47  5017.9  337.43  5023.9  338.84
  5032.9  336.74  5041.4  336.47  5041.9  335.97  5047.9  335.97  5048.4  336.47
  5054.1  338.44  5081.1  338.74  5090.3  339.61  5096.3  339.05  5111.4  340.39
  5117.3  340.07  5126.5  340.57  5283.8  342.12  5385.8     342    5422  342.72
  5437.1  342.42  5566.8  343.52  5587.9   344.2  5767.7  346.05    5853  346.93
#Mann= 4 ,-1 , 0
  4314.8    .035       0  5041.4    .035       0  5048.4    .035       0
  5767.7     .05       0
Bank Sta=5041.4,5048.4
XS Rating Curve= 0 ,0
Exp/Cntr=0.3,0.1

Type RM Length L Ch R = 1 ,19716   ,711,711,711
BEGIN DESCRIPTION:
Mapping XS 08069c89
END DESCRIPTION:
XS GIS Cut Line= 4
      2433199.05      13562485.6      2433053.22     13561923.11
      2432740.72     13561173.11      2432265.75     13560999.77
#Sta/Elev= 30
    4439  349.56  4632.6  346.71  4794.9  345.31  4894.2  341.46  4911.5  340.98
  4916.7  341.44  4952.1  338.88  4957.3  339.07  4976.8  337.82  4983.6   335.9
  4984.1   335.4  4990.2   335.4  4990.7   335.9  4992.7  337.17  5020.1  337.41
  5031.4  338.32  5055.2  338.58    5209  338.43  5214.5  339.02  5238.3  339.18
  5362.9  339.02    5469  340.67  5569.8  340.33  5613.9  340.76    5668  340.03
  5819.7  340.38  5959.7  341.63  6022.4   342.8    6212  345.82  6338.2  347.36
#Mann= 5 ,-1 , 0
    4439    .035       0  4983.6    .035       0  4990.7    .035       0
  6022.4     .05       0    6212    .035       0
Bank Sta=4983.6,4990.7
XS Rating Curve= 0 ,0
Exp/Cntr=0.3,0.1

Type RM Length L Ch R = 1 ,19005   ,472,472,472
BEGIN DESCRIPTION:
Mapping XS 3865fb60
END DESCRIPTION:
XS GIS Cut Line= 4
      2433508.06     13562183.49      2433247.66     13561412.69
      2432810.16     13561072.42      2432279.43     13560930.19
#Sta/Elev= 30
    4036  347.24  4181.5  345.13  4218.3  345.21  4370.3  342.65  4564.3  341.35
  4614.9  340.69  4627.2  339.56  4658.6  338.99  4699.4  339.03  4716.3   338.3
  4817.8  337.52  4856.6  336.98  4956.2  337.34  4985.1  336.44  5010.5   333.5
    5011     333  5017.2     333  5017.7   333.5  5034.9  338.68  5049.1  339.14
  5084.7  340.41  5128.1  340.97  5169.7  340.37  5206.8  341.02  5262.9  339.81
    5385  339.88  5640.2  343.07  5781.9  345.34  5842.3  345.53  5953.3  347.27
#Mann= 7 ,-1 , 0
    4036    .035       0  4817.8     .04       0  5010.5     .04       0
  5017.7     .04       0  5049.1    .035       0  5640.2     .05       0
  5842.3    .035       0
Bank Sta=5010.5,5017.7
XS Rating Curve= 0 ,0
Exp/Cntr=0.3,0.1

Type RM Length L Ch R = 1 ,18533   ,269,269,269
BEGIN DESCRIPTION:
Mapping XS ee404435
END DESCRIPTION:
XS GIS Cut Line= 4
      2434153.94     13561645.35      2433508.08     13561173.11
      2432969.88     13561009.92      2432195.61     13560815.48
#Sta/Elev= 30
    4212  354.34  4561.8  345.57  4605.8   345.5  4691.5  343.31  4898.2  342.28
  4919.4  340.76  4954.9  335.84  4991.1  335.27  5001.2  330.18  5001.7  329.68
    5009  330.18  5010.9  333.15  5016.3  333.15  5021.7  335.44  5026.9  335.62
  5245.2  335.96  5267.7  336.31    5287  337.92  5300.6  337.34    5406  338.75
  5541.4  338.95  5761.9  340.79    5827  341.01  5965.6  343.54  5971.6  343.57
  5979.2  343.65  6109.2  343.97  6267.1  346.04  6290.9  345.68  6372.8  347.51
#Mann= 9 ,-1 , 0
    4212     .04       0  5001.2     .04       0    5009     .04       0
    5406    .035       0  5761.9     .05       0  5965.6    .035       0
  5971.6     .05       0  5979.2    .035       0  6267.1     .04       0
Bank Sta=5001.2,5009
XS Rating Curve= 0 ,0
Exp/Cntr=0.3,0.1

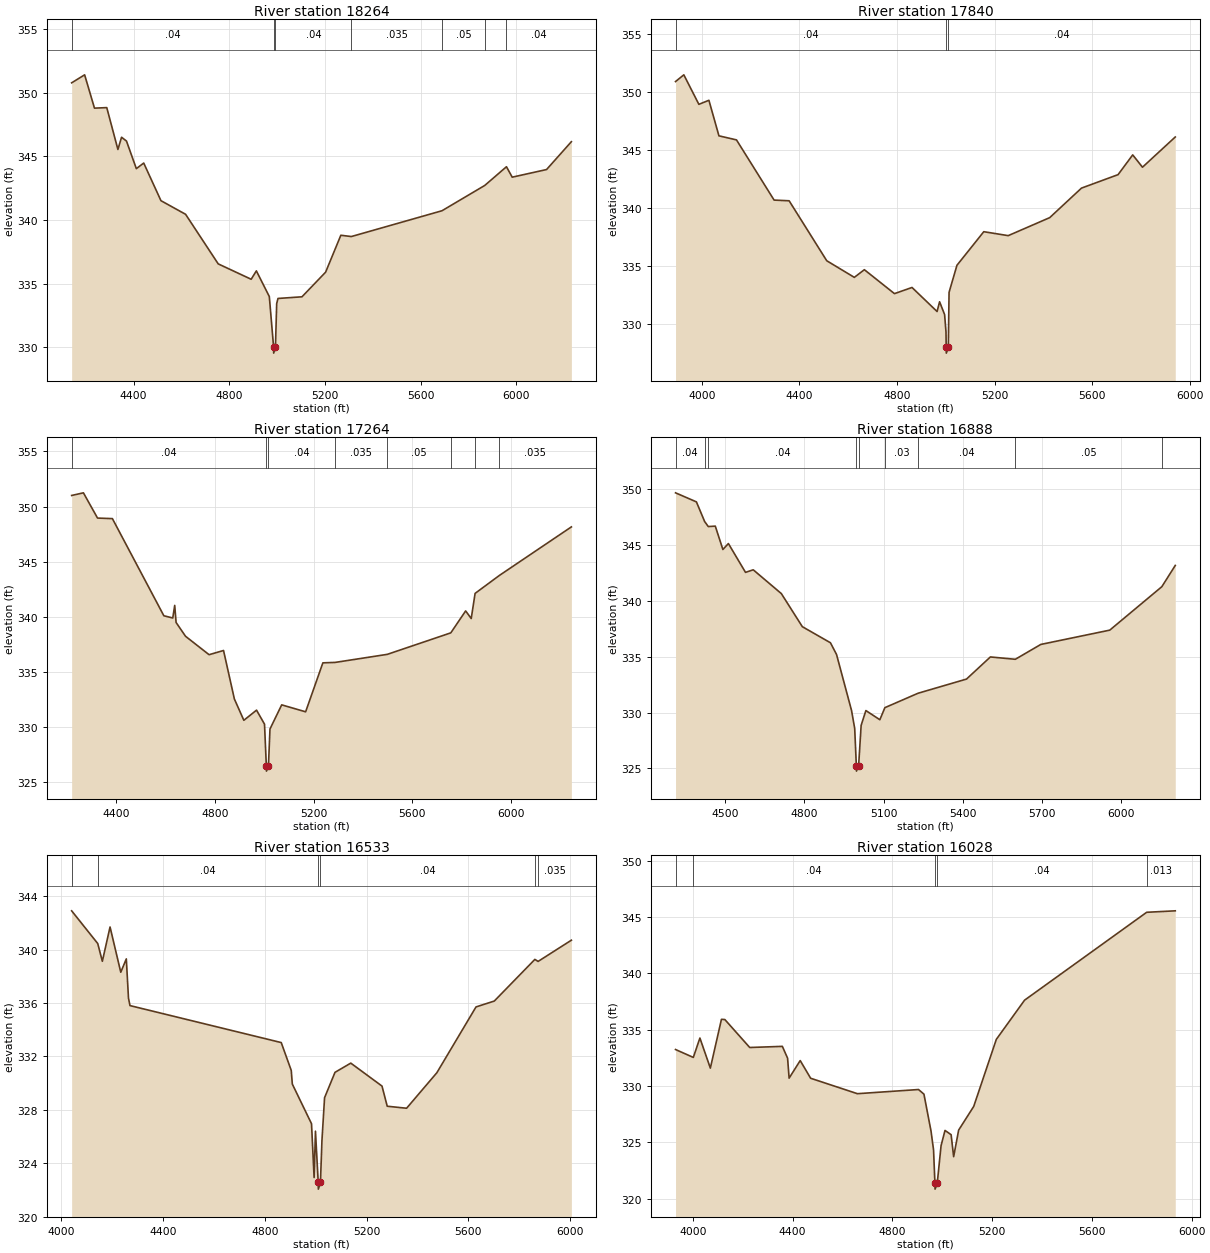
Type RM Length L Ch R = 1 ,18264   ,424,424,424
BEGIN DESCRIPTION:
Mapping XS a8f4ccbe
END DESCRIPTION:
XS GIS Cut Line= 4
      2434247.69     13561006.45       2433643.5     13560857.14
      2433289.33     13561006.44      2432233.96     13560759.96
#Sta/Elev= 30
  4140.5  350.79  4194.8  351.42    4236   348.8  4287.4  348.84    4334  345.55
  4349.3  346.51  4369.9  346.21  4411.1  344.04    4442  344.48  4514.1  341.52
  4617.1  340.45  4753.6  336.55  4891.5  335.34  4913.2     336  4967.4  333.98
  4985.2  330.03  4985.7  329.53  4993.1  330.03  4998.2  333.42  5003.7  333.83
    5104  333.96    5203   335.9  5266.6   338.8  5310.6   338.7  5689.9  340.73
  5868.7  342.72  5959.4  344.19  5983.5  343.37  6127.2  343.97    6231  346.16
#Mann= 7 ,-1 , 0
  4140.5     .04       0  4985.2     .04       0  4993.1     .04       0
  5310.6    .035       0  5689.9     .05       0  5868.7    .035       0
  5959.4     .04       0
Bank Sta=4985.2,4993.1
XS Rating Curve= 0 ,0
Exp/Cntr=0.3,0.1

Type RM Length L Ch R = 1 ,17840   ,576,576,576
BEGIN DESCRIPTION:
Mapping XS 3cf6f0a6
END DESCRIPTION:
XS GIS Cut Line= 3
      2434258.11     13560933.53      2433164.33     13560676.58
      2432240.75     13560659.22
#Sta/Elev= 30
  3892.4  350.87  3926.4  351.45    3988  348.91  4029.1  349.26  4070.2   346.2
  4142.1  345.85  4296.2  340.67  4357.8  340.61  4511.9  335.45  4624.9  334.02
    4666  334.68  4789.3  332.62  4861.2  333.15  4963.9  331.08  4974.2  331.92
  4994.7  330.82  5000.4  329.34  5001.3     328  5001.8   327.5  5009.9     328
    5013  332.73  5045.3  335.06  5155.3  337.95  5255.3  337.61  5425.4  339.16
  5555.4   341.7  5705.4  342.86  5765.4  344.56  5805.4   343.5  5939.7   346.1
#Mann= 3 ,-1 , 0
  3892.4     .04       0  5001.3     .04       0  5009.9     .04       0
Bank Sta=5001.3,5009.9
XS Rating Curve= 0 ,0
Exp/Cntr=0.3,0.1

Type RM Length L Ch R = 1 ,17264   ,376,376,376
BEGIN DESCRIPTION:
Mapping XS 3ea76f8d
END DESCRIPTION:
XS GIS Cut Line= 4
      2434317.14     13560846.74      2433629.61     13560482.14
      2433101.83     13560315.47      2432410.87      13560249.5
#Sta/Elev= 30
  4219.4  351.01  4267.1  351.25  4324.3  348.96  4384.6  348.91  4593.2   340.1
  4629.3   339.9  4637.2  341.04  4642.8  339.49  4681.1  338.24  4776.5  336.57
  4835.1  336.95  4879.1  332.55  4917.4  330.62  4968.9  331.54  5001.2  330.27
  5008.6  326.51  5009.1  326.01  5017.2  326.51  5023.4  329.83  5070.9  332.02
  5167.9  331.39  5237.8  335.83  5287.8  335.87  5498.9   336.6  5756.4  338.55
  5816.6  340.54  5839.2  339.85  5854.9  342.13  5953.5  343.76  6245.2  348.16
#Mann= 8 ,-1 , 0
  4219.4     .04       0  5008.6     .04       0  5017.2     .04       0
  5287.8    .035       0  5498.9     .05       0  5756.4    .035       0
  5854.9     .05       0  5953.5    .035       0
Bank Sta=5008.6,5017.2
XS Rating Curve= 0 ,0
Exp/Cntr=0.3,0.1

Type RM Length L Ch R = 1 ,16888   ,355,355,355
BEGIN DESCRIPTION:
Mapping XS 91d19f87
END DESCRIPTION:
XS GIS Cut Line= 4
      2434344.86      13560756.4      2433990.72     13560273.81
      2433702.52     13560173.11      2432718.21      13560072.6
#Sta/Elev= 30
  4311.9  349.67    4391  348.86  4422.2   347.1    4436  346.65  4462.5  346.69
  4491.3   344.6  4512.2  345.13    4577  342.55  4606.3  342.78  4712.8  340.65
  4792.3  337.69  4898.8  336.25  4921.9   335.2  4978.7  330.19  4990.7  328.58
  4996.9  325.26  4997.4  324.76  5005.6  325.26  5015.1  328.86  5033.1  330.18
    5086  329.36    5105  330.44  5230.6  331.73  5414.3     333  5504.8  334.98
  5599.2  334.77  5695.8   336.1  5957.1  337.38  6154.4  341.27  6205.2  343.17
#Mann= 9 ,-1 , 0
  4311.9     .04       0  4422.2    .013       0    4436     .04       0
  4996.9     .04       0  5005.6     .04       0    5105     .03       0
  5230.6     .04       0  5599.2     .05       0  6154.4    .035       0
Bank Sta=4996.9,5005.6
XS Rating Curve= 0 ,0
Exp/Cntr=0.3,0.1

Type RM Length L Ch R = 1 ,16533   ,505,505,505
BEGIN DESCRIPTION:
Mapping XS 22a8fa14
END DESCRIPTION:
XS GIS Cut Line= 3
      2434674.77     13560433.54      2433952.52     13559961.31
       2432879.8     13559714.82
#Sta/Elev= 30
  4041.2  342.91  4143.7  340.46  4161.8  339.13  4192.1   341.7  4234.2  338.31
    4256  339.31  4264.5  336.37  4270.4  335.81  4864.7  333.04  4904.1  330.95
  4908.3  329.93  4983.7  326.96  4993.9  322.93  4999.2   326.4  5010.1  322.56
  5010.6  322.06  5018.8  322.56  5024.7   325.7    5035  328.91    5076  330.81
    5138   331.5  5260.7  329.78  5281.2  328.27  5357.3  328.12  5476.2  330.78
  5630.1  335.71  5701.9  336.15  5861.3  339.27  5874.1  339.12  6004.8  340.71
#Mann= 6 ,-1 , 0
  4041.2    .013       0  4143.7     .04       0  5010.1     .04       0
  5018.8     .04       0  5861.3     .05       0  5874.1    .035       0
Bank Sta=5010.1,5018.8
XS Rating Curve= 0 ,0
Exp/Cntr=0.3,0.1

Type RM Length L Ch R = 1 ,16028   ,209,209,209
BEGIN DESCRIPTION:
Mapping XS 51d559a9
END DESCRIPTION:
XS GIS Cut Line= 4
       2434677.2     13560017.93      2433988.14     13559537.24
      2433473.36     13559478.67      2432872.66     13559242.55
#Sta/Elev= 30
  3930.6  333.25  4001.9  332.55  4028.3  334.27  4070.2   331.6  4114.7  335.93
  4128.4  335.91  4228.1  333.43  4358.9  333.53  4379.9  332.48    4386  330.71
  4430.5  332.27  4472.3   330.7  4659.9  329.33  4904.8   329.7  4926.6  329.29
  4955.1     326  4965.1  324.35  4970.7  321.36  4971.2  320.86  4979.8  321.36
  4995.3  324.72  5011.1  326.07  5035.6  325.69  5045.7  323.74  5065.8   326.1
  5126.2   328.2  5216.8  334.15  5330.1  337.63  5819.7  345.43  5934.3  345.56
#Mann= 5 ,-1 , 0
  3930.6    .013       0  4001.9     .04       0  4970.7     .04       0
  4979.8     .04       0  5819.7    .013       0
Bank Sta=4970.7,4979.8
XS Rating Curve= 0 ,0
Exp/Cntr=0.3,0.1