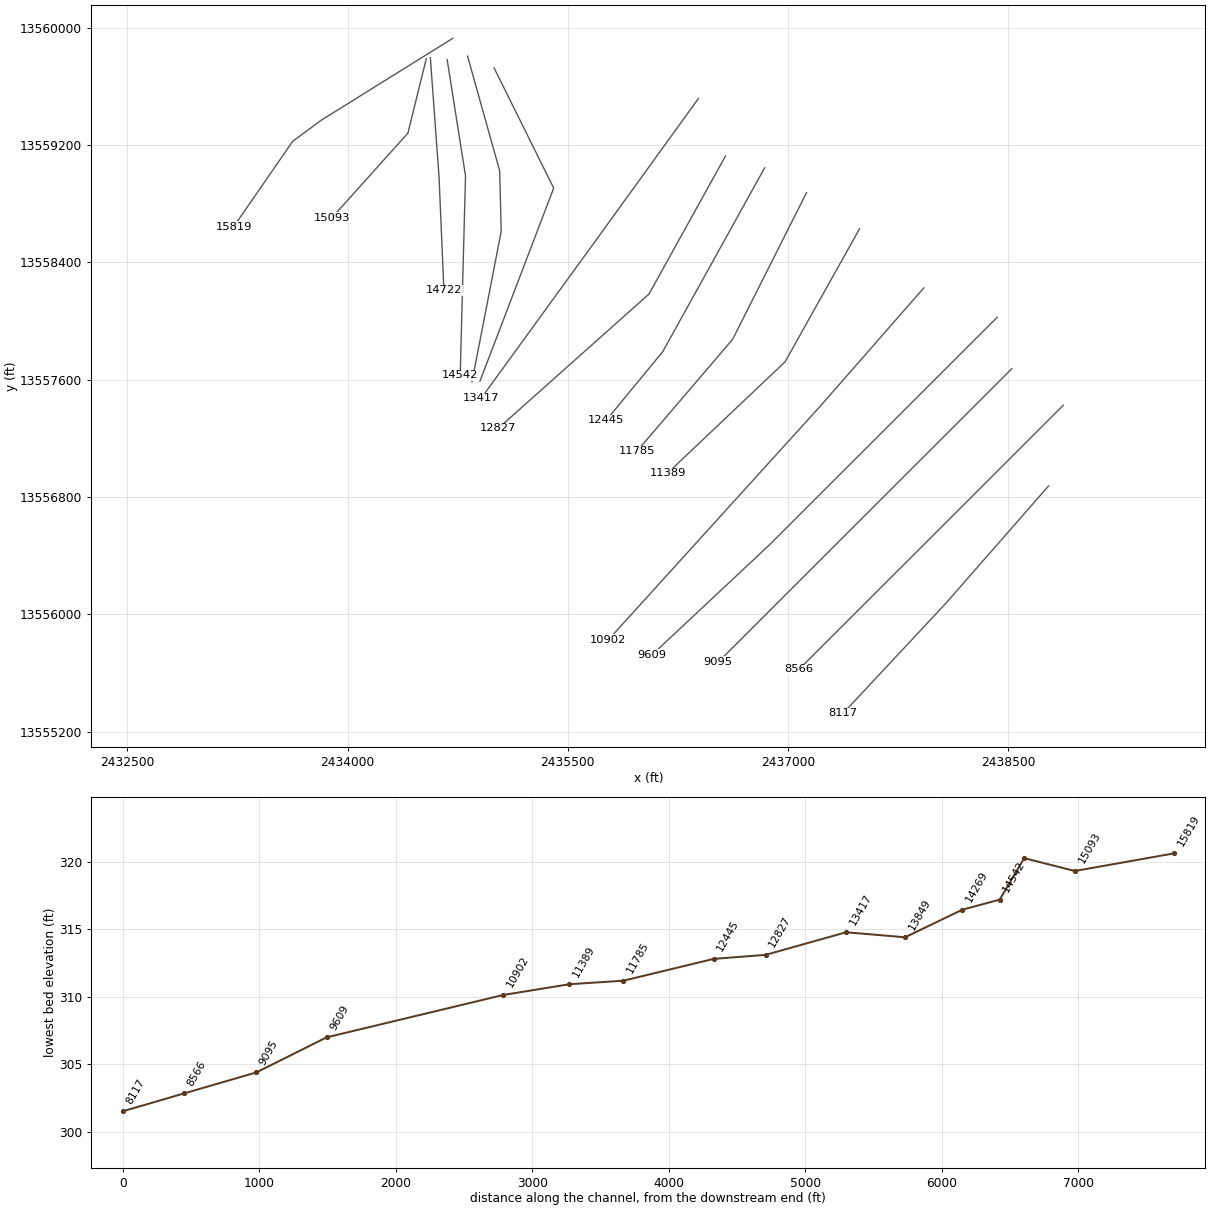
HEC-RAS study TRIB 6 TO YORKTOWN CREEK.prj: TRIB 6 TO YORKTOWN CREEK Base Level Engineering

--- TRIB 6 TO YORKTOWN CREEK.g01 (geometry) --- (continued)

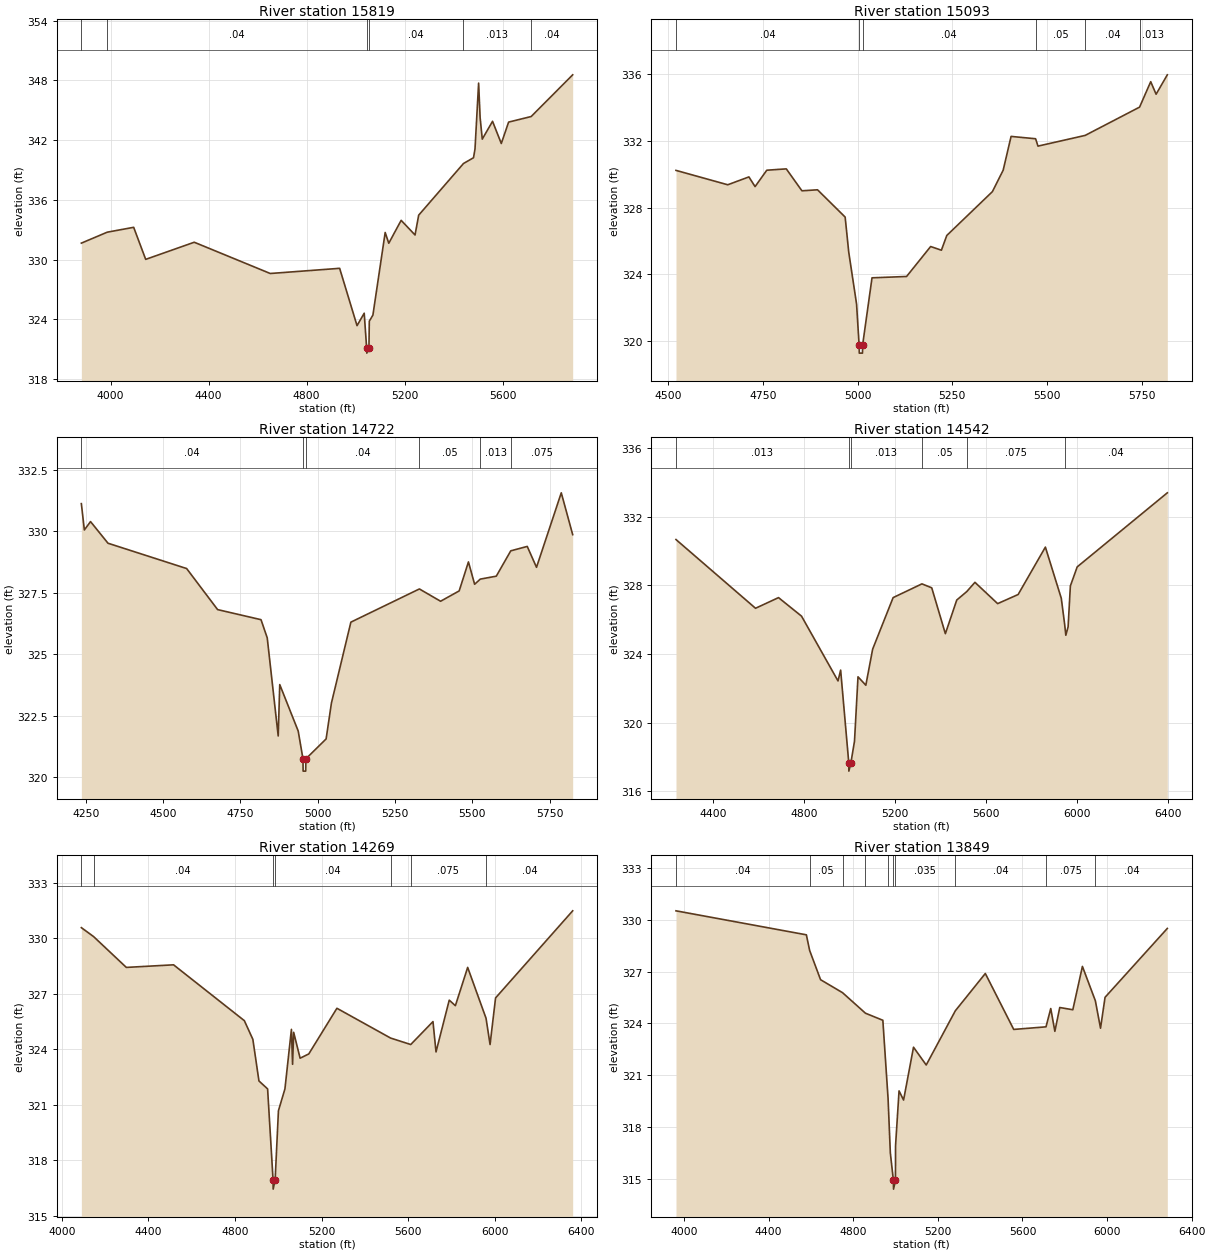
Type RM Length L Ch R = 1 ,15819   ,726,726,726
BEGIN DESCRIPTION:
Mapping XS bd2cacf3
END DESCRIPTION:
XS GIS Cut Line= 4
      2434716.27     13559926.79      2433824.05     13559371.03
      2433626.13     13559225.19      2433223.34     13558641.84
#Sta/Elev= 30
  3880.5  331.65  3986.1  332.75  4094.1  333.24  4143.2  330.02  4341.4  331.74
  4651.8   328.6    4935  329.12    5006  323.36  5035.3  324.61  5045.3   321.1
  5045.8   320.6  5054.6   321.1  5056.1  323.81  5070.8  324.42  5120.9  332.72
  5135.6  331.64  5186.1  333.94  5242.8  332.47  5257.7  334.46  5440.6  339.65
  5481.5  340.23  5487.6   341.1  5502.4  347.73  5508.5  344.27  5517.3   342.1
  5559.2  343.89    5595  341.66  5624.8  343.81  5716.9  344.37  5886.4  348.56
#Mann= 6 ,-1 , 0
  3880.5    .013       0  3986.1     .04       0  5045.3     .04       0
  5054.6     .04       0  5440.6    .013       0  5716.9     .04       0
Bank Sta=5045.3,5054.6
XS Rating Curve= 0 ,0
Exp/Cntr=0.3,0.1

Type RM Length L Ch R = 1 ,15093   ,371,371,371
BEGIN DESCRIPTION:
Mapping XS 7806829f
END DESCRIPTION:
XS GIS Cut Line= 3
      2434535.85     13559787.66      2434410.86     13559280.75
       2433893.5     13558704.37
#Sta/Elev= 30
  4520.7  330.22  4657.3  329.36  4713.1  329.83  4729.4  329.25  4760.3  330.23
  4811.8  330.31    4853     329  4894.2  329.06  4967.1  327.43  4976.6  325.33
  4997.2  322.24  5003.9   319.8  5004.4   319.3  5012.8   319.3  5013.3   319.8
    5038   323.8  5129.2  323.88  5192.7  325.67  5221.1  325.45  5235.3  326.33
  5355.7  328.95  5384.1  330.23    5405  332.25  5469.7  332.11    5476  331.67
  5600.5  332.31  5744.1     334  5773.5  335.52  5787.7  334.77  5817.3  335.93
#Mann= 6 ,-1 , 0
  4520.7     .04       0  5003.9     .04       0  5013.3     .04       0
  5469.7     .05       0  5600.5     .04       0  5744.1    .013       0
Bank Sta=5003.9,5013.3
XS Rating Curve= 0 ,0
Exp/Cntr=0.3,0.1

Type RM Length L Ch R = 1 ,14722   ,180,180,180
BEGIN DESCRIPTION:
Mapping XS 33b9a7b7
END DESCRIPTION:
XS GIS Cut Line= 3
      2434563.63     13559794.67      2434622.66     13558985.61
      2434656.08     13558208.13
#Sta/Elev= 30
  4235.5  331.13  4245.2  330.06  4265.2   330.4  4321.7  329.52  4576.1  328.49
  4676.3  326.82  4816.7  326.41  4836.8  325.67  4872.3  321.68  4877.3  323.77
    4937  321.88  4952.4  320.75  4952.9  320.25  4961.3  320.25  4961.8  320.75
  5027.3  321.56  5044.5  323.02  5107.4  326.31    5329  327.66  5397.6  327.16
  5457.7  327.58  5487.7  328.76  5507.7  327.85    5526  328.06  5577.8  328.18
  5624.6  329.21  5677.9  329.39  5707.9  328.54    5788  331.57  5824.9  329.87
#Mann= 6 ,-1 , 0
  4235.5     .04       0  4952.4     .04       0  4961.8     .04       0
    5329     .05       0    5526    .013       0  5624.6    .075       0
Bank Sta=4952.4,4961.8
XS Rating Curve= 0 ,0
Exp/Cntr=0.3,0.1

Type RM Length L Ch R = 1 ,14542   ,273,273,273
BEGIN DESCRIPTION:
Mapping XS c5b38d93
END DESCRIPTION:
XS GIS Cut Line= 3
      2434678.21      13559780.8      2434803.22     13558989.08
      2434766.88     13557628.49
#Sta/Elev= 30
  4235.1  330.66  4585.2  326.66  4686.4  327.28  4787.7   326.2  4948.2  322.43
  4959.8  323.06  4995.5  317.68    4996  317.18  5005.1  317.68  5020.8  318.92
  5036.2  322.67  5070.7  322.18  5100.7  324.28  5190.8  327.28  5317.6  328.08
  5360.8  327.85  5420.8  325.18  5470.9  327.14  5514.9  327.63  5550.9  328.17
  5650.9  326.93    5741  327.46    5861  330.22    5931  327.24  5945.5  325.76
    5951  325.09    5961  325.58    5971  327.96  6001.1  329.07  6397.7  333.38
#Mann= 6 ,-1 , 0
  4235.1    .013       0  4995.5     .03       0  5005.1    .013       0
  5317.6     .05       0  5514.9    .075       0  5945.5     .04       0
Bank Sta=4995.5,5005.1
XS Rating Curve= 0 ,0
Exp/Cntr=0.3,0.1

Type RM Length L Ch R = 1 ,14269   ,420,420,420
BEGIN DESCRIPTION:
Mapping XS 28c81d00
END DESCRIPTION:
XS GIS Cut Line= 4
      2434817.11     13559805.05      2435035.86     13559023.81
      2435046.27     13558610.61      2434847.34     13557585.45
#Sta/Elev= 30
  4090.7  330.58  4146.9   330.1  4298.4  328.43  4516.5  328.57  4843.4  325.55
  4882.7  324.54  4910.8  322.29  4950.8  321.86    4976  316.94  4976.5  316.44
  4985.6  316.94  5000.8  320.68  5030.8  321.86  5060.8  325.08  5066.1  323.19
  5071.1  324.92  5100.9  323.52  5140.9  323.75  5270.9  326.22  5518.7  324.61
  5611.8  324.26  5714.5   325.5  5728.5  323.86  5789.6  326.66  5817.9  326.36
  5874.7  328.43  5959.5  325.68  5978.1  324.26  6003.5  326.78  6359.6  331.49
#Mann= 7 ,-1 , 0
  4090.7    .013       0  4146.9     .04       0    4976     .04       0
  4985.6     .04       0  5518.7    .013       0  5611.8    .075       0
  5959.5     .04       0
Bank Sta=4976,4985.6
XS Rating Curve= 0 ,0
Exp/Cntr=0.3,0.1

Type RM Length L Ch R = 1 ,13849   ,432,432,432
BEGIN DESCRIPTION:
Mapping XS 906e19ef
END DESCRIPTION:
XS GIS Cut Line= 3
      2434997.67     13559725.18      2435403.91     13558905.75
      2434901.65     13557589.95
#Sta/Elev= 30
  3961.9  330.52  4578.3  329.13  4593.9  328.22  4645.5  326.53  4749.2  325.78
  4857.6  324.59  4939.9  324.18  4964.7  319.63  4975.3   316.5  4989.9   314.9
  4990.4   314.4  4999.5   314.9    5000  316.92  5016.5  320.09  5037.9  319.56
  5084.9  322.62    5145  321.59  5282.6  324.73  5424.4  326.89  5558.7  323.65
  5711.3   323.8  5733.8  324.86  5753.2  323.54  5776.4  324.92  5838.1  324.79
  5883.5   327.3  5944.7  325.31  5969.1  323.72  5990.5  325.51  6284.9   329.5
#Mann= 10 ,-1 , 0
  3961.9     .04       0  4593.9     .05       0  4749.2     .04       0
  4857.6     .05       0  4964.7    .035       0  4989.9    .035       0
  4999.5    .035       0  5282.6     .04       0  5711.3    .075       0
  5944.7     .04       0
Bank Sta=4989.9,4999.5
XS Rating Curve= 0 ,0
Exp/Cntr=0.3,0.1

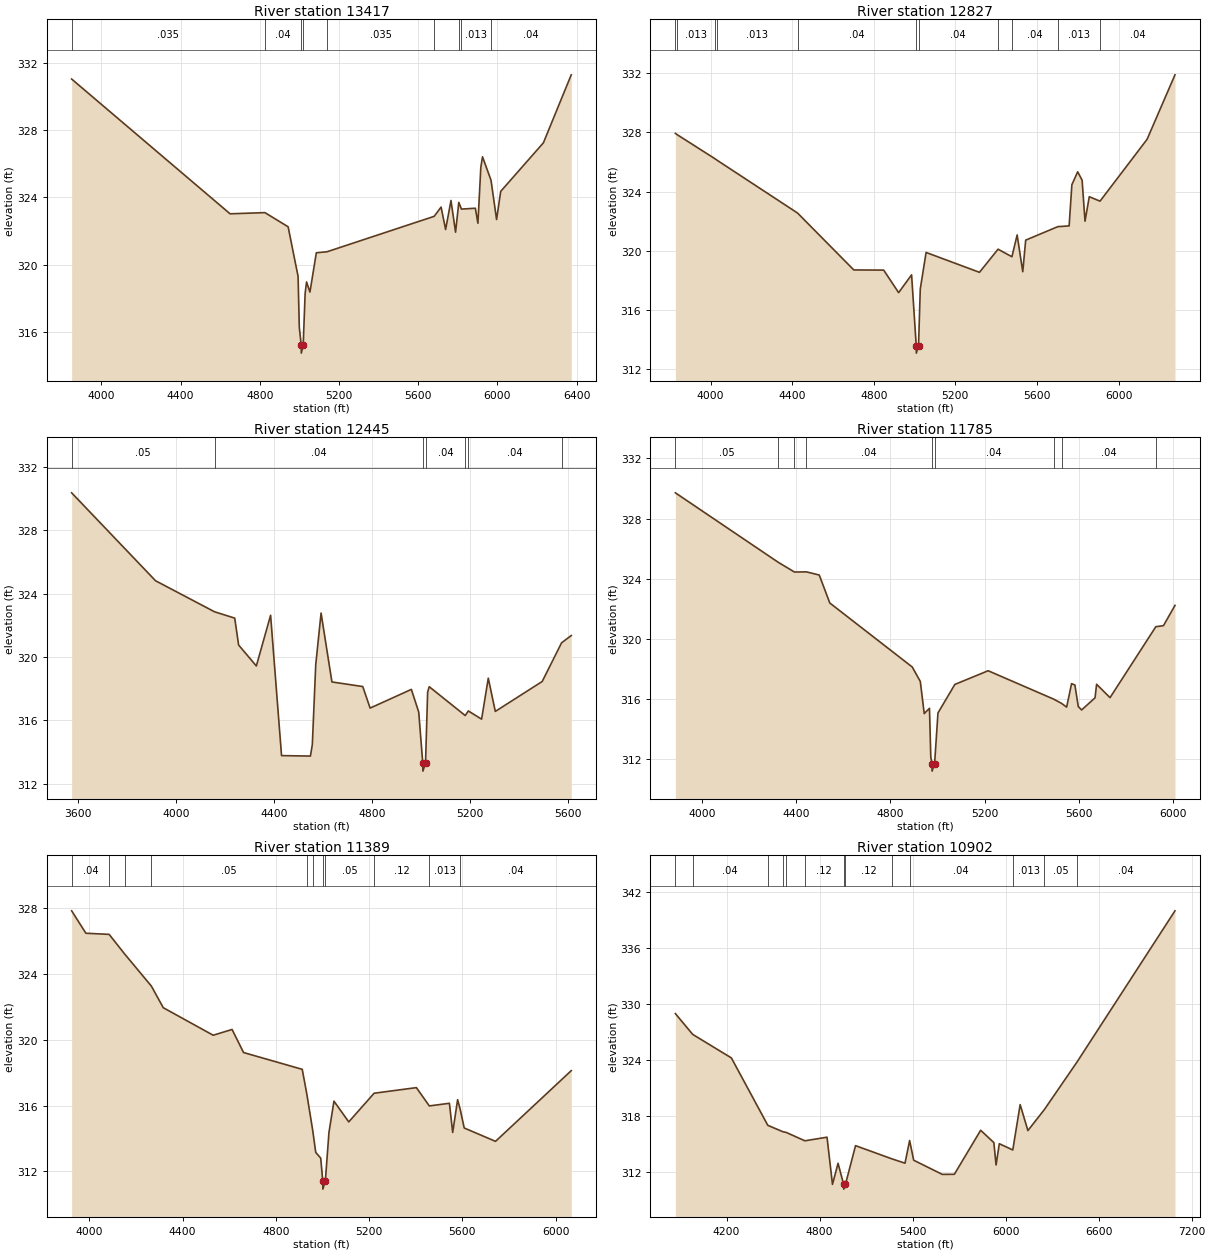
Type RM Length L Ch R = 1 ,13417   ,590,590,590
BEGIN DESCRIPTION:
Mapping XS 8dc20f77
END DESCRIPTION:
XS GIS Cut Line= 3
      2436390.02     13559516.86      2435685.16     13558541.17
       2434909.8     13557472.97
#Sta/Elev= 30
  3849.3  331.02  4649.6  323.03  4825.7   323.1  4942.8  322.26  4993.1  319.32
  4999.3  316.29  5008.9  315.27  5009.4  314.77    5019  315.27  5028.7  318.31
  5035.9  318.99    5053  318.39  5085.3  320.72  5139.3  320.78  5680.5  322.88
  5715.5  323.43  5738.4   322.1  5765.4  323.82  5788.6  321.94  5804.9  323.71
  5818.2  323.31  5888.5  323.36  5901.5  322.47  5916.2  325.79  5924.7  326.41
  5967.7  325.02  5995.8  322.69  6016.6  324.36  6232.3  327.24  6372.9  331.27
#Mann= 9 ,-1 , 0
  3849.3    .035       0  4825.7     .04       0  5008.9     .04       0
    5019     .04       0  5139.3    .035       0  5680.5    .013       0
  5804.9     .04       0  5818.2    .013       0  5967.7     .04       0
Bank Sta=5008.9,5019
XS Rating Curve= 0 ,0
Exp/Cntr=0.3,0.1

Type RM Length L Ch R = 1 ,12827   ,382,382,382
BEGIN DESCRIPTION:
Mapping XS 9fb1e736
END DESCRIPTION:
XS GIS Cut Line= 3
      2436574.07     13559124.54      2436053.22     13558183.53
      2435027.53     13557269.34
#Sta/Elev= 30
  3827.4  327.92  3835.6  327.84  4022.6   326.2  4031.8  326.11  4426.3  322.55
  4702.2  318.71  4848.7   318.7    4922  317.18  4985.5  318.38  5008.3   313.6
  5008.8   313.1  5019.5   313.6  5028.1  317.43  5056.6  319.89  5318.3  318.55
  5409.5  320.11  5477.4   319.6    5503  321.07  5530.6  318.59  5544.9  320.72
  5702.4  321.63  5757.9  321.68  5771.4  324.46  5799.9  325.33  5821.6  324.76
  5835.8     322  5856.7  323.65  5909.4  323.35  6140.1  327.52  6276.9  331.87
#Mann= 11 ,-1 , 0
  3827.4     .04       0  3835.6    .013       0  4022.6     .05       0
  4031.8    .013       0  4426.3     .04       0  5008.3     .04       0
  5019.5     .04       0  5409.5    .013       0  5477.4     .04       0
  5702.4    .013       0  5909.4     .04       0
Bank Sta=5008.3,5019.5
XS Rating Curve= 0 ,0
Exp/Cntr=0.3,0.1

Type RM Length L Ch R = 1 ,12445   ,660,660,660
BEGIN DESCRIPTION:
Mapping XS 94109faf
END DESCRIPTION:
XS GIS Cut Line= 3
      2436841.39      13559044.6      2436146.97     13557791.17
      2435761.55     13557322.41
#Sta/Elev= 30
  3574.7  330.37  3917.2  324.82  4158.1  322.86  4240.5  322.46  4256.5  320.76
  4328.8  319.44    4387  322.64  4431.7  313.78  4549.6  313.75  4557.4  314.48
  4571.3  319.52  4593.1  322.78  4637.4  318.43  4763.2  318.14  4793.4  316.78
  4961.7  317.96  4991.8  316.53  5008.3   313.3  5008.8   312.8  5019.5   313.3
  5028.2  317.79  5034.7  318.13  5181.6  316.31  5194.3   316.6  5248.5  316.08
  5275.8  318.67  5304.5  316.57    5496  318.46    5575   320.9  5614.5  321.36
#Mann= 7 ,-1 , 0
  3574.7     .05       0  4158.1     .04       0  5008.3     .04       0
  5019.5     .04       0  5181.6    .013       0  5194.3     .04       0
    5575     .05       0
Bank Sta=5008.3,5019.5
XS Rating Curve= 0 ,0
Exp/Cntr=0.3,0.1

Type RM Length L Ch R = 1 ,11785   ,396,396,396
BEGIN DESCRIPTION:
Mapping XS 35a95cc3
END DESCRIPTION:
XS GIS Cut Line= 3
      2437126.14      13558874.5      2436622.66      13557874.5
      2435969.95     13557110.69
#Sta/Elev= 30
  3885.6  329.71  4323.6  325.08  4391.9  324.44  4442.9  324.45  4497.4  324.24
  4542.1  322.38  4892.7  318.12    4927  317.16  4943.7  315.02    4966  315.37
  4971.6  312.13  4976.6  311.69  4977.1  311.19  4987.8  311.69  5002.1  315.06
  5073.9  316.96  5215.5  317.87  5494.2  315.98  5527.4   315.7  5549.2  315.45
  5570.2  317.01  5584.4  316.92  5598.6  315.49  5612.9  315.26    5670  316.07
  5676.6  316.97  5733.7  316.08  5928.4   320.8  5960.9  320.87  6009.9  322.22
#Mann= 9 ,-1 , 0
  3885.6     .05       0  4323.6     .04       0  4391.9     .05       0
  4442.9     .04       0  4976.6     .04       0  4987.8     .04       0
  5494.2    .013       0  5527.4     .04       0  5928.4    .013       0
Bank Sta=4976.6,4987.8
XS Rating Curve= 0 ,0
Exp/Cntr=0.3,0.1

Type RM Length L Ch R = 1 ,11389   ,487,487,487
BEGIN DESCRIPTION:
Mapping XS ba331cdc
END DESCRIPTION:
XS GIS Cut Line= 3
      2437487.27     13558628.01       2436980.3     13557721.72
      2436179.09     13556962.13
#Sta/Elev= 30
  3924.5  327.82  3985.7  326.46  4085.4  326.39  4151.3  325.21  4266.5  323.25
  4317.5  321.94  4531.5  320.27  4612.5  320.62  4661.7  319.22  4913.4   318.2
  4933.3  316.68  4957.6  314.56  4971.3  313.16  4992.7  312.81  5001.3  311.43
  5001.8  310.93  5012.5  311.43  5027.9  314.36  5049.4  316.27  5112.9  315.01
  5221.6  316.75  5402.9  317.09  5458.4  315.98  5544.5  316.14  5558.6  314.37
  5579.7  316.36  5591.5  315.73    5608  314.64  5742.3  313.83    6067  318.12
#Mann= 11 ,-1 , 0
  3924.5     .04       0  4085.4     .05       0  4151.3     .04       0
  4266.5     .05       0  4933.3     .12       0  4957.6     .05       0
  5001.3     .05       0  5012.5     .05       0  5221.6     .12       0
  5458.4    .013       0  5591.5     .04       0
Bank Sta=5001.3,5012.5
XS Rating Curve= 0 ,0
Exp/Cntr=0.3,0.1

Type RM Length L Ch R = 1 ,10902   ,1293,1293,1293
BEGIN DESCRIPTION:
TRIB 6 TO YORKTOWN CREEK 19.0
END DESCRIPTION:
XS GIS Cut Line= 3
      2437924.98     13558224.98        2437225.       13557425.
      2435774.98     13555824.98
#Sta/Elev= 30
  3869.8  328.95  3981.6  326.72  4230.9   324.2    4466  316.97  4562.4  316.29
  4584.6  316.21  4705.1  315.31  4847.8   315.7    4883  310.64    4919   312.9
  4955.2  310.63  4955.7  310.13  4966.5  310.63  5031.8  314.79  5265.7  313.38
  5350.8  312.91  5380.5  315.34  5406.9  313.23  5591.4  311.71  5669.1  311.72
  5838.7  316.44  5923.9  315.12  5938.1  312.72    5959     315  6045.9  314.33
  6093.5  319.19  6143.5  316.41  6249.2  318.65  6459.9  323.75  7092.1  339.97
#Mann= 13 ,-1 , 0
  3869.8     .05       0  3981.6     .04       0    4466     .05       0
  4562.4     .04       0  4584.6     .05       0  4705.1     .12       0
  4955.2     .05       0  4966.5     .12       0  5265.7    .013       0
  5380.5     .04       0  6045.9    .013       0  6249.2     .05       0
  6459.9     .04       0
Bank Sta=4955.2,4966.5
XS Rating Curve= 0 ,0
Exp/Cntr=0.3,0.1

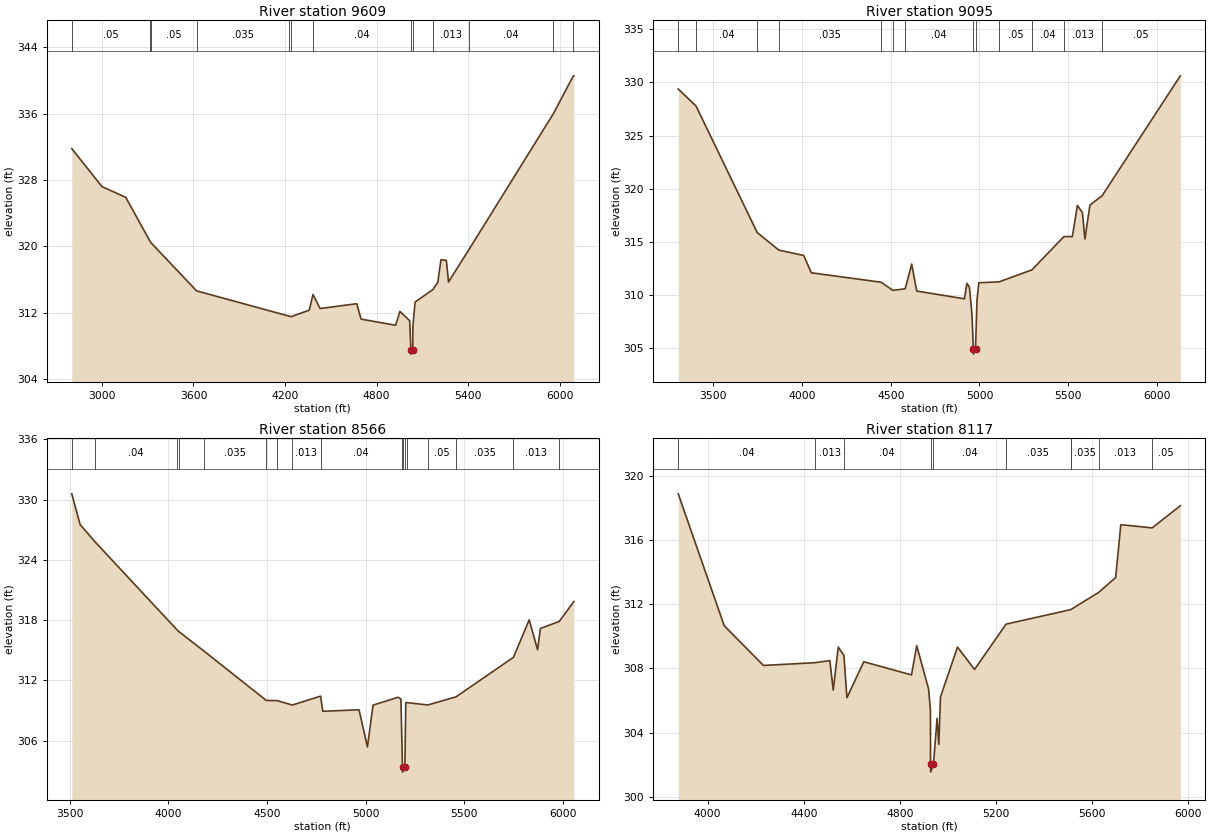
Type RM Length L Ch R = 1 ,9609    ,514,514,514
BEGIN DESCRIPTION:
TRIB 6 TO YORKTOWN CREEK 18.0
END DESCRIPTION:
XS GIS Cut Line= 3
      2438424.98     13558024.98        2436875.       13556475.
      2436074.99     13555724.99
#Sta/Elev= 30
  2802.8  331.78  3000.8   327.2  3156.3  325.91  3317.7  320.53  3320.4  320.46
  3620.1  314.63  4228.2  311.57  4239.3  311.52  4358.4   312.3  4382.8  314.19
  4429.1   312.5  4669.5  313.08  4697.8  311.22  4924.1  310.48  4952.4  312.15
    5016  311.04  5024.2   307.5  5024.7     307  5036.3   307.5  5037.1  310.29
  5051.2  313.27    5169   314.8  5200.2  315.66  5221.2  318.39  5256.4   318.3
  5270.5   315.7  5401.4  319.52  5957.1  335.99  6088.4  340.56  6091.4  340.56
#Mann= 13 ,-1 , 0
  2802.8     .05       0  3317.7     .04       0  3320.4     .05       0
  3620.1    .035       0  4228.2     .04       0  4239.3    .013       0
  4382.8     .04       0  5024.2     .04       0  5036.3     .04       0
    5169    .013       0  5401.4     .04       0  5957.1     .03       0
  6088.4     .05       0
Bank Sta=5024.2,5036.3
XS Rating Curve= 0 ,0
Exp/Cntr=0.3,0.1

Type RM Length L Ch R = 1 ,9095    ,529,529,529
BEGIN DESCRIPTION:
TRIB 6 TO YORKTOWN CREEK 17.0
END DESCRIPTION:
XS GIS Cut Line= 3
      2438524.99     13557674.99        2437325.       13556475.
      2436525.01     13555675.01
#Sta/Elev= 30
  3303.1  329.38  3403.6  327.77  3747.9  315.86  3869.4  314.21  4010.2   313.7
  4052.6  312.07  4446.6  311.18  4512.8  310.41  4581.8  310.57  4618.3  312.89
  4646.6  310.35  4915.3  309.62  4929.4  311.08  4943.6   310.7  4957.7  308.19
  4965.8  304.91  4966.3  304.41  4977.9  304.91    4986  309.49  4996.6  311.13
  5111.1  311.22  5294.9  312.34  5476.1  315.48  5523.4  315.48  5551.7  318.41
    5580  317.74  5594.1  315.25  5622.4  318.45  5690.8  319.32  6131.5  330.62
#Mann= 13 ,-1 , 0
  3303.1     .05       0  3403.6     .04       0  3747.9     .05       0
  3869.4    .035       0  4446.6     .04       0  4512.8    .013       0
  4581.8     .04       0  4965.8     .04       0  4977.9     .04       0
  5111.1     .05       0  5294.9     .04       0  5476.1    .013       0
  5690.8     .05       0
Bank Sta=4965.8,4977.9
XS Rating Curve= 0 ,0
Exp/Cntr=0.3,0.1

Type RM Length L Ch R = 1 ,8566    ,449,449,449
BEGIN DESCRIPTION:
TRIB 6 TO YORKTOWN CREEK 16.0
END DESCRIPTION:
XS GIS Cut Line= 3
      2438875.01     13557425.01        2437675.       13556225.
      2437074.99     13555624.99
#Sta/Elev= 30
  3510.3  330.58  3552.7  327.52  3628.7  325.79  4043.5  317.04  4054.4  316.84
  4178.7  314.95  4496.5     310  4552.3  309.98  4628.4  309.54  4771.9  310.43
  4783.1  308.92  4966.9  309.07  5009.4  305.37  5037.7  309.53  5164.9  310.32
  5179.1  310.14  5184.6  305.54  5187.2  303.36  5187.7  302.86  5199.3  303.36
  5203.8  309.78  5210.6  309.78  5316.1  309.55  5458.8  310.36  5749.9   314.3
  5829.6  318.03    5872  315.04  5886.2  317.17  5982.1  317.87  6055.9  319.85
#Mann= 17 ,-1 , 0
  3510.3     .05       0  3628.7     .04       0  4043.5    .035       0
  4054.4     .04       0  4178.7    .035       0  4496.5     .04       0
  4552.3    .035       0  4628.4    .013       0  4771.9     .04       0
  5184.6     .05       0  5187.2     .04       0  5199.3     .05       0
  5210.6     .04       0  5316.1     .05       0  5458.8    .035       0
  5749.9    .013       0  5982.1     .05       0
Bank Sta=5187.2,5199.3
XS Rating Curve= 0 ,0
Exp/Cntr=0.3,0.1

Type RM Length L Ch R = 1 ,8117    ,405,405,405
BEGIN DESCRIPTION:
TRIB 6 TO YORKTOWN CREEK 15.0
END DESCRIPTION:
XS GIS Cut Line= 3
      2438775.02     13556875.02        2438075.       13556075.
      2437374.97     13555324.97
#Sta/Elev= 30
  3877.9  318.86  4069.2  310.65  4232.4  308.18  4447.6  308.35  4508.6  308.48
  4522.9  306.65  4543.7  309.32  4567.2  308.81  4579.8  306.17    4650  308.41
  4848.4  307.59  4870.2  309.41  4919.6  306.71  4927.2   305.4  4927.8  302.04
  4928.3  301.54  4939.9  302.04  4954.9  304.89  4962.2  303.27    4969  306.22
  5039.9  309.32  5110.7  307.93    5242  310.75  5510.3  311.65  5510.8  311.65
  5626.7  312.72  5697.9  313.65  5719.4  316.94    5850  316.74  5966.9  318.12
#Mann= 10 ,-1 , 0
  3877.9     .04       0  4447.6    .013       0  4567.2     .04       0
  4927.8     .04       0  4939.9     .04       0    5242    .035       0
  5510.3    .013       0  5510.8    .035       0  5626.7    .013       0
    5850     .05       0
Bank Sta=4927.8,4939.9
XS Rating Curve= 0 ,0
Exp/Cntr=0.3,0.1