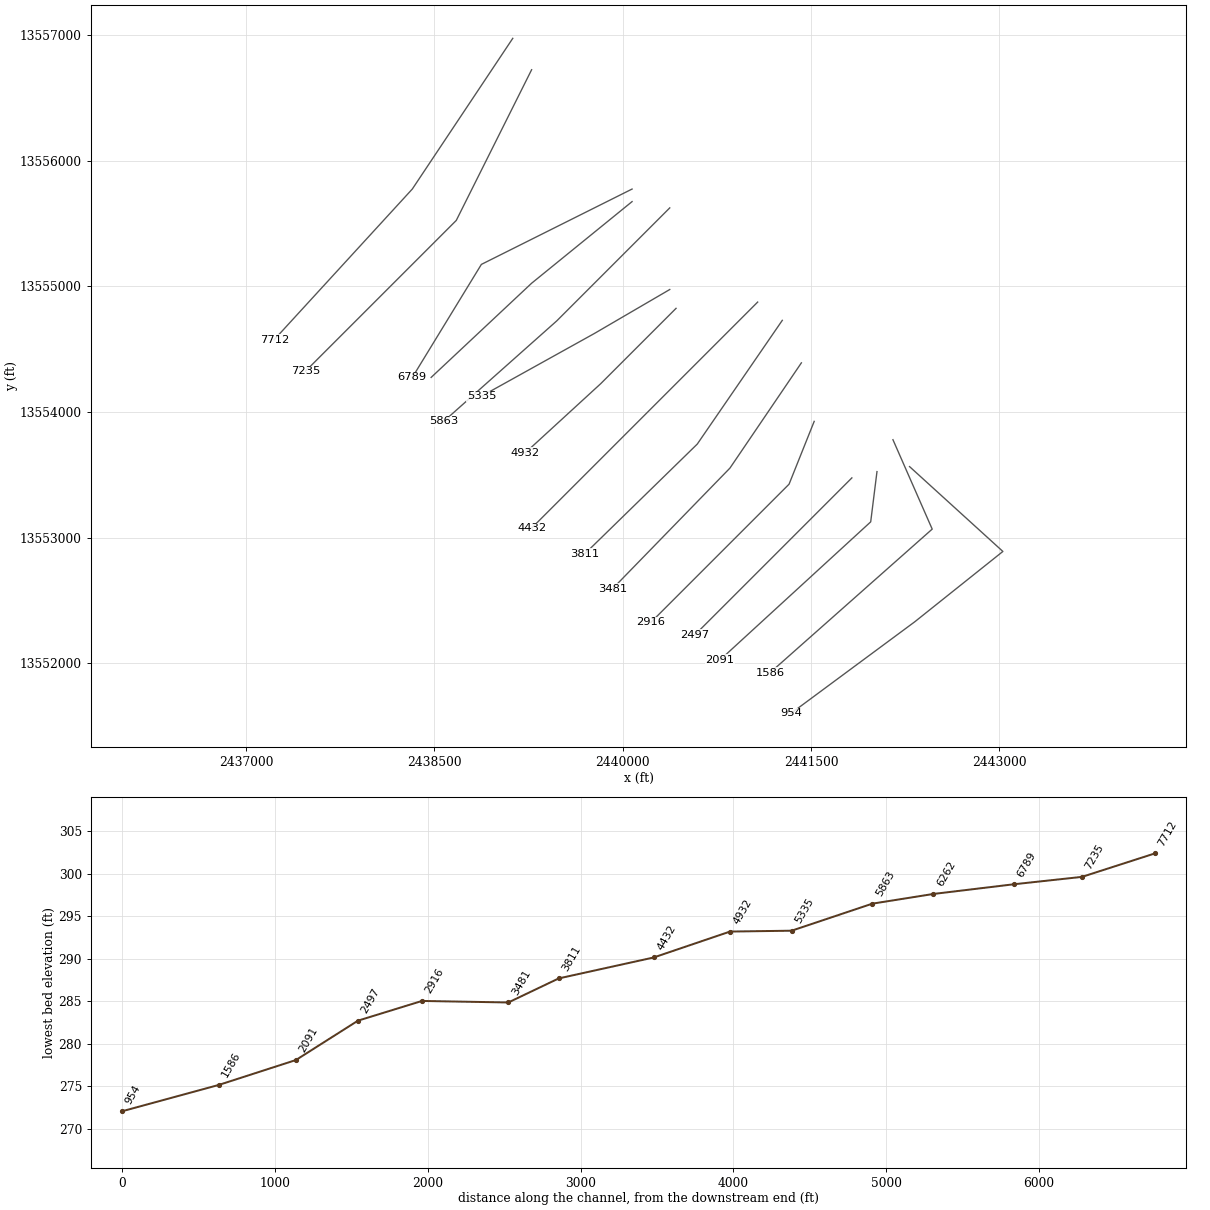
HEC-RAS study TRIB 6 TO YORKTOWN CREEK.prj: TRIB 6 TO YORKTOWN CREEK Base Level Engineering

--- TRIB 6 TO YORKTOWN CREEK.g01 (geometry) --- (continued)

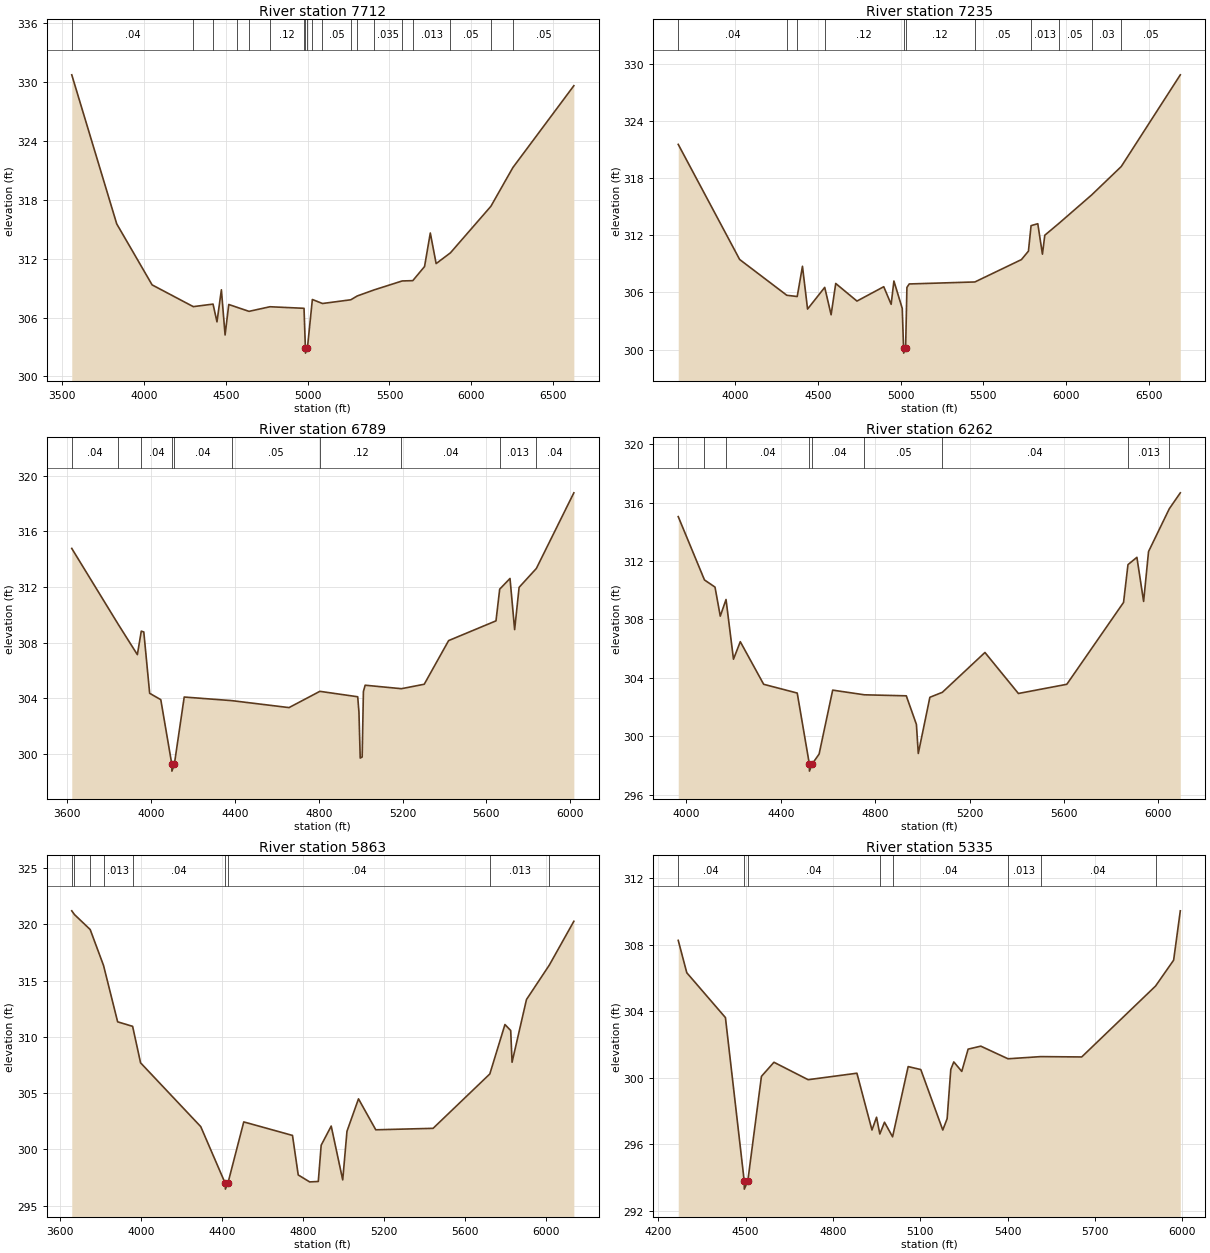
Type RM Length L Ch R = 1 ,7712    ,477,477,477
BEGIN DESCRIPTION:
TRIB 6 TO YORKTOWN CREEK 14.0
END DESCRIPTION:
XS GIS Cut Line= 3
      2439125.01     13556975.02        2438325.       13555775.
      2437225.01     13554575.02
#Sta/Elev= 30
  3557.2  330.76  3832.1  315.56  4048.5  309.34  4300.3  307.12  4421.1  307.38
  4445.1  305.57  4472.1  308.84  4494.7  304.23  4517.2  307.34  4564.9  307.07
    4641  306.64    4769  307.11  4977.4  306.95  4985.8  302.88  4986.3  302.38
    4998  302.88  5028.4  307.85  5090.2  307.44  5263.4  307.82    5303  308.21
  5404.6  308.82  5577.7  309.74  5642.4  309.77  5714.4  311.21  5749.6  314.63
  5785.3  311.51  5872.8  312.61  6119.9  317.35  6254.4   321.3  6627.3  329.65
#Mann= 19 ,-1 , 0
  3557.2     .04       0  4300.3    .013       0  4421.1     .05       0
  4564.9     .12       0    4641     .05       0    4769     .12       0
  4977.4     .05       0  4985.8     .05       0    4998     .05       0
  5028.4     .12       0  5090.2     .05       0  5263.4    .035       0
    5303     .04       0  5404.6    .035       0  5577.7     .04       0
  5642.4    .013       0  5872.8     .05       0  6119.9     .03       0
  6254.4     .05       0
Bank Sta=4985.8,4998
XS Rating Curve= 0 ,0
Exp/Cntr=0.3,0.1

Type RM Length L Ch R = 1 ,7235    ,446,446,446
BEGIN DESCRIPTION:
TRIB 6 TO YORKTOWN CREEK 13.0
END DESCRIPTION:
XS GIS Cut Line= 3
      2439275.02     13556725.03        2438675.       13555525.
      2437475.02     13554325.02
#Sta/Elev= 30
  3653.5  321.56  4025.3  309.46  4310.6   305.7  4373.6  305.57  4405.4  308.75
  4436.2  304.25  4540.1  306.53  4578.7  303.65  4606.7  306.94  4735.2  305.09
  4897.3   306.6  4942.1  304.75  4958.8   307.2  5009.3  304.32  5017.4  300.12
  5017.9  299.62  5029.6  300.12  5037.6  306.53  5051.7  306.89    5449   307.1
  5730.6  309.45    5773  310.34    5789  313.02  5829.6  313.22  5857.8  310.02
    5872  312.01  5956.4  313.24  6155.9  316.25  6334.7  319.23  6692.2  328.87
#Mann= 11 ,-1 , 0
  3653.5     .04       0  4310.6    .013       0  4373.6     .05       0
  4540.1     .12       0  5017.4     .05       0  5029.6     .12       0
    5449     .05       0    5789    .013       0  5956.4     .05       0
  6155.9     .03       0  6334.7     .05       0
Bank Sta=5017.4,5029.6
XS Rating Curve= 0 ,0
Exp/Cntr=0.3,0.1

Type RM Length L Ch R = 1 ,6789    ,527,527,527
BEGIN DESCRIPTION:
TRIB 6 TO YORKTOWN CREEK 12.0
END DESCRIPTION:
XS GIS Cut Line= 3
      2440075.01     13555775.01        2438875.       13555175.
        2438325.     13554275.01
#Sta/Elev= 30
  3621.4  314.77  3843.2  309.31  3934.5  307.13  3953.2  308.82  3965.2  308.76
  3993.2  304.35  4046.3  303.89  4098.9  299.25  4099.4  298.75  4111.1  299.25
  4158.1  304.08  4385.6  303.82  4658.4  303.32  4805.5  304.49  4986.2   304.1
  4992.1     303  4998.2  299.69  5007.5  299.77  5013.4  304.48  5021.7  304.93
  5194.9  304.68  5303.7     305  5420.1  308.14  5646.2  309.56  5663.9  311.84
  5713.1  312.61  5735.2  308.93  5756.5  311.97  5838.9  313.33  6017.8  318.77
#Mann= 10 ,-1 , 0
  3621.4     .04       0  3843.2    .013       0  3953.2     .04       0
  4098.9     .05       0  4111.1     .04       0  4385.6     .05       0
  4805.5     .12       0  5194.9     .04       0  5663.9    .013       0
  5838.9     .04       0
Bank Sta=4098.9,4111.1
XS Rating Curve= 0 ,0
Exp/Cntr=0.3,0.1

Type RM Length L Ch R = 1 ,6262    ,399,399,399
BEGIN DESCRIPTION:
TRIB 6 TO YORKTOWN CREEK 11.0
END DESCRIPTION:
XS GIS Cut Line= 3
      2440074.98     13555674.98        2439275.       13555025.
      2438475.02     13554275.02
#Sta/Elev= 30
  3965.2  315.05  4076.4  310.71    4121  310.22  4143.3  308.23  4167.7  309.37
  4199.3  305.28  4228.1  306.48  4327.2  303.56  4469.4  302.96  4520.6  298.11
  4521.1  297.61  4533.1  298.11  4562.1  298.78  4619.6  303.16  4754.1  302.84
  4931.5  302.77  4974.4  300.81  4982.3  298.82  5031.4  302.67  5084.2  303.01
  5264.8  305.74  5406.5  302.93  5611.6  303.56    5852  309.17  5870.8  311.76
  5908.6  312.26    5937  309.24    5958  312.66  6045.9  315.59  6092.5  316.68
#Mann= 9 ,-1 , 0
  3965.2     .04       0  4076.4    .013       0  4167.7     .04       0
  4520.6     .05       0  4533.1     .04       0  4754.1     .05       0
  5084.2     .04       0  5870.8    .013       0  6045.9     .04       0
Bank Sta=4520.6,4533.1
XS Rating Curve= 0 ,0
Exp/Cntr=0.3,0.1

Type RM Length L Ch R = 1 ,5863    ,528,528,528
BEGIN DESCRIPTION:
TRIB 6 TO YORKTOWN CREEK 10.0
END DESCRIPTION:
XS GIS Cut Line= 3
      2440374.99     13555624.99        2439475.       13554725.
      2438575.03     13553925.02
#Sta/Elev= 30
    3659  321.19  3672.2  320.86  3749.8  319.53  3815.7  316.34  3885.3  311.33
  3959.2  310.93  3998.4  307.69  4295.4  302.02  4416.4  296.97  4416.9  296.47
  4428.9  296.97  4507.5  302.44  4747.9  301.24  4776.2  297.73  4832.8  297.11
  4875.2  297.15  4889.4  300.37  4938.9  302.07  4995.7  297.29  5016.7  301.61
  5073.5  304.49  5158.8  301.74  5441.5  301.87  5721.4   306.7    5796  311.09
  5824.4  310.56  5831.1  307.74  5902.2  313.31  6014.9  316.37  6135.9  320.26
#Mann= 9 ,-1 , 0
    3659     .04       0  3672.2     .05       0  3749.8     .04       0
  3815.7    .013       0  3959.2     .04       0  4416.4     .04       0
  4428.9     .04       0  5721.4    .013       0  6014.9     .04       0
Bank Sta=4416.4,4428.9
XS Rating Curve= 0 ,0
Exp/Cntr=0.3,0.1

Type RM Length L Ch R = 1 ,5335    ,403,403,403
BEGIN DESCRIPTION:
TRIB 6 TO YORKTOWN CREEK 9.0
END DESCRIPTION:
XS GIS Cut Line= 3
        2440375.       13554975.        2439775.       13554625.
      2438874.99     13554124.99
#Sta/Elev= 30
  4268.7  308.27  4298.1  306.32  4430.8  303.62  4495.2  293.79  4495.7  293.29
  4507.7  293.79  4554.4  300.08  4597.4  300.93  4714.8  299.88  4882.3  300.27
    4934  296.85  4949.7  297.62    4961  296.61    4977  297.32  5004.8  296.44
  5058.3  300.67  5101.7  300.49  5177.2  296.85  5192.1  297.53  5204.7   300.5
    5215  300.95  5242.4  300.38  5264.2  301.72  5307.7   301.9  5401.2  301.14
  5513.3  301.27  5654.3  301.25  5907.9  305.52    5970  307.08  5992.9  310.05
#Mann= 8 ,-1 , 0
  4268.7     .04       0  4495.2     .05       0  4507.7     .04       0
    4961     .05       0  5004.8     .04       0  5401.2    .013       0
  5513.3     .04       0  5907.9    .013       0
Bank Sta=4495.2,4507.7
XS Rating Curve= 0 ,0
Exp/Cntr=0.3,0.1

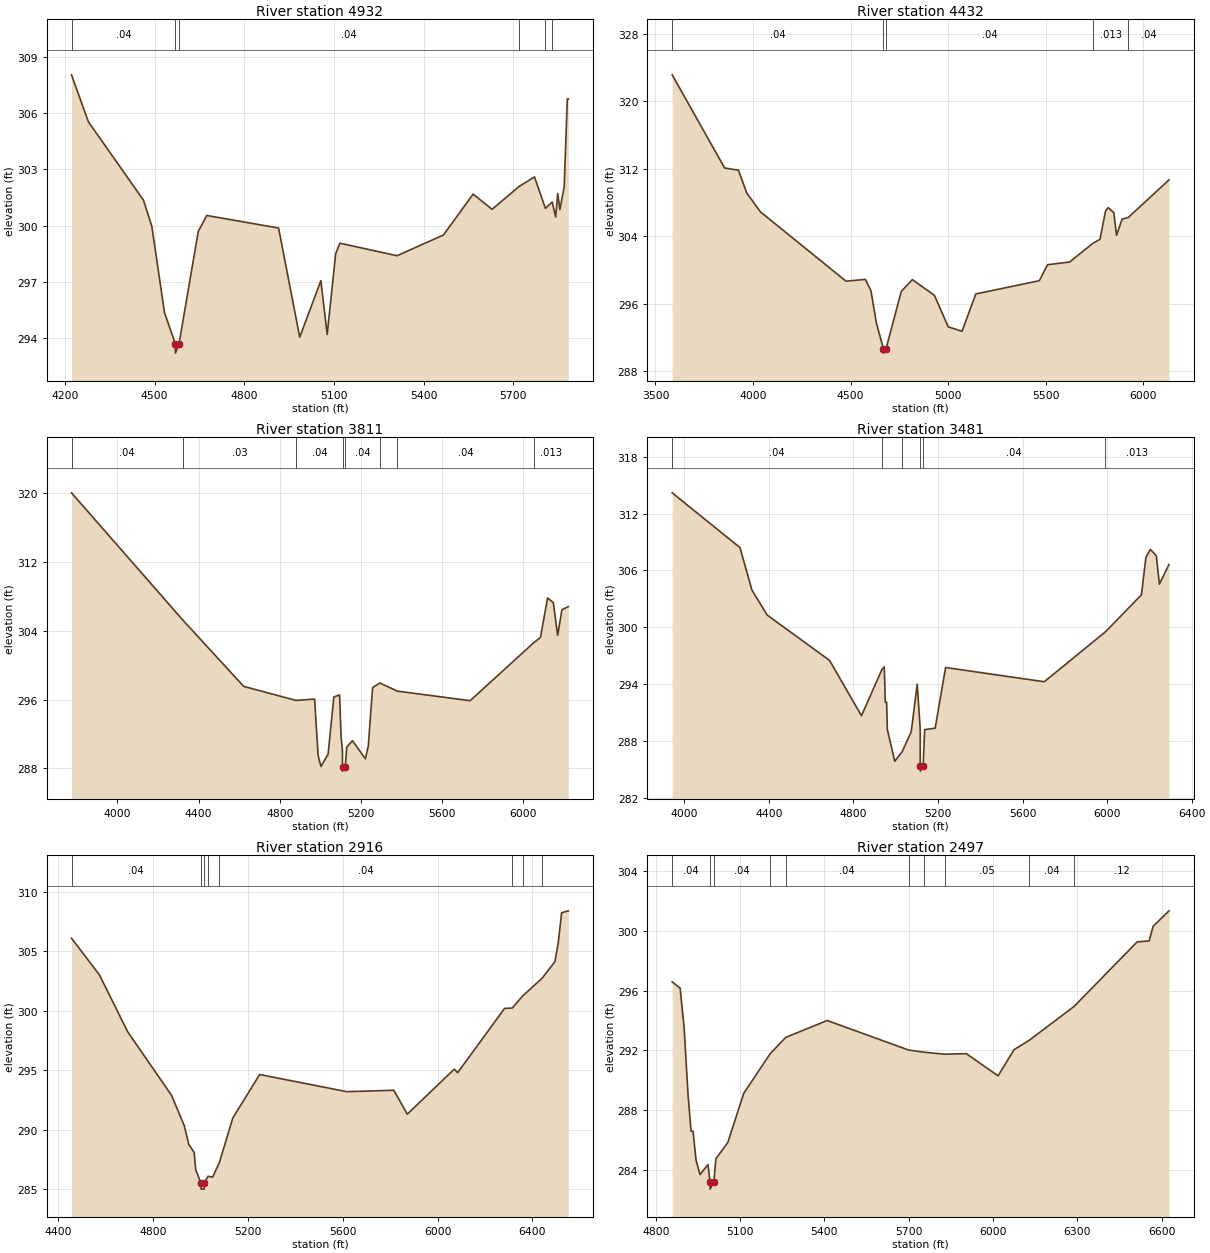
Type RM Length L Ch R = 1 ,4932    ,500,500,500
BEGIN DESCRIPTION:
TRIB 6 TO YORKTOWN CREEK 8.0
END DESCRIPTION:
XS GIS Cut Line= 3
        2440425.       13554825.        2439825.       13554225.
      2439224.98     13553674.98
#Sta/Elev= 30
  4222.1  308.05  4278.7  305.54  4462.5  301.37  4490.8  299.97  4533.2  295.36
  4569.4  293.69  4569.9  293.19  4581.9  293.69  4646.4  299.69  4674.7  300.54
  4915.1  299.87  4985.8  294.04  5056.5  297.06  5077.7  294.19  5106.1   298.5
  5120.3  299.06  5311.4  298.39  5466.8   299.5  5566.1  301.68  5629.6  300.87
  5719.9  302.09  5771.4   302.6  5807.9  300.92  5830.7  301.26  5842.3  300.46
  5849.1  301.71  5856.5  300.86  5870.7  302.06  5881.2  306.76  5884.6  306.76
#Mann= 6 ,-1 , 0
  4222.1     .04       0  4569.4     .04       0  4581.9     .04       0
  5719.9    .013       0  5807.9     .04       0  5830.7    .013       0
Bank Sta=4569.4,4581.9
XS Rating Curve= 0 ,0
Exp/Cntr=0.3,0.1

Type RM Length L Ch R = 1 ,4432    ,621,621,621
BEGIN DESCRIPTION:
TRIB 6 TO YORKTOWN CREEK 7.0
END DESCRIPTION:
XS GIS Cut Line= 3
      2441074.97     13554874.97        2440175.       13553975.
      2439275.03     13553075.03
#Sta/Elev= 30
  3585.8  323.11  3854.5  312.07  3925.2  311.82  3967.6  309.12  4038.3  306.87
  4476.7  298.66  4575.7  298.88    4604  297.55  4632.3  293.69  4668.2  290.64
  4668.7  290.14  4681.3  290.64  4759.6  297.45  4816.1  298.85  4929.3  296.99
    5000  293.25  5070.7  292.73  5141.4  297.15  5466.7  298.72  5509.1  300.61
  5622.2  300.94  5741.9  303.16  5777.8  303.63  5806.1  306.97  5820.2  307.38
  5848.5  306.78  5862.6   304.1  5890.9  306.01  5922.5  306.21  6131.3  310.66
#Mann= 5 ,-1 , 0
  3585.8     .04       0  4668.2     .04       0  4681.3     .04       0
  5741.9    .013       0  5922.5     .04       0
Bank Sta=4668.2,4681.3
XS Rating Curve= 0 ,0
Exp/Cntr=0.3,0.1

Type RM Length L Ch R = 1 ,3811    ,330,330,330
BEGIN DESCRIPTION:
Mapping XS 8ecf117f
END DESCRIPTION:
XS GIS Cut Line= 3
       2441271.1     13554729.54      2440594.02     13553744.29
       2439696.8     13552868.75
#Sta/Elev= 30
  3773.3  320.04  4323.3  305.21  4622.4  297.53  4880.6   295.9  4971.6  296.06
  4988.8  289.54  5002.9  288.22  5038.2  289.65  5066.5   296.3  5094.8  296.54
    5102  291.75  5108.9  290.06  5109.3  288.18  5109.8  287.68  5122.9  288.18
  5130.3  290.49  5158.5  291.22  5222.1  289.11  5236.3   290.6  5257.6  297.39
  5293.3  297.93  5380.3  296.98  5738.3  295.87  6051.3   302.6    6085  303.23
  6120.2  307.81  6148.5  307.28  6169.7  303.48    6191  306.45  6222.4  306.81
#Mann= 8 ,-1 , 0
  3773.3     .04       0  4323.3     .03       0  4880.6     .04       0
  5109.3     .04       0  5122.9     .04       0  5293.3     .03       0
  5380.3     .04       0  6051.3    .013       0
Bank Sta=5109.3,5122.9
XS Rating Curve= 0 ,0
Exp/Cntr=0.3,0.1

Type RM Length L Ch R = 1 ,3481    ,565,565,565
BEGIN DESCRIPTION:
Mapping XS fc2c8c26
END DESCRIPTION:
XS GIS Cut Line= 3
      2441422.98     13554390.95      2440854.43     13553553.32
      2439921.27     13552594.11
#Sta/Elev= 30
  3942.2  314.18  4262.8  308.41  4319.7  303.92  4391.6   301.3  4686.6  296.52
  4837.8  290.69  4935.1  295.58  4945.6  295.84  4950.5  292.11  4956.9  292.11
  4960.1  289.25  4995.3  285.89  5030.6  286.91  5073.2     289  5101.5  294.01
  5115.7  289.31  5115.8  285.35  5116.3  284.85  5129.4  285.35  5136.8  289.22
  5186.4  289.38  5235.8  295.77  5702.6  294.27  5991.9  299.53  6162.3  303.43
  6183.4  307.36  6204.7  308.22    6233  307.55  6247.2  304.55  6292.8  306.63
#Mann= 6 ,-1 , 0
  3942.2     .04       0  4935.1     .05       0  5030.6     .04       0
  5115.8     .05       0  5129.4     .04       0  5991.9    .013       0
Bank Sta=5115.8,5129.4
XS Rating Curve= 0 ,0
Exp/Cntr=0.3,0.1

Type RM Length L Ch R = 1 ,2916    ,419,419,419
BEGIN DESCRIPTION:
TRIB 6 TO YORKTOWN CREEK 4.0
END DESCRIPTION:
XS GIS Cut Line= 3
      2441525.02     13553925.04        2441325.       13553425.
        2440225.       13552325.
#Sta/Elev= 30
  4456.9  306.09  4574.1  303.03  4693.9  298.23  4878.3  292.91  4932.2  290.36
    4951  288.79  4973.9  288.11  4980.7  286.64  5002.8  285.53  5003.3  285.03
    5016  285.03  5016.5  285.53  5032.6  286.11    5052  286.04  5080.7  287.29
  5136.9     291    5250  294.65  5617.7  293.21  5815.7  293.33  5872.3  291.32
  6070.3   295.1  6084.4   294.8  6282.4   300.2  6314.6  300.23    6358  301.23
    6441  302.74  6494.5  304.12  6508.7  305.71  6522.8  308.23  6551.1  308.39
#Mann= 8 ,-1 , 0
  4456.9     .04       0  5002.8     .04       0  5016.5     .04       0
  5032.6      .1       0  5080.7     .04       0  6314.6    .013       0
    6358     .04       0    6441    .013       0
Bank Sta=5002.8,5016.5
XS Rating Curve= 0 ,0
Exp/Cntr=0.3,0.1

Type RM Length L Ch R = 1 ,2497    ,406,406,406
BEGIN DESCRIPTION:
TRIB 6 TO YORKTOWN CREEK 3.0
END DESCRIPTION:
XS GIS Cut Line= 3
      2441825.01     13553475.01        2441775.       13553425.
      2440574.99     13552224.99
#Sta/Elev= 30
  4858.7   296.6    4887  296.18  4901.1  293.55  4915.3  288.99  4925.9  286.59
    4933  286.59  4943.6  284.65  4957.7  283.68    4986  284.36  4993.3  283.21
  4993.8  282.71    5007  283.21  5014.3  284.75  5056.7  285.84  5113.3  289.13
  5207.2  291.78  5262.8  292.88  5410.3  294.01    5700  292.03  5753.1  291.89
    5829  291.75  5905.2  291.79  6018.4   290.3  6074.9  292.05  6129.6  292.69
  6288.5  294.95  6513.3  299.28  6555.8  299.34  6569.9  300.32  6626.5  301.36
#Mann= 10 ,-1 , 0
  4858.7     .04       0  4993.3     .04       0    5007     .04       0
  5207.2      .1       0  5262.8     .04       0    5700     .05       0
  5753.1     .04       0    5829     .05       0  6129.6     .04       0
  6288.5     .12       0
Bank Sta=4993.3,5007
XS Rating Curve= 0 ,0
Exp/Cntr=0.3,0.1

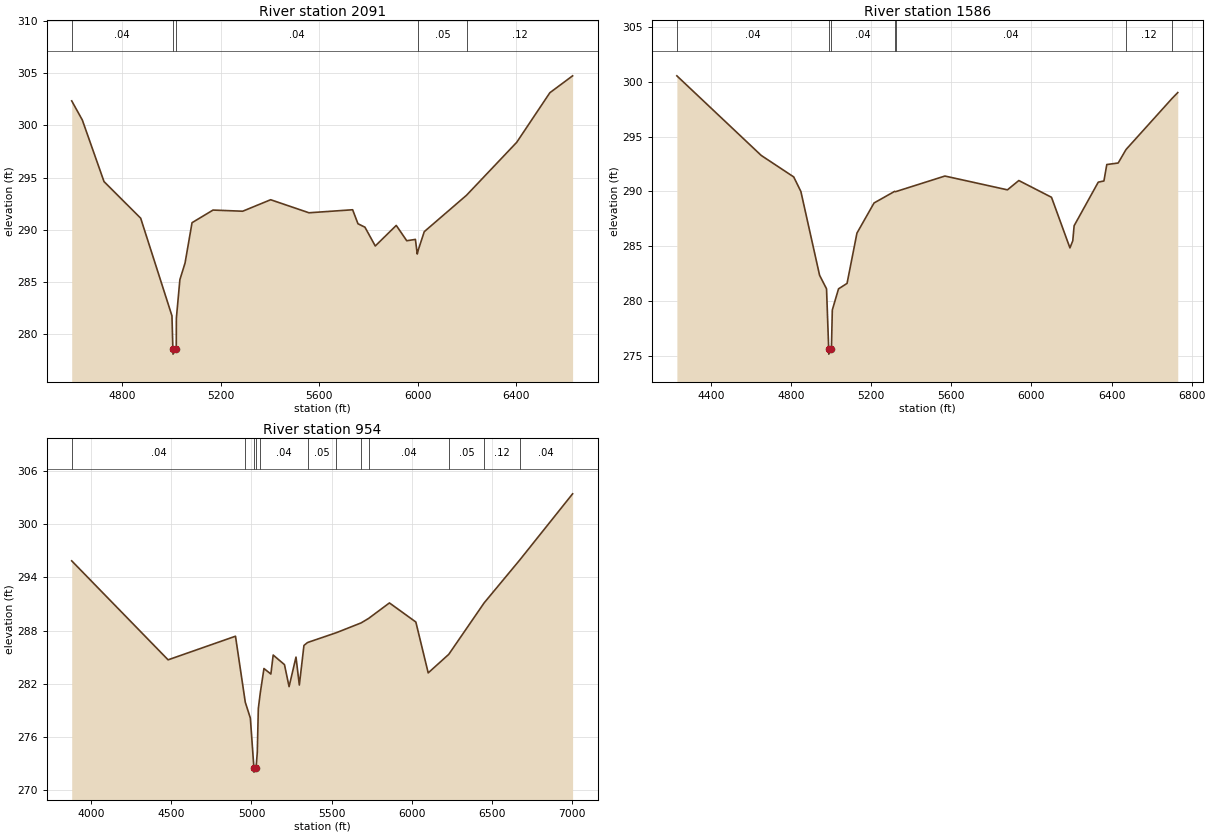
Type RM Length L Ch R = 1 ,2091    ,505,505,505
BEGIN DESCRIPTION:
TRIB 6 TO YORKTOWN CREEK 2.0
END DESCRIPTION:
XS GIS Cut Line= 3
        2442025.     13553525.02        2441975.       13553125.
      2440775.01     13552025.01
#Sta/Elev= 30
  4596.6  302.34  4639.4  300.52  4727.6  294.61  4876.3   291.1  5003.1  281.75
  5006.8  278.58  5007.3  278.08  5020.5  278.58    5021  281.53  5035.2  285.21
  5056.2  286.81  5084.5  290.67  5169.6  291.88  5289.9  291.77  5403.3  292.87
  5558.7  291.62  5735.7  291.91  5757.3  290.57  5785.6  290.24  5827.5  288.44
  5912.6  290.41  5955.2  288.94  5990.3  289.07  5997.7  287.67  6002.1  288.08
  6026.1  289.81  6197.5   293.3    6401  298.37  6535.4  303.12  6627.6  304.74
#Mann= 5 ,-1 , 0
  4596.6     .04       0  5006.8     .04       0  5020.5     .04       0
  6002.1     .05       0  6197.5     .12       0
Bank Sta=5006.8,5020.5
XS Rating Curve= 0 ,0
Exp/Cntr=0.3,0.1

Type RM Length L Ch R = 1 ,1586    ,632,632,632
BEGIN DESCRIPTION:
TRIB 6 TO YORKTOWN CREEK 1.0
END DESCRIPTION:
XS GIS Cut Line= 3
      2442152.16     13553779.05      2442464.68     13553067.21
      2441174.99     13551924.99
#Sta/Elev= 30
  4230.5  300.56  4651.7  293.29  4813.7  291.33  4849.5     290  4942.9  282.35
  4977.6  281.11  4988.3  275.65  4988.8  275.15    5002  275.65  5006.4  279.18
  5037.4  281.11    5080  281.61  5129.4   286.2  5214.7  288.95  5317.4  290.01
  5321.8  289.98  5568.5  291.41  5880.5  290.15  5937.4     291  6100.5  289.47
  6192.5  284.85  6206.7   285.5  6213.4  286.87  6333.8  290.85  6362.2  290.96
  6376.5  292.46  6433.3   292.6  6472.5  293.83  6701.5  298.48  6730.7  299.03
#Mann= 7 ,-1 , 0
  4230.5     .04       0  4988.3     .04       0    5002     .04       0
  5317.4     .05       0  5321.8     .04       0  6472.5     .12       0
  6701.5     .04       0
Bank Sta=4988.3,5002
XS Rating Curve= 0 ,0
Exp/Cntr=0.3,0.1

Type RM Length L Ch R = 1 ,954     ,0,0,0
BEGIN DESCRIPTION:
4863
END DESCRIPTION:
XS GIS Cut Line= 4
      2442284.46     13553564.83      2443027.56     13552889.29
      2442325.01      13552328.6      2441340.04     13551599.99
#Sta/Elev= 30
  3877.2  295.86  4479.2  284.71  4900.1  287.37  4961.3  279.93    4993  278.14
    5015  272.56  5015.5  272.06  5028.7  272.56  5036.3   274.3  5042.7  279.22
    5055  280.99  5077.9  283.73  5121.1  283.11  5135.5  285.25    5206  284.17
  5234.8  281.69    5278  285.02  5298.8  281.87  5327.7  286.33  5350.1  286.66
  5530.4  287.77  5684.9  288.87  5731.1  289.37  5861.6  291.12  6026.5  288.97
  6103.7  283.24  6232.2  285.33  6453.3  291.13  6674.7  295.94  7005.5  303.41
#Mann= 12 ,-1 , 0
  3877.2     .04       0  4961.3     .05       0    5015     .05       0
  5028.7     .05       0    5055     .04       0  5350.1     .05       0
  5530.4     .04       0  5684.9     .05       0  5731.1     .04       0
  6232.2     .05       0  6453.3     .12       0  6674.7     .04       0
Bank Sta=5015,5028.7
XS Rating Curve= 0 ,0
Exp/Cntr=0.3,0.1

Chan Stop Cuts=-1
Use User Specified Reach Order=0
Composite Channel Slope=5