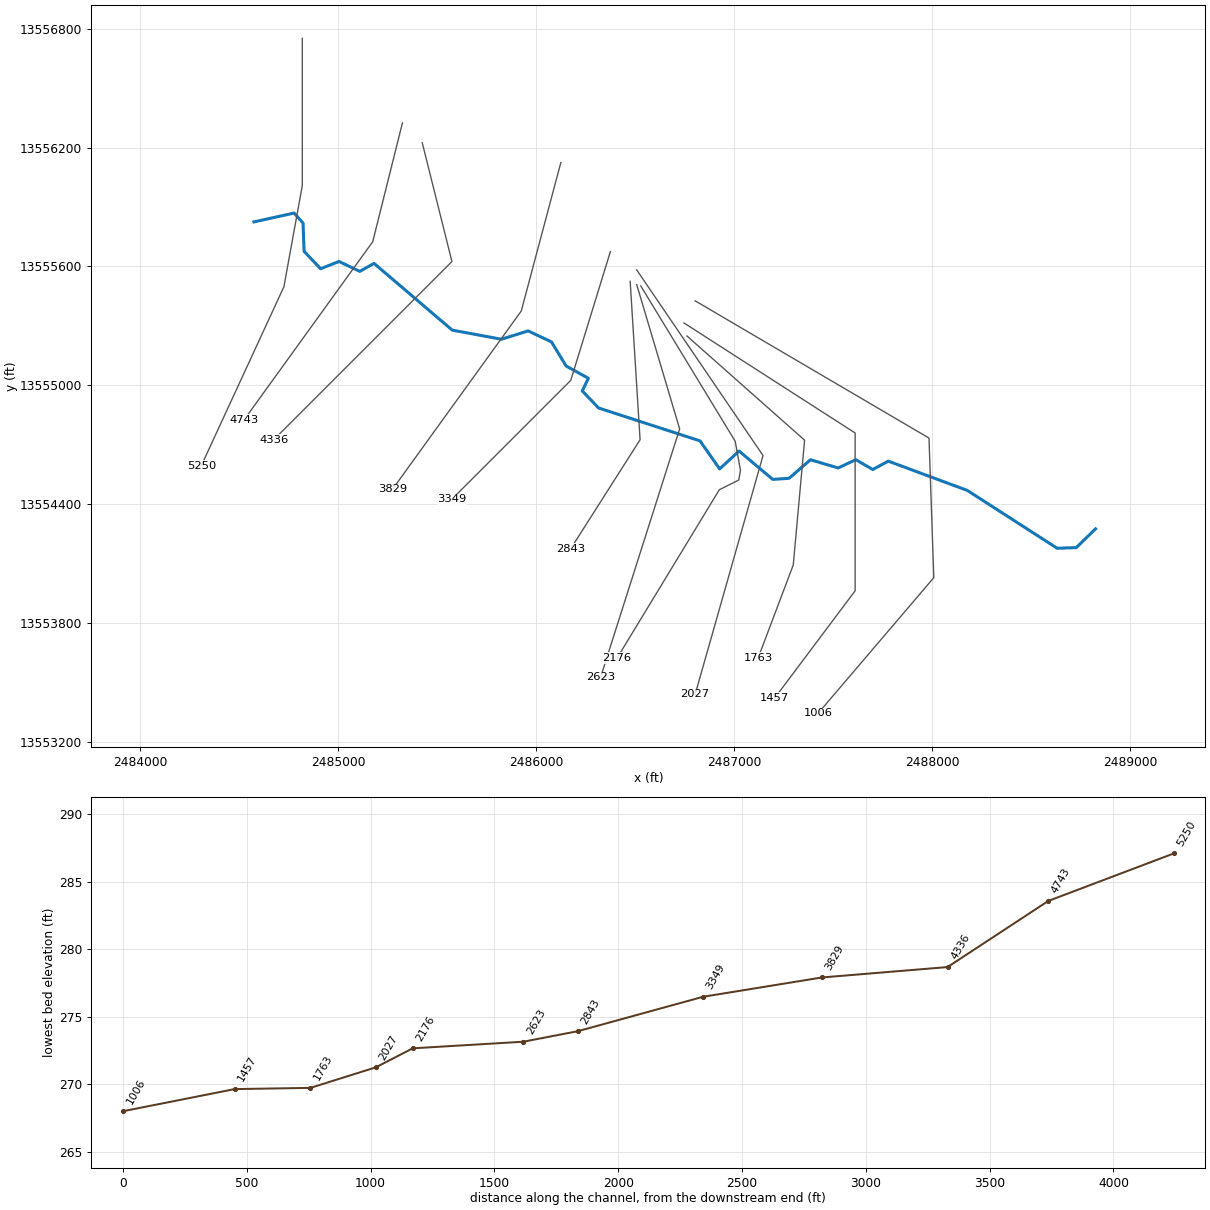
--- TRIB 6_1 TO FIVEMILE CREEK.prj (project) ---

Proj Title=TRIB 6_1 TO FIVEMILE CREEK Base Level Engineering
Current Plan=p01
Default Exp/Contr=0.3,0.1
English Units
Geom File=g01
Flow File=f01
Plan File=p01
BEGIN DESCRIPTION:
TRIB 6_1 TO FIVEMILE CREEK
END DESCRIPTION:

--- TRIB 6_1 TO FIVEMILE CREEK.p01 (plan) ---

Plan Title=Multiple Run
Short Identifier=Multiple
Geom File=g01
Flow File=f01
Subcritical Flow
K Sum by GR= 0
Std Step Tol= 0.01
Critical Tol= 0.01
Num of Std Step Trials= 20
Max Error Tol= 0.3
Flow Tol Ratio= 0.001
Split Flow NTrial= 30
Split Flow Tol= 0.02
Split Flow Ratio= 0.02
Log Output Level= 0
Friction Slope Method= 1
Unsteady Friction Slope Method= 2
Unsteady Bridges Friction Slope Method= 1
Parabolic Critical Depth
Global Vel Dist=  1 , 1 , 1
Global Log Level= 0
CheckData=True
Encroach Param= -1, 0, 0, 0
BEGIN DESCRIPTION:
Multiple Run
END DESCRIPTION:

--- TRIB 6_1 TO FIVEMILE CREEK.f01 (steady flow) ---

Flow Title=Multiple
Number of Profiles=7
Profile Names=10-year,25-year,50-year,1pct_min,100-year,1pct_plu,500-year
River Rch & RM= TRIB 6_1 TO FIVE,Reach-1,5250
     409     643     848     543    1084    2164    1753
River Rch & RM= TRIB 6_1 TO FIVE,Reach-1,2843
     575     921    1231     797    1590    3173    2628
Boundary for River Rch & Prof#=TRIB 6_1 TO FIVE,Reach-1,1
Up Type=0
Dn Type=3
Dn Slope=0.005
Boundary for River Rch & Prof#=TRIB 6_1 TO FIVE,Reach-1,2
Up Type=0
Dn Type=3
Dn Slope=0.005
Boundary for River Rch & Prof#=TRIB 6_1 TO FIVE,Reach-1,3
Up Type=0
Dn Type=3
Dn Slope=0.005
Boundary for River Rch & Prof#=TRIB 6_1 TO FIVE,Reach-1,4
Up Type=0
Dn Type=3
Dn Slope=0.005
Boundary for River Rch & Prof#=TRIB 6_1 TO FIVE,Reach-1,5
Up Type=0
Dn Type=3
Dn Slope=0.005
Boundary for River Rch & Prof#=TRIB 6_1 TO FIVE,Reach-1,6
Up Type=0
Dn Type=3
Dn Slope=0.005
Boundary for River Rch & Prof#=TRIB 6_1 TO FIVE,Reach-1,7
Up Type=0
Dn Type=3
Dn Slope=0.005

--- TRIB 6_1 TO FIVEMILE CREEK.g01 (geometry) ---

Geom Title=Existing Conditions

River Reach=TRIB 6_1 TO FIVE,Reach-1
Reach XY= 30
      2484575.00     13555825.00      2484777.71     13555869.72
      2484823.02     13555819.35      2484828.54     13555676.44
      2484911.59     13555588.53      2485004.80     13555625.19
      2485109.66     13555575.23      2485181.61     13555615.57
      2485576.46     13555278.54      2485825.00     13555232.56
      2485959.73     13555274.63      2486077.55     13555219.27
      2486151.18     13555097.87      2486263.89     13555035.32
      2486233.00     13554971.66      2486315.17     13554885.52
      2486827.55     13554719.27      2486926.79     13554577.86
      2487024.80     13554667.98      2487195.06     13554524.78
      2487277.42     13554530.41      2487385.49     13554624.05
      2487525.01     13554582.60      2487614.30     13554624.16
      2487700.03     13554574.70      2487778.31     13554616.93
      2488177.29     13554469.15      2488630.97     13554177.14
      2488727.45     13554180.33      2488825.00     13554275.00

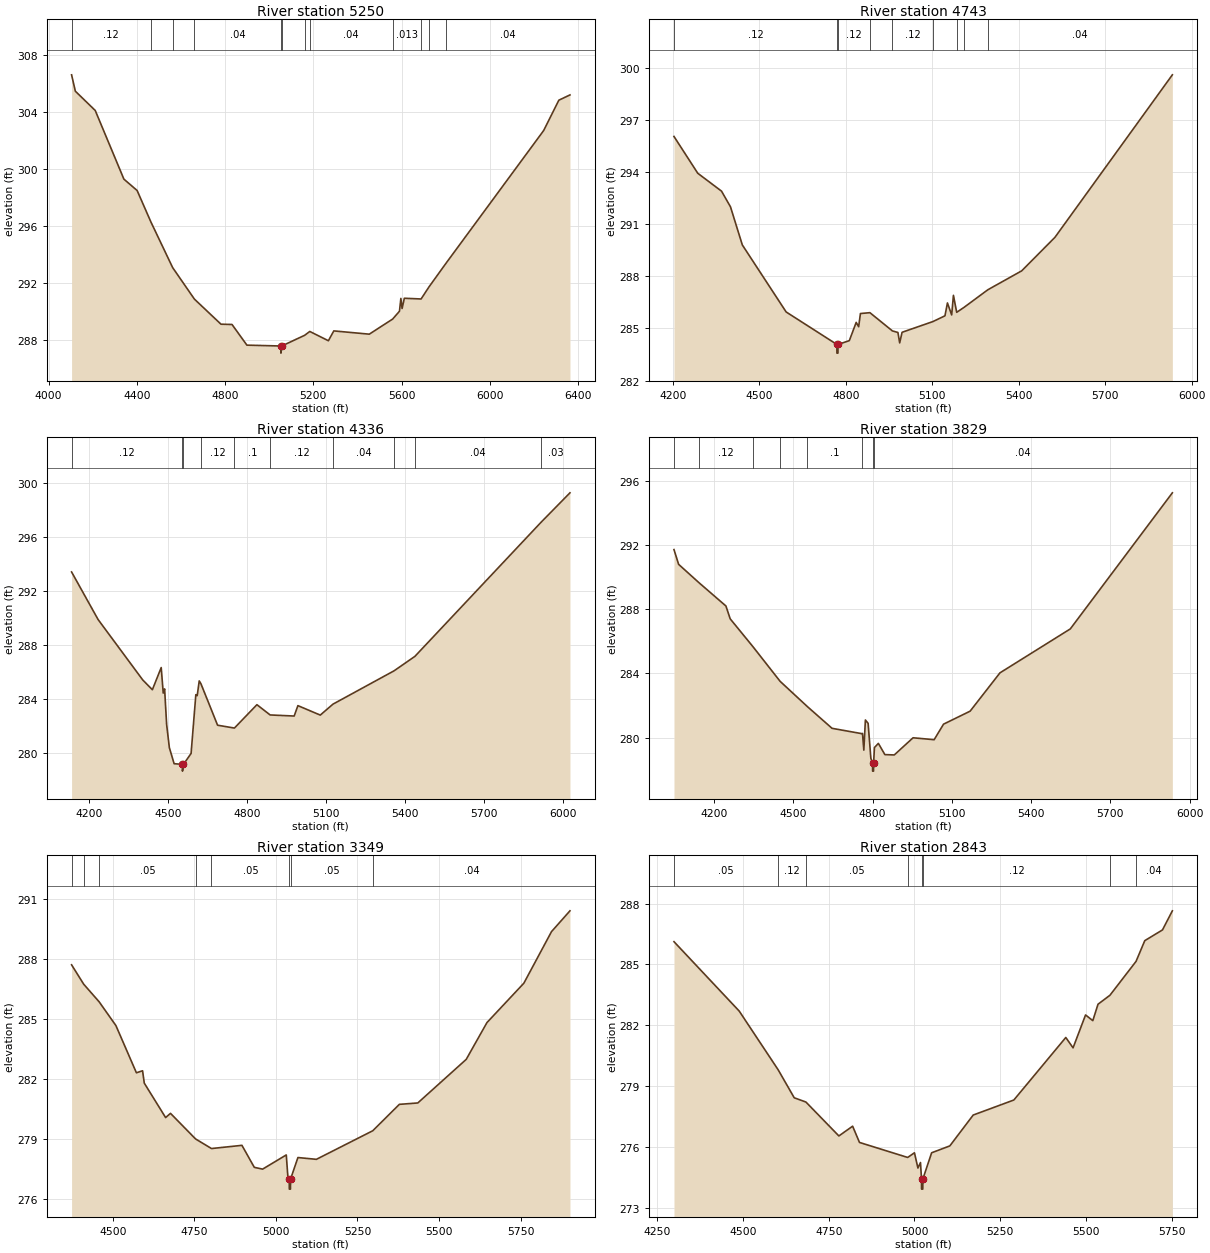
Type RM Length L Ch R = 1,5250,507,507,507
BEGIN DESCRIPTION:
Mapping XS f565a2fd
END DESCRIPTION:
XS GIS Cut Line= 4
      2484819.45     13556752.05      2484819.45     13556008.73
      2484726.54     13555497.69      2484309.21     13554593.49
#Sta/Elev= 30
  4104.3  306.63  4121.4  305.48  4211.4  304.13  4341.4  299.31  4401.4  298.51
  4463.9  296.30  4562.4  293.10  4661.0  290.89  4781.4  289.13  4831.4  289.11
  4898.8  287.66  5052.7  287.60  5052.9  287.10  5056.7  287.60  5160.4  288.35
  5183.8  288.62  5268.1  287.97  5292.7  288.66  5453.4  288.43  5559.3  289.49
  5590.3  290.04  5596.6  290.94  5602.1  290.23  5612.3  290.95  5688.2  290.90
  5724.1  291.75  5801.3  293.41  6243.7  302.72  6312.5  304.85  6362.9  305.22
#Mann=12,-1,0
  4104.3    0.12       0  4463.9    0.04       0  4562.4    0.12       0
  4661.0    0.04       0  5052.7    0.04       0  5056.7    0.04       0
  5160.4    0.12       0  5183.8    0.04       0  5559.3   0.013       0
  5688.2    0.04       0  5724.1   0.013       0  5801.3    0.04       0
Bank Sta=5052.7,5056.7
Exp/Cntr=0.3,0.1

Type RM Length L Ch R = 1,4743,407,407,407
BEGIN DESCRIPTION:
TRIB 6_1 TO FIVEMILE CREEK 8.0
END DESCRIPTION:
XS GIS Cut Line= 3
      2485325.01     13556325.02      2485175.00     13555725.00
      2484524.98     13554824.98
#Sta/Elev= 30
  4204.4  296.06  4286.9  293.94  4369.3  292.91  4400.3  292.01  4441.5  289.81
  4593.5  285.95  4769.4  284.08  4769.6  283.58  4773.1  283.58  4773.4  284.08
  4812.6  284.30  4836.4  285.35  4845.0  285.10  4851.1  285.86  4884.0  285.91
  4962.0  284.86  4981.1  284.77  4987.3  284.17  4995.6  284.78  5102.9  285.40
  5144.3  285.73  5152.9  286.47  5167.6  285.78  5173.7  286.91  5185.0  285.93
  5210.8  286.22  5293.1  287.23  5410.5  288.32  5525.8  290.25  5933.1  299.61
#Mann=9,-1,0
  4204.4    0.12       0  4769.4    0.05       0  4773.4    0.12       0
  4884.0     0.1       0  4962.0    0.12       0  5102.9    0.04       0
  5185.0   0.013       0  5210.8    0.05       0  5293.1    0.04       0
Bank Sta=4769.4,4773.4
Exp/Cntr=0.3,0.1

Type RM Length L Ch R = 1,4336,507,507,507
BEGIN DESCRIPTION:
TRIB 6_1 TO FIVEMILE CREEK 7.0
END DESCRIPTION:
XS GIS Cut Line= 3
      2485425.01     13556224.96      2485575.00     13555625.00
      2484675.01     13554725.01
#Sta/Elev= 30
  4134.1  293.43  4234.6  289.91  4404.6  285.42  4440.7  284.71  4474.2  286.35
  4481.9  284.46  4487.1  284.77  4494.8  282.13  4505.1  280.42  4523.2  279.23
  4554.7  279.18  4554.9  278.68  4558.7  279.18  4587.6  279.99  4605.6  284.34
  4610.8  284.27  4618.5  285.36  4625.0  285.15  4688.1  282.08  4752.0  281.87
  4837.4  283.60  4887.6  282.84  4978.8  282.76  4992.9  283.53  5077.8  282.83
  5126.0  283.64  5358.0  286.11  5437.0  287.18  5915.6  297.11  6025.3  299.29
#Mann=10,-1,0
  4134.1    0.12       0  4554.7    0.05       0  4558.7    0.12       0
  4625.0    0.12       0  4752.0     0.1       0  4887.6    0.12       0
  5126.0    0.04       0  5358.0    0.05       0  5437.0    0.04       0
  5915.6    0.03       0
Bank Sta=4554.7,4558.7
Exp/Cntr=0.3,0.1

Type RM Length L Ch R = 1,3829,480,480,480
BEGIN DESCRIPTION:
TRIB 6_1 TO FIVEMILE CREEK 6.0
END DESCRIPTION:
XS GIS Cut Line= 3
      2486125.00     13556124.99      2485925.00     13555375.00
      2485274.99     13554474.98
#Sta/Elev= 30
  4048.6  291.73  4066.1  290.81  4142.1  289.68  4245.2  288.21  4261.4  287.41
  4347.6  285.67  4450.4  283.51  4553.2  281.94  4646.9  280.58  4758.8  280.25
  4762.1  280.26  4767.2  279.22  4773.1  281.10  4783.4  280.89  4793.8  278.71
  4800.2  278.41  4800.4  277.91  4803.9  277.91  4804.2  278.41  4807.3  279.38
  4822.2  279.64  4846.9  278.94  4882.4  278.92  4953.6  279.99  5033.3  279.87
  5068.9  280.84  5169.5  281.65  5282.4  284.04  5548.6  286.78  5935.0  295.27
#Mann=8,-1,0
  4048.6    0.05       0  4142.1    0.12       0  4347.6    0.04       0
  4450.4    0.12       0  4553.2     0.1       0  4758.8    0.04       0
  4800.2    0.04       0  4804.2    0.04       0
Bank Sta=4800.2,4804.2
Exp/Cntr=0.3,0.1

Type RM Length L Ch R = 1,3349,506,506,506
BEGIN DESCRIPTION:
TRIB 6_1 TO FIVEMILE CREEK 5.0
END DESCRIPTION:
XS GIS Cut Line= 3
      2486374.99     13555674.97      2486175.00     13555025.00
      2485574.98     13554424.98
#Sta/Elev= 30
  4373.1  287.70  4410.3  286.73  4457.6  285.85  4509.1  284.66  4571.9  282.30
  4590.8  282.40  4596.1  281.78  4661.5  280.06  4676.5  280.27  4753.4  278.99
  4802.2  278.51  4895.6  278.67  4933.5  277.57  4959.0  277.48  5031.6  278.19
  5036.8  277.03  5040.7  276.98  5040.9  276.48  5044.4  276.48  5044.7  276.98
  5067.3  278.06  5123.9  277.97  5296.9  279.40  5378.4  280.72  5435.0  280.79
  5583.5  282.97  5647.1  284.81  5760.3  286.78  5845.1  289.36  5901.7  290.40
#Mann=8,-1,0
  4373.1    0.05       0  4410.3    0.12       0  4457.6    0.05       0
  4753.4     0.1       0  4802.2    0.05       0  5040.7    0.05       0
  5044.7    0.05       0  5296.9    0.04       0
Bank Sta=5040.7,5044.7
Exp/Cntr=0.3,0.1

Type RM Length L Ch R = 1,2843,220,220,220
BEGIN DESCRIPTION:
TRIB 6_1 TO FIVEMILE CREEK 4.0
END DESCRIPTION:
XS GIS Cut Line= 3
      2486475.00     13555524.97      2486525.00     13554725.00
      2486174.97     13554174.96
#Sta/Elev= 30
  4298.6  286.12  4488.9  282.70  4602.4  279.81  4649.3  278.43  4683.4  278.22
  4779.5  276.55  4819.6  277.03  4839.6  276.23  4980.2  275.49  4999.9  275.72
  5010.0  274.97  5017.5  275.24  5020.5  274.43  5020.7  273.93  5024.2  273.93
  5024.5  274.43  5050.0  275.72  5103.1  276.06  5171.3  277.58  5289.8  278.32
  5441.3  281.40  5462.5  280.89  5498.9  282.51  5520.1  282.23  5535.3  283.04
  5570.0  283.48  5646.2  285.15  5671.6  286.17  5723.3  286.70  5752.1  287.64
#Mann=8,-1,0
  4298.6    0.05       0  4602.4    0.12       0  4683.4    0.05       0
  4980.2    0.12       0  5020.5    0.05       0  5024.5    0.12       0
  5570.0    0.05       0  5646.2    0.04       0
Bank Sta=5020.5,5024.5
Exp/Cntr=0.3,0.1

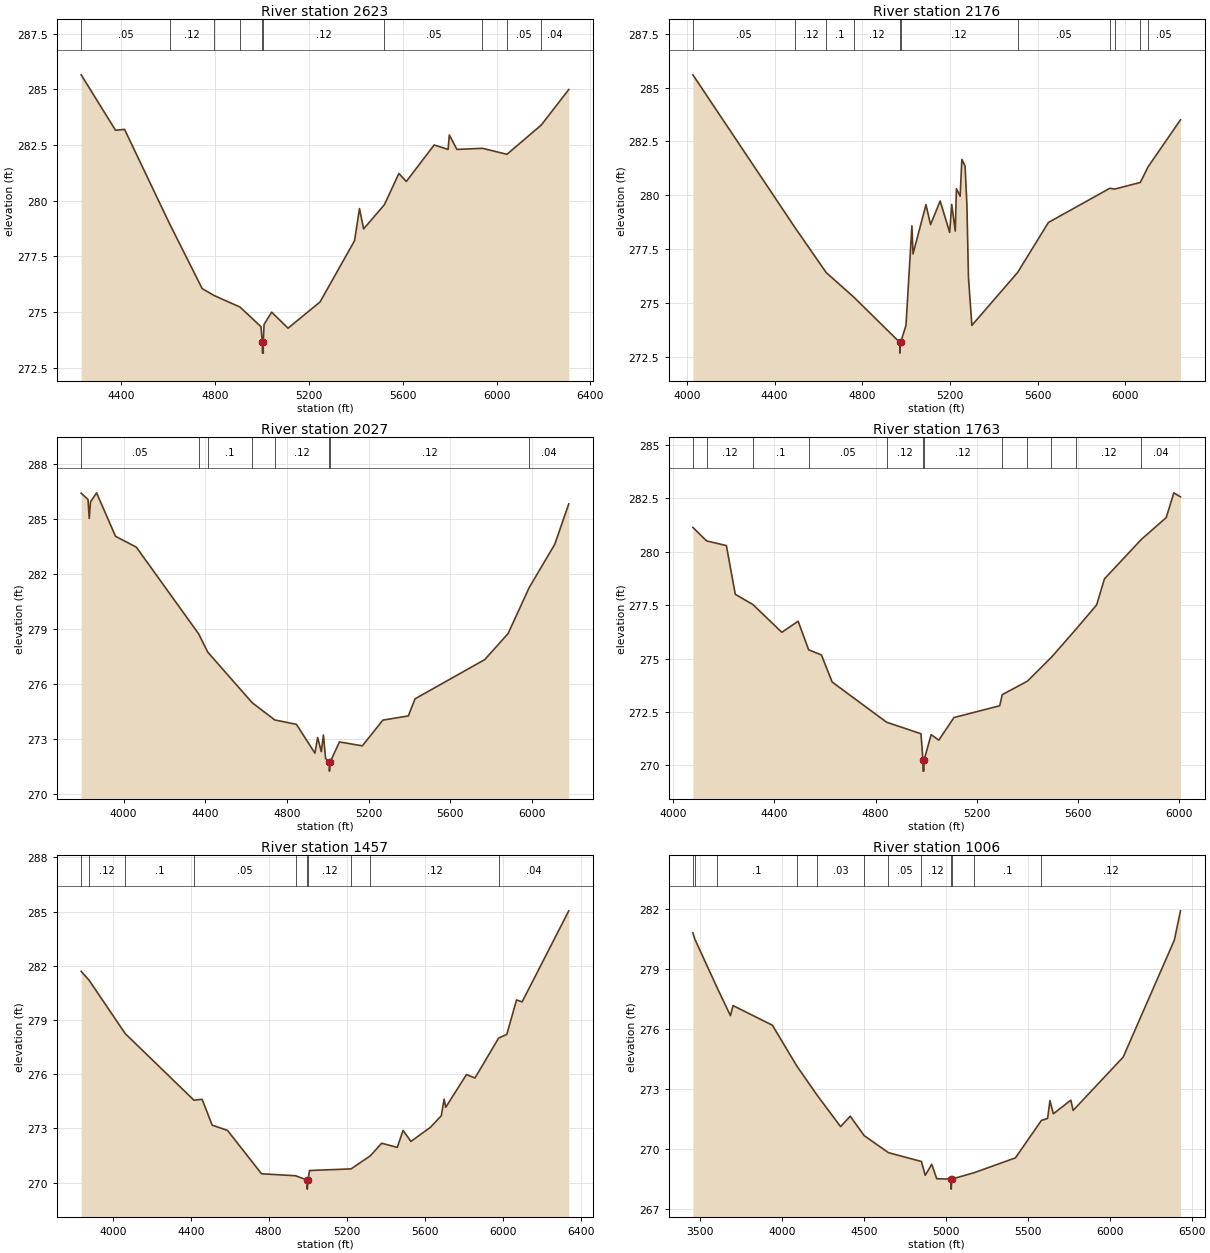
Type RM Length L Ch R = 1,2623,447,447,447
BEGIN DESCRIPTION:
Mapping XS 9913c2cd
END DESCRIPTION:
XS GIS Cut Line= 3
      2486507.84     13555508.97      2486724.85     13554779.81
      2486325.55     13553525.50
#Sta/Elev= 30
  4230.6  285.65  4377.0  283.16  4415.4  283.20  4607.3  278.96  4746.0  276.05
  4796.4  275.74  4907.2  275.22  4996.5  274.34  5002.5  273.65  5002.8  273.15
  5006.3  273.15  5006.5  273.65  5009.7  274.44  5042.0  274.99  5111.9  274.27
  5248.3  275.45  5395.2  278.20  5416.2  279.64  5433.9  278.73  5522.5  279.82
  5584.1  281.22  5615.6  280.86  5734.4  282.50  5793.6  282.30  5798.9  282.95
  5831.1  282.30  5940.0  282.35  6044.4  282.08  6190.2  283.39  6307.7  284.99
#Mann=10,-1,0
  4230.6    0.05       0  4607.3    0.12       0  4796.4    0.05       0
  4907.2    0.12       0  5002.5    0.05       0  5006.5    0.12       0
  5522.5    0.05       0  5940.0    0.12       0  6044.4    0.05       0
  6190.2    0.04       0
Bank Sta=5002.5,5006.5
Exp/Cntr=0.3,0.1

Type RM Length L Ch R = 1,2176,149,149,149
BEGIN DESCRIPTION:
4864
END DESCRIPTION:
XS GIS Cut Line= 6
      2486528.40     13555501.91      2487005.28     13554717.51
      2487032.02     13554570.44      2487023.11     13554521.42
      2486925.06     13554472.40      2486409.04     13553622.74
#Sta/Elev= 30
  4027.9  285.59  4494.9  278.47  4635.9  276.40  4761.7  275.26  4971.1  273.16
  4971.3  272.66  4975.1  273.16  4999.3  273.95  5026.4  278.57  5031.5  277.27
  5090.5  279.56  5111.4  278.63  5155.2  279.73  5198.5  278.27  5207.9  279.57
  5224.1  278.33  5229.2  280.30  5246.3  279.95  5254.1  281.66  5268.7  281.35
  5277.0  279.58  5284.2  276.17  5299.7  273.95  5508.5  276.41  5648.6  278.73
  5928.9  280.32  5950.3  280.28  6067.6  280.59  6102.7  281.31  6250.7  283.50
#Mann=11,-1,0
  4027.9    0.05       0  4494.9    0.12       0  4635.9     0.1       0
  4761.7    0.12       0  4971.1    0.05       0  4975.1    0.12       0
  5508.5    0.05       0  5928.9    0.12       0  5950.3    0.05       0
  6067.6    0.12       0  6102.7    0.05       0
Bank Sta=4971.1,4975.1
Exp/Cntr=0.3,0.1

Type RM Length L Ch R = 1,2027,264,264,264
BEGIN DESCRIPTION:
Mapping XS 867b32c2
END DESCRIPTION:
XS GIS Cut Line= 3
      2486507.83     13555582.77      2487145.85     13554645.26
      2486803.16     13553439.33
#Sta/Elev= 30
  3791.9  286.40  3825.4  286.06  3831.4  285.02  3837.6  285.93  3867.3  286.42
  3960.2  284.05  4061.9  283.46  4367.4  278.73  4411.5  277.74  4629.3  274.98
  4739.9  274.04  4846.0  273.80  4936.6  272.23  4949.8  273.08  4967.8  272.31
  4978.2  273.22  4988.8  271.94  5007.4  271.75  5007.6  271.25  5011.4  271.75
  5056.6  272.84  5168.7  272.63  5269.3  274.03  5394.0  274.26  5426.7  275.19
  5768.3  277.33  5882.6  278.75  5985.6  281.25  6111.3  283.62  6179.6  285.82
#Mann=8,-1,0
  3791.9    0.05       0  4367.4    0.12       0  4411.5     0.1       0
  4629.3    0.05       0  4739.9    0.12       0  5007.4    0.05       0
  5011.4    0.12       0  5985.6    0.04       0
Bank Sta=5007.4,5011.4
Exp/Cntr=0.3,0.1

Type RM Length L Ch R = 1,1763,306,306,306
BEGIN DESCRIPTION:
Mapping XS 2afdc410
END DESCRIPTION:
XS GIS Cut Line= 4
      2486761.97     13555248.79      2487355.75     13554722.72
      2487298.46     13554092.51      2487121.37     13553623.76
#Sta/Elev= 30
  4078.1  281.14  4132.2  280.51  4210.5  280.29  4245.7  278.01  4315.3  277.53
  4429.7  276.23  4494.1  276.75  4535.7  275.41  4586.1  275.17  4628.7  273.90
  4843.8  272.02  4979.6  271.48  4987.6  270.23  4987.9  269.73  4991.4  269.73
  4991.6  270.23  5019.7  271.44  5050.1  271.18  5110.1  272.24  5290.8  272.79
  5300.8  273.31  5400.0  273.94  5494.4  275.05  5594.2  276.40  5673.8  277.51
  5704.7  278.73  5850.7  280.58  5948.9  281.60  5979.1  282.76  6005.3  282.57
#Mann=12,-1,0
  4078.1    0.05       0  4132.2    0.12       0  4315.3     0.1       0
  4535.7    0.05       0  4843.8    0.12       0  4987.6    0.05       0
  4991.6    0.12       0  5300.8    0.05       0  5400.0    0.12       0
  5494.4    0.05       0  5594.2    0.12       0  5850.7    0.04       0
Bank Sta=4987.6,4991.6
Exp/Cntr=0.3,0.1

Type RM Length L Ch R = 1,1457,451,451,451
BEGIN DESCRIPTION:
4865
END DESCRIPTION:
XS GIS Cut Line= 4
      2486746.76     13555314.72      2487610.96     13554759.18
      2487610.96     13553962.30      2487204.72     13553420.65
#Sta/Elev= 30
  3838.1  281.69  3878.1  281.21  4063.8  278.25  4416.8  274.56  4458.6  274.61
  4510.1  273.18  4588.7  272.89  4763.3  270.49  4938.1  270.38  4997.6  270.14
  4997.9  269.64  5001.6  270.14  5009.6  270.67  5222.6  270.76  5321.2  271.48
  5379.6  272.18  5459.6  271.95  5489.6  272.89  5529.6  272.28  5629.6  273.06
  5685.4  273.70  5700.0  274.62  5708.3  274.17  5814.6  275.98  5858.3  275.79
  5979.6  278.00  6021.5  278.20  6071.5  280.11  6100.0  280.00  6339.4  285.04
#Mann=10,-1,0
  3838.1    0.05       0  3878.1    0.12       0  4063.8     0.1       0
  4416.8    0.05       0  4938.1    0.12       0  4997.6    0.05       0
  5001.6    0.12       0  5222.6    0.05       0  5321.2    0.12       0
  5979.6    0.04       0
Bank Sta=4997.6,5001.6
Exp/Cntr=0.3,0.1

Type RM Length L Ch R = 1,1006,0,0,0
BEGIN DESCRIPTION:
TRIB 6_1 TO FIVEMILE CREEK 1.0
END DESCRIPTION:
XS GIS Cut Line= 4
      2486803.04     13555426.58      2487983.88     13554733.48
      2488008.18     13554028.62      2487423.74     13553343.27
#Sta/Elev= 30
  3456.8  280.79  3469.2  280.47  3606.5  278.02  3686.1  276.66  3701.8  277.16
  3942.1  276.18  4090.0  274.16  4212.1  272.72  4358.2  271.12  4416.9  271.64
  4502.0  270.67  4650.2  269.82  4851.2  269.38  4874.5  268.69  4914.5  269.24
  4944.6  268.52  5032.6  268.50  5032.9  268.00  5036.6  268.50  5173.1  268.82
  5424.9  269.56  5583.5  271.43  5621.2  271.53  5635.5  272.42  5656.3  271.76
  5762.9  272.44  5777.1  271.93  6082.4  274.59  6394.2  280.42  6432.0  281.89
#Mann=12,-1,0
  3456.8    0.05       0  3469.2    0.12       0  3606.5     0.1       0
  4090.0    0.05       0  4212.1    0.03       0  4502.0    0.12       0
  4650.2    0.05       0  4851.2    0.12       0  5032.6    0.05       0
  5036.6    0.12       0  5173.1     0.1       0  5583.5    0.12       0
Bank Sta=5032.6,5036.6
Exp/Cntr=0.3,0.1

Chan Stop Cuts=-1