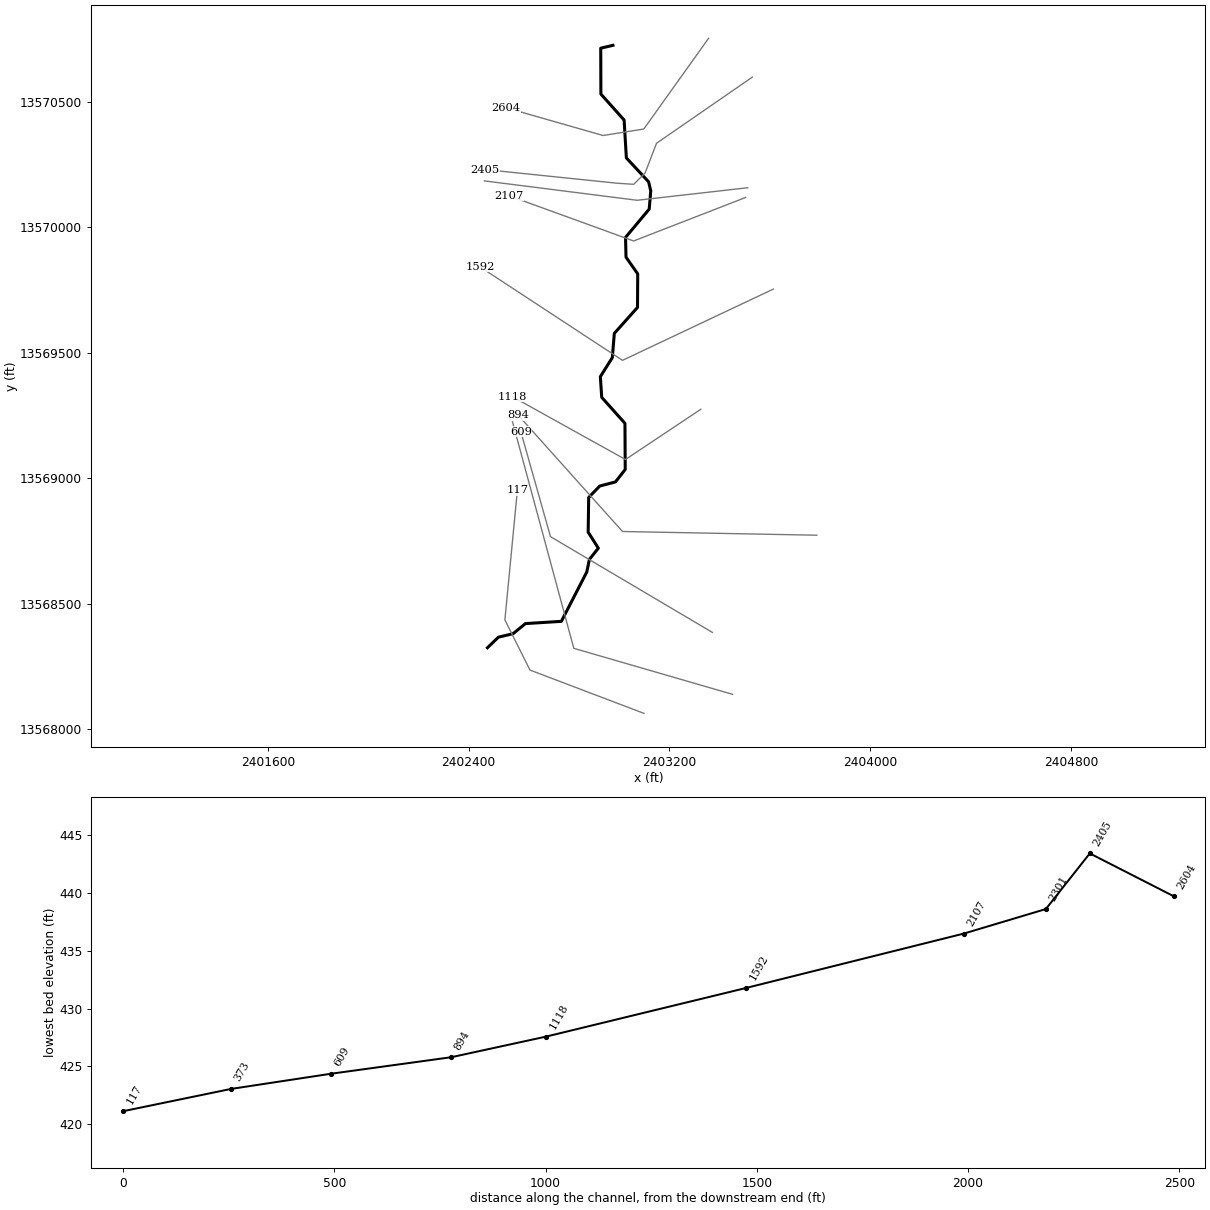
--- TRIB 6_1 TO THOMAS CREEK.prj (project) ---

Proj Title=TRIB 6_1 TO THOMAS CREEK Base Level Engineering
Current Plan=p01
Default Exp/Contr=0.3,0.1
English Units
Geom File=g01
Flow File=f01
Plan File=p01
BEGIN DESCRIPTION:
TRIB 6_1 TO THOMAS CREEK
END DESCRIPTION:

--- TRIB 6_1 TO THOMAS CREEK.p01 (plan) ---

Plan Title=Multiple Run
Short Identifier=Multiple
Geom File=g01
Flow File=f01
Subcritical Flow
K Sum by GR= 0
Std Step Tol= 0.01
Critical Tol= 0.01
Num of Std Step Trials= 20
Max Error Tol= 0.3
Flow Tol Ratio= 0.001
Split Flow NTrial= 30
Split Flow Tol= 0.02
Split Flow Ratio= 0.02
Log Output Level= 0
Friction Slope Method= 1
Unsteady Friction Slope Method= 2
Unsteady Bridges Friction Slope Method= 1
Parabolic Critical Depth
Global Vel Dist=  1 , 1 , 1
Global Log Level= 0
CheckData=True
Encroach Param= -1, 0, 0, 0
BEGIN DESCRIPTION:
Multiple Run
END DESCRIPTION:

--- TRIB 6_1 TO THOMAS CREEK.f01 (steady flow) ---

Flow Title=Multiple
Number of Profiles=7
Profile Names=10-year,25-year,50-year,1pct_min,100-year,1pct_plu,500-year
River Rch & RM= TRIB 6_1 TO THOM,Reach-1,2604
     410     652     867     560    1118    2230    1838
Boundary for River Rch & Prof#=TRIB 6_1 TO THOM,Reach-1,1
Up Type=0
Dn Type=3
Dn Slope=0.005
Boundary for River Rch & Prof#=TRIB 6_1 TO THOM,Reach-1,2
Up Type=0
Dn Type=3
Dn Slope=0.005
Boundary for River Rch & Prof#=TRIB 6_1 TO THOM,Reach-1,3
Up Type=0
Dn Type=3
Dn Slope=0.005
Boundary for River Rch & Prof#=TRIB 6_1 TO THOM,Reach-1,4
Up Type=0
Dn Type=3
Dn Slope=0.005
Boundary for River Rch & Prof#=TRIB 6_1 TO THOM,Reach-1,5
Up Type=0
Dn Type=3
Dn Slope=0.005
Boundary for River Rch & Prof#=TRIB 6_1 TO THOM,Reach-1,6
Up Type=0
Dn Type=3
Dn Slope=0.005
Boundary for River Rch & Prof#=TRIB 6_1 TO THOM,Reach-1,7
Up Type=0
Dn Type=3
Dn Slope=0.005

--- TRIB 6_1 TO THOMAS CREEK.g01 (geometry) ---

Geom Title=Existing Conditions

River Reach=TRIB 6_1 TO THOM,Reach-1
Reach XY= 30
      2402975.00     13570725.00      2402926.43     13570713.57
      2402927.06     13570530.86      2403019.52     13570427.44
      2403028.56     13570276.47      2403117.22     13570181.16
      2403125.68     13570145.07      2403119.59     13570072.58
      2403025.25     13569959.78      2403027.16     13569880.98
      2403073.79     13569814.49      2403072.94     13569680.86
      2402980.54     13569577.42      2402972.64     13569480.98
      2402924.90     13569404.90      2402930.41     13569322.58
      2403022.94     13569219.14      2403024.02     13569035.28
      2402985.04     13568985.63      2402922.45     13568969.25
      2402878.44     13568923.75      2402876.37     13568785.44
      2402916.96     13568721.68      2402881.39     13568677.29
      2402870.87     13568626.74      2402769.59     13568430.18
      2402626.56     13568421.25      2402577.22     13568381.03
      2402518.85     13568367.09      2402475.00     13568325.00

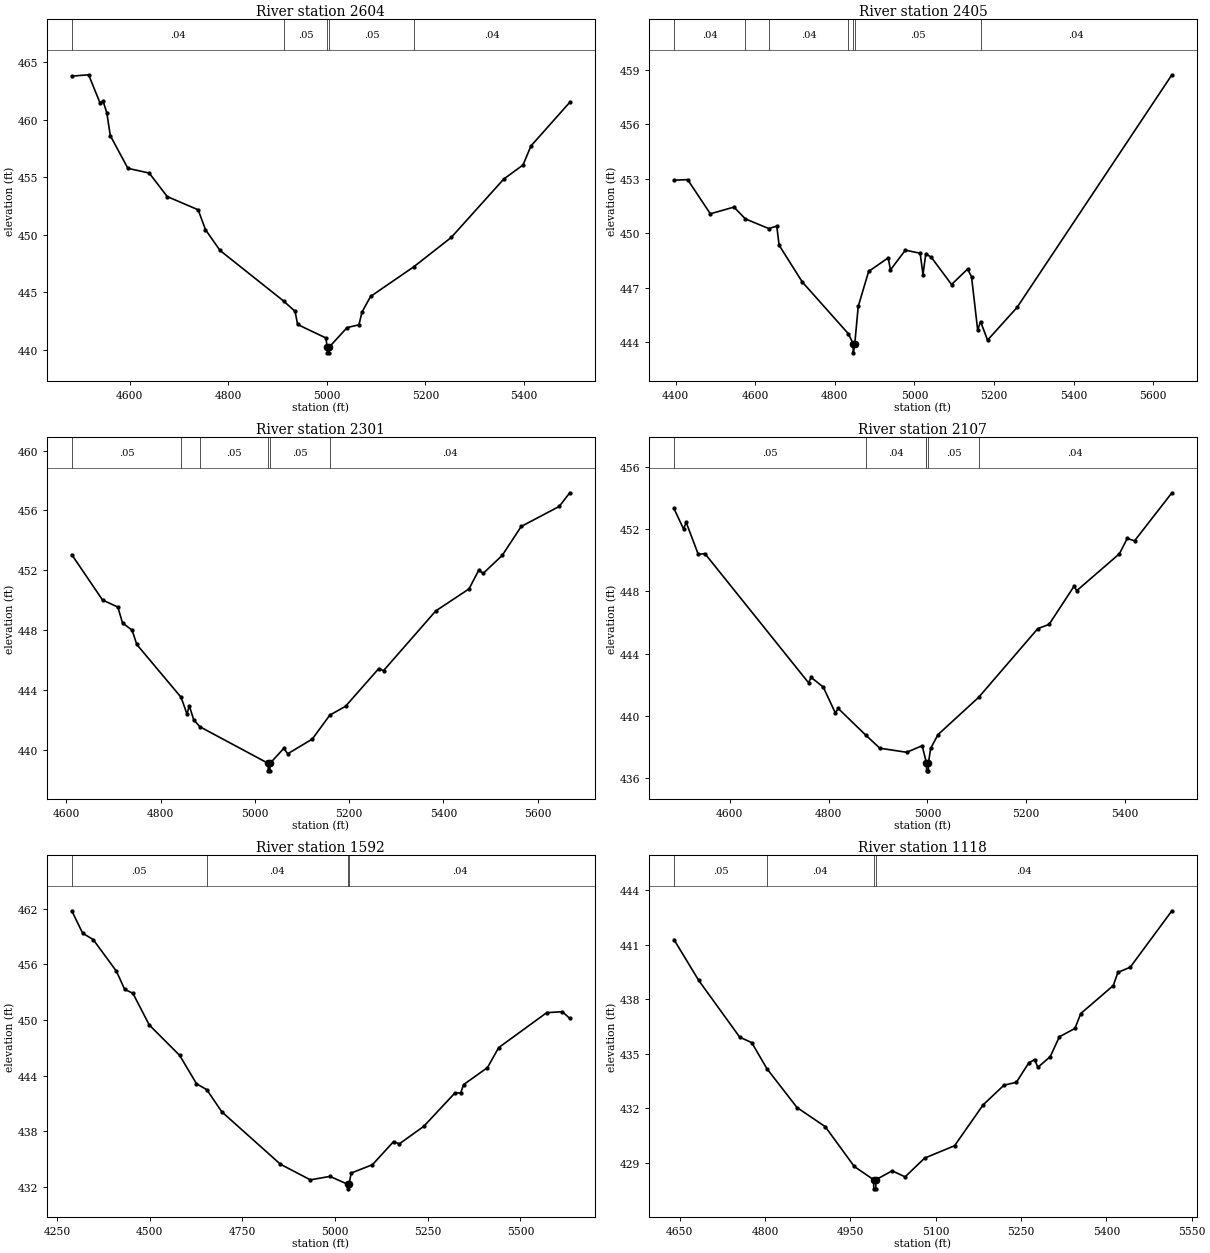
Type RM Length L Ch R = 1,2604,199,199,199
BEGIN DESCRIPTION:
Mapping XS a8f1e7cb
END DESCRIPTION:
XS GIS Cut Line= 4
      2403356.05     13570752.85      2403098.00     13570391.58
      2402935.81     13570365.78      2402549.37     13570476.19
#Sta/Elev= 30
  4482.5  463.81  4516.7  463.93  4539.8  461.48  4546.0  461.63  4553.6  460.62
  4560.7  458.63  4596.4  455.78  4639.6  455.37  4676.2  453.32  4738.9  452.17
  4753.7  450.44  4783.2  448.63  4912.3  444.22  4935.5  443.32  4940.6  442.18
  4997.7  441.01  5000.8  440.21  5001.1  439.71  5004.6  439.71  5004.8  440.21
  5040.9  441.91  5065.0  442.15  5071.3  443.27  5088.6  444.62  5176.1  447.20
  5252.2  449.76  5358.8  454.85  5397.8  456.07  5413.9  457.73  5492.6  461.53
#Mann=5,-1,0
  4482.5    0.04       0  4912.3    0.05       0  5000.8    0.05       0
  5004.8    0.05       0  5176.1    0.04       0
Bank Sta=5000.8,5004.8
Exp/Cntr=0.3,0.1

Type RM Length L Ch R = 1,2405,104,104,104
BEGIN DESCRIPTION:
4861
END DESCRIPTION:
XS GIS Cut Line= 6
      2403530.30     13570598.27      2403148.73     13570334.82
      2403103.31     13570216.71      2403057.88     13570171.28
      2402989.75     13570175.83      2402464.40     13570230.17
#Sta/Elev= 30
  4396.0  452.92  4430.5  452.95  4487.5  451.07  4546.8  451.44  4575.5  450.79
  4634.1  450.26  4654.3  450.39  4660.3  449.34  4718.4  447.32  4834.2  444.47
  4846.3  443.92  4846.5  443.42  4850.3  443.92  4858.9  445.97  4885.1  447.90
  4934.4  448.65  4939.8  447.98  4977.3  449.07  5014.5  448.90  5021.6  447.73
  5028.7  448.87  5042.8  448.67  5093.4  447.18  5133.6  448.03  5143.6  447.60
  5159.0  444.67  5166.2  445.14  5183.8  444.12  5257.9  445.92  5646.9  458.72
#Mann=7,-1,0
  4396.0    0.04       0  4575.5    0.05       0  4634.1    0.04       0
  4834.2    0.05       0  4846.3    0.05       0  4850.3    0.05       0
  5166.2    0.04       0
Bank Sta=4846.3,4850.3
Exp/Cntr=0.3,0.1

Type RM Length L Ch R = 1,2301,194,194,194
BEGIN DESCRIPTION:
4862
END DESCRIPTION:
XS GIS Cut Line= 3
      2403512.15     13570157.66      2403071.51     13570107.69
      2402462.85     13570184.91
#Sta/Elev= 30
  4611.2  453.05  4676.5  450.02  4709.0  449.55  4719.0  448.48  4739.2  448.01
  4749.2  447.05  4843.3  443.52  4855.8  442.40  4860.8  442.95  4870.0  442.02
  4883.4  441.55  5028.1  439.11  5028.3  438.61  5031.8  438.61  5032.1  439.11
  5061.2  440.11  5069.6  439.75  5121.7  440.73  5158.9  442.33  5192.3  442.92
  5262.8  445.44  5272.9  445.30  5383.8  449.29  5454.4  450.76  5474.9  452.00
  5484.6  451.80  5524.9  453.00  5565.2  454.93  5645.9  456.27  5668.2  457.18
#Mann=6,-1,0
  4611.2    0.05       0  4843.3    0.04       0  4883.4    0.05       0
  5028.1    0.05       0  5032.1    0.05       0  5158.9    0.04       0
Bank Sta=5028.1,5032.1
Exp/Cntr=0.3,0.1

Type RM Length L Ch R = 1,2107,515,515,515
BEGIN DESCRIPTION:
Mapping XS c2a05c3a
END DESCRIPTION:
XS GIS Cut Line= 3
      2403503.48     13570118.80      2403057.45     13569945.55
      2402559.91     13570126.14
#Sta/Elev= 30
  4487.0  453.32  4506.4  452.00  4511.8  452.42  4536.3  450.37  4549.7  450.42
  4759.4  442.14  4764.8  442.48  4789.3  441.86  4813.8  440.19  4819.2  440.50
  4874.9  438.79  4903.8  437.94  4958.0  437.68  4989.4  438.10  4997.8  437.02
  4998.0  436.99  4998.3  436.49  5001.8  436.49  5002.0  436.99  5006.6  437.93
  5021.3  438.81  5103.9  441.21  5223.4  445.61  5246.2  445.88  5296.8  448.33
  5302.1  448.04  5388.6  450.41  5404.3  451.39  5419.2  451.24  5494.8  454.32
#Mann=6,-1,0
  4487.0    0.05       0  4874.9    0.04       0  4997.8    0.05       0
  4998.0    0.05       0  5002.0    0.05       0  5103.9    0.04       0
Bank Sta=4998,5002
Exp/Cntr=0.3,0.1

Type RM Length L Ch R = 1,1592,474,474,474
BEGIN DESCRIPTION:
Mapping XS bc55089e
END DESCRIPTION:
XS GIS Cut Line= 3
      2403614.06     13569753.87      2403013.22     13569470.04
      2402445.52     13569842.36
#Sta/Elev= 30
  4289.5  461.76  4319.0  459.34  4347.3  458.66  4410.1  455.24  4432.2  453.29
  4454.4  452.87  4498.6  449.45  4580.5  446.18  4626.0  443.12  4653.9  442.47
  4694.3  440.09  4852.5  434.44  4933.1  432.76  4986.1  433.13  5033.6  432.29
  5033.8  431.79  5037.6  432.29  5043.3  433.49  5100.6  434.39  5157.8  436.89
  5172.9  436.63  5238.9  438.52  5323.6  442.14  5338.7  442.12  5346.5  443.02
  5411.0  444.86  5441.2  447.01  5570.8  450.78  5613.0  450.88  5632.9  450.16
#Mann=4,-1,0
  4289.5    0.05       0  4653.9    0.04       0  5033.6    0.04       0
  5037.6    0.04       0
Bank Sta=5033.6,5037.6
Exp/Cntr=0.3,0.1

Type RM Length L Ch R = 1,1118,224,224,224
BEGIN DESCRIPTION:
TRIB 6_1 TO THOMAS CREEK 2.0
END DESCRIPTION:
XS GIS Cut Line= 3
      2403325.03     13569275.02      2403025.00     13569075.00
      2402574.98     13569325.01
#Sta/Elev= 30
  4639.9  441.29  4683.5  439.04  4755.6  435.92  4776.7  435.62  4803.3  434.19
  4856.3  432.05  4905.9  431.00  4956.9  428.81  4991.0  428.08  4991.2  427.58
  4994.7  427.58  4995.0  428.08  5023.4  428.57  5046.3  428.24  5080.6  429.27
  5133.2  429.95  5183.5  432.20  5220.1  433.28  5241.9  433.44  5263.6  434.50
  5273.9  434.69  5279.6  434.26  5301.4  434.85  5317.4  435.94  5344.8  436.40
  5355.1  437.22  5412.3  438.76  5420.3  439.48  5442.1  439.77  5515.3  442.87
#Mann=4,-1,0
  4639.9    0.05       0  4803.3    0.04       0  4991.0    0.04       0
  4995.0    0.04       0
Bank Sta=4991,4995
Exp/Cntr=0.3,0.1

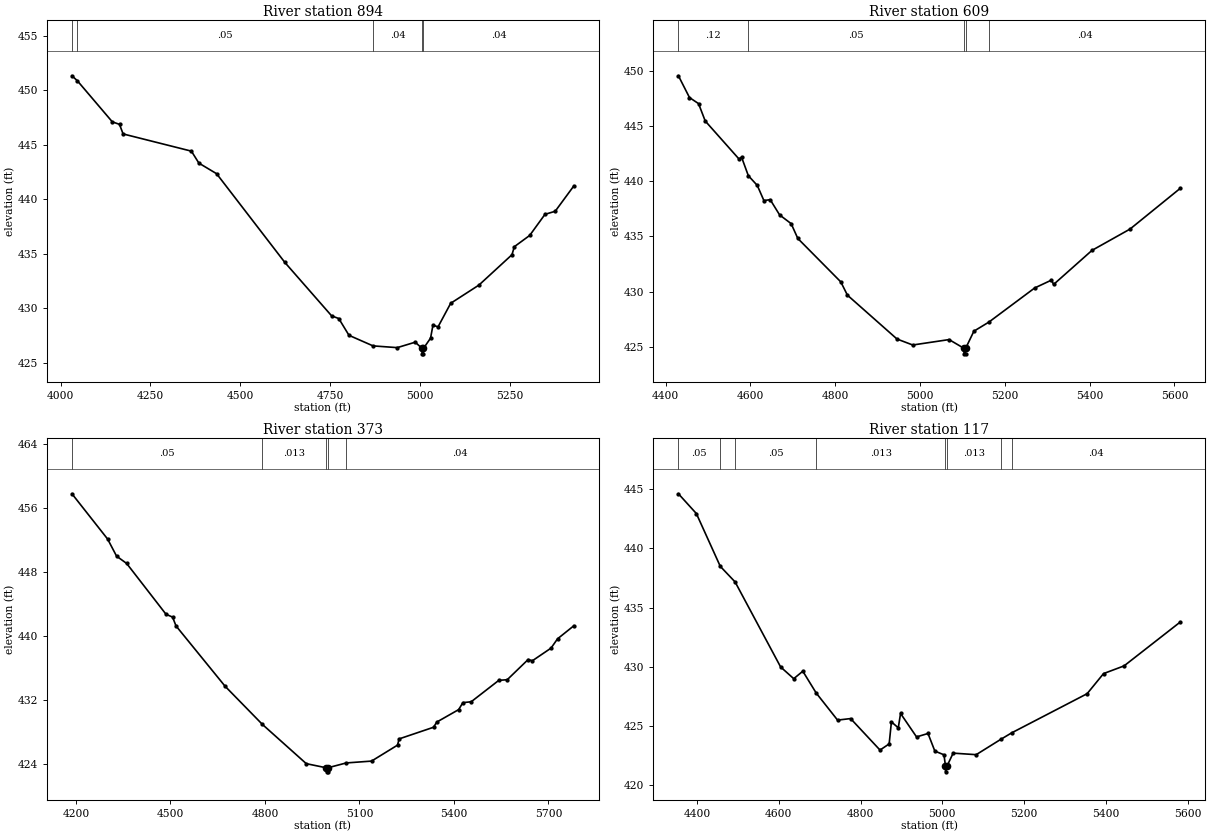
Type RM Length L Ch R = 1,894,285,285,285
BEGIN DESCRIPTION:
Mapping XS 7b807d2f
END DESCRIPTION:
XS GIS Cut Line= 3
      2403787.28     13568773.35      2403013.22     13568788.10
      2402597.80     13569251.30
#Sta/Elev= 30
  4031.6  451.33  4046.4  450.88  4143.9  447.10  4163.9  446.87  4173.9  445.99
  4363.9  444.41  4384.8  443.31  4434.0  442.34  4624.0  434.19  4754.0  429.29
  4774.0  429.04  4802.4  427.50  4869.3  426.53  4936.6  426.37  4986.7  426.87
  5005.6  426.30  5005.8  425.80  5009.3  425.80  5009.6  426.30  5029.3  427.24
  5036.0  428.43  5050.2  428.28  5085.3  430.44  5163.8  432.11  5255.8  434.90
  5262.5  435.64  5305.1  436.67  5347.7  438.61  5376.1  438.89  5428.0  441.22
#Mann=5,-1,0
  4031.6    0.04       0  4046.4    0.05       0  4869.3    0.04       0
  5005.6    0.04       0  5009.6    0.04       0
Bank Sta=5005.6,5009.6
Exp/Cntr=0.3,0.1

Type RM Length L Ch R = 1,609,236,236,236
BEGIN DESCRIPTION:
4860
END DESCRIPTION:
XS GIS Cut Line= 3
      2403371.35     13568386.05      2402726.28     13568767.64
      2402608.16     13569185.58
#Sta/Elev= 30
  4430.1  449.53  4456.2  447.56  4477.6  447.01  4493.3  445.44  4573.2  441.99
  4579.0  442.17  4595.0  440.49  4616.1  439.61  4631.7  438.24  4646.6  438.32
  4668.8  436.94  4696.0  436.15  4711.7  434.81  4813.1  430.88  4828.7  429.68
  4945.7  425.71  4982.8  425.17  5068.5  425.66  5103.6  424.87  5103.9  424.37
  5107.4  424.37  5107.6  424.87  5127.0  426.42  5162.3  427.24  5270.4  430.33
  5309.9  431.04  5315.1  430.65  5405.5  433.73  5495.3  435.66  5613.9  439.35
#Mann=5,-1,0
  4430.1    0.12       0  4595.0    0.05       0  5103.6    0.05       0
  5107.6    0.05       0  5162.3    0.04       0
Bank Sta=5103.6,5107.6
Exp/Cntr=0.3,0.1

Type RM Length L Ch R = 1,373,256,256,256
BEGIN DESCRIPTION:
TRIB 6_1 TO THOMAS CREEK 1.0
END DESCRIPTION:
XS GIS Cut Line= 3
      2403451.85     13568139.34      2402819.15     13568322.71
      2402574.99     13569225.02
#Sta/Elev= 30
  4187.2  457.74  4300.5  452.09  4328.9  449.96  4360.9  449.05  4485.9  442.71
  4506.7  442.36  4517.6  441.26  4673.3  433.74  4792.0  428.97  4931.2  424.08
  4995.2  423.56  4995.4  423.06  4998.9  423.06  4999.2  423.56  5058.0  424.17
  5138.4  424.40  5220.8  426.39  5226.0  427.17  5335.2  428.62  5345.6  429.27
  5414.9  430.82  5428.4  431.69  5454.8  431.80  5542.4  434.47  5569.2  434.55
  5635.6  437.07  5648.9  436.91  5708.2  438.49  5728.9  439.65  5780.7  441.28
#Mann=5,-1,0
  4187.2    0.05       0  4792.0   0.013       0  4995.2    0.03       0
  4999.2   0.013       0  5058.0    0.04       0
Bank Sta=4995.2,4999.2
Exp/Cntr=0.3,0.1

Type RM Length L Ch R = 1,117,0,0,0
BEGIN DESCRIPTION:
4859
END DESCRIPTION:
XS GIS Cut Line= 4
      2403098.72     13568063.56      2402644.51     13568236.16
      2402544.58     13568436.03      2402594.36     13568951.97
#Sta/Elev= 30
  4354.4  444.62  4398.3  442.95  4456.8  438.49  4493.1  437.17  4604.4  429.99
  4636.5  429.00  4658.7  429.63  4691.4  427.79  4743.7  425.50  4775.6  425.63
  4847.5  422.97  4869.9  423.49  4875.4  425.35  4892.2  424.85  4897.8  426.06
  4936.9  424.08  4964.9  424.37  4981.7  422.88  5004.0  422.57  5007.6  421.63
  5007.9  421.13  5011.6  421.63  5026.4  422.71  5082.8  422.58  5142.7  423.87
  5169.4  424.42  5354.1  427.73  5394.3  429.43  5444.5  430.08  5582.1  433.79
#Mann=8,-1,0
  4354.4    0.05       0  4456.8    0.12       0  4493.1    0.05       0
  4691.4   0.013       0  5007.6    0.03       0  5011.6   0.013       0
  5142.7    0.12       0  5169.4    0.04       0
Bank Sta=5007.6,5011.6
Exp/Cntr=0.3,0.1

Chan Stop Cuts=-1