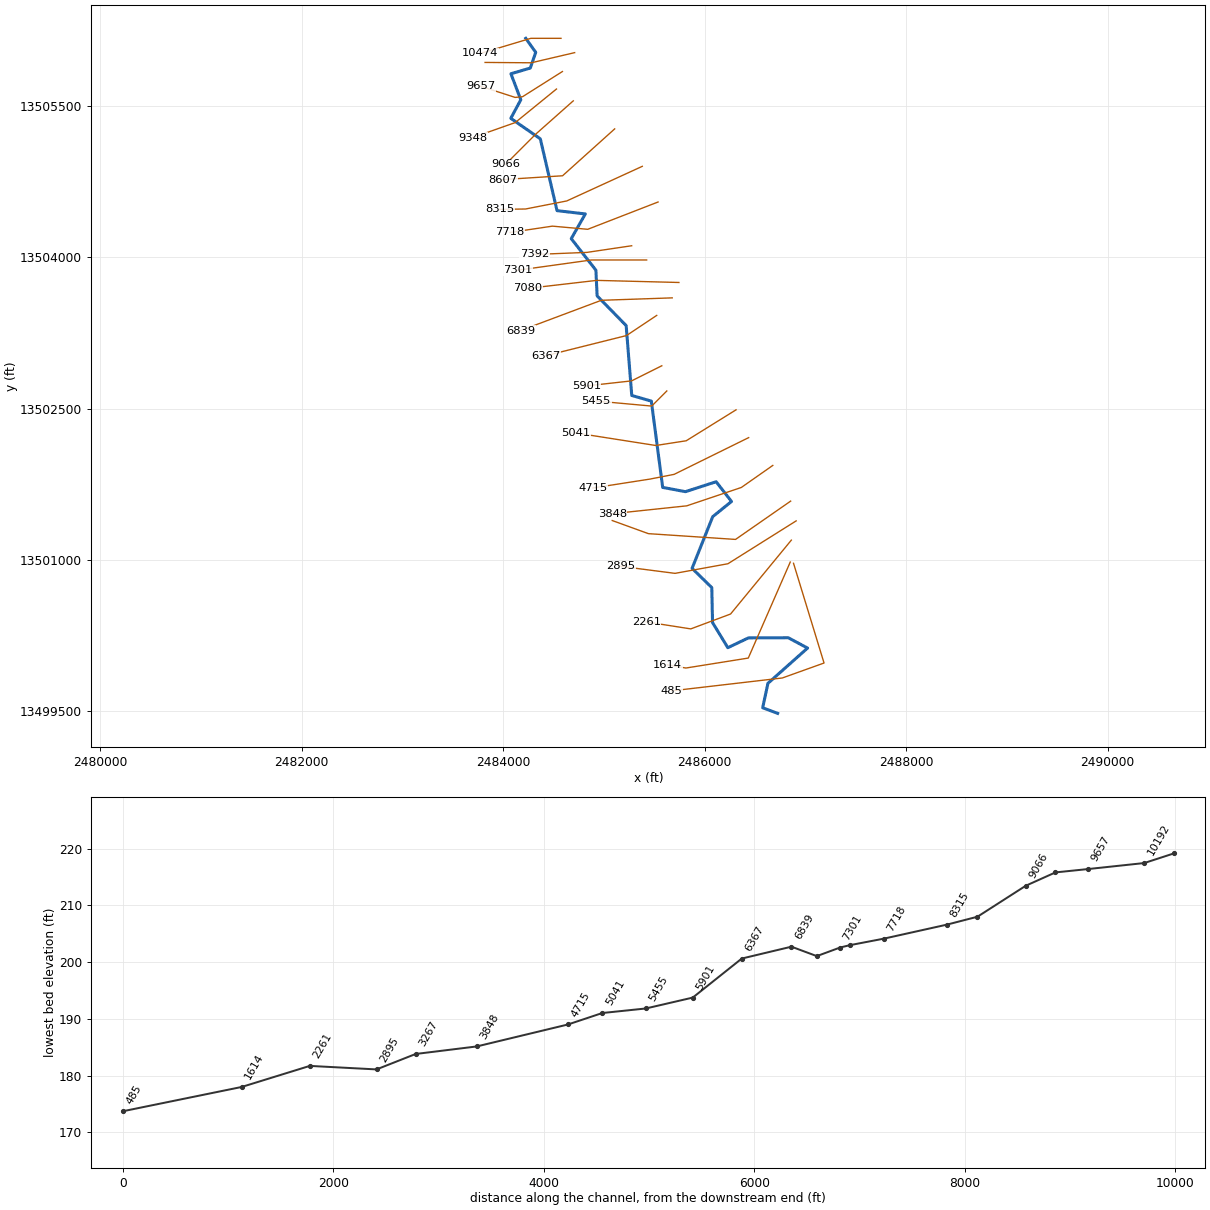
--- TRIB 7 TO EIGHTEENMILE CREEK.prj (project) ---

Proj Title=TRIB 7 TO EIGHTEENMILE CREEK Base Level Engineering
Current Plan=p01
Default Exp/Contr=0.3,0.1
English Units
Geom File=g01
Flow File=f01
Plan File=p01
Y Axis Title=Elevation
X Axis Title(PF)=Main Channel Distance
X Axis Title(XS)=Station
BEGIN DESCRIPTION:
TRIB 7 TO EIGHTEENMILE CREEK
END DESCRIPTION:
DSS Export Rating Curves= 0
DSS Export Rating Curve Sorted= 0
DSS Export Volume Flow Curves= 0
DXF OffsetX= 0
DXF OffsetY= 0
DXF ScaleX= 1
DXF ScaleY= 10

--- TRIB 7 TO EIGHTEENMILE CREEK.p01 (plan) ---

Plan Title=Multiple Run
Program Version=4.10
Short Identifier=Multiple
Geom File=g01
Flow File=f01
Subcritical Flow
K Sum by GR= 0
Std Step Tol= 0.01
Critical Tol= 0.01
Num of Std Step Trials= 20
Max Error Tol= 0.3
Flow Tol Ratio= 0.001
Split Flow NTrial= 30
Split Flow Tol= 0.02
Split Flow Ratio= 0.02
Log Output Level= 0
Friction Slope Method= 1
Unsteady Friction Slope Method= 2
Unsteady Bridges Friction Slope Method= 1
Parabolic Critical Depth
Global Vel Dist= 1 , 1 , 1
Global Log Level= 0
CheckData=True
Persistent XS Scale= 4400 , 5600 , 218 , 202 , 200 , 2
Encroach Param=-1 ,0,0, 0
BEGIN DESCRIPTION:
Multiple Run
END DESCRIPTION:
Computation Interval=1HOUR
Output Interval=1HOUR
Run HTab= 0
Run UNet= 0
Run PostProcess= 0
Run WQNet= 0
UNET Theta= 1
UNET Theta Warmup= 1
UNET ZTol= 0.02
UNET ZSATol= 0.05
UNET MxIter= 20
UNET MaxInSteps= 0
UNET DtIC= 0
UNET DtMin= 0
UNET MaxCRTS= 20
UNET WFStab= 2
UNET SFStab= 1
UNET WFX= 1
UNET SFX= 1
UNET DSS MLevel= 4
UNET DZMax Abort= 100
UNET Convert EG Bridges= 0
UNET Use Existing IB Tables=-1
UNET Froude Reduction=False
UNET Froude Limit= 1
UNET Froude Power= 10
UNET Time Slicing=0,0, 5
UNET Junction Losses=0
Instantaneous Interval=1HOUR
Write IC File= 0
Write IC File at Sim End=0
Echo Input=False
Echo Parameters=False
Echo Output=False
Write Detailed= 0
WQ AD Non Conservative
WQ ULTIMATE=-1
WQ Max Comp Step=1HOUR
WQ Output Interval=15MIN
WQ Output Selected Increments= 0
WQ Output face flow=0
WQ Output face velocity=0
WQ Output face area=0
WQ Output face dispersion=0
WQ Output cell volume=0
WQ Output cell surface area=0
WQ Output cell continuity=0
WQ Output cumulative cell continuity=0
WQ Output face conc=0
WQ Output face dconc_dx=0
WQ Output face courant=0
WQ Output face peclet=0
WQ Output face adv mass=0
WQ Output face disp mass=0
WQ Output cell mass=0
WQ Output cell source sink temp=0
WQ Output cell source sink nsm=0
WQ Output MaxMinRange=-1
WQ Daily Max Min Mean=-1
WQ Daily Range=0
WQ Daily Time=0
WQ Create Restart=0
WQ Fixed Restart=0
WQ System Summary=0
WQ Use Fixed Temperature=0
Sorting and Armoring Iterations= 10
XS Update Threshold= 0.02
Hydraulics Update Threshold= 0.02
Energy Slope Method= 1
Volume Change Method= 0
XS Weighting Method= 0
Number of US Weighted Cross Sections= 1
Number of DS Weighted Cross Sections= 1
Upstream XS Weight=0.25
Main XS Weight=0.5
Downstream XS Weight=0.25
Number of DS XS's Weighted with US Boundary= 1
Upstream Boundary Weight= 1
Weight of XSs Associated with US Boundary= 0
Number of US XS's Weighted with DS Boundary= 1
Downstream Boundary Weight= 0.5
Weight of XSs Associated with DS Boundary= 0.5
Sediment Output Level= 4
Mass or Volume Output= 0
Output Increment Type= 1
Profile and TS Output Increment= 10
XS Output Flag= 0
XS Output Increment= 10
Disregard all LS=0
Disregard all Conn=0
Disregard all Breaches=0
Disregard all Pumps=0

--- TRIB 7 TO EIGHTEENMILE CREEK.f01 (steady flow) ---

Flow Title=Multiple
Number of Profiles=7
Profile Names=10-year,25-year,50-year,1pct_min,100-year,1pct_plu,500-year
River Rch & RM= TRIB 7 TO EIGHTE,Reach-1,10474
     693    1120    1506     981    1957    3904    3267
River Rch & RM= TRIB 7 TO EIGHTE,Reach-1,9066
     927    1522    2068    1359    2712    5410    4613
River Rch & RM= TRIB 7 TO EIGHTE,Reach-1,5041
    1073    1771    2414    1590    3172    6329    5421
Boundary for River Rch & Prof#=TRIB 7 TO EIGHTE,Reach-1,1
Up Type=0
Dn Type=3
Dn Slope=0.005
Boundary for River Rch & Prof#=TRIB 7 TO EIGHTE,Reach-1,2
Up Type=0
Dn Type=3
Dn Slope=0.005
Boundary for River Rch & Prof#=TRIB 7 TO EIGHTE,Reach-1,3
Up Type=0
Dn Type=3
Dn Slope=0.005
Boundary for River Rch & Prof#=TRIB 7 TO EIGHTE,Reach-1,4
Up Type=0
Dn Type=3
Dn Slope=0.005
Boundary for River Rch & Prof#=TRIB 7 TO EIGHTE,Reach-1,5
Up Type=0
Dn Type=3
Dn Slope=0.005
Boundary for River Rch & Prof#=TRIB 7 TO EIGHTE,Reach-1,6
Up Type=0
Dn Type=3
Dn Slope=0.005
Boundary for River Rch & Prof#=TRIB 7 TO EIGHTE,Reach-1,7
Up Type=0
Dn Type=3
Dn Slope=0.005

--- TRIB 7 TO EIGHTEENMILE CREEK.g01 (geometry) ---

Geom Title=Existing Conditions
Program Version=4.10

River Reach=TRIB 7 TO EIGHTE,Reach-1
Reach XY= 30
        2484225.       13506175.      2484323.91     13506035.55
      2484269.92     13505880.04        2484078.      13505823.6
      2484175.55     13505564.81      2484076.58     13505381.03
      2484369.53     13505177.45      2484535.38     13504464.78
      2484816.18       13504432.      2484676.51     13504186.88
      2484921.32     13503873.41      2484933.14     13503618.96
      2485221.55     13503323.75      2485276.98     13502630.62
      2485471.47     13502574.01      2485584.01     13501717.94
      2485809.84     13501675.39      2486114.57     13501773.96
      2486267.17     13501578.22      2486080.73     13501427.55
       2485875.7     13500914.29      2486071.48     13500723.72
      2486078.74     13500376.56      2486230.71     13500126.88
      2486435.63      13500224.4      2486830.03     13500225.81
      2487022.14     13500123.21      2486628.76     13499773.44
      2486576.51     13499530.84        2486725.       13499475.

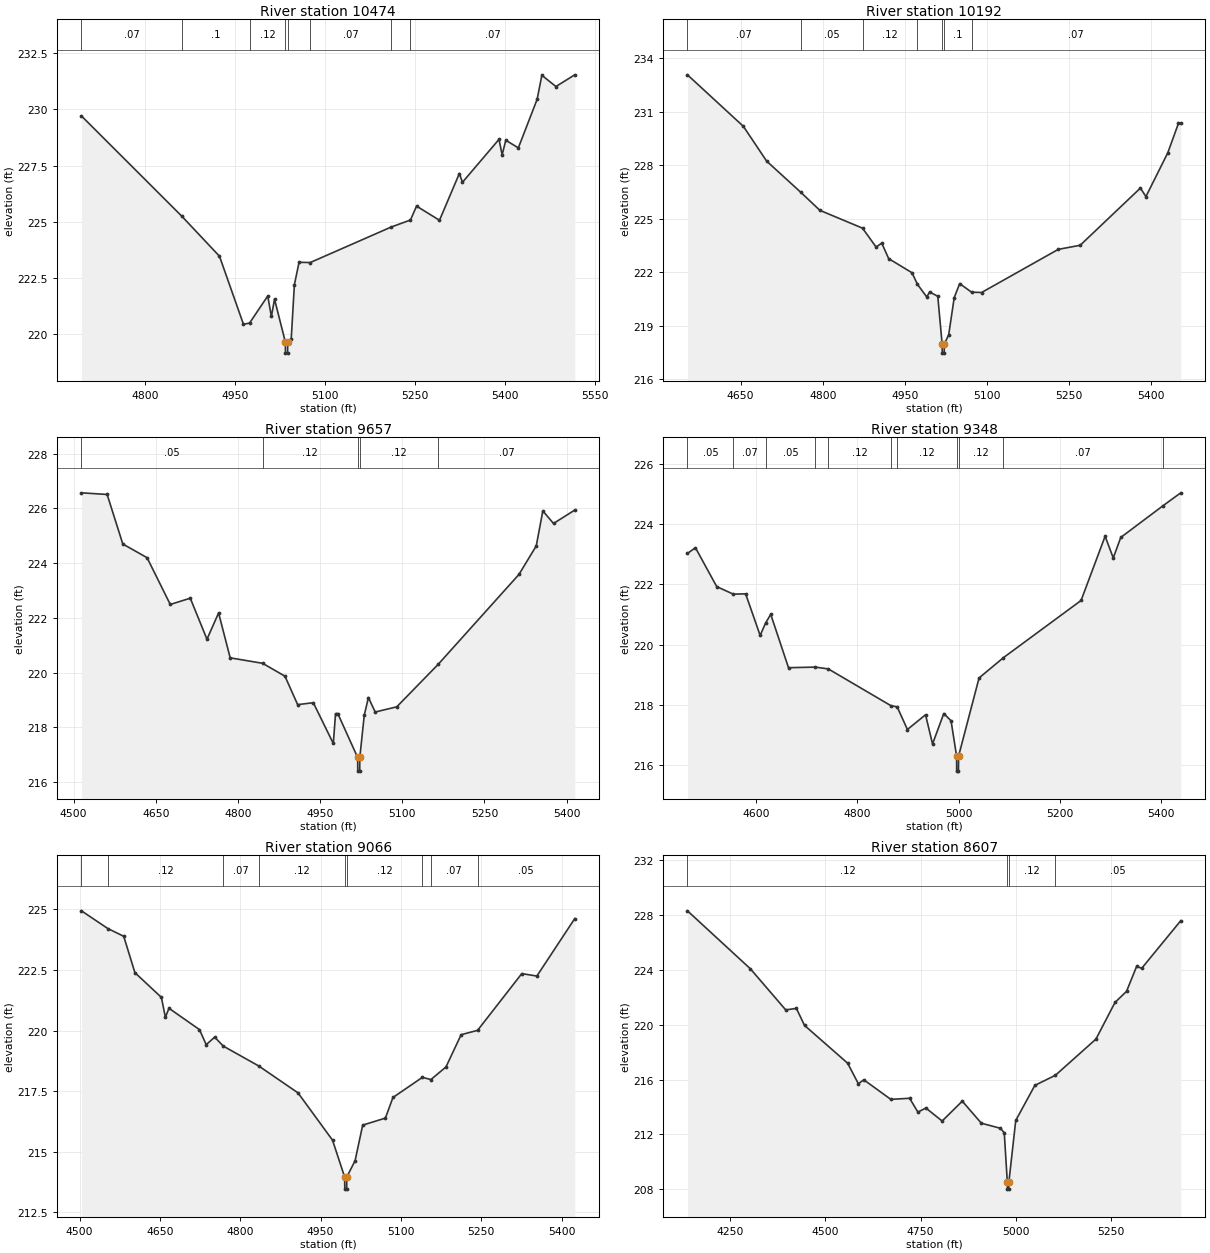
Type RM Length L Ch R = 1 ,10474   ,282,282,282
BEGIN DESCRIPTION:
TRIB 7 TO EIGHTEENMILE CREEK 19.0
END DESCRIPTION:
XS GIS Cut Line= 3
      2484574.95       13506175.        2484275.       13506175.
      2483774.97     13506024.99
#Sta/Elev= 30
  4694.3  229.71  4861.2  225.26  4924.3  223.47  4964.3  220.44  4974.5   220.5
  5004.7   221.7  5010.8  220.79    5016  221.56    5034  219.66  5034.3  219.16
  5037.8  219.16    5038  219.66  5043.8  219.77  5049.1   222.2  5056.9   223.2
  5075.5  223.19  5210.5  224.77  5242.5  225.08  5252.7   225.7  5290.9  225.07
    5324  227.15  5329.2  226.76  5390.1  228.67  5395.3  227.98  5401.4  228.63
  5422.3  228.29  5453.6  230.45  5461.5  231.52  5484.9  231.02  5516.3  231.54
#Mann= 8 ,-1 , 0
  4694.3     .07       0  4861.2      .1       0  4974.5     .12       0
    5034     .05       0    5038     .12       0  5075.5     .07       0
  5210.5     .12       0  5242.5     .07       0
Bank Sta=5034,5038
XS Rating Curve= 0 ,0
Exp/Cntr=0.3,0.1

Type RM Length L Ch R = 1 ,10192   ,535,535,535
BEGIN DESCRIPTION:
Mapping XS 84761e6b
END DESCRIPTION:
XS GIS Cut Line= 3
      2484710.37     13506033.04      2484279.78     13505932.34
      2483821.41     13505935.81
#Sta/Elev= 30
  4553.1  233.07  4655.2  230.18  4697.7  228.23  4759.7  226.49  4794.8  225.47
  4872.7  224.47  4897.5  223.41  4907.8  223.63  4920.5  222.76    4963  221.97
    4973  221.32    4990  220.61  4995.2  220.89  5010.1  220.65  5018.1  217.96
  5018.3  217.46  5021.8  217.46  5022.1  217.96  5030.1   218.5  5040.1  220.57
  5050.1  221.36  5071.7  220.88  5090.1  220.86  5230.1  223.28  5270.1  223.51
  5380.1  226.72  5390.1  226.24  5430.1   228.7  5449.4  230.34  5453.7  230.34
#Mann= 7 ,-1 , 0
  4553.1     .07       0  4759.7     .05       0  4872.7     .12       0
    4973      .1       0  5018.1     .05       0  5022.1      .1       0
  5071.7     .07       0
Bank Sta=5018.1,5022.1
XS Rating Curve= 0 ,0
Exp/Cntr=0.3,0.1

Type RM Length L Ch R = 1 ,9657    ,309,309,309
BEGIN DESCRIPTION:
Mapping XS 095184e8
END DESCRIPTION:
XS GIS Cut Line= 4
      2484588.82     13505845.55      2484192.97     13505595.53
      2484120.05     13505588.59      2483778.11     13505699.12
#Sta/Elev= 30
  4514.2  226.57  4561.1  226.51  4589.7   224.7    4634   224.2  4676.4  222.49
  4712.9  222.72  4743.4  221.22  4764.6  222.18  4785.8  220.54    4845  220.34
  4885.8  219.87    4909  218.83  4937.6   218.9  4974.1  217.41  4978.2   218.5
  4982.4   218.5  5018.5   216.9  5018.8   216.4  5022.3   216.4  5022.5   216.9
  5030.6  218.44  5038.2  219.09  5050.6  218.56    5090  218.75  5165.5   220.3
  5313.2  223.59  5344.7  224.63  5356.7  225.91  5376.2  225.45    5415  225.94
#Mann= 5 ,-1 , 0
  4514.2     .05       0    4845     .12       0  5018.5     .05       0
  5022.5     .12       0  5165.5     .07       0
Bank Sta=5018.5,5022.5
XS Rating Curve= 0 ,0
Exp/Cntr=0.3,0.1

Type RM Length L Ch R = 1 ,9348    ,282,282,282
BEGIN DESCRIPTION:
Mapping XS e37609b3
END DESCRIPTION:
XS GIS Cut Line= 3
      2484529.82     13505671.95      2484120.05     13505338.59
      2483699.27     13505190.28
#Sta/Elev= 30
  4464.3  223.03  4480.1  223.22  4522.1  221.93  4554.8  221.68  4579.2  221.69
  4607.9  220.31  4618.6  220.72  4628.8  221.01  4663.9  219.24  4716.7  219.26
  4742.5   219.2  4866.3  217.98  4878.6  217.94  4898.8  217.19  4934.6  217.68
  4948.4  216.71  4970.6  217.72    4985  217.48  4995.9  216.31  4996.1  215.81
  4999.6  215.81  4999.9  216.31  5040.3   218.9  5088.2  219.57  5241.8  221.47
  5289.3   223.6  5305.4  222.88  5320.2  223.56  5403.5  224.61  5438.7  225.04
#Mann= 11 ,-1 , 0
  4464.3     .05       0  4554.8     .07       0  4618.6     .05       0
  4716.7     .07       0  4742.5     .12       0  4866.3      .1       0
  4878.6     .12       0  4995.9     .05       0  4999.9     .12       0
  5088.2     .07       0  5403.5     .12       0
Bank Sta=4995.9,4999.9
XS Rating Curve= 0 ,0
Exp/Cntr=0.3,0.1

Type RM Length L Ch R = 1 ,9066    ,459,459,459
BEGIN DESCRIPTION:
TRIB 7 TO EIGHTEENMILE CREEK 17.0
END DESCRIPTION:
XS GIS Cut Line= 3
      2484696.61     13505554.55        2484325.       13505225.
      2484025.03     13504925.03
#Sta/Elev= 30
  4503.6  224.94  4552.8  224.21  4582.5  223.89  4603.4  222.39  4652.8  221.37
  4660.3  220.55    4667  220.92  4723.9  220.04  4736.5  219.42  4752.3  219.73
  4768.4  219.36  4834.6  218.54  4907.9  217.43  4972.3  215.48  4994.9  213.96
  4995.2  213.46  4998.7  213.46  4998.9  213.96  5014.4  214.63  5028.6   216.1
    5071  216.39  5085.1  217.24    5140  218.07    5156  217.98  5184.1   218.5
  5212.4  219.83  5243.1  220.01  5325.6  222.35  5353.8  222.25  5424.5  224.62
#Mann= 9 ,-1 , 0
  4503.6     .07       0  4552.8     .12       0  4768.4     .07       0
  4834.6     .12       0  4994.9     .05       0  4998.9     .12       0
    5140     .05       0    5156     .07       0  5243.1     .05       0
Bank Sta=4994.9,4998.9
XS Rating Curve= 0 ,0
Exp/Cntr=0.3,0.1

Type RM Length L Ch R = 1 ,8607    ,292,292,292
BEGIN DESCRIPTION:
Mapping XS 07c64274
END DESCRIPTION:
XS GIS Cut Line= 3
       2485107.5     13505276.16      2484590.15      13504810.9
      2483992.96     13504772.71
#Sta/Elev= 30
  4138.5  228.31  4303.6  224.08  4396.3  221.08  4424.3  221.19  4445.6  219.95
  4558.8  217.19  4586.9  215.69  4601.1  215.98  4672.1  214.55  4721.4  214.63
  4743.1  213.62    4764  213.92  4806.7  212.97  4859.5  214.42  4909.6  212.81
  4959.7  212.44  4969.7  212.11  4977.7   208.5    4978     208  4981.5     208
  4981.7   208.5  4999.8  213.01  5049.9  215.57  5103.9  216.31  5210.2  218.95
  5260.3  221.63  5290.4  222.43  5316.9  224.25  5330.4  224.12  5432.7  227.59
#Mann= 4 ,-1 , 0
  4138.5     .12       0  4977.7     .05       0  4981.7     .12       0
  5103.9     .05       0
Bank Sta=4977.7,4981.7
XS Rating Curve= 0 ,0
Exp/Cntr=0.3,0.1

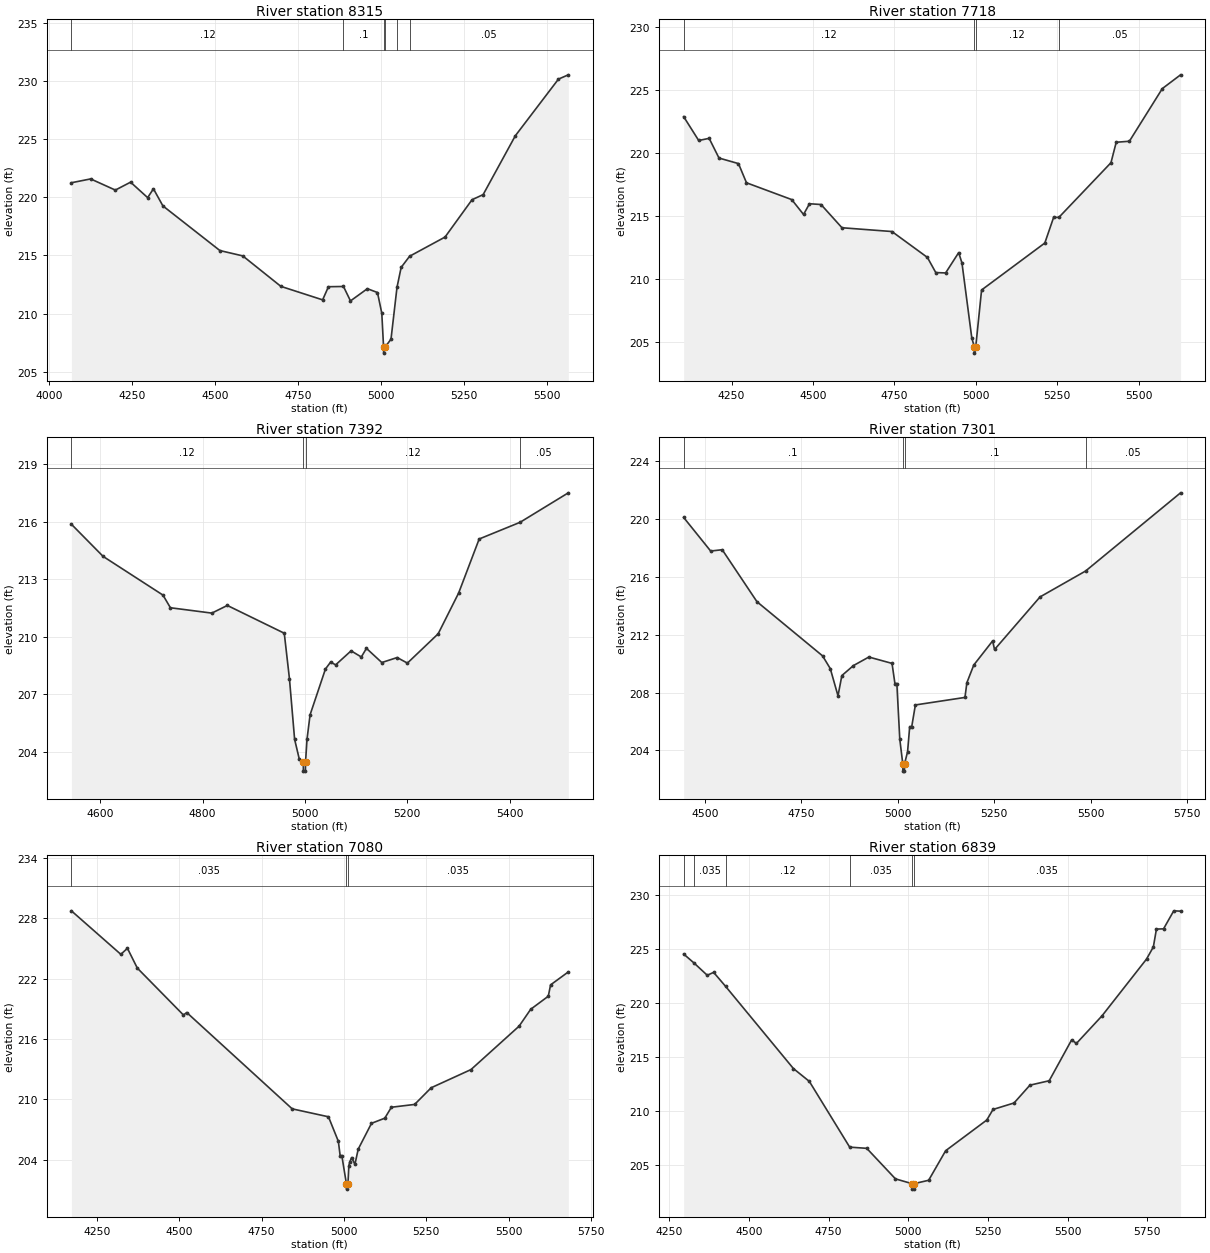
Type RM Length L Ch R = 1 ,8315    ,597,597,597
BEGIN DESCRIPTION:
Mapping XS d0319eb1
END DESCRIPTION:
XS GIS Cut Line= 4
       2485381.8     13504904.64      2484631.82      13504560.9
       2484222.1     13504481.04      2483965.16     13504477.56
#Sta/Elev= 30
  4066.3  221.25  4124.4  221.58  4198.9  220.62  4244.9   221.3  4296.4  219.97
  4313.9  220.73  4342.4  219.26  4514.4  215.42  4583.4  214.96  4698.4  212.34
  4824.4  211.18  4841.9  212.31  4887.3  212.33  4908.4  211.09  4959.4  212.14
  4989.9  211.81  5002.9  210.03  5008.3   207.1  5008.6   206.6  5012.3   207.1
  5030.7   207.8  5048.8  212.26  5061.3  213.97  5086.8  214.93  5193.7  216.58
  5275.2  219.79  5308.7  220.23  5405.8  225.29  5535.9  230.16  5565.7  230.53
#Mann= 6 ,-1 , 0
  4066.3     .12       0  4887.3      .1       0  5008.3     .05       0
  5012.3      .1       0  5048.8     .12       0  5086.8     .05       0
Bank Sta=5008.3,5012.3
XS Rating Curve= 0 ,0
Exp/Cntr=0.3,0.1

Type RM Length L Ch R = 1 ,7718    ,326,326,326
BEGIN DESCRIPTION:
Mapping XS 69ae57cf
END DESCRIPTION:
XS GIS Cut Line= 4
      2485538.03     13504550.47      2484840.15     13504279.65
      2484489.46      13504310.9      2484069.65     13504248.45
#Sta/Elev= 30
  4103.1  222.87  4149.3  220.98  4181.4  221.15  4211.6  219.59  4271.4  219.15
    4296  217.63  4434.8   216.3  4471.1  215.12  4489.3  215.97  4524.7  215.91
    4589  214.07  4742.4  213.77  4851.2  211.72  4876.9  210.52  4907.1  210.49
  4947.2   212.1  4957.3  211.28  4987.4  205.35  4995.2  204.64  4995.5  204.14
  4999.6  204.64  5017.5  209.14  5211.6  212.86  5238.6  214.89  5254.7  214.89
  5414.6  219.22  5430.7  220.84  5471.1  220.92  5572.2  225.09  5628.2  226.18
#Mann= 4 ,-1 , 0
  4103.1     .12       0  4995.2     .05       0  4999.6     .12       0
  5254.7     .05       0
Bank Sta=4995.2,4999.6
XS Rating Curve= 0 ,0
Exp/Cntr=0.3,0.1

Type RM Length L Ch R = 1 ,7392    ,91,91,91
BEGIN DESCRIPTION:
Mapping XS 9434c43f
END DESCRIPTION:
XS GIS Cut Line= 3
      2485276.31     13504116.37      2484831.86      13504050.4
      2484310.99     13504029.56
#Sta/Elev= 30
  4543.9  215.87  4605.9  214.19  4722.8  212.17  4737.3  211.51  4818.2  211.23
  4848.5  211.63  4959.7  210.18  4969.8  207.81  4979.9  204.64  4989.1   203.6
  4996.8  203.48  4997.1  202.98    5001  202.98  5001.3  203.48  5004.1  204.64
  5010.1  205.92  5040.1  208.31  5050.1  208.67  5060.1  208.53  5090.2  209.26
  5110.2  208.94  5120.2  209.39  5150.2  208.65  5180.2  208.91  5200.2  208.62
  5260.3  210.15  5300.3  212.28  5340.4   215.1  5420.2  215.97  5514.5  217.51
#Mann= 4 ,-1 , 0
  4543.9     .12       0  4996.8     .05       0  5001.3     .12       0
  5420.2     .05       0
Bank Sta=4996.8,5001.3
XS Rating Curve= 0 ,0
Exp/Cntr=0.3,0.1

Type RM Length L Ch R = 1 ,7301    ,221,221,221
BEGIN DESCRIPTION:
TRIB 7 TO EIGHTEENMILE CREEK 13.0
END DESCRIPTION:
XS GIS Cut Line= 3
      2485424.97       13503975.        2484875.       13503975.
      2484144.32     13503873.31
#Sta/Elev= 30
  4445.3  220.09  4515.3  217.77  4545.3  217.86  4635.3  214.27  4805.3  210.53
  4825.3  209.65  4845.3  207.77  4855.3  209.17  4885.3  209.86  4925.3  210.45
  4985.3  210.01  4992.8  208.62  4997.8  208.62  5005.4  204.77  5013.2  203.07
  5013.5  202.57  5017.4  202.57  5017.7  203.07  5025.6  203.91  5031.1  205.65
  5036.1   205.6  5045.8  207.14  5174.3  207.66  5179.3  208.68  5197.2   209.9
  5245.9  211.56    5251  210.97  5368.8   214.6  5486.9  216.39    5733  221.79
#Mann= 4 ,-1 , 0
  4445.3      .1       0  5013.2     .05       0  5017.7      .1       0
  5486.9     .05       0
Bank Sta=5013.2,5017.7
XS Rating Curve= 0 ,0
Exp/Cntr=0.3,0.1

Type RM Length L Ch R = 1 ,7080    ,241,241,241
BEGIN DESCRIPTION:
Mapping XS 963dc94f
END DESCRIPTION:
XS GIS Cut Line= 3
      2485745.01     13503751.79      2484929.08     13503772.62
      2484241.59     13503692.76
#Sta/Elev= 30
  4172.9  228.76    4323  224.43    4343  225.03    4373  223.06    4513  218.39
    4523  218.64  4843.1  209.05  4953.2  208.26  4983.2  205.82  4988.6   204.4
  4993.7   204.4  5007.8  201.56  5008.1  201.06  5012.3  201.56  5015.1  203.41
  5018.4   203.8  5023.4   204.2  5033.5  203.53  5043.5  205.04  5083.8  207.61
  5124.1  208.12  5144.2  209.21  5214.7  209.49    5265  211.15  5385.8  212.96
  5531.8  217.28    5567  218.96  5620.4  220.26  5627.4  221.39  5681.2  222.68
#Mann= 3 ,-1 , 0
  4172.9    .035       0  5007.8    .035       0  5012.3    .035       0
Bank Sta=5007.8,5012.3
XS Rating Curve= 0 ,0
Exp/Cntr=0.3,0.1

Type RM Length L Ch R = 1 ,6839    ,472,472,472
BEGIN DESCRIPTION:
TRIB 7 TO EIGHTEENMILE CREEK 12.0
END DESCRIPTION:
XS GIS Cut Line= 3
      2485679.09     13503599.01        2484975.       13503575.
        2484175.       13503275.
#Sta/Elev= 30
  4295.5   224.5  4328.7  223.65  4369.6  222.53  4389.6   222.8  4426.9  221.51
  4639.8  213.89  4689.8   212.7  4816.4  206.61  4869.9   206.5    4960  203.67
  5012.8  203.22  5013.2  202.72  5017.1  202.72  5017.4  203.22  5064.1  203.54
  5117.5  206.28  5246.5  209.12  5266.1   210.1    5332   210.7  5381.8  212.35
  5442.3  212.76  5512.6  216.54  5527.8  216.22  5607.9  218.77  5747.6  224.03
    5769  225.15  5778.7  226.81    5801  226.83    5833   228.5  5854.4  228.47
#Mann= 6 ,-1 , 0
  4295.5     .05       0  4328.7    .035       0  4426.9     .12       0
  4816.4    .035       0  5012.8    .035       0  5017.4    .035       0
Bank Sta=5012.8,5017.4
XS Rating Curve= 0 ,0
Exp/Cntr=0.3,0.1

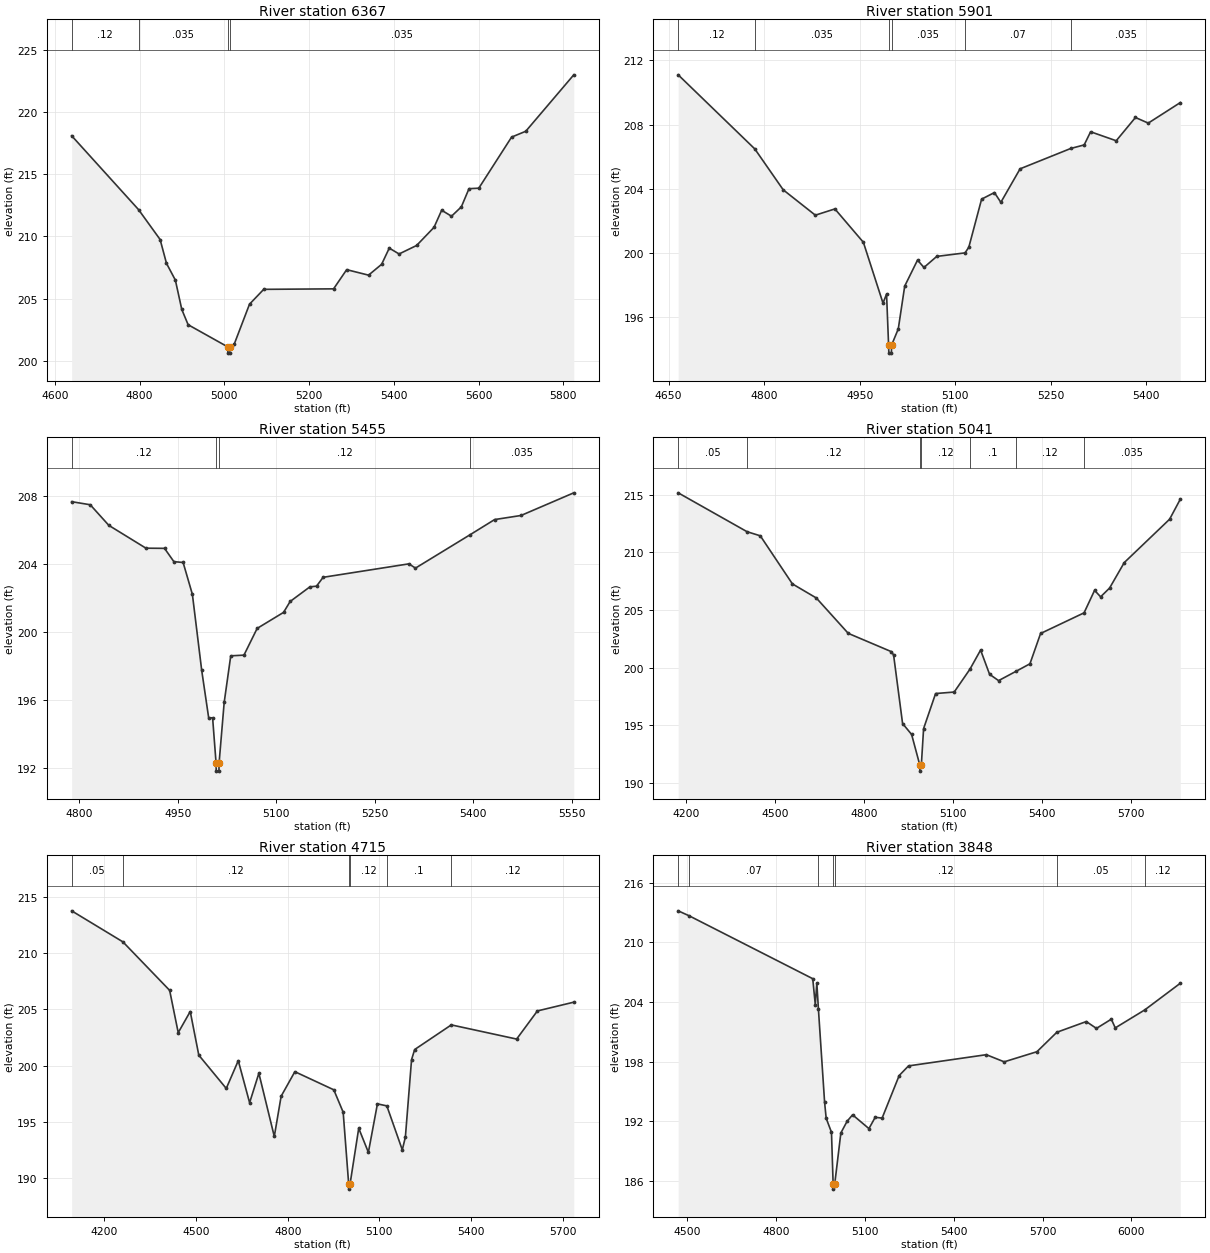
Type RM Length L Ch R = 1 ,6367    ,466,466,466
BEGIN DESCRIPTION:
TRIB 7 TO EIGHTEENMILE CREEK 11.0
END DESCRIPTION:
XS GIS Cut Line= 3
      2485524.97     13503424.98        2485225.       13503225.
      2484425.04     13503025.01
#Sta/Elev= 30
  4639.6  218.08  4797.5  212.15  4848.4  209.75  4863.4  207.84  4884.4  206.49
  4899.5  204.14  4914.5  202.91  5008.1  201.13  5008.4  200.63  5012.4  200.63
  5012.7  201.13  5023.3  201.35  5059.4  204.56  5092.9  205.75  5257.8  205.79
  5288.7  207.33  5340.3  206.89  5371.2  207.76  5389.2  209.06  5412.4  208.59
  5453.7  209.27  5494.9  210.73  5512.9   212.1  5536.1  211.62  5559.3  212.37
  5577.4  213.83  5600.5  213.87  5677.9  217.97  5711.4  218.44  5824.7  222.97
#Mann= 4 ,-1 , 0
  4639.6     .12       0  4797.5    .035       0  5008.1    .035       0
  5012.7    .035       0
Bank Sta=5008.1,5012.7
XS Rating Curve= 0 ,0
Exp/Cntr=0.3,0.1

Type RM Length L Ch R = 1 ,5901    ,446,446,446
BEGIN DESCRIPTION:
TRIB 7 TO EIGHTEENMILE CREEK 10.0
END DESCRIPTION:
XS GIS Cut Line= 3
      2485575.03     13502925.02        2485275.       13502775.
      2484825.02       13502725.
#Sta/Elev= 30
    4665   211.1  4785.3  206.48  4829.9  203.93  4880.3  202.35    4911  202.74
  4955.7  200.66  4986.5  196.87  4992.1  197.43  4995.3  194.25  4995.7  193.75
  4999.7  193.75    5000  194.25  5010.5  195.26  5020.6  197.93  5040.7  199.55
  5050.8  199.09  5070.9  199.78  5115.3     200  5121.2  200.35  5141.3  203.35
  5161.4  203.76  5171.5  203.15  5201.7  205.24  5281.3  206.51  5302.3  206.73
  5312.4  207.55  5352.6  206.99  5382.8  208.44  5402.9  208.09  5453.2  209.37
#Mann= 6 ,-1 , 0
    4665     .12       0  4785.3    .035       0  4995.3    .035       0
    5000    .035       0  5115.3     .07       0  5281.3    .035       0
Bank Sta=4995.3,5000
XS Rating Curve= 0 ,0
Exp/Cntr=0.3,0.1

Type RM Length L Ch R = 1 ,5455    ,414,414,414
BEGIN DESCRIPTION:
TRIB 7 TO EIGHTEENMILE CREEK 9.0
END DESCRIPTION:
XS GIS Cut Line= 3
      2485624.99     13502674.99        2485475.       13502525.
      2484924.99       13502575.
#Sta/Elev= 30
  4788.5  207.65  4816.8  207.47  4845.1  206.26  4901.6  204.92  4929.9  204.91
  4944.1  204.13  4958.2  204.08  4972.3  202.21  4986.5  197.74  4997.1  194.96
  5003.1  194.96  5008.3  192.33  5008.6  191.83  5012.7  191.83    5013  192.33
  5020.7  195.86  5030.7   198.6  5050.8  198.64  5070.9  200.21  5111.1  201.15
  5121.1  201.79  5151.2  202.65  5161.3  202.69  5171.3  203.21  5301.9     204
  5311.9  203.75  5395.5  205.72  5432.4   206.6  5472.6  206.84  5552.9  208.17
#Mann= 4 ,-1 , 0
  4788.5     .12       0  5008.3     .05       0    5013     .12       0
  5395.5    .035       0
Bank Sta=5008.3,5013
XS Rating Curve= 0 ,0
Exp/Cntr=0.3,0.1

Type RM Length L Ch R = 1 ,5041    ,326,326,326
BEGIN DESCRIPTION:
Mapping XS db52fc26
END DESCRIPTION:
XS GIS Cut Line= 4
      2486312.41       13502488.      2485817.58     13502180.69
       2485515.5     13502133.81      2484719.32     13502258.71
#Sta/Elev= 30
  4172.4  215.17  4404.6   211.8  4449.5  211.44  4557.8  207.27  4638.4  206.05
  4746.2  202.98    4892  201.39  4899.2   201.1  4929.5  195.16    4960  194.21
  4987.9  191.53  4988.2  191.03  4992.7  191.53  5000.4  194.72  5040.9  197.76
  5103.6  197.89  5156.7  199.87  5192.7  201.53    5223  199.43  5253.4  198.88
  5312.4  199.69  5359.2  200.34  5395.1  202.97  5541.8  204.76  5577.3  206.71
  5597.6  206.15  5627.9  206.91  5677.4  209.12  5830.4  212.88  5866.5  214.62
#Mann= 7 ,-1 , 0
  4172.4     .05       0  4404.6     .12       0  4987.9     .05       0
  4992.7     .12       0  5156.7      .1       0  5312.4     .12       0
  5541.8    .035       0
Bank Sta=4987.9,4992.7
XS Rating Curve= 0 ,0
Exp/Cntr=0.3,0.1

Type RM Length L Ch R = 1 ,4715    ,867,867,867
BEGIN DESCRIPTION:
Mapping XS 61989b14
END DESCRIPTION:
XS GIS Cut Line= 4
       2486437.4     13502211.95      2485697.79     13501847.36
      2485458.21     13501800.48      2484890.49     13501711.94
#Sta/Elev= 30
  4092.8  213.75  4260.6  210.99  4413.5  206.68  4441.6  202.92  4480.9   204.8
  4508.9  200.92  4598.8  197.96  4638.1  200.43  4675.2  196.69  4705.5  199.31
    4756  193.69  4778.4  197.27  4823.3  199.45  4950.7  197.84  4981.4  195.85
  4999.3  189.51  4999.7  189.01  5004.2  189.51  5032.3  194.42  5063.9  192.28
  5093.5  196.59  5124.3  196.41  5174.9   192.5    5185  193.64  5205.2  200.52
  5215.4  201.42  5335.3  203.61  5549.1  202.35    5617  204.85  5736.1  205.63
#Mann= 6 ,-1 , 0
  4092.8     .05       0  4260.6     .12       0  4999.3     .05       0
  5004.2     .12       0  5124.3      .1       0  5335.3     .12       0
Bank Sta=4999.3,5004.2
XS Rating Curve= 0 ,0
Exp/Cntr=0.3,0.1

Type RM Length L Ch R = 1 ,3848    ,581,581,581
BEGIN DESCRIPTION:
Mapping XS 3e386dbc
END DESCRIPTION:
XS GIS Cut Line= 4
      2486676.94     13501935.89      2486364.46     13501717.15
      2485822.79     13501534.86      2485083.16     13501456.73
#Sta/Elev= 30
  4468.7  213.19  4506.4  212.68  4923.4  206.35    4932  203.73  4937.2  205.91
  4942.5  203.32  4963.5  193.88  4968.8  192.28  4986.7  190.87  4992.3  185.64
  4992.7  185.14  4997.6  185.64  5018.4   190.8  5039.5  191.98    5058  192.63
  5113.3  191.24  5134.4  192.38  5157.8   192.3  5215.5  196.59    5247  197.56
  5509.9  198.69  5570.3  197.97  5680.9  198.99  5748.2  200.95  5847.7  202.03
    5882  201.34  5932.3  202.27  5945.6  201.39  6045.1   203.2  6165.4  205.89
#Mann= 7 ,-1 , 0
  4468.7     .05       0  4506.4     .07       0  4942.5     .12       0
  4992.3     .05       0  4997.6     .12       0  5748.2     .05       0
  6045.1     .12       0
Bank Sta=4992.3,4997.6
XS Rating Curve= 0 ,0
Exp/Cntr=0.3,0.1

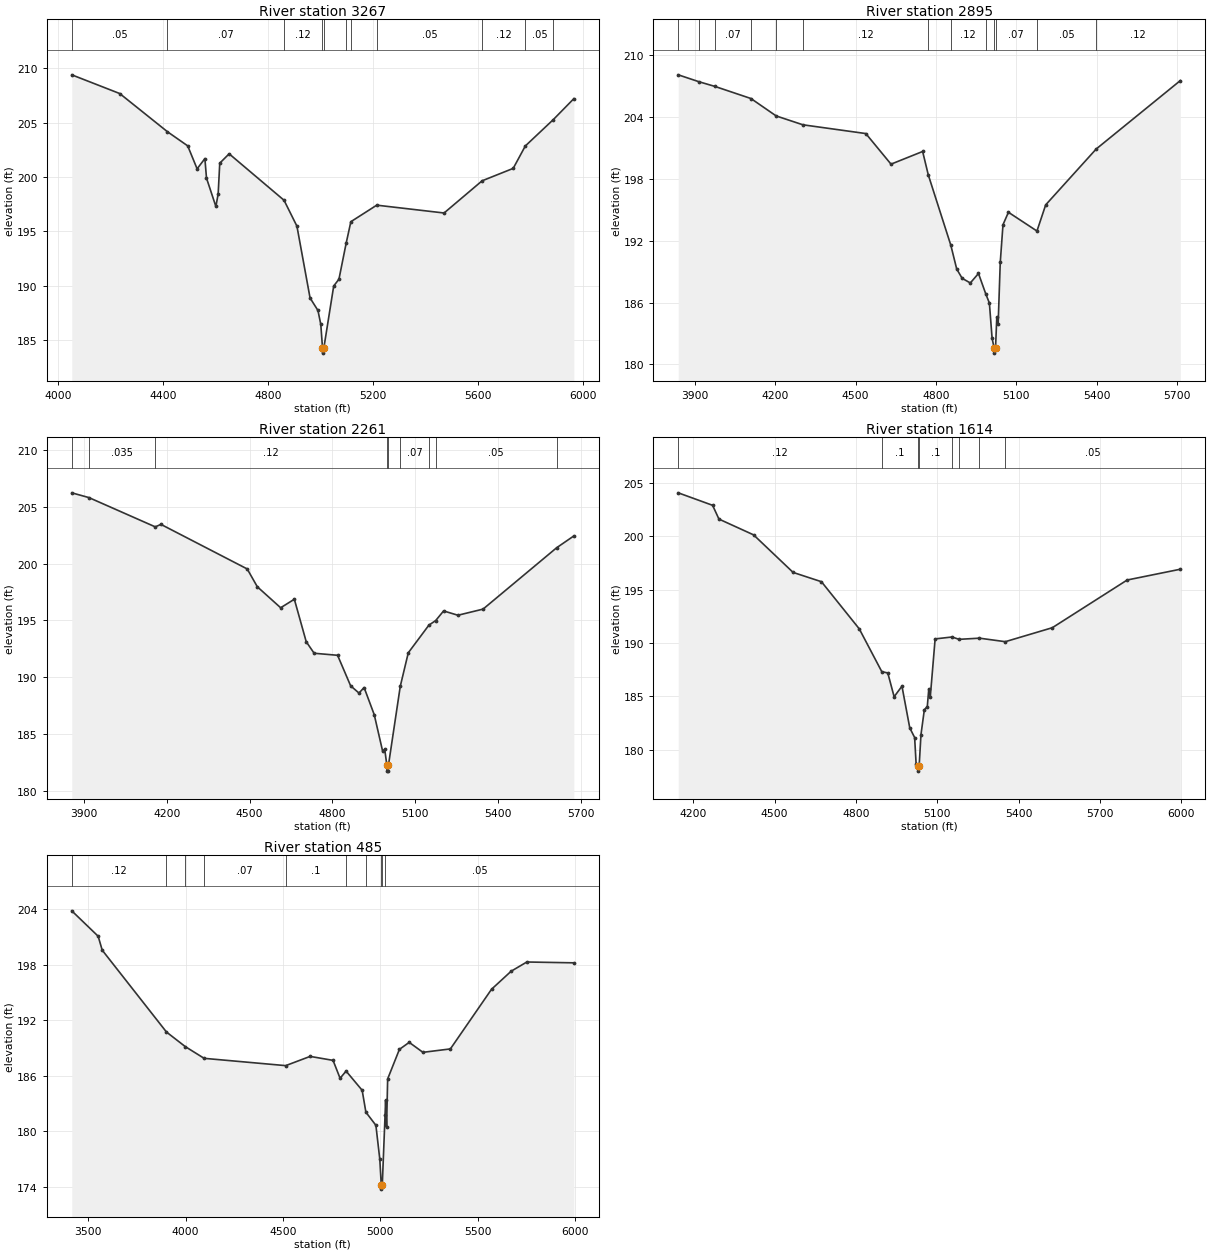
Type RM Length L Ch R = 1 ,3267    ,372,372,372
BEGIN DESCRIPTION:
Mapping XS 716b5452
END DESCRIPTION:
XS GIS Cut Line= 4
      2486854.07     13501581.75      2486307.17     13501201.52
      2485442.58     13501258.81      2485083.22     13501389.02
#Sta/Elev= 30
  4051.5  209.39  4234.4  207.67  4416.4  204.16  4493.7  202.86  4529.5  200.75
  4559.2  201.69  4565.3   199.9  4601.1  197.29  4609.8  198.44  4615.9  201.27
  4651.7  202.13  4861.1  197.86  4910.2  195.48  4960.3  188.88  4990.4  187.73
  5001.2  186.45  5007.7  184.31  5008.1  183.81    5013  184.31  5050.5  189.98
  5070.5  190.61  5098.1  193.93  5115.9  195.89  5214.6  197.41  5471.4  196.69
  5616.5  199.65    5735  200.79  5781.2  202.85  5888.2  205.28  5966.3   207.2
#Mann= 11 ,-1 , 0
  4051.5     .05       0  4416.4     .07       0  4861.1     .12       0
  5007.7     .05       0    5013     .12       0  5098.1     .07       0
  5115.9     .12       0  5214.6     .05       0  5616.5     .12       0
  5781.2     .05       0  5888.2     .12       0
Bank Sta=5007.7,5013
XS Rating Curve= 0 ,0
Exp/Cntr=0.3,0.1

Type RM Length L Ch R = 1 ,2895    ,634,634,634
BEGIN DESCRIPTION:
Mapping XS 0c9ef6d7
END DESCRIPTION:
XS GIS Cut Line= 4
      2486908.72     13501385.54      2486231.65      13500960.2
      2485706.47     13500864.72       2485169.1     13500934.06
#Sta/Elev= 30
  3837.5   208.1  3914.9  207.43  3975.1  206.97  4109.1   205.8  4203.3  204.11
  4303.2  203.25  4538.1   202.4  4632.2  199.43  4750.3  200.66  4771.4  198.39
  4855.5  191.57  4877.6  189.25  4897.9  188.35  4928.4   187.9  4958.9  188.82
  4986.1  186.84  4999.6  185.95  5009.7  182.54  5017.3  181.59  5017.7  181.09
  5022.6  181.59  5027.3  184.59  5032.3  183.89  5040.2  189.89  5050.4  193.55
  5070.7  194.76  5177.3  192.94  5209.9  195.48  5398.5   200.9  5712.7  207.54
#Mann= 13 ,-1 , 0
  3837.5     .05       0  3914.9     .12       0  3975.1     .07       0
  4109.1     .12       0  4203.3     .07       0  4303.2     .12       0
  4771.4      .1       0  4855.5     .12       0  4986.1     .07       0
  5017.3     .05       0  5022.6     .07       0  5177.3     .05       0
  5398.5     .12       0
Bank Sta=5017.3,5022.6
XS Rating Curve= 0 ,0
Exp/Cntr=0.3,0.1

Type RM Length L Ch R = 1 ,2261    ,647,647,647
BEGIN DESCRIPTION:
Mapping XS 83afc496
END DESCRIPTION:
XS GIS Cut Line= 4
      2486860.98     13501194.58      2486257.69     13500461.07
      2485862.72      13500313.5        2485420.     13500382.95
#Sta/Elev= 30
  3855.5  206.24  3917.7  205.82  4158.1  203.24  4178.6  203.46  4491.3  199.53
  4527.9  197.96  4612.5  196.11  4662.1  196.86  4705.1  193.12  4733.8   192.1
  4818.8  191.92  4866.1  189.23  4896.4  188.59  4914.9  189.08  4951.7  186.68
    4982  183.47  4989.6  183.64  4997.5  182.21    4998  181.71  5002.6  181.71
    5003  182.21    5046  189.19    5075  192.14  5149.8  194.58  5174.3  194.98
    5203  195.83  5254.9  195.45    5346  195.99  5612.7   201.4    5675  202.44
#Mann= 9 ,-1 , 0
  3855.5     .12       0  3917.7    .035       0  4158.1     .12       0
  4997.5     .05       0    5003     .12       0    5046     .07       0
  5149.8     .12       0  5174.3     .05       0  5612.7     .12       0
Bank Sta=4997.5,5003
XS Rating Curve= 0 ,0
Exp/Cntr=0.3,0.1

Type RM Length L Ch R = 1 ,1614    ,1129,1129,1129
BEGIN DESCRIPTION:
Mapping XS feaf5e72
END DESCRIPTION:
XS GIS Cut Line= 4
      2486850.39     13500977.16      2486433.72     13500024.02
      2485813.93     13499925.06      2485631.66     13499956.31
#Sta/Elev= 30
  4144.2  204.08    4271  202.91  4294.4  201.62  4422.3  200.14  4568.2  196.62
  4672.7  195.75  4812.3  191.33  4895.4  187.32  4917.5   187.2  4940.9  184.97
  4969.8  185.96  4998.6  182.05  5016.6  181.15    5022  178.69  5027.8   178.5
  5028.3     178  5033.3   178.5    5040  181.43  5052.4  183.75  5063.3  184.05
  5068.8   185.7  5074.3  184.95  5092.2  190.39  5154.7  190.57  5180.4  190.35
  5255.9  190.46  5351.1  190.13  5524.7  191.44  5800.9  195.91    5997  196.92
#Mann= 8 ,-1 , 0
  4144.2     .12       0  4895.4      .1       0  5027.8     .05       0
  5033.3      .1       0  5154.7     .12       0  5180.4     .05       0
  5255.9     .12       0  5351.1     .05       0
Bank Sta=5027.8,5033.3
XS Rating Curve= 0 ,0
Exp/Cntr=0.3,0.1

Type RM Length L Ch R = 1 ,485     ,0,0,0
BEGIN DESCRIPTION:
Mapping XS 348e1ee9
END DESCRIPTION:
XS GIS Cut Line= 4
      2486882.68     13500964.56      2487185.54      13499974.8
      2486771.48     13499826.36      2485675.11     13499698.76
#Sta/Elev= 30
  3415.2  203.85  3550.7   201.1  3571.6  199.59  3901.5  190.73  3998.2  189.15
  4095.1  187.88  4513.9  187.09  4639.5  188.09  4757.2  187.66  4793.3  185.72
  4824.1   186.5  4906.7  184.42  4925.8  182.05  4977.2  180.63  4997.3  176.95
  5004.6  174.22    5005  173.72  5010.1  174.22  5024.4  181.79  5027.1  183.36
  5032.1  180.42  5037.6  185.65    5098  188.85  5148.3  189.61  5218.8  188.53
  5359.8   188.9  5571.2  195.36  5671.8  197.31  5752.4  198.31  5993.9  198.22
#Mann= 10 ,-1 , 0
  3415.2     .12       0  3901.5     .07       0  3998.2     .12       0
  4095.1     .07       0  4513.9      .1       0  4824.1     .12       0
  4925.8     .07       0  5004.6     .05       0  5010.1     .07       0
  5024.4     .05       0
Bank Sta=5004.6,5010.1
XS Rating Curve= 0 ,0
Exp/Cntr=0.3,0.1

Chan Stop Cuts=-1
Use User Specified Reach Order=0
Composite Channel Slope=5