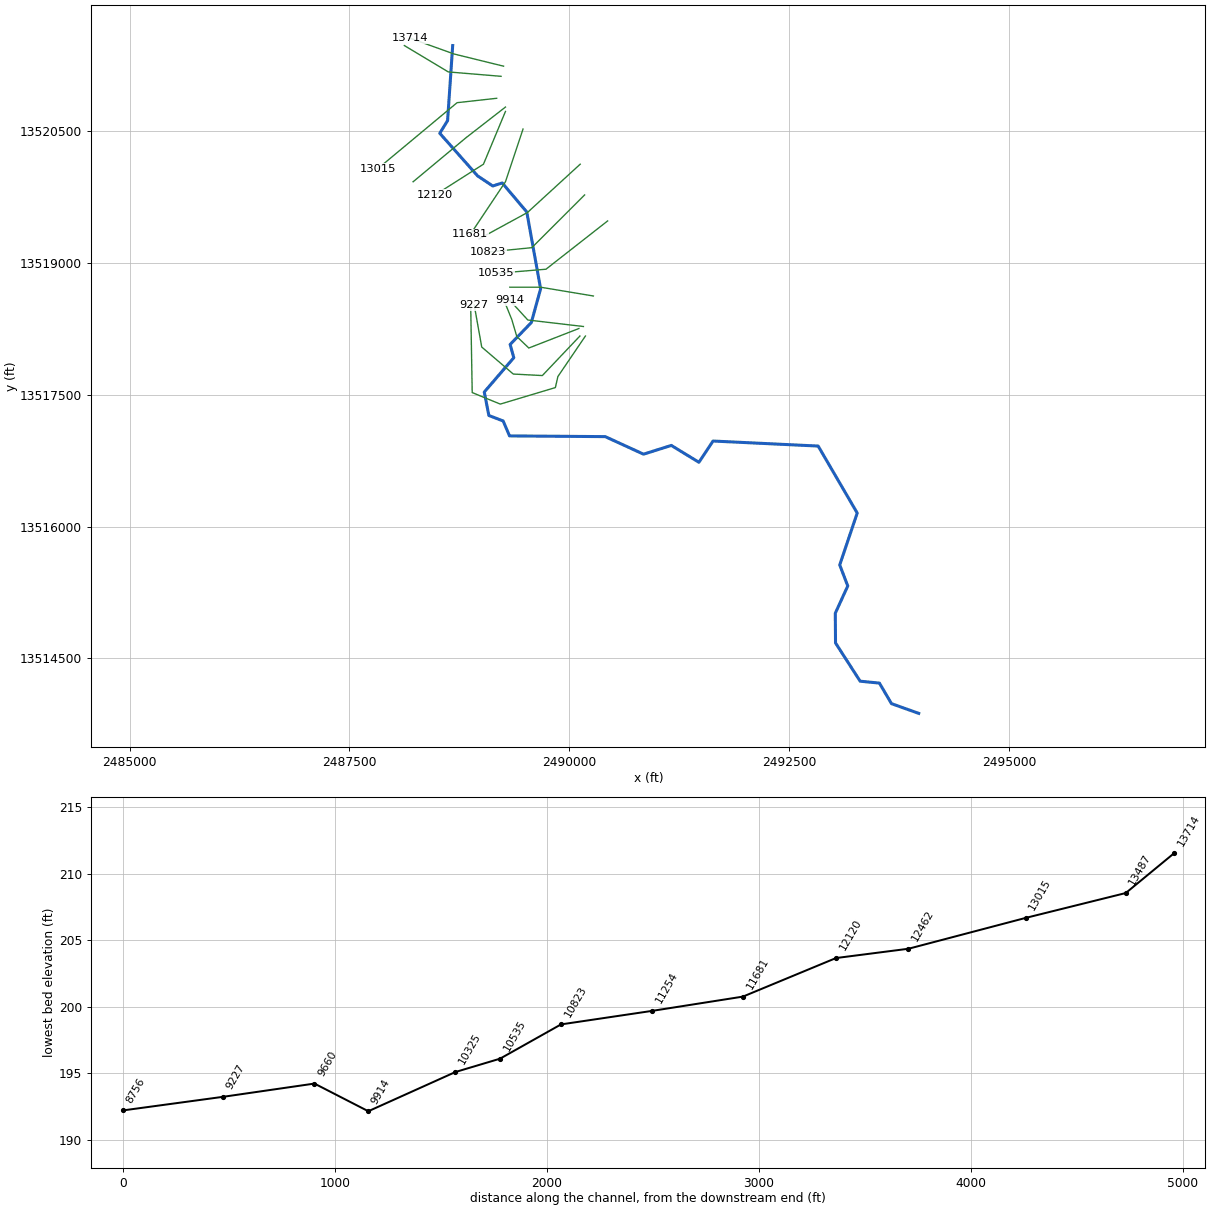
--- TRIB 7 TO FIFTEENMILE CREEK.prj (project) ---

Proj Title=TRIB 7 TO FIFTEENMILE CREEK Base Level Engineering
Current Plan=p01
Default Exp/Contr=0.3,0.1
English Units
Geom File=g01
Flow File=f01
Plan File=p01
BEGIN DESCRIPTION:
TRIB 7 TO FIFTEENMILE CREEK
END DESCRIPTION:

--- TRIB 7 TO FIFTEENMILE CREEK.p01 (plan) ---

Plan Title=Multiple Run
Short Identifier=Multiple
Geom File=g01
Flow File=f01
Subcritical Flow
K Sum by GR= 0
Std Step Tol= 0.01
Critical Tol= 0.01
Num of Std Step Trials= 20
Max Error Tol= 0.3
Flow Tol Ratio= 0.001
Split Flow NTrial= 30
Split Flow Tol= 0.02
Split Flow Ratio= 0.02
Log Output Level= 0
Friction Slope Method= 1
Unsteady Friction Slope Method= 2
Unsteady Bridges Friction Slope Method= 1
Parabolic Critical Depth
Global Vel Dist=  1 , 1 , 1
Global Log Level= 0
CheckData=True
Encroach Param= -1, 0, 0, 0
BEGIN DESCRIPTION:
Multiple Run
END DESCRIPTION:

--- TRIB 7 TO FIFTEENMILE CREEK.f01 (steady flow) ---

Flow Title=Multiple
Number of Profiles=7
Profile Names=10-year,25-year,50-year,1pct_min,100-year,1pct_plu,500-year
River Rch & RM= TRIB 7 TO FIFTEE,Reach-1,13714
     570     908    1210     780    1557    3107    2551
River Rch & RM= TRIB 7 TO FIFTEE,Reach-1,12462
     595     949    1266     818    1632    3256    2679
River Rch & RM= TRIB 7 TO FIFTEE,Reach-1,11254
     735    1181    1581    1024    2043    4076    3374
Boundary for River Rch & Prof#=TRIB 7 TO FIFTEE,Reach-1,1
Up Type=0
Dn Type=3
Dn Slope=0.005
Boundary for River Rch & Prof#=TRIB 7 TO FIFTEE,Reach-1,2
Up Type=0
Dn Type=3
Dn Slope=0.005
Boundary for River Rch & Prof#=TRIB 7 TO FIFTEE,Reach-1,3
Up Type=0
Dn Type=3
Dn Slope=0.005
Boundary for River Rch & Prof#=TRIB 7 TO FIFTEE,Reach-1,4
Up Type=0
Dn Type=3
Dn Slope=0.005
Boundary for River Rch & Prof#=TRIB 7 TO FIFTEE,Reach-1,5
Up Type=0
Dn Type=3
Dn Slope=0.005
Boundary for River Rch & Prof#=TRIB 7 TO FIFTEE,Reach-1,6
Up Type=0
Dn Type=3
Dn Slope=0.005
Boundary for River Rch & Prof#=TRIB 7 TO FIFTEE,Reach-1,7
Up Type=0
Dn Type=3
Dn Slope=0.005

--- TRIB 7 TO FIFTEENMILE CREEK.g01 (geometry) ---

Geom Title=Existing Conditions

River Reach=TRIB 7 TO FIFTEE,Reach-1
Reach XY= 30
      2488675.00     13521475.00      2488617.00     13520621.67
      2488528.11     13520476.65      2488958.33     13519991.65
      2489130.64     13519876.78      2489238.38     13519911.46
      2489517.48     13519581.04      2489674.81     13518706.72
      2489569.17     13518322.70      2489328.13     13518073.37
      2489369.91     13517922.70      2489034.13     13517531.74
      2489086.24     13517264.95      2489248.82     13517202.68
      2489321.31     13517032.70      2490409.79     13517024.49
      2490845.16     13516824.68      2491161.03     13516924.47
      2491475.03     13516732.48      2491635.47     13516974.43
      2492831.17     13516917.14      2493275.21     13516154.95
      2493076.19     13515564.50      2493167.70     13515325.08
      2493025.77     13515014.31      2493028.54     13514676.47
      2493308.33     13514241.39      2493527.67     13514219.58
      2493665.00     13513985.63      2493975.00     13513875.00

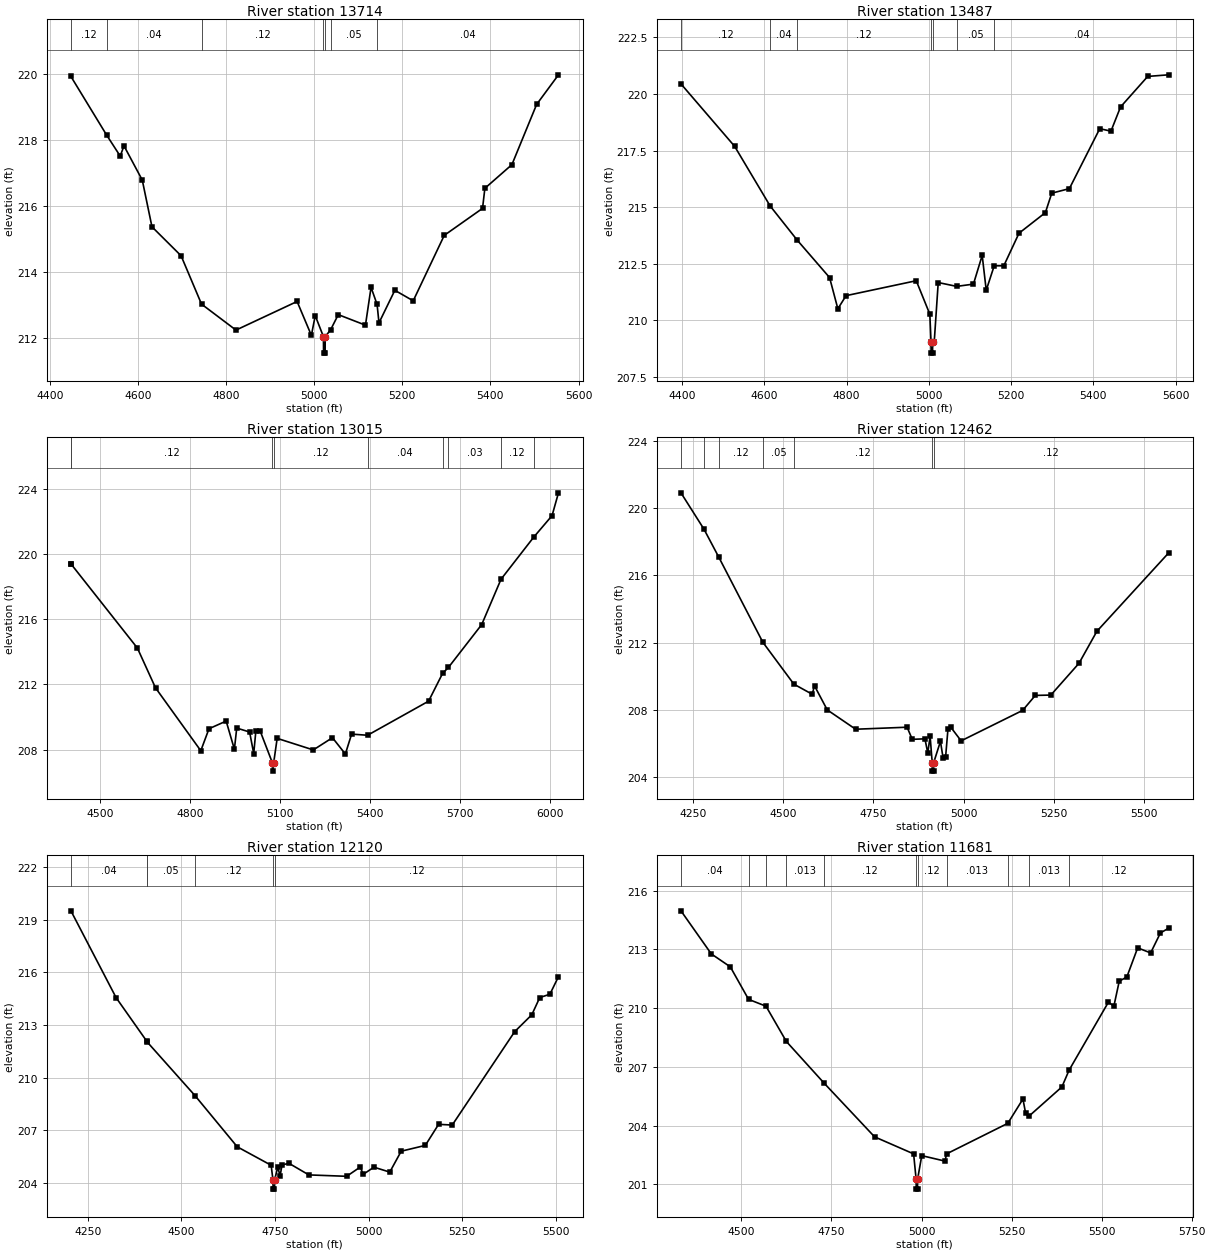
Type RM Length L Ch R = 1,13714,227,227,227
BEGIN DESCRIPTION:
Mapping XS 634509f1
END DESCRIPTION:
XS GIS Cut Line= 3
      2489253.66     13521240.40      2488689.40     13521379.29
      2488194.63     13521557.24
#Sta/Elev= 30
  4447.6  219.94  4528.6  218.16  4559.5  217.52  4568.1  217.83  4609.6  216.79
  4631.6  215.37  4697.7  214.49  4744.1  213.02  4822.3  212.23  4961.1  213.10
  4993.5  212.07  5002.3  212.67  5020.9  212.03  5021.2  211.53  5024.7  211.53
  5024.9  212.03  5037.2  212.24  5054.6  212.70  5116.3  212.38  5129.0  213.53
  5142.7  213.01  5147.0  212.45  5183.0  213.44  5224.7  213.12  5295.2  215.11
  5382.1  215.93  5387.4  216.54  5448.8  217.26  5504.9  219.09  5554.5  219.99
#Mann=7,-1,0
  4447.6    0.12       0  4528.6    0.04       0  4744.1    0.12       0
  5020.9    0.05       0  5024.9    0.12       0  5037.2    0.05       0
  5142.7    0.04       0
Bank Sta=5020.9,5024.9
Exp/Cntr=0.3,0.1

Type RM Length L Ch R = 1,13487,472,472,472
BEGIN DESCRIPTION:
TRIB 7 TO FIFTEENMILE CREEK 19.0
END DESCRIPTION:
XS GIS Cut Line= 3
      2489225.04     13521125.00      2488625.00     13521175.00
      2488125.01     13521474.99
#Sta/Elev= 30
  4397.4  220.45  4527.9  217.69  4614.0  215.06  4680.2  213.54  4758.7  211.89
  4778.8  210.51  4798.8  211.09  4969.4  211.75  5002.4  210.27  5005.3  209.05
  5005.5  208.55  5009.0  208.55  5009.3  209.05  5013.1  209.05  5022.8  211.67
  5067.7  211.50  5108.4  211.60  5129.7  212.87  5139.5  211.33  5158.9  212.41
  5182.2  212.41  5219.2  213.85  5283.3  214.76  5298.8  215.62  5341.6  215.82
  5415.5  218.47  5442.7  218.36  5466.0  219.43  5532.1  220.78  5582.6  220.85
#Mann=7,-1,0
  4397.4    0.12       0  4614.0    0.04       0  4680.2    0.12       0
  5005.3    0.05       0  5009.3    0.12       0  5067.7    0.05       0
  5158.9    0.04       0
Bank Sta=5005.3,5009.3
Exp/Cntr=0.3,0.1

Type RM Length L Ch R = 1,13015,553,553,553
BEGIN DESCRIPTION:
TRIB 7 TO FIFTEENMILE CREEK 18.0
END DESCRIPTION:
XS GIS Cut Line= 3
      2489175.03     13520875.00      2488725.00     13520825.00
      2487825.03     13520075.02
#Sta/Elev= 30
  4403.4  219.37  4404.4  219.37  4624.8  214.23  4685.2  211.79  4836.1  207.93
  4863.4  209.28  4920.6  209.75  4948.0  208.02  4955.8  209.32  4998.7  209.08
  5012.4  207.76  5019.6  209.15  5033.9  209.14  5074.8  207.18  5075.1  206.68
  5078.8  207.18  5090.5  208.69  5210.9  207.98  5274.7  208.73  5317.7  207.73
  5338.5  208.95  5391.7  208.88  5594.9  210.97  5641.8  212.68  5661.1  213.04
  5772.0  215.67  5836.3  218.45  5945.2  221.03  6006.3  222.35  6027.7  223.75
#Mann=9,-1,0
  4403.4    0.05       0  4404.4    0.12       0  5074.8    0.05       0
  5078.8    0.12       0  5391.7    0.04       0  5641.8    0.05       0
  5661.1    0.03       0  5836.3    0.12       0  5945.2    0.03       0
Bank Sta=5074.8,5078.8
Exp/Cntr=0.3,0.1

Type RM Length L Ch R = 1,12462,342,342,342
BEGIN DESCRIPTION:
TRIB 7 TO FIFTEENMILE CREEK 17.0
END DESCRIPTION:
XS GIS Cut Line= 3
      2489274.97     13520774.98      2488825.00     13520425.00
      2488224.98     13519924.98
#Sta/Elev= 30
  4216.6  220.90  4280.4  218.74  4321.6  217.07  4443.5  212.02  4529.5  209.53
  4580.3  208.93  4586.7  209.43  4622.0  208.00  4700.7  206.85  4843.3  206.97
  4857.6  206.25  4892.7  206.28  4900.6  205.44  4907.1  206.43  4912.9  204.86
  4913.1  204.36  4916.6  204.36  4916.9  204.86  4935.7  206.13  4942.9  205.16
  4950.0  205.20  4956.5  206.85  4964.3  206.97  4993.0  206.16  5163.5  207.97
  5198.6  208.86  5241.6  208.88  5319.7  210.77  5369.2  212.67  5567.7  217.32
#Mann=7,-1,0
  4216.6    0.05       0  4280.4    0.04       0  4321.6    0.12       0
  4443.5    0.05       0  4529.5    0.12       0  4912.9    0.05       0
  4916.9    0.12       0
Bank Sta=4912.9,4916.9
Exp/Cntr=0.3,0.1

Type RM Length L Ch R = 1,12120,439,439,439
BEGIN DESCRIPTION:
TRIB 7 TO FIFTEENMILE CREEK 16.0
END DESCRIPTION:
XS GIS Cut Line= 3
      2489275.01     13520725.03      2489025.00     13520125.00
      2488474.96     13519774.97
#Sta/Elev= 30
  4205.0  219.51  4325.8  214.56  4407.7  212.08  4409.1  212.03  4536.2  208.99
  4649.2  206.07  4739.7  205.02  4744.7  204.16  4744.9  203.66  4748.4  203.66
  4748.7  204.16  4757.5  204.92  4763.5  204.41  4768.9  205.04  4787.3  205.13
  4840.4  204.47  4941.4  204.39  4977.8  204.92  4985.4  204.50  5014.2  204.91
  5056.5  204.63  5087.0  205.82  5151.4  206.15  5186.9  207.35  5223.3  207.31
  5390.1  212.63  5435.8  213.59  5457.0  214.57  5484.1  214.76  5507.0  215.76
#Mann=6,-1,0
  4205.0    0.04       0  4407.7    0.12       0  4409.1    0.05       0
  4536.2    0.12       0  4744.7    0.05       0  4748.7    0.12       0
Bank Sta=4744.7,4748.7
Exp/Cntr=0.3,0.1

Type RM Length L Ch R = 1,11681,427,427,427
BEGIN DESCRIPTION:
TRIB 7 TO FIFTEENMILE CREEK 15.0
END DESCRIPTION:
XS GIS Cut Line= 3
      2489474.99     13520524.96      2489275.00     13519925.00
      2488875.01     13519325.02
#Sta/Elev= 30
  4332.2  214.97  4416.5  212.77  4469.2  212.11  4519.9  210.45  4568.3  210.10
  4624.8  208.30  4729.7  206.17  4869.7  203.43  4978.1  202.56  4985.1  201.26
  4985.4  200.76  4988.9  200.76  4989.1  201.26  5000.7  202.47  5065.3  202.19
  5069.6  202.56  5239.6  204.12  5281.6  205.36  5289.1  204.63  5298.0  204.48
  5389.8  205.98  5409.6  206.83  5519.0  210.31  5534.0  210.10  5549.0  211.38
  5570.0  211.59  5600.1  213.08  5636.1  212.82  5663.2  213.84  5685.7  214.08
#Mann=11,-1,0
  4332.2    0.04       0  4519.9   0.013       0  4568.3    0.12       0
  4624.8   0.013       0  4729.7    0.12       0  4985.1    0.05       0
  4989.1    0.12       0  5069.6   0.013       0  5239.6    0.12       0
  5298.0   0.013       0  5409.6    0.12       0
Bank Sta=4985.1,4989.1
Exp/Cntr=0.3,0.1

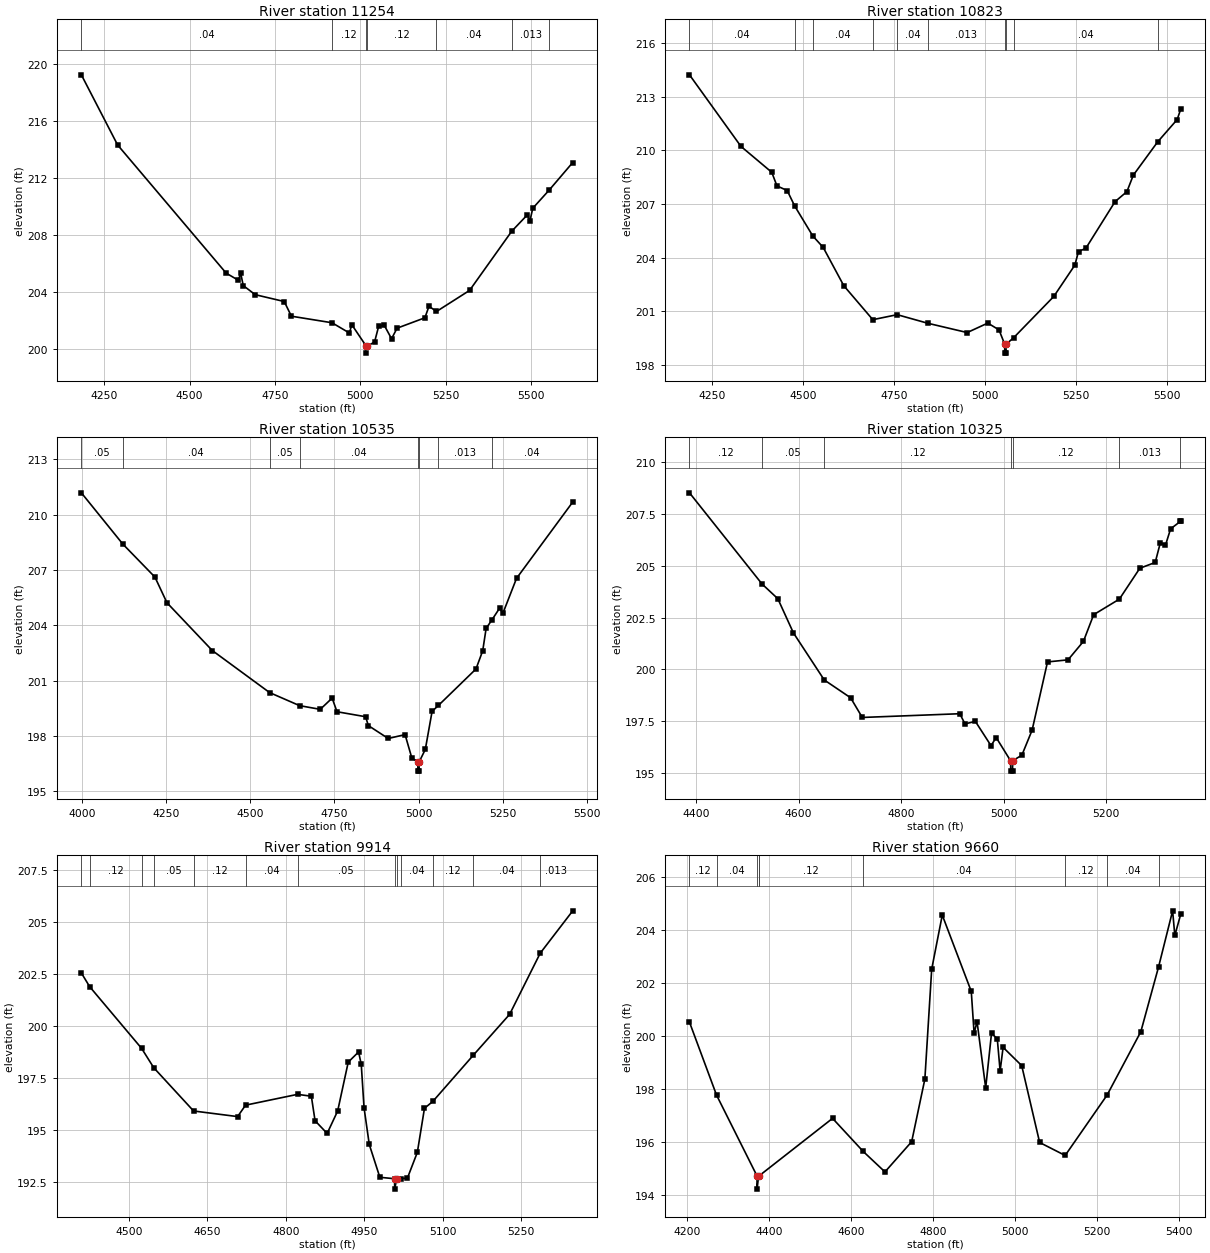
Type RM Length L Ch R = 1,11254,431,431,431
BEGIN DESCRIPTION:
TRIB 7 TO FIFTEENMILE CREEK 14.0
END DESCRIPTION:
XS GIS Cut Line= 3
      2490124.98     13520124.98      2489525.00     13519575.00
      2488975.01     13519275.01
#Sta/Elev= 30
  4182.5  219.21  4288.8  214.29  4607.0  205.30  4642.8  204.80  4649.6  205.29
  4657.0  204.43  4692.1  203.79  4777.2  203.31  4798.2  202.28  4917.3  201.82
  4968.4  201.10  4975.1  201.69  5017.2  200.19  5017.4  199.69  5021.2  200.19
  5042.0  200.47  5053.8  201.56  5070.0  201.66  5091.8  200.70  5108.0  201.44
  5189.6  202.17  5201.5  202.98  5223.5  202.61  5320.6  204.09  5444.1  208.24
  5489.5  209.38  5497.6  208.98  5505.7  209.85  5554.4  211.14  5622.9  213.06
#Mann=7,-1,0
  4182.5    0.04       0  4917.3    0.12       0  5017.2    0.05       0
  5021.2    0.12       0  5223.5    0.04       0  5444.1   0.013       0
  5554.4    0.12       0
Bank Sta=5017.2,5021.2
Exp/Cntr=0.3,0.1

Type RM Length L Ch R = 1,10823,288,288,288
BEGIN DESCRIPTION:
TRIB 7 TO FIFTEENMILE CREEK 13.0
END DESCRIPTION:
XS GIS Cut Line= 3
      2490175.03     13519775.03      2489575.00     13519175.00
      2489074.96     13519125.00
#Sta/Elev= 30
  4187.2  214.23  4328.7  210.23  4413.5  208.78  4427.7  208.02  4455.9  207.76
  4476.4  206.90  4526.3  205.22  4554.9  204.58  4611.5  202.44  4691.3  200.54
  4758.3  200.82  4842.5  200.34  4950.9  199.82  5007.5  200.35  5038.3  199.97
  5053.9  199.17  5054.1  198.67  5057.6  198.67  5057.9  199.17  5078.5  199.53
  5189.0  201.84  5246.8  203.59  5256.9  204.35  5277.0  204.53  5357.4  207.14
  5390.0  207.70  5407.6  208.62  5474.5  210.48  5528.2  211.73  5538.3  212.33
#Mann=10,-1,0
  4187.2    0.04       0  4476.4   0.013       0  4526.3    0.04       0
  4691.3   0.013       0  4758.3    0.04       0  4842.5   0.013       0
  5053.9    0.03       0  5057.9   0.013       0  5078.5    0.04       0
  5474.5   0.013       0
Bank Sta=5053.9,5057.9
Exp/Cntr=0.3,0.1

Type RM Length L Ch R = 1,10535,210,210,210
BEGIN DESCRIPTION:
Mapping XS 36db66db
END DESCRIPTION:
XS GIS Cut Line= 3
      2490437.12     13519479.36      2489735.69     13518929.59
      2489168.46     13518882.32
#Sta/Elev= 30
  3997.7  211.18  4120.5  208.41  4216.4  206.61  4252.1  205.22  4386.8  202.63
  4557.1  200.35  4646.4  199.64  4707.7  199.44  4743.0  200.05  4757.5  199.31
  4842.5  199.04  4850.6  198.56  4909.7  197.86  4959.8  198.07  4979.9  196.80
  4997.7  196.59  4997.9  196.09  5001.4  196.09  5001.7  196.59  5020.0  197.27
  5040.1  199.33  5058.8  199.65  5170.6  201.63  5190.6  202.62  5200.7  203.83
  5217.6  204.28  5240.5  204.92  5250.8  204.66  5291.0  206.54  5458.1  210.68
#Mann=8,-1,0
  3997.7    0.05       0  4120.5    0.04       0  4557.1    0.05       0
  4646.4    0.04       0  4997.7    0.04       0  5001.7    0.04       0
  5058.8   0.013       0  5217.6    0.04       0
Bank Sta=4997.7,5001.7
Exp/Cntr=0.3,0.1

Type RM Length L Ch R = 1,10325,411,411,411
BEGIN DESCRIPTION:
TRIB 7 TO FIFTEENMILE CREEK 12.0
END DESCRIPTION:
XS GIS Cut Line= 3
      2490274.96     13518625.01      2489675.00     13518725.00
      2489325.04     13518725.00
#Sta/Elev= 30
  4387.2  208.52  4528.7  204.12  4559.5  203.41  4589.9  201.76  4650.0  199.49
  4701.4  198.63  4724.2  197.68  4914.3  197.86  4924.5  197.37  4944.7  197.49
  4975.2  196.32  4985.3  196.71  5013.4  195.59  5013.7  195.09  5017.2  195.09
  5017.4  195.59  5035.4  195.86  5055.4  197.07  5085.4  200.36  5125.4  200.46
  5155.4  201.35  5175.4  202.64  5225.5  203.39  5265.4  204.88  5295.4  205.16
  5305.4  206.11  5315.4  205.99  5325.4  206.78  5344.4  207.14  5345.4  207.14
#Mann=7,-1,0
  4387.2    0.12       0  4528.7    0.05       0  4650.0    0.12       0
  5013.4    0.05       0  5017.4    0.12       0  5225.5   0.013       0
  5344.4    0.04       0
Bank Sta=5013.4,5017.4
Exp/Cntr=0.3,0.1

Type RM Length L Ch R = 1,9914,254,254,254
BEGIN DESCRIPTION:
TRIB 7 TO FIFTEENMILE CREEK 11.0
END DESCRIPTION:
XS GIS Cut Line= 3
      2490161.59     13518277.80      2489529.28     13518351.86
      2489324.97     13518575.03
#Sta/Elev= 30
  4409.2  202.54  4425.1  201.88  4524.4  198.91  4547.6  197.98  4623.7  195.90
  4707.8  195.63  4723.1  196.18  4822.4  196.70  4848.8  196.61  4855.9  195.43
  4879.0  194.82  4899.1  195.90  4919.3  198.25  4939.1  198.74  4944.2  198.14
  4949.5  196.06  4959.5  194.29  4979.7  192.71  5007.9  192.64  5008.1  192.14
  5011.9  192.64  5021.0  192.65  5032.4  192.67  5051.4  193.91  5065.0  196.03
  5081.0  196.36  5158.6  198.59  5227.8  200.55  5286.2  203.49  5348.4  205.53
#Mann=13,-1,0
  4409.2    0.05       0  4425.1    0.12       0  4524.4    0.04       0
  4547.6    0.05       0  4623.7    0.12       0  4723.1    0.04       0
  4822.4    0.05       0  5007.9    0.05       0  5011.9    0.05       0
  5021.0    0.04       0  5081.0    0.12       0  5158.6    0.04       0
  5286.2   0.013       0
Bank Sta=5007.9,5011.9
Exp/Cntr=0.3,0.1

Type RM Length L Ch R = 1,9660,433,433,433
BEGIN DESCRIPTION:
4880
END DESCRIPTION:
XS GIS Cut Line= 5
      2490110.36     13518255.02      2489540.67     13518032.84
      2489403.95     13518163.86      2489346.98     13518357.56
      2489272.93     13518539.84
#Sta/Elev= 30
  4206.1  200.52  4272.1  197.77  4370.9  194.72  4371.1  194.22  4374.9  194.72
  4376.0  194.72  4555.4  196.89  4630.3  195.64  4683.3  194.87  4748.5  196.01
  4780.7  198.37  4797.4  202.52  4823.2  204.56  4894.0  201.68  4900.9  200.10
  4908.1  200.54  4929.2  198.04  4943.4  200.10  4957.5  199.89  4964.4  198.68
  4971.7  199.57  5017.1  198.88  5060.9  195.98  5123.2  195.49  5225.6  197.77
  5307.9  200.16  5351.3  202.61  5385.5  204.72  5390.9  203.79  5405.6  204.61
#Mann=9,-1,0
  4206.1    0.12       0  4272.1    0.04       0  4370.9    0.04       0
  4374.9    0.04       0  4376.0    0.12       0  4630.3    0.04       0
  5123.2    0.12       0  5225.6    0.04       0  5351.3   0.013       0
Bank Sta=4370.9,4374.9
Exp/Cntr=0.3,0.1

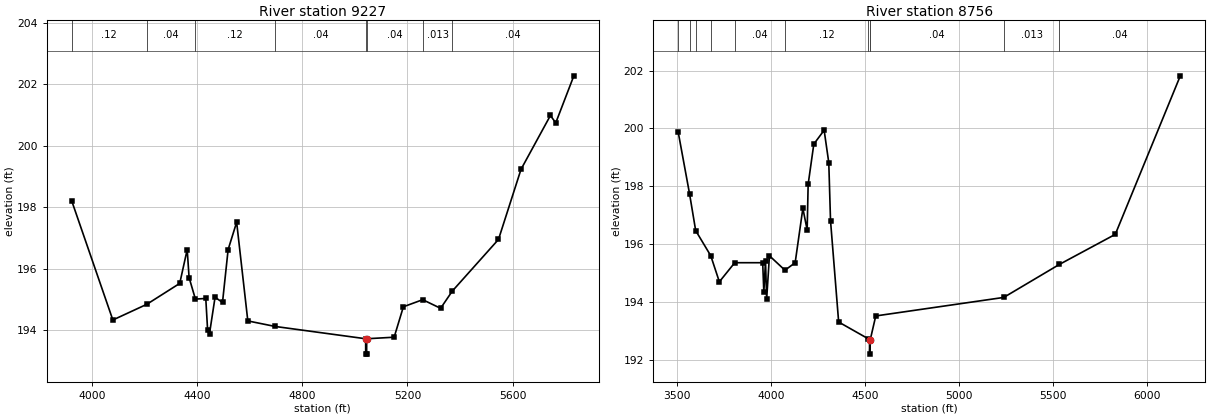
Type RM Length L Ch R = 1,9227,471,471,471
BEGIN DESCRIPTION:
4881
END DESCRIPTION:
XS GIS Cut Line= 5
      2490121.76     13518169.57      2489694.49     13517719.51
      2489364.07     13517736.60      2489005.17     13518044.23
      2488919.72     13518522.73
#Sta/Elev= 30
  3922.7  198.21  4079.4  194.33  4208.5  194.84  4333.8  195.52  4362.2  196.62
  4369.4  195.71  4393.4  195.01  4432.9  195.03  4439.8  194.01  4447.1  193.89
  4468.2  195.07  4496.5  194.90  4517.9  196.62  4550.3  197.51  4592.8  194.30
  4696.6  194.12  5041.0  193.72  5041.2  193.22  5044.7  193.22  5045.0  193.72
  5149.4  193.77  5184.5  194.76  5258.0  194.99  5326.1  194.71  5370.6  195.27
  5546.3  196.95  5632.0  199.23  5743.8  200.98  5764.1  200.74  5832.9  202.27
#Mann=8,-1,0
  3922.7    0.12       0  4208.5    0.04       0  4393.4    0.12       0
  4696.6    0.04       0  5041.0    0.04       0  5045.0    0.04       0
  5258.0   0.013       0  5370.6    0.04       0
Bank Sta=5041,5045
Exp/Cntr=0.3,0.1

Type RM Length L Ch R = 1,8756,0,0,0
BEGIN DESCRIPTION:
4879
END DESCRIPTION:
XS GIS Cut Line= 6
      2490184.42     13518169.57      2489871.09     13517708.12
      2489842.60     13517582.79      2489215.95     13517394.79
      2488896.93     13517525.82      2488879.85     13518510.72
#Sta/Elev= 30
  3506.4  199.89  3567.0  197.75  3599.8  196.47  3680.1  195.60  3725.7  194.70
  3807.5  195.36  3956.2  195.36  3962.3  194.34  3971.2  195.42  3977.2  194.09
  3992.1  195.60  4074.6  195.10  4128.9  195.36  4169.9  197.24  4192.7  196.49
  4198.0  198.07  4228.1  199.46  4283.0  199.94  4307.7  198.82  4317.0  196.81
  4360.2  193.31  4517.8  192.73  4524.4  192.70  4524.6  192.20  4528.4  192.70
  4557.5  193.52  5238.2  194.16  5533.9  195.30  5831.5  196.34  6177.3  201.82
#Mann=11,-1,0
  3506.4    0.05       0  3567.0    0.12       0  3599.8    0.05       0
  3680.1    0.12       0  3807.5    0.04       0  4074.6    0.12       0
  4517.8    0.04       0  4524.4    0.04       0  4528.4    0.04       0
  5238.2   0.013       0  5533.9    0.04       0
Bank Sta=4524.4,4528.4
Exp/Cntr=0.3,0.1

Chan Stop Cuts=-1