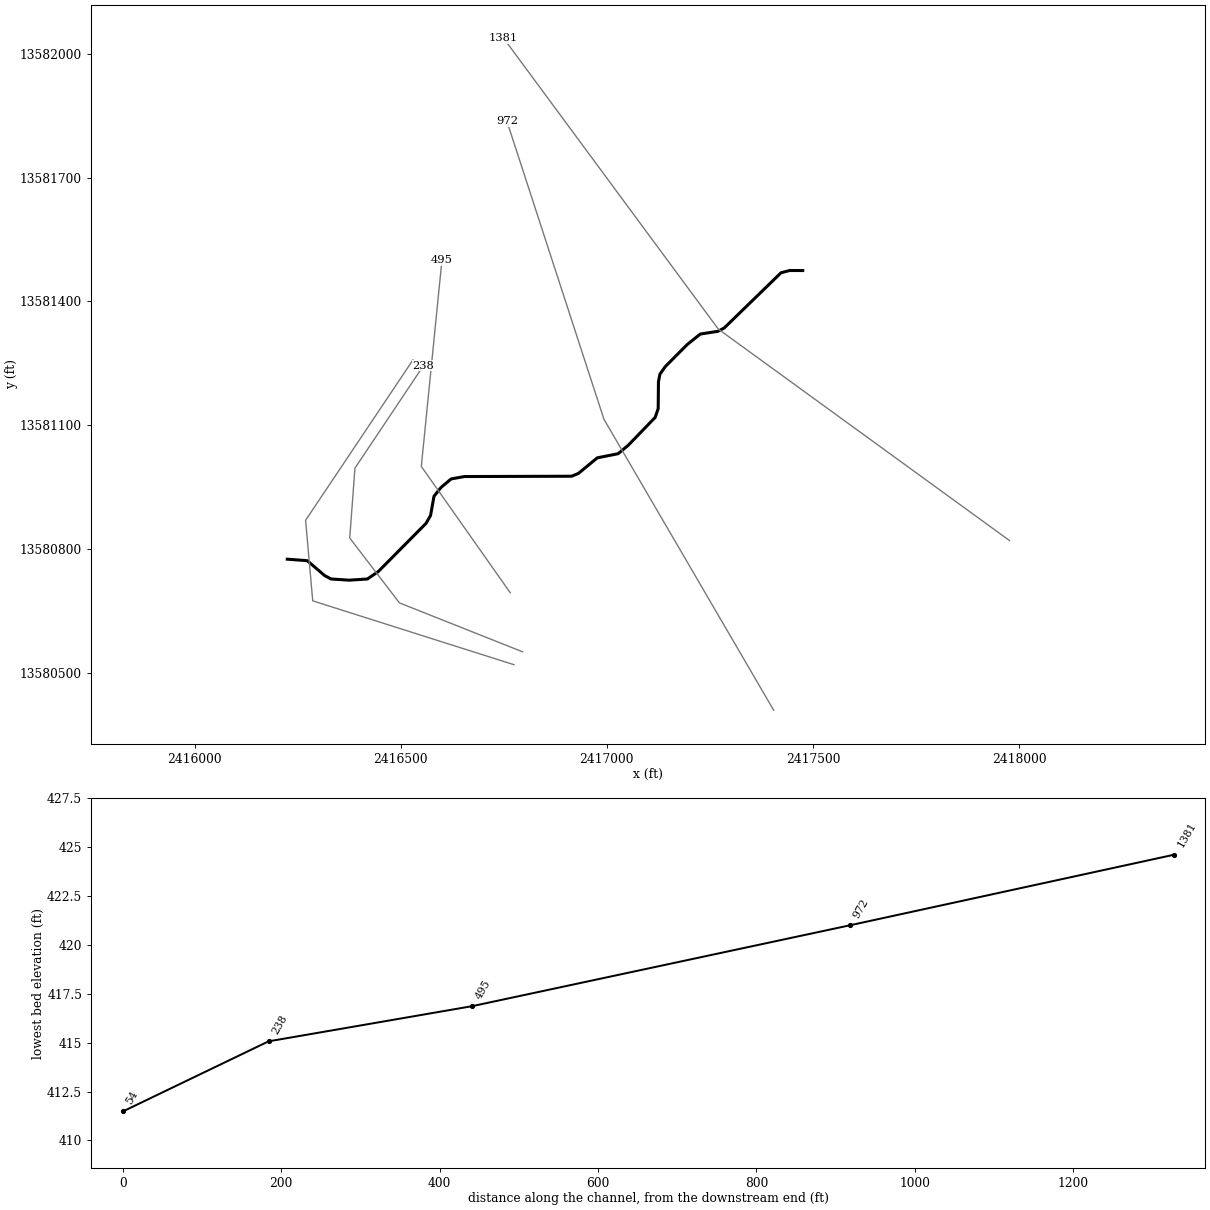
--- TRIB 7 TO LITTLE SALT CREEK.prj (project) ---

Proj Title=TRIB 7 TO LITTLE SALT CREEK Base Level Engineering
Current Plan=p01
Default Exp/Contr=0.3,0.1
English Units
Geom File=g01
Flow File=f01
Plan File=p01
BEGIN DESCRIPTION:
TRIB 7 TO LITTLE SALT CREEK
END DESCRIPTION:

--- TRIB 7 TO LITTLE SALT CREEK.p01 (plan) ---

Plan Title=Multiple Run
Short Identifier=Multiple
Geom File=g01
Flow File=f01
Subcritical Flow
K Sum by GR= 0
Std Step Tol= 0.01
Critical Tol= 0.01
Num of Std Step Trials= 20
Max Error Tol= 0.3
Flow Tol Ratio= 0.001
Split Flow NTrial= 30
Split Flow Tol= 0.02
Split Flow Ratio= 0.02
Log Output Level= 0
Friction Slope Method= 1
Unsteady Friction Slope Method= 2
Unsteady Bridges Friction Slope Method= 1
Parabolic Critical Depth
Global Vel Dist=  1 , 1 , 1
Global Log Level= 0
CheckData=True
Encroach Param= -1, 0, 0, 0
BEGIN DESCRIPTION:
Multiple Run
END DESCRIPTION:

--- TRIB 7 TO LITTLE SALT CREEK.f01 (steady flow) ---

Flow Title=Multiple
Number of Profiles=7
Profile Names=10-year,25-year,50-year,1pct_min,100-year,1pct_plu,500-year
River Rch & RM= TRIB 7 TO LITTLE,Reach-1,1381
     297     461     604     385     769    1534    1228
Boundary for River Rch & Prof#=TRIB 7 TO LITTLE,Reach-1,1
Up Type=0
Dn Type=3
Dn Slope=0.005
Boundary for River Rch & Prof#=TRIB 7 TO LITTLE,Reach-1,2
Up Type=0
Dn Type=3
Dn Slope=0.005
Boundary for River Rch & Prof#=TRIB 7 TO LITTLE,Reach-1,3
Up Type=0
Dn Type=3
Dn Slope=0.005
Boundary for River Rch & Prof#=TRIB 7 TO LITTLE,Reach-1,4
Up Type=0
Dn Type=3
Dn Slope=0.005
Boundary for River Rch & Prof#=TRIB 7 TO LITTLE,Reach-1,5
Up Type=0
Dn Type=3
Dn Slope=0.005
Boundary for River Rch & Prof#=TRIB 7 TO LITTLE,Reach-1,6
Up Type=0
Dn Type=3
Dn Slope=0.005
Boundary for River Rch & Prof#=TRIB 7 TO LITTLE,Reach-1,7
Up Type=0
Dn Type=3
Dn Slope=0.005

--- TRIB 7 TO LITTLE SALT CREEK.g01 (geometry) ---

Geom Title=Existing Conditions

River Reach=TRIB 7 TO LITTLE,Reach-1
Reach XY= 30
      2417475.00     13581475.00      2417443.12     13581475.07
      2417422.48     13581469.69      2417284.68     13581335.78
      2417268.95     13581327.54      2417226.63     13581321.03
      2417194.76     13581295.42      2417141.44     13581241.79
      2417128.61     13581223.51      2417125.13     13581204.95
      2417124.48     13581140.21      2417117.14     13581118.81
      2417051.89     13581051.26      2417027.31     13581030.82
      2416976.75     13581020.78      2416931.08     13580983.09
      2416914.50     13580976.20      2416654.75     13580975.46
      2416622.30     13580969.64      2416597.81     13580948.97
      2416580.74     13580927.58      2416572.45     13580881.09
      2416561.36     13580861.80      2416445.16     13580744.58
      2416419.11     13580726.96      2416375.02     13580724.14
      2416330.92     13580727.02      2416315.26     13580735.52
      2416273.49     13580771.35      2416225.00     13580775.00

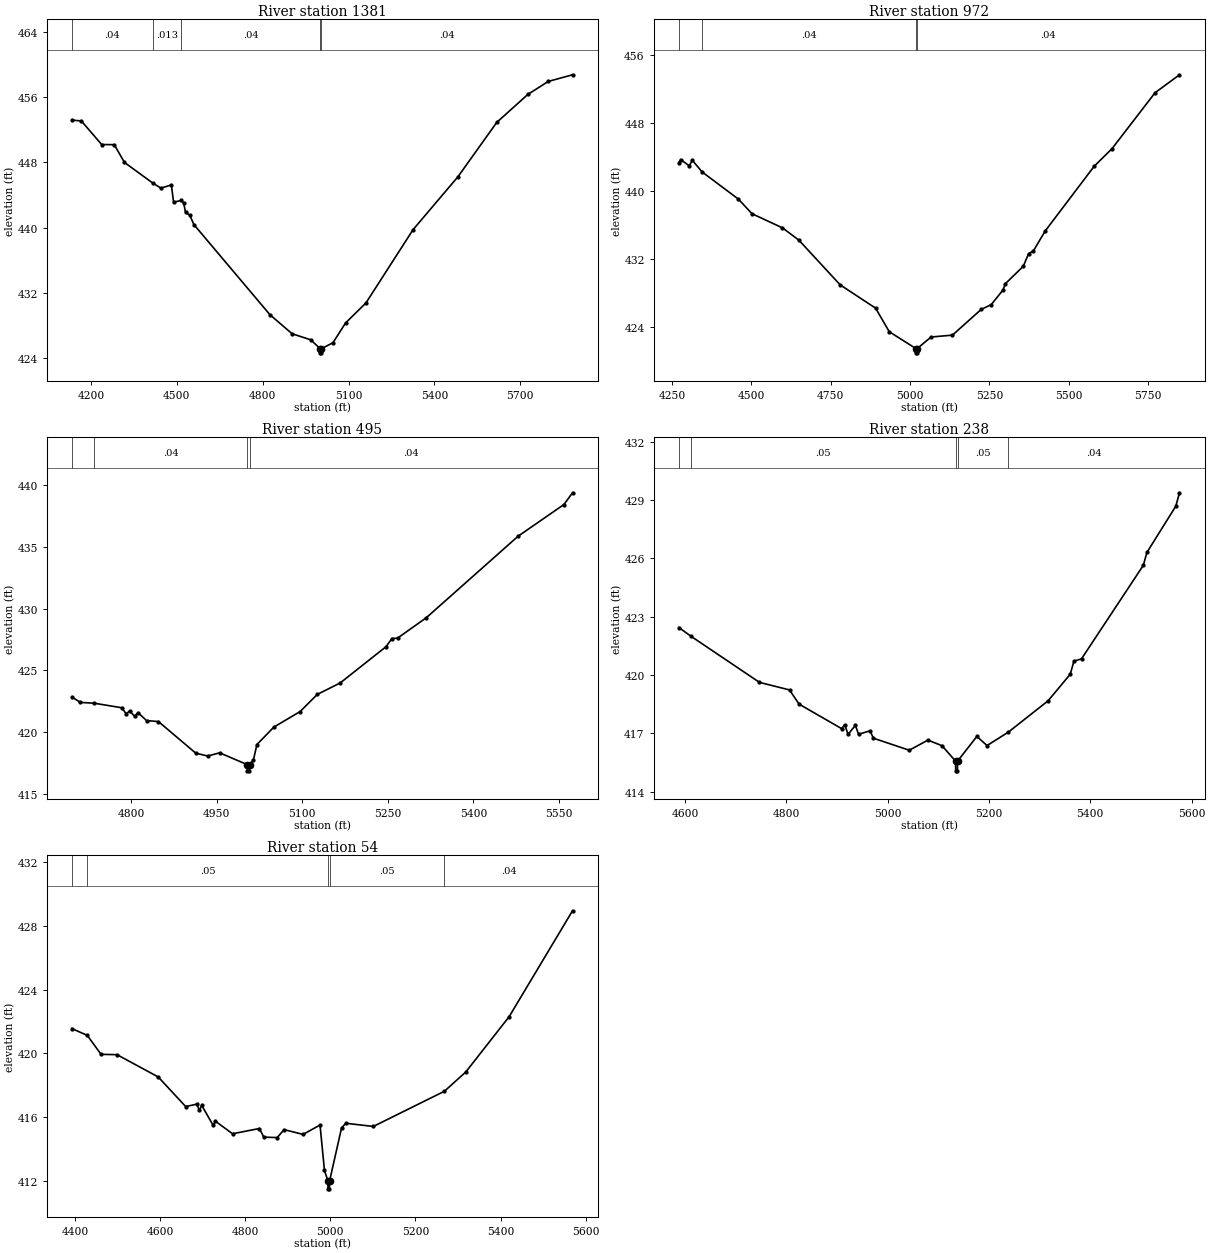
Type RM Length L Ch R = 1,1381,409,409,409
BEGIN DESCRIPTION:
LGII4621
END DESCRIPTION:
XS GIS Cut Line= 3
      2417976.26     13580820.38      2417270.23     13581333.09
      2416749.57     13582038.50
#Sta/Elev= 30
  4133.2  453.18  4166.1  453.09  4237.2  450.19  4281.3  450.17  4316.9  447.99
  4415.4  445.47  4444.4  444.84  4480.8  445.23  4488.5  443.12  4515.3  443.32
  4524.0  443.00  4530.2  441.85  4544.9  441.53  4559.6  440.36  4825.5  429.29
  4902.8  426.96  4967.7  426.22  5001.1  425.12  5001.4  424.62  5004.9  424.62
  5005.1  425.12  5045.7  425.87  5089.6  428.29  5160.6  430.74  5325.6  439.75
  5482.1  446.23  5617.9  452.91  5726.5  456.34  5797.5  457.93  5882.5  458.75
#Mann=5,-1,0
  4133.2    0.04       0  4415.4   0.013       0  4515.3    0.04       0
  5001.1    0.04       0  5005.1    0.04       0
Bank Sta=5001.1,5005.1
Exp/Cntr=0.3,0.1

Type RM Length L Ch R = 1,972,477,477,477
BEGIN DESCRIPTION:
LGII4620
END DESCRIPTION:
XS GIS Cut Line= 3
      2417404.72     13580408.48      2416992.85     13581114.55
      2416757.51     13581837.39
#Sta/Elev= 30
  4271.2  443.38  4276.8  443.73  4304.1  442.98  4313.5  443.65  4344.1  442.28
  4458.7  439.08  4501.7  437.36  4597.6  435.70  4649.2  434.26  4779.5  429.00
  4891.2  426.26  4934.2  423.49  5018.2  421.51  5018.4  421.01  5021.9  421.01
  5022.2  421.51  5066.0  422.87  5133.3  423.09  5223.8  426.11  5255.7  426.68
  5292.9  428.41  5299.4  429.11  5356.7  431.19  5373.0  432.65  5388.7  433.01
  5425.9  435.35  5580.2  442.95  5636.0  445.00  5771.8  451.58  5848.8  453.69
#Mann=4,-1,0
  4271.2   0.013       0  4344.1    0.04       0  5018.2    0.04       0
  5022.2    0.04       0
Bank Sta=5018.2,5022.2
Exp/Cntr=0.3,0.1

Type RM Length L Ch R = 1,495,257,257,257
BEGIN DESCRIPTION:
LGII4619
END DESCRIPTION:
XS GIS Cut Line= 3
      2416765.71     13580693.58      2416550.00     13581000.00
      2416600.00     13581499.97
#Sta/Elev= 30
  4696.6  422.85  4711.6  422.41  4735.3  422.35  4783.9  421.98  4791.7  421.49
  4797.8  421.72  4806.5  421.29  4812.6  421.58  4827.4  420.94  4848.3  420.86
  4913.7  418.30  4934.6  418.07  4955.5  418.33  5004.0  417.37  5004.3  416.87
  5007.8  416.87  5008.0  417.37  5014.7  417.75  5020.8  419.00  5050.4  420.41
  5096.5  421.67  5126.6  423.06  5166.8  423.99  5247.2  426.93  5257.3  427.58
  5267.3  427.62  5317.6  429.27  5478.4  435.87  5558.8  438.44  5573.8  439.39
#Mann=4,-1,0
  4696.6    0.05       0  4735.3    0.04       0  5004.0    0.04       0
  5008.0    0.04       0
Bank Sta=5004,5008
Exp/Cntr=0.3,0.1

Type RM Length L Ch R = 1,238,184,184,184
BEGIN DESCRIPTION:
LGII4618
END DESCRIPTION:
XS GIS Cut Line= 5
      2416795.65     13580550.37      2416496.93     13580669.06
      2416376.38     13580826.41      2416389.05     13580995.87
      2416555.22     13581244.33
#Sta/Elev= 30
  4587.6  422.44  4611.6  421.99  4746.7  419.62  4806.1  419.23  4825.0  418.50
  4909.0  417.24  4915.3  417.44  4921.6  416.94  4936.1  417.41  4942.4  416.95
  4965.2  417.13  4971.5  416.75  5042.5  416.13  5079.4  416.65  5107.3  416.36
  5133.9  415.57  5134.2  415.07  5137.7  415.07  5137.9  415.57  5176.0  416.84
  5196.1  416.37  5238.1  417.06  5316.6  418.67  5360.4  420.04  5367.6  420.71
  5382.6  420.83  5504.7  425.64  5511.7  426.30  5568.8  428.68  5576.1  429.37
#Mann=5,-1,0
  4587.6    0.04       0  4611.6    0.05       0  5133.9    0.05       0
  5137.9    0.05       0  5238.1    0.04       0
Bank Sta=5133.9,5137.9
Exp/Cntr=0.3,0.1

Type RM Length L Ch R = 1,54,0,0,0
BEGIN DESCRIPTION:
4884
END DESCRIPTION:
XS GIS Cut Line= 4
      2416774.79     13580519.12      2416286.69     13580673.96
      2416269.33     13580869.28      2416529.70     13581258.21
#Sta/Elev= 30
  4392.9  421.55  4429.1  421.12  4461.4  419.93  4498.9  419.91  4595.7  418.51
  4660.3  416.65  4686.4  416.80  4692.6  416.41  4697.8  416.73  4724.8  415.47
  4730.1  415.73  4770.4  414.94  4833.3  415.27  4843.8  414.73  4875.3  414.70
  4891.4  415.20  4936.1  414.90  4975.9  415.49  4986.3  412.64  4994.4  411.98
  4994.6  411.48  4998.1  411.48  4998.4  411.98  5026.5  415.31  5036.5  415.60
  5101.1  415.40  5268.1  417.61  5318.3  418.82  5420.3  422.30  5569.1  428.95
#Mann=5,-1,0
  4392.9    0.04       0  4429.1    0.05       0  4994.4    0.05       0
  4998.4    0.05       0  5268.1    0.04       0
Bank Sta=4994.4,4998.4
Exp/Cntr=0.3,0.1

Chan Stop Cuts=-1