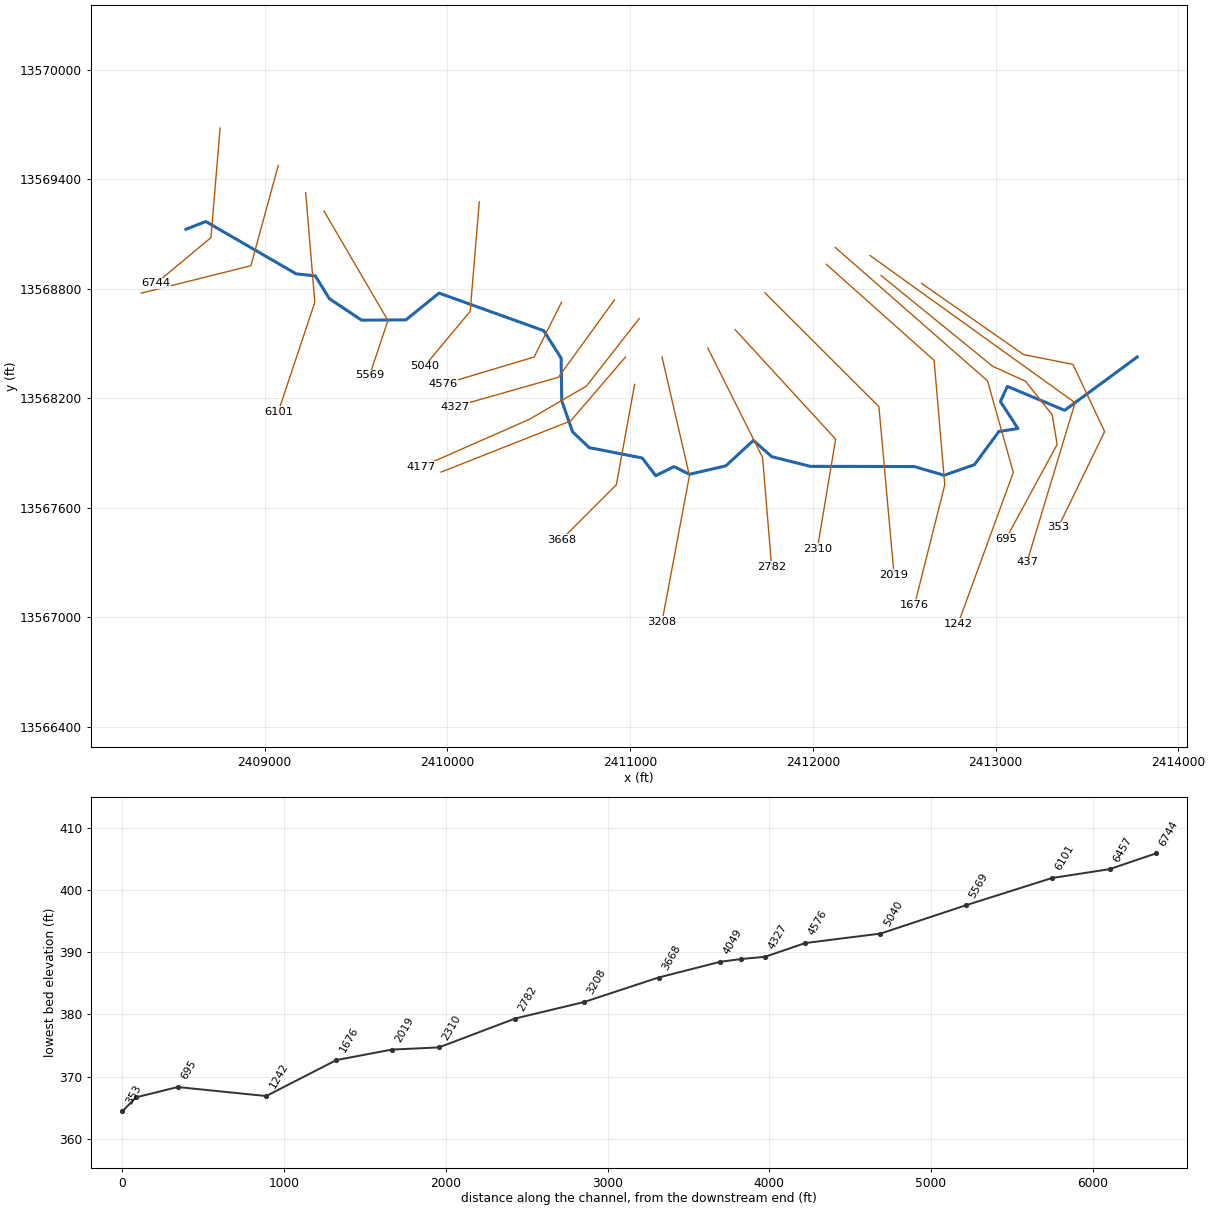
--- TRIB 7 TO SALT CREEK.prj (project) ---

Proj Title=TRIB 7 TO SALT CREEK Base Level Engineering
Current Plan=p01
Default Exp/Contr=0.3,0.1
English Units
Geom File=g01
Flow File=f01
Plan File=p01
BEGIN DESCRIPTION:
TRIB 7 TO SALT CREEK
END DESCRIPTION:

--- TRIB 7 TO SALT CREEK.p01 (plan) ---

Plan Title=Multiple Run
Short Identifier=Multiple
Geom File=g01
Flow File=f01
Subcritical Flow
K Sum by GR= 0
Std Step Tol= 0.01
Critical Tol= 0.01
Num of Std Step Trials= 20
Max Error Tol= 0.3
Flow Tol Ratio= 0.001
Split Flow NTrial= 30
Split Flow Tol= 0.02
Split Flow Ratio= 0.02
Log Output Level= 0
Friction Slope Method= 1
Unsteady Friction Slope Method= 2
Unsteady Bridges Friction Slope Method= 1
Parabolic Critical Depth
Global Vel Dist=  1 , 1 , 1
Global Log Level= 0
CheckData=True
Encroach Param= -1, 0, 0, 0
BEGIN DESCRIPTION:
Multiple Run
END DESCRIPTION:

--- TRIB 7 TO SALT CREEK.f01 (steady flow) ---

Flow Title=Multiple
Number of Profiles=7
Profile Names=10-year,25-year,50-year,1pct_min,100-year,1pct_plu,500-year
River Rch & RM= TRIB 7 TO SALT C,Reach-1,6744
     649    1061    1438     944    1883    3757    3202
River Rch & RM= TRIB 7 TO SALT C,Reach-1,3208
     895    1488    2039    1353    2699    5385    4688
Boundary for River Rch & Prof#=TRIB 7 TO SALT C,Reach-1,1
Up Type=0
Dn Type=3
Dn Slope=0.005
Boundary for River Rch & Prof#=TRIB 7 TO SALT C,Reach-1,2
Up Type=0
Dn Type=3
Dn Slope=0.005
Boundary for River Rch & Prof#=TRIB 7 TO SALT C,Reach-1,3
Up Type=0
Dn Type=3
Dn Slope=0.005
Boundary for River Rch & Prof#=TRIB 7 TO SALT C,Reach-1,4
Up Type=0
Dn Type=3
Dn Slope=0.005
Boundary for River Rch & Prof#=TRIB 7 TO SALT C,Reach-1,5
Up Type=0
Dn Type=3
Dn Slope=0.005
Boundary for River Rch & Prof#=TRIB 7 TO SALT C,Reach-1,6
Up Type=0
Dn Type=3
Dn Slope=0.005
Boundary for River Rch & Prof#=TRIB 7 TO SALT C,Reach-1,7
Up Type=0
Dn Type=3
Dn Slope=0.005

--- TRIB 7 TO SALT CREEK.g01 (geometry) ---

Geom Title=Existing Conditions

River Reach=TRIB 7 TO SALT C,Reach-1
Reach XY= 30
      2408569.80     13569125.00      2408678.39     13569167.37
      2409172.68     13568880.77      2409277.67     13568869.58
      2409354.53     13568744.64      2409530.86     13568627.06
      2409773.54     13568628.54      2409954.79     13568775.36
      2410527.55     13568569.27      2410622.76     13568419.07
      2410626.22     13568185.50      2410685.51     13568015.19
      2410776.48     13567928.61      2411066.69     13567871.89
      2411140.22     13567774.92      2411240.41     13567824.83
      2411324.99     13567782.59      2411523.53     13567828.54
      2411675.00     13567967.92      2411776.47     13567878.57
      2411985.50     13567826.22      2412554.97     13567824.93
      2412719.03     13567777.17      2412884.81     13567835.51
      2413018.60     13568017.23      2413122.54     13568033.17
      2413026.59     13568181.13      2413064.50     13568264.04
      2413378.31     13568133.02      2413775.00     13568425.00

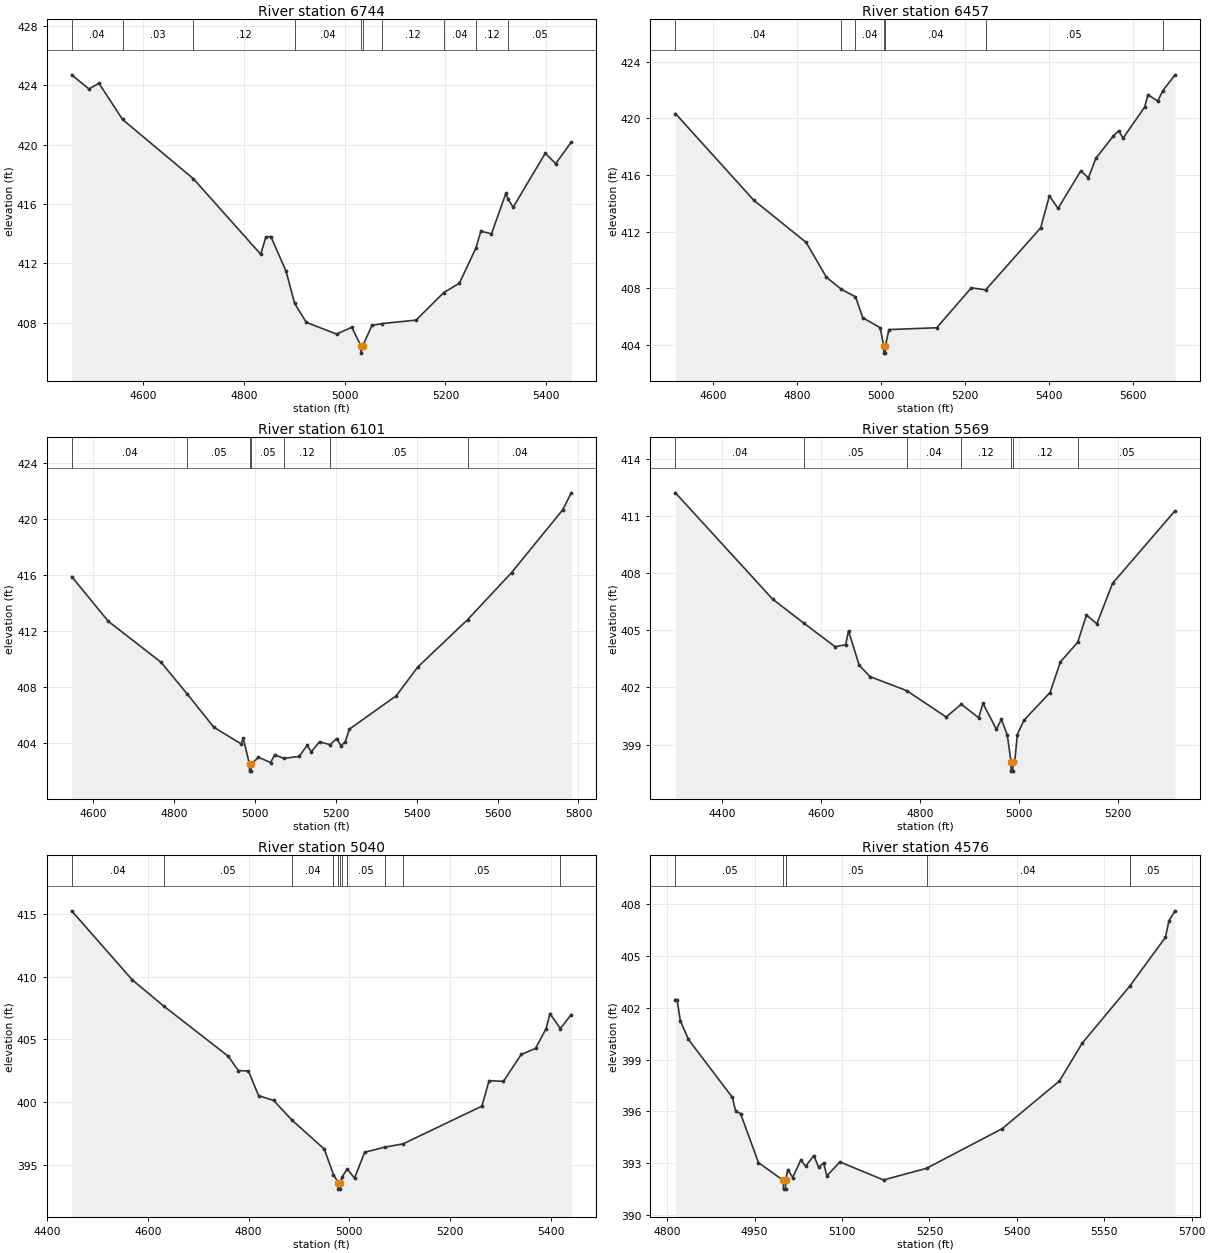
Type RM Length L Ch R = 1,6744,287,287,287
BEGIN DESCRIPTION:
TRIB 7 TO SALT CREEK 12.0
END DESCRIPTION:
XS GIS Cut Line= 3
      2408756.60     13569679.15      2408706.60     13569079.18
      2408407.10     13568829.60
#Sta/Elev= 30
  4458.0  424.69  4492.3  423.74  4512.3  424.12  4559.0  421.69  4699.7  417.70
  4833.4  412.62  4843.5  413.78  4853.5  413.81  4883.6  411.49  4900.6  409.32
  4923.8  408.04  4984.0  407.25  5014.1  407.71  5032.1  406.47  5032.4  405.97
  5036.1  406.47  5054.2  407.83  5074.4  407.96  5141.8  408.19  5196.5  410.04
  5227.7  410.67  5260.6  413.04  5270.4  414.17  5291.5  414.00  5320.1  416.72
  5324.3  416.33  5334.5  415.78  5398.2  419.41  5419.1  418.72  5449.9  420.17
#Mann=10,-1,0
  4458.0    0.04       0  4559.0    0.03       0  4699.7    0.12       0
  4900.6    0.04       0  5032.1    0.04       0  5036.1    0.04       0
  5074.4    0.12       0  5196.5    0.04       0  5260.6    0.12       0
  5324.3    0.05       0
Bank Sta=5032.1,5036.1
Exp/Cntr=0.3,0.1

Type RM Length L Ch R = 1,6457,356,356,356
BEGIN DESCRIPTION:
TRIB 7 TO SALT CREEK 11.0
END DESCRIPTION:
XS GIS Cut Line= 3
      2409075.00     13569475.01      2408925.00     13568925.00
      2408324.96     13568774.99
#Sta/Elev= 30
  4511.0  420.33  4697.6  414.21  4822.0  411.24  4870.3  408.78  4905.4  407.94
  4939.4  407.40  4956.7  405.93  4998.2  405.22  5006.5  403.93  5006.8  403.43
  5010.3  403.43  5010.5  403.93  5018.9  405.09  5132.6  405.22  5215.1  408.04
  5249.0  407.89  5380.0  412.27  5400.6  414.52  5421.3  413.64  5475.4  416.29
  5493.4  415.79  5511.4  417.18  5552.7  418.74  5565.6  419.12  5575.9  418.59
  5627.4  420.79  5635.1  421.66  5658.3  421.21  5670.5  421.94  5699.6  423.06
#Mann=7,-1,0
  4511.0    0.04       0  4905.4    0.05       0  4939.4    0.04       0
  5006.5    0.04       0  5010.5    0.04       0  5249.0    0.05       0
  5670.5    0.03       0
Bank Sta=5006.5,5010.5
Exp/Cntr=0.3,0.1

Type RM Length L Ch R = 1,6101,532,532,532
BEGIN DESCRIPTION:
TRIB 7 TO SALT CREEK 10.0
END DESCRIPTION:
XS GIS Cut Line= 3
      2409225.00     13569325.02      2409275.00     13568725.00
      2409074.98     13568124.95
#Sta/Elev= 30
  4547.6  415.90  4637.9  412.71  4768.4  409.78  4833.0  407.52  4898.8  405.14
  4966.6  403.94  4971.6  404.34  4987.1  402.50  4987.4  402.00  4990.9  402.00
  4991.1  402.50  5009.2  402.99  5039.3  402.61  5049.3  403.17  5072.0  402.91
  5109.6  403.05  5129.6  403.84  5139.7  403.38  5160.2  404.10  5186.4  403.89
  5202.4  404.33  5212.9  403.82  5223.5  404.08  5234.0  405.00  5350.0  407.39
  5402.7  409.43  5526.3  412.83  5634.6  416.18  5761.1  420.67  5782.2  421.88
#Mann=7,-1,0
  4547.6    0.04       0  4833.0    0.05       0  4987.1    0.05       0
  4991.1    0.05       0  5072.0    0.12       0  5186.4    0.05       0
  5526.3    0.04       0
Bank Sta=4987.1,4991.1
Exp/Cntr=0.3,0.1

Type RM Length L Ch R = 1,5569,529,529,529
BEGIN DESCRIPTION:
TRIB 7 TO SALT CREEK 9.0
END DESCRIPTION:
XS GIS Cut Line= 3
      2409325.02     13569224.97      2409675.00     13568625.00
      2409575.00     13568325.01
#Sta/Elev= 30
  4305.3  412.21  4502.1  406.63  4565.3  405.37  4628.2  404.14  4649.7  404.24
  4655.5  404.97  4677.0  403.17  4698.9  402.57  4773.4  401.83  4853.1  400.45
  4883.6  401.12  4918.8  400.41  4927.5  401.16  4954.8  399.80  4964.7  400.33
  4976.7  399.51  4984.2  398.11  4984.5  397.61  4988.0  397.61  4988.2  398.11
  4992.0  398.16  4997.0  399.53  5010.4  400.28  5063.1  401.73  5084.2  403.34
  5119.1  404.37  5136.9  405.80  5158.0  405.34  5189.6  407.46  5316.1  411.27
#Mann=7,-1,0
  4305.3    0.04       0  4565.3    0.05       0  4773.4    0.04       0
  4883.6    0.12       0  4984.2    0.05       0  4988.2    0.12       0
  5119.1    0.05       0
Bank Sta=4984.2,4988.2
Exp/Cntr=0.3,0.1

Type RM Length L Ch R = 1,5040,464,464,464
BEGIN DESCRIPTION:
TRIB 7 TO SALT CREEK 8.0
END DESCRIPTION:
XS GIS Cut Line= 3
      2410175.00     13569275.04      2410125.00     13568675.00
      2409875.02     13568375.03
#Sta/Elev= 30
  4448.4  415.24  4568.9  409.73  4631.2  407.65  4759.5  403.64  4779.6  402.50
  4799.7  402.46  4819.7  400.50  4849.8  400.11  4885.8  398.56  4950.2  396.24
  4968.6  394.20  4978.3  393.54  4978.5  393.04  4982.0  393.04  4982.3  393.54
  4985.5  394.00  4995.9  394.65  5010.4  393.92  5030.5  395.98  5070.7  396.39
  5106.8  396.65  5263.4  399.66  5277.7  401.69  5306.3  401.64  5341.5  403.78
  5370.1  404.27  5390.9  405.84  5398.7  407.04  5419.3  405.85  5441.0  406.97
#Mann=11,-1,0
  4448.4    0.04       0  4631.2    0.05       0  4885.8    0.04       0
  4968.6    0.05       0  4978.3    0.05       0  4982.3    0.05       0
  4985.5    0.04       0  4995.9    0.05       0  5070.7    0.04       0
  5106.8    0.05       0  5419.3    0.04       0
Bank Sta=4978.3,4982.3
Exp/Cntr=0.3,0.1

Type RM Length L Ch R = 1,4576,249,249,249
BEGIN DESCRIPTION:
TRIB 7 TO SALT CREEK 7.0
END DESCRIPTION:
XS GIS Cut Line= 3
      2410624.98     13568724.97      2410475.00     13568425.00
      2409974.99     13568275.00
#Sta/Elev= 30
  4814.1  402.46  4816.9  402.46  4822.5  401.24  4836.4  400.16  4911.9  396.81
  4917.5  396.01  4925.9  395.88  4956.6  393.05  4999.3  392.02  4999.6  391.52
  5003.1  391.52  5003.3  392.02  5006.9  392.65  5015.3  392.19  5029.3  393.20
  5037.7  392.84  5051.6  393.46  5060.0  392.77  5068.4  393.03  5074.0  392.29
  5096.4  393.09  5171.2  392.05  5245.0  392.72  5374.8  395.01  5473.1  397.76
  5512.3  399.95  5593.4  403.22  5655.0  406.05  5661.1  407.01  5671.5  407.58
#Mann=5,-1,0
  4814.1    0.05       0  4999.3    0.05       0  5003.3    0.05       0
  5245.0    0.04       0  5593.4    0.05       0
Bank Sta=4999.3,5003.3
Exp/Cntr=0.3,0.1

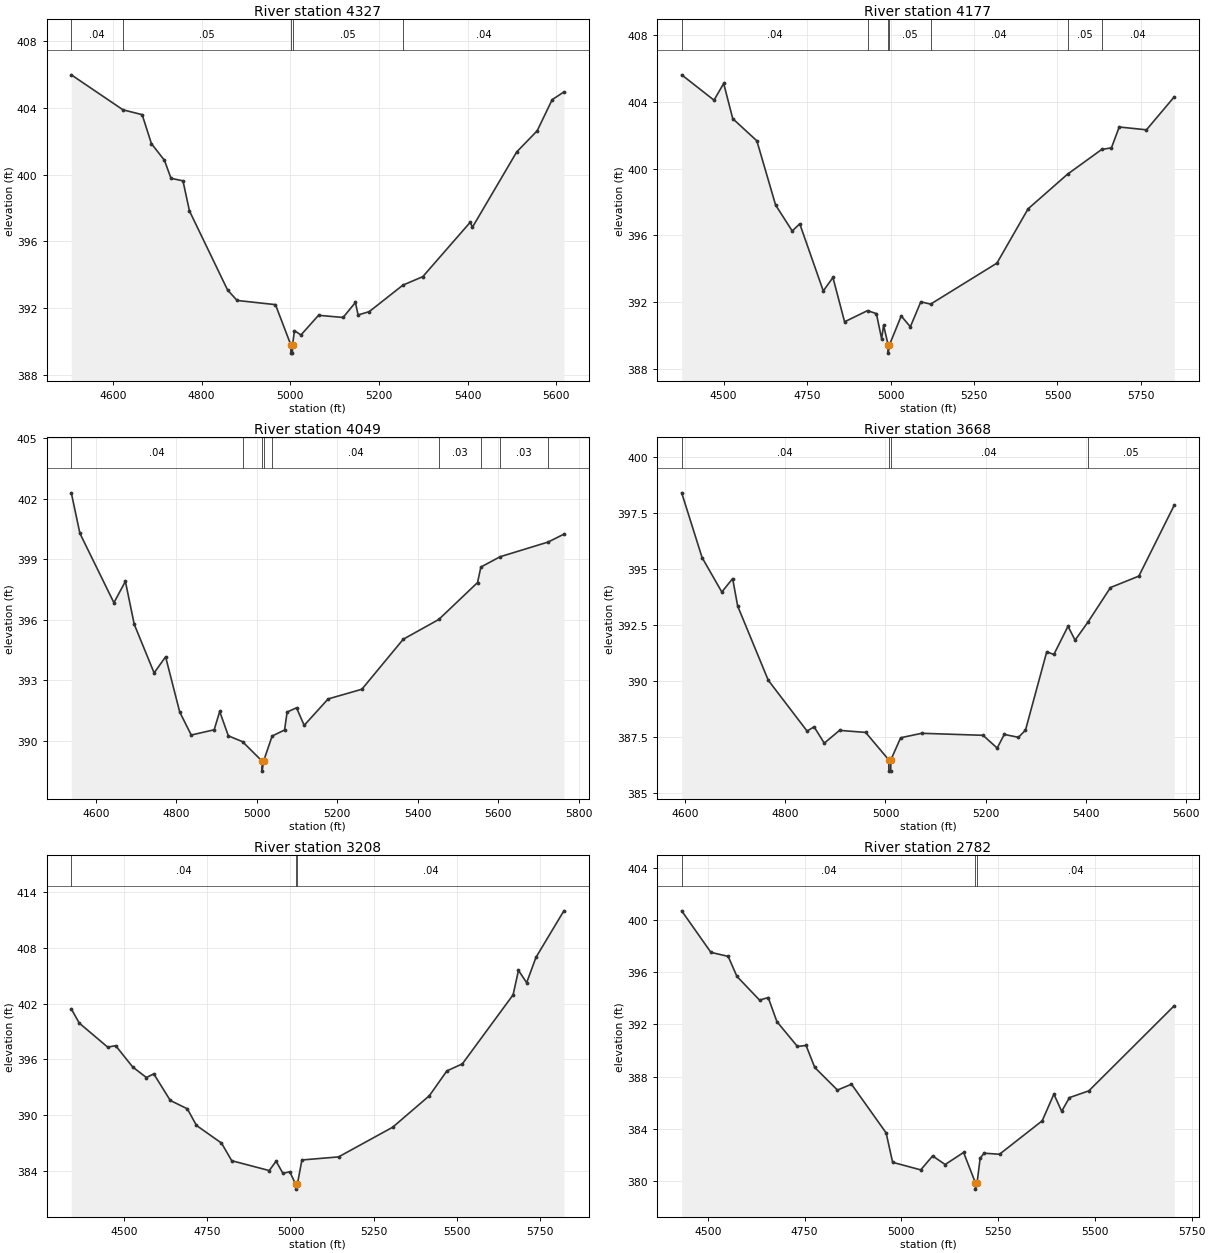
Type RM Length L Ch R = 1,4327,150,150,150
BEGIN DESCRIPTION:
Mapping XS 9857d5a3
END DESCRIPTION:
XS GIS Cut Line= 3
      2410914.86     13568737.87      2410607.96     13568314.05
      2410042.85     13568153.28
#Sta/Elev= 30
  4506.0  406.00  4622.6  403.90  4665.8  403.61  4686.7  401.87  4716.1  400.87
  4730.8  399.79  4757.8  399.64  4772.5  397.83  4858.4  393.09  4879.9  392.46
  4966.4  392.21  5001.0  389.80  5001.2  389.30  5004.7  389.30  5005.0  389.80
  5009.2  390.65  5023.9  390.39  5063.5  391.57  5118.9  391.44  5146.7  392.34
  5152.8  391.59  5177.9  391.79  5253.8  393.38  5298.7  393.89  5405.5  397.15
  5410.7  396.86  5510.6  401.38  5556.6  402.64  5590.4  404.51  5616.8  404.97
#Mann=5,-1,0
  4506.0    0.04       0  4622.6    0.05       0  5001.0    0.05       0
  5005.0    0.05       0  5253.8    0.04       0
Bank Sta=5001,5005
Exp/Cntr=0.3,0.1

Type RM Length L Ch R = 1,4177,128,128,128
BEGIN DESCRIPTION:
Mapping XS 1e4b86c0
END DESCRIPTION:
XS GIS Cut Line= 4
      2411050.20     13568635.57      2410761.17     13568265.81
      2410448.67     13568083.52      2409858.77     13567823.65
#Sta/Elev= 30
  4374.2  405.64  4471.0  404.12  4500.0  405.12  4527.2  403.01  4599.4  401.68
  4655.5  397.83  4705.3  396.27  4727.9  396.70  4798.4  392.67  4827.3  393.48
  4862.2  390.82  4930.9  391.49  4957.5  391.31  4973.2  389.80  4979.0  390.61
  4992.7  389.44  4992.9  388.94  4996.7  389.44  5031.9  391.17  5059.2  390.52
  5090.6  392.02  5119.9  391.88  5318.6  394.34  5412.0  397.60  5530.3  399.68
  5632.4  401.16  5661.7  401.26  5685.0  402.51  5766.6  402.34  5849.9  404.32
#Mann=7,-1,0
  4374.2    0.04       0  4930.9    0.05       0  4992.7    0.05       0
  4996.7    0.05       0  5119.9    0.04       0  5530.3    0.05       0
  5632.4    0.04       0
Bank Sta=4992.7,4996.7
Exp/Cntr=0.3,0.1

Type RM Length L Ch R = 1,4049,381,381,381
BEGIN DESCRIPTION:
TRIB 7 TO SALT CREEK 6.0
END DESCRIPTION:
XS GIS Cut Line= 3
      2410974.98     13568424.97      2410675.00     13568075.00
      2409965.56     13567794.56
#Sta/Elev= 30
  4539.0  402.29  4560.4  400.28  4644.9  396.84  4673.4  397.90  4695.4  395.77
  4744.8  393.36  4773.3  394.16  4808.4  391.42  4837.0  390.28  4894.0  390.54
  4907.7  391.45  4929.2  390.24  4964.5  389.95  5012.8  388.99  5013.1  388.49
  5016.8  388.99  5038.0  390.23  5068.9  390.53  5075.2  391.42  5098.6  391.63
  5117.6  390.76  5177.1  392.07  5260.9  392.55  5363.7  395.03  5452.0  396.01
  5548.3  397.84  5556.6  398.61  5604.3  399.12  5723.7  399.85  5762.8  400.24
#Mann=9,-1,0
  4539.0    0.04       0  4964.5    0.05       0  5012.8    0.05       0
  5016.8    0.05       0  5038.0    0.04       0  5452.0    0.03       0
  5556.6    0.05       0  5604.3    0.03       0  5723.7    0.04       0
Bank Sta=5012.8,5016.8
Exp/Cntr=0.3,0.1

Type RM Length L Ch R = 1,3668,460,460,460
BEGIN DESCRIPTION:
TRIB 7 TO SALT CREEK 5.0
END DESCRIPTION:
XS GIS Cut Line= 3
      2411025.00     13568275.02      2410925.00     13567725.00
      2410625.00     13567425.00
#Sta/Elev= 30
  4593.2  398.39  4633.9  395.50  4673.3  393.96  4694.9  394.56  4705.0  393.33
  4766.0  390.02  4843.5  387.75  4857.5  387.94  4877.8  387.21  4908.3  387.78
  4960.4  387.69  5006.7  386.46  5006.9  385.96  5010.4  385.96  5010.7  386.46
  5030.3  387.45  5072.2  387.65  5194.7  387.56  5223.0  386.99  5237.1  387.60
  5265.4  387.47  5279.5  387.79  5321.9  391.29  5336.1  391.17  5364.4  392.43
  5378.5  391.81  5403.7  392.60  5449.2  394.16  5505.8  394.67  5576.5  397.84
#Mann=4,-1,0
  4593.2    0.04       0  5006.7    0.04       0  5010.7    0.04       0
  5403.7    0.05       0
Bank Sta=5006.7,5010.7
Exp/Cntr=0.3,0.1

Type RM Length L Ch R = 1,3208,426,426,426
BEGIN DESCRIPTION:
TRIB 7 TO SALT CREEK 4.0
END DESCRIPTION:
XS GIS Cut Line= 3
      2411175.00     13568425.00      2411325.00     13567775.00
      2411175.01     13566975.03
#Sta/Elev= 30
  4341.0  401.42  4365.0  399.89  4450.5  397.30  4474.4  397.46  4525.7  395.16
  4566.8  394.03  4589.0  394.42  4638.6  391.56  4689.9  390.66  4717.3  388.87
  4792.6  386.97  4823.4  385.07  4936.2  384.01  4956.8  385.02  4977.3  383.71
  4997.8  383.88  5016.0  382.51  5016.3  382.01  5020.6  382.51  5034.4  385.15
  5144.6  385.48  5307.4  388.68  5417.6  392.07  5470.2  394.74  5516.8  395.50
  5669.4  402.94  5685.5  405.57  5710.1  404.24  5738.1  406.97  5822.0  411.98
#Mann=3,-1,0
  4341.0    0.04       0  5016.0    0.04       0  5020.6    0.04       0
Bank Sta=5016,5020.6
Exp/Cntr=0.3,0.1

Type RM Length L Ch R = 1,2782,472,472,472
BEGIN DESCRIPTION:
TRIB 7 TO SALT CREEK 3.0
END DESCRIPTION:
XS GIS Cut Line= 3
      2411425.00     13568475.01      2411725.00     13567875.00
      2411775.00     13567275.01
#Sta/Elev= 30
  4432.2  400.73  4507.7  397.54  4552.4  397.23  4574.8  395.70  4633.5  393.87
  4655.8  394.07  4678.2  392.22  4731.3  390.31  4753.6  390.39  4776.0  388.70
  4834.7  386.96  4871.0  387.41  4960.5  383.67  4977.3  381.41  5049.9  380.83
  5080.7  381.90  5113.1  381.24  5160.7  382.17  5191.0  379.85  5191.3  379.35
  5195.6  379.85  5203.4  381.71  5213.4  382.11  5253.5  382.03  5363.9  384.60
  5394.0  386.65  5414.1  385.33  5434.2  386.38  5484.3  386.90  5705.1  393.44
#Mann=3,-1,0
  4432.2    0.04       0  5191.0    0.04       0  5195.6    0.04       0
Bank Sta=5191,5195.6
Exp/Cntr=0.3,0.1

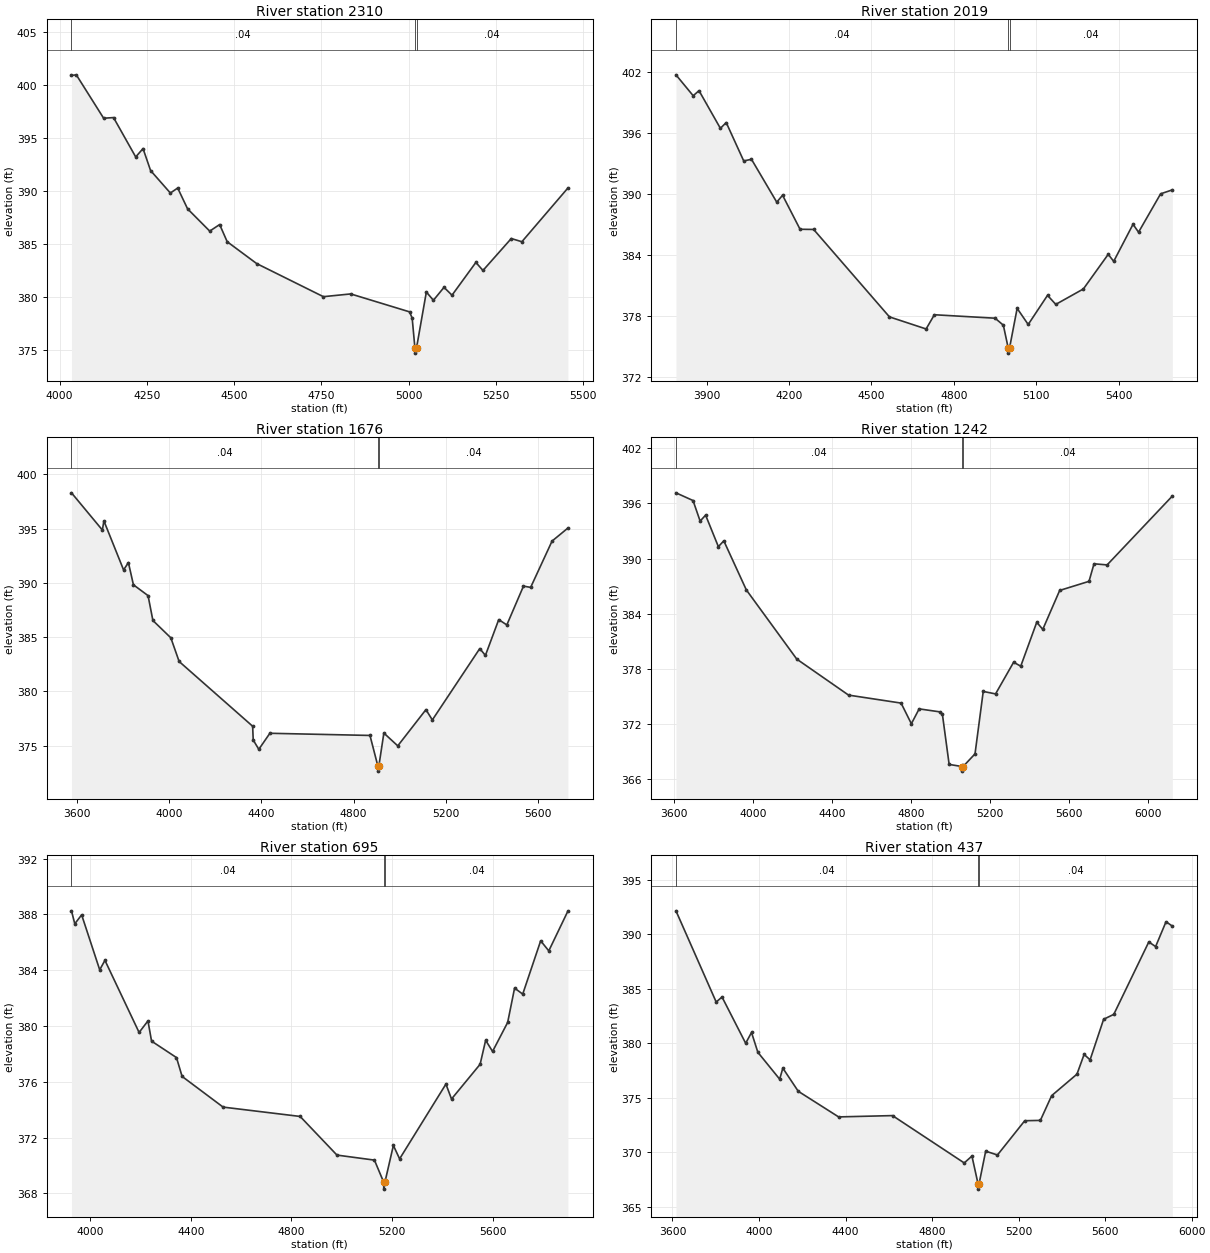
Type RM Length L Ch R = 1,2310,291,291,291
BEGIN DESCRIPTION:
TRIB 7 TO SALT CREEK 2.0
END DESCRIPTION:
XS GIS Cut Line= 3
      2411575.03     13568574.96      2412125.00     13567975.00
      2412024.99     13567374.97
#Sta/Elev= 30
  4034.0  400.86  4047.8  400.92  4126.1  396.83  4154.5  396.89  4218.0  393.18
  4239.0  393.97  4260.6  391.90  4317.3  389.78  4338.3  390.25  4366.6  388.29
  4430.1  386.19  4458.5  386.81  4480.1  385.19  4564.6  383.13  4755.7  380.01
  4834.0  380.27  5002.5  378.58  5010.1  377.99  5017.9  375.19  5018.2  374.69
  5022.6  375.19  5050.7  380.45  5070.9  379.67  5101.3  380.89  5124.2  380.15
  5192.6  383.24  5212.9  382.48  5294.0  385.49  5324.4  385.19  5456.2  390.25
#Mann=3,-1,0
  4034.0    0.04       0  5017.9    0.04       0  5022.6    0.04       0
Bank Sta=5017.9,5022.6
Exp/Cntr=0.3,0.1

Type RM Length L Ch R = 1,2019,343,343,343
BEGIN DESCRIPTION:
Mapping XS 919a18c2
END DESCRIPTION:
XS GIS Cut Line= 3
      2411738.16     13568776.88      2412361.77     13568153.28
      2412444.59     13567232.51
#Sta/Elev= 30
  3788.5  401.75  3851.2  399.69  3872.4  400.19  3950.2  396.48  3971.4  397.05
  4035.1  393.27  4063.4  393.43  4155.3  389.21  4176.5  389.89  4240.1  386.54
  4289.6  386.52  4565.4  377.91  4698.8  376.72  4728.9  378.12  4949.8  377.78
  4979.9  377.09  4997.6  374.84  4998.0  374.34  5002.4  374.84  5030.1  378.75
  5070.3  377.16  5140.6  380.03  5170.7  379.14  5271.1  380.66  5361.5  384.07
  5381.5  383.38  5451.8  387.03  5471.9  386.25  5552.2  390.03  5594.9  390.42
#Mann=3,-1,0
  3788.5    0.04       0  4997.6    0.04       0  5002.4    0.04       0
Bank Sta=4997.6,5002.4
Exp/Cntr=0.3,0.1

Type RM Length L Ch R = 1,1676,434,434,434
BEGIN DESCRIPTION:
Mapping XS f3351794
END DESCRIPTION:
XS GIS Cut Line= 4
      2412074.32     13568932.77      2412663.81     13568406.61
      2412722.27     13567724.57      2412557.03     13567068.46
#Sta/Elev= 30
  3577.8  398.31  3711.6  394.88  3718.3  395.72  3803.6  391.20  3824.5  391.88
  3846.2  389.83  3909.7  388.83  3930.6  386.54  4008.4  384.94  4044.3  382.76
  4362.9  376.79  4365.4  375.52  4389.6  374.66  4437.6  376.14  4871.4  375.94
  4905.2  373.15  4905.6  372.65  4910.1  373.15  4931.6  376.16  4991.8  374.98
  5113.9  378.32  5141.7  377.37  5347.2  383.95  5371.7  383.32  5429.4  386.62
  5464.5  386.13  5536.7  389.71  5567.7  389.59  5660.5  393.86  5729.1  395.06
#Mann=3,-1,0
  3577.8    0.04       0  4905.2    0.04       0  4910.1    0.04       0
Bank Sta=4905.2,4910.1
Exp/Cntr=0.3,0.1

Type RM Length L Ch R = 1,1242,547,547,547
BEGIN DESCRIPTION:
Mapping XS 97c5ca31
END DESCRIPTION:
XS GIS Cut Line= 4
      2412123.07     13569025.30      2412956.11     13568294.56
      2413097.39     13567792.78      2412795.34     13566964.56
#Sta/Elev= 30
  3610.0  397.16  3696.4  396.32  3732.3  394.08  3760.0  394.73  3824.5  391.30
  3852.1  391.93  3965.9  386.59  4221.2  379.05  4483.1  375.13  4748.8  374.26
  4800.8  372.01  4840.2  373.63  4946.2  373.30  4957.8  373.04  4991.9  367.58
  5057.5  367.35  5057.8  366.85  5062.4  367.35  5122.8  368.73  5164.4  375.53
  5226.7  375.26  5318.1  378.71  5354.1  378.28  5435.0  383.06  5465.6  382.29
  5551.1  386.53  5699.4  387.52  5724.7  389.43  5791.1  389.31  6121.0  396.81
#Mann=3,-1,0
  3610.0    0.04       0  5057.5    0.04       0  5062.4    0.04       0
Bank Sta=5057.5,5062.4
Exp/Cntr=0.3,0.1

Type RM Length L Ch R = 1,695,258,258,258
BEGIN DESCRIPTION:
4887
END DESCRIPTION:
XS GIS Cut Line= 6
      2412373.80     13568871.54      2412985.36     13568373.63
      2413163.95     13568292.45      2413310.07     13568108.45
      2413337.13     13567946.10      2413056.63     13567428.24
#Sta/Elev= 30
  3925.9  388.25  3939.0  387.32  3966.3  387.96  4038.1  384.02  4058.9  384.70
  4194.7  379.53  4229.9  380.36  4244.2  378.91  4343.3  377.73  4365.6  376.38
  4528.6  374.18  4834.9  373.51  4981.2  370.74  5130.2  370.38  5166.9  368.80
  5167.3  368.30  5171.9  368.80  5205.5  371.43  5230.3  370.47  5414.4  375.83
  5436.6  374.76  5550.3  377.25  5572.3  378.97  5599.8  378.17  5659.8  380.25
  5687.3  382.71  5719.7  382.28  5791.0  386.10  5823.3  385.38  5899.2  388.23
#Mann=3,-1,0
  3925.9    0.04       0  5166.9    0.04       0  5171.9    0.04       0
Bank Sta=5166.9,5171.9
Exp/Cntr=0.3,0.1

Type RM Length L Ch R = 1,437,84,84,84
BEGIN DESCRIPTION:
TRIB 7 TO SALT CREEK 1.0
END DESCRIPTION:
XS GIS Cut Line= 3
      2412313.02     13568981.49      2413435.19     13568174.54
      2413171.86     13567300.85
#Sta/Elev= 30
  3616.1  392.15  3802.1  383.79  3829.1  384.25  3938.4  380.01  3965.4  381.00
  3994.8  379.18  4095.5  376.72  4110.2  377.73  4181.4  375.61  4368.0  373.26
  4617.2  373.38  4948.7  369.04  4984.3  369.67  5012.4  367.14  5012.8  366.64
  5017.4  367.14  5047.9  370.12  5102.3  369.77  5228.5  372.91  5300.7  372.94
  5352.9  375.21  5469.9  377.18  5502.9  378.99  5530.5  378.49  5593.1  382.21
  5640.1  382.66  5802.0  389.30  5833.4  388.87  5881.5  391.15  5910.8  390.75
#Mann=3,-1,0
  3616.1    0.04       0  5012.4    0.04       0  5017.4    0.04       0
Bank Sta=5012.4,5017.4
Exp/Cntr=0.3,0.1

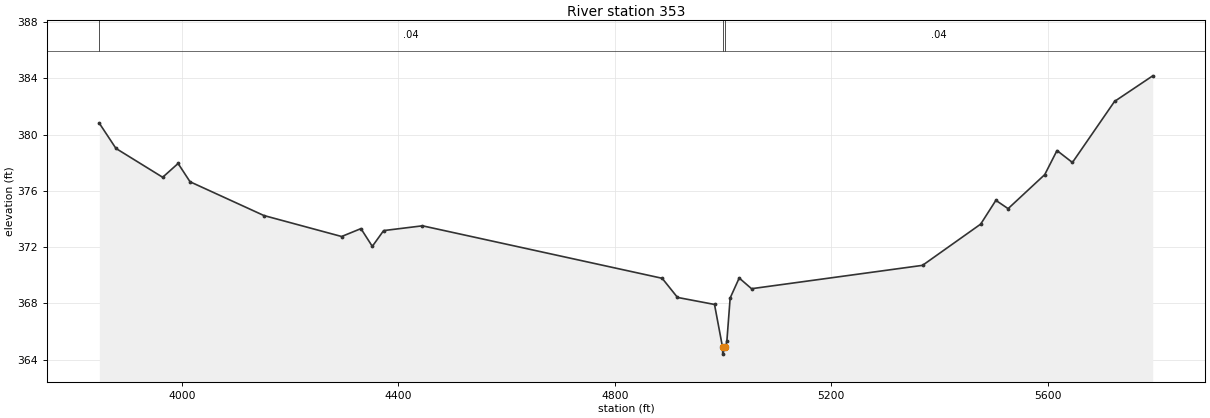
Type RM Length L Ch R = 1,353,0,0,0
BEGIN DESCRIPTION:
4888
END DESCRIPTION:
XS GIS Cut Line= 5
      2412595.72     13568828.22      2413153.13     13568438.57
      2413423.72     13568384.45      2413596.90     13568016.45
      2413342.54     13567491.49
#Sta/Elev= 30
  3847.7  380.81  3878.4  379.02  3964.7  376.97  3993.2  377.95  4015.3  376.65
  4151.8  374.25  4295.3  372.76  4331.0  373.32  4352.0  372.06  4372.9  373.18
  4444.7  373.52  4887.5  369.79  4915.8  368.43  4984.2  367.93  4999.0  364.90
  4999.4  364.40  5004.0  364.90  5007.0  365.31  5013.1  368.39  5029.8  369.81
  5052.6  369.05  5368.5  370.71  5475.9  373.64  5504.0  375.33  5526.6  374.74
  5594.3  377.16  5616.9  378.87  5645.4  378.02  5723.2  382.36  5793.8  384.18
#Mann=3,-1,0
  3847.7    0.04       0  4999.0    0.04       0  5004.0    0.04       0
Bank Sta=4999,5004
Exp/Cntr=0.3,0.1

Chan Stop Cuts=-1