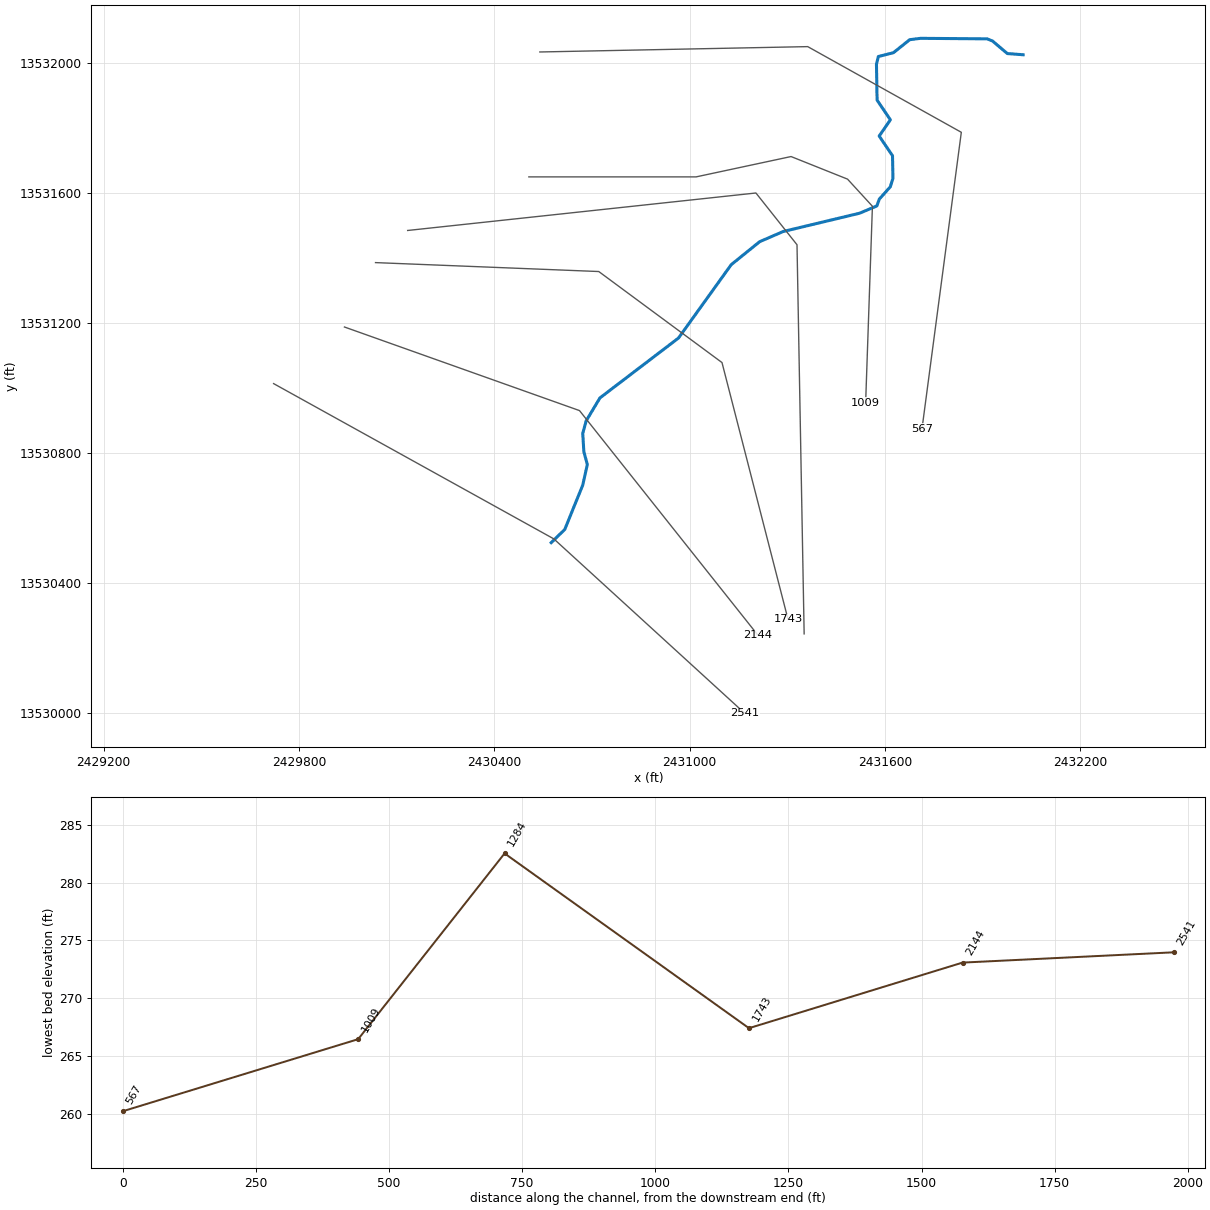
--- TRIB 7 TO SMITH CREEK.prj (project) ---

Proj Title=TRIB 7 TO SMITH CREEK Base Level Engineering
Current Plan=p01
Default Exp/Contr=0.3,0.1
English Units
Geom File=g01
Flow File=f01
Plan File=p01
BEGIN DESCRIPTION:
TRIB 7 TO SMITH CREEK
END DESCRIPTION:

--- TRIB 7 TO SMITH CREEK.p01 (plan) ---

Plan Title=Multiple Run
Short Identifier=Multiple
Geom File=g01
Flow File=f01
Subcritical Flow
K Sum by GR= 0
Std Step Tol= 0.01
Critical Tol= 0.01
Num of Std Step Trials= 20
Max Error Tol= 0.3
Flow Tol Ratio= 0.001
Split Flow NTrial= 30
Split Flow Tol= 0.02
Split Flow Ratio= 0.02
Log Output Level= 0
Friction Slope Method= 1
Unsteady Friction Slope Method= 2
Unsteady Bridges Friction Slope Method= 1
Parabolic Critical Depth
Global Vel Dist=  1 , 1 , 1
Global Log Level= 0
CheckData=True
Encroach Param= -1, 0, 0, 0
BEGIN DESCRIPTION:
Multiple Run
END DESCRIPTION:

--- TRIB 7 TO SMITH CREEK.f01 (steady flow) ---

Flow Title=Multiple
Number of Profiles=7
Profile Names=10-year,25-year,50-year,1pct_min,100-year,1pct_plu,500-year
River Rch & RM= TRIB 7 TO SMITH ,Reach-1,2541
     443     704     936     604    1205    2405    1975
River Rch & RM= TRIB 7 TO SMITH ,Reach-1,2144
     520     835    1118     726    1448    2890    2404
Boundary for River Rch & Prof#=TRIB 7 TO SMITH ,Reach-1,1
Up Type=0
Dn Type=3
Dn Slope=0.005
Boundary for River Rch & Prof#=TRIB 7 TO SMITH ,Reach-1,2
Up Type=0
Dn Type=3
Dn Slope=0.005
Boundary for River Rch & Prof#=TRIB 7 TO SMITH ,Reach-1,3
Up Type=0
Dn Type=3
Dn Slope=0.005
Boundary for River Rch & Prof#=TRIB 7 TO SMITH ,Reach-1,4
Up Type=0
Dn Type=3
Dn Slope=0.005
Boundary for River Rch & Prof#=TRIB 7 TO SMITH ,Reach-1,5
Up Type=0
Dn Type=3
Dn Slope=0.005
Boundary for River Rch & Prof#=TRIB 7 TO SMITH ,Reach-1,6
Up Type=0
Dn Type=3
Dn Slope=0.005
Boundary for River Rch & Prof#=TRIB 7 TO SMITH ,Reach-1,7
Up Type=0
Dn Type=3
Dn Slope=0.005

--- TRIB 7 TO SMITH CREEK.g01 (geometry) ---

Geom Title=Existing Conditions

River Reach=TRIB 7 TO SMITH ,Reach-1
Reach XY= 30
      2430575.00     13530525.00      2430616.70     13530565.54
      2430671.90     13530701.78      2430686.02     13530765.32
      2430675.43     13530804.15      2430671.90     13530860.62
      2430682.49     13530899.45      2430724.85     13530970.05
      2430966.19     13531154.08      2431128.08     13531379.52
      2431215.62     13531450.28      2431287.57     13531481.45
      2431522.60     13531537.81      2431575.60     13531560.19
      2431583.15     13531581.06      2431616.91     13531618.97
      2431625.09     13531645.10      2431623.74     13531714.52
      2431582.80     13531775.10      2431617.20     13531824.90
      2431576.36     13531885.45      2431574.43     13531995.43
      2431580.16     13532019.59      2431626.77     13532031.31
      2431676.52     13532071.26      2431709.81     13532075.44
      2431914.54     13532073.88      2431931.16     13532067.11
      2431976.51     13532028.65      2432025.00     13532025.00

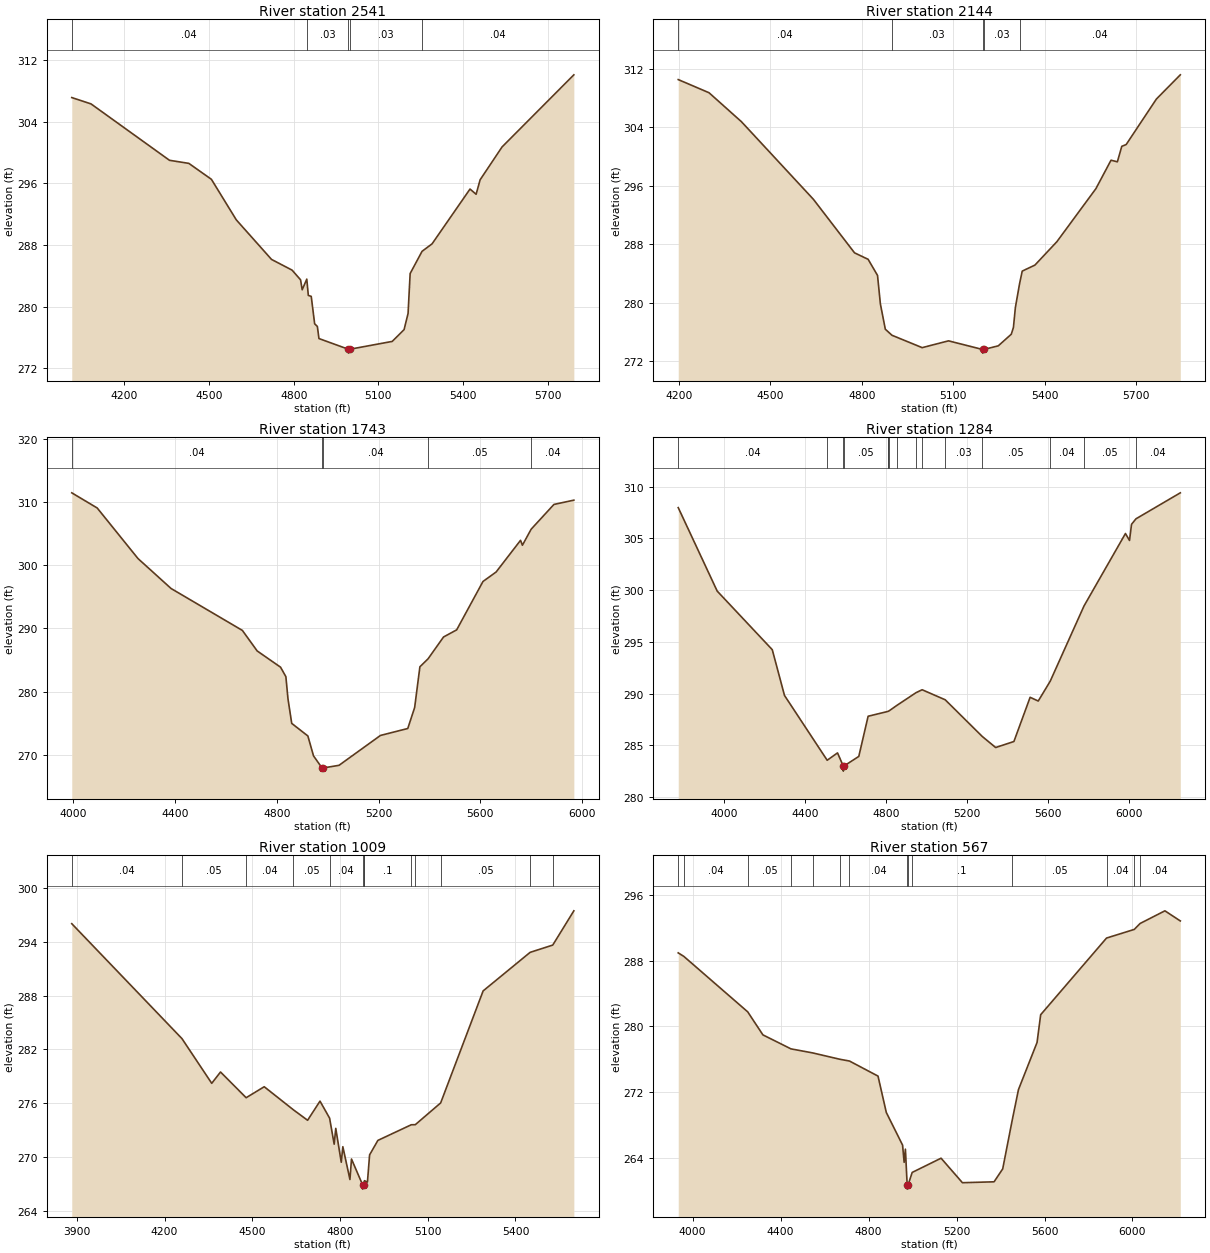
Type RM Length L Ch R = 1,2541,397,397,397
BEGIN DESCRIPTION:
LGII4655
END DESCRIPTION:
XS GIS Cut Line= 3
      2429722.06     13531013.98      2430583.15     13530536.57
      2431169.92     13530000.14
#Sta/Elev= 30
  4013.3  307.13  4081.5  306.31  4359.7  298.99  4428.3  298.59  4508.3  296.52
  4596.5  291.26  4721.3  286.13  4794.2  284.74  4824.3  283.48  4830.0  282.19
  4846.3  283.57  4851.8  281.46  4862.1  281.33  4874.2  277.78  4883.8  277.43
  4889.5  275.86  4994.1  274.47  4994.3  273.97  4998.1  274.47  5149.2  275.49
  5191.2  277.02  5205.3  279.12  5212.7  284.30  5254.9  287.18  5290.4  288.15
  5424.9  295.26  5446.5  294.58  5460.7  296.46  5538.4  300.72  5792.9  310.08
#Mann=5,-1,0
  4013.3    0.04       0  4846.3    0.03       0  4994.1    0.03       0
  4998.1    0.03       0  5254.9    0.04       0
Bank Sta=4994.1,4998.1
Exp/Cntr=0.3,0.1

Type RM Length L Ch R = 1,2144,401,401,401
BEGIN DESCRIPTION:
Mapping XS 601c4346
END DESCRIPTION:
XS GIS Cut Line= 3
      2429939.72     13531187.97      2430661.96     13530931.01
      2431210.28     13530240.41
#Sta/Elev= 30
  4197.4  310.50  4298.5  308.70  4405.1  304.73  4641.2  294.12  4776.2  286.80
  4820.9  285.91  4851.7  283.71  4861.1  279.81  4877.3  276.35  4899.3  275.52
  4998.3  273.83  5084.8  274.76  5196.6  273.58  5196.8  273.08  5200.6  273.58
  5248.3  274.08  5290.9  275.67  5297.9  276.59  5304.3  279.32  5318.0  282.56
  5326.8  284.30  5368.4  285.12  5440.5  288.32  5568.7  295.58  5618.3  299.47
  5639.2  299.25  5653.6  301.37  5668.0  301.61  5767.3  307.84  5845.8  311.15
#Mann=5,-1,0
  4197.4    0.04       0  4899.3    0.03       0  5196.6    0.03       0
  5200.6    0.03       0  5318.0    0.04       0
Bank Sta=5196.6,5200.6
Exp/Cntr=0.3,0.1

Type RM Length L Ch R = 1,1743,459,459,459
BEGIN DESCRIPTION:
LGII4654
END DESCRIPTION:
XS GIS Cut Line= 4
      2430035.22     13531385.96      2430721.16     13531358.52
      2431099.81     13531078.65      2431302.64     13530289.23
#Sta/Elev= 30
  3994.9  311.48  4094.8  309.08  4254.9  301.08  4385.0  296.33  4665.2  289.69
  4723.3  286.44  4815.1  283.87  4836.0  282.37  4844.4  278.83  4859.0  274.97
  4922.4  272.98  4944.6  269.83  4978.1  267.91  4978.3  267.41  4982.1  267.91
  5044.8  268.33  5207.6  273.06  5314.9  274.16  5341.9  277.48  5362.5  283.93
  5394.5  285.19  5455.4  288.65  5507.0  289.78  5610.3  297.44  5661.9  298.94
  5757.9  303.96  5765.2  303.18  5799.6  305.72  5889.1  309.64  5967.3  310.32
#Mann=5,-1,0
  3994.9    0.04       0  4978.1    0.04       0  4982.1    0.04       0
  5394.5    0.05       0  5799.6    0.04       0
Bank Sta=4978.1,4982.1
Exp/Cntr=0.3,0.1

Type RM Length L Ch R = 1,1284,275,275,275
BEGIN DESCRIPTION:
LGII4653
END DESCRIPTION:
XS GIS Cut Line= 4
      2430133.99     13531484.74      2431204.07     13531599.98
      2431330.29     13531440.84      2431352.24     13530244.53
#Sta/Elev= 30
  3775.0  307.97  3967.1  299.91  4238.7  294.25  4299.0  289.83  4509.5  283.57
  4560.5  284.28  4588.7  283.02  4589.0  282.52  4592.7  283.02  4665.4  283.94
  4711.4  287.82  4807.8  288.28  4810.7  288.30  4815.5  288.35  4854.8  288.89
  4947.8  290.10  4977.8  290.38  5091.6  289.41  5274.1  285.87  5340.3  284.80
  5430.3  285.38  5510.3  289.65  5550.3  289.29  5609.2  291.20  5775.7  298.46
  5980.4  305.47  6000.4  304.80  6010.4  306.36  6032.3  306.89  6250.9  309.40
#Mann=15,-1,0
  3775.0    0.04       0  4509.5    0.05       0  4588.7    0.05       0
  4592.7    0.05       0  4807.8    0.04       0  4810.7    0.05       0
  4815.5    0.04       0  4854.8    0.05       0  4947.8    0.04       0
  4977.8    0.05       0  5091.6    0.03       0  5274.1    0.05       0
  5609.2    0.04       0  5775.7    0.05       0  6032.3    0.04       0
Bank Sta=4588.7,4592.7
Exp/Cntr=0.3,0.1

Type RM Length L Ch R = 1,1009,442,442,442
BEGIN DESCRIPTION:
4889
END DESCRIPTION:
XS GIS Cut Line= 6
      2430506.40     13531649.51      2431020.33     13531649.51
      2431311.99     13531712.01      2431485.60     13531642.56
      2431561.99     13531559.23      2431541.16     13530955.03
#Sta/Elev= 30
  3882.9  295.99  4259.8  283.20  4361.5  278.23  4391.5  279.49  4479.2  276.63
  4541.0  277.85  4640.9  275.28  4689.3  274.12  4731.7  276.25  4764.5  274.36
  4780.2  271.46  4785.6  273.22  4804.4  269.45  4809.8  271.18  4834.1  267.53
  4839.4  269.81  4877.1  266.96  4877.3  266.46  4881.1  266.96  4883.7  267.40
  4893.9  267.24  4901.3  270.27  4929.6  271.88  5043.8  273.62  5057.6  273.63
  5144.3  276.05  5289.5  288.51  5450.2  292.80  5527.6  293.61  5599.7  297.42
#Mann=13,-1,0
  3882.9    0.04       0  4259.8    0.05       0  4479.2    0.04       0
  4640.9    0.05       0  4764.5    0.04       0  4877.1    0.05       0
  4881.1    0.04       0  4883.7     0.1       0  5043.8    0.05       0
  5057.6    0.04       0  5144.3    0.05       0  5450.2    0.04       0
  5527.6    0.05       0
Bank Sta=4877.1,4881.1
Exp/Cntr=0.3,0.1

Type RM Length L Ch R = 1,567,0,0,0
BEGIN DESCRIPTION:
LGII4652
END DESCRIPTION:
XS GIS Cut Line= 4
      2430540.10     13532033.51      2431363.22     13532049.97
      2431835.16     13531786.56      2431714.43     13530875.59
#Sta/Elev= 30
  3934.7  288.95  3960.2  288.52  4250.6  281.78  4319.7  278.98  4447.2  277.28
  4545.5  276.79  4670.6  276.01  4713.3  275.80  4843.0  273.97  4880.7  269.55
  4954.7  265.58  4961.8  263.49  4967.5  265.09  4975.6  260.73  4975.9  260.23
  4979.6  260.73  4998.4  262.26  5129.7  263.99  5226.8  261.01  5370.7  261.12
  5409.9  262.69  5453.3  268.63  5481.6  272.33  5566.1  278.06  5582.5  281.43
  5882.0  290.75  6008.1  291.80  6034.5  292.52  6147.4  294.06  6217.4  292.83
#Mann=14,-1,0
  3934.7    0.05       0  3960.2    0.04       0  4250.6    0.05       0
  4447.2    0.03       0  4545.5    0.04       0  4670.6    0.03       0
  4713.3    0.04       0  4975.6    0.05       0  4979.6    0.04       0
  4998.4     0.1       0  5453.3    0.05       0  5882.0    0.04       0
  6008.1    0.05       0  6034.5    0.04       0
Bank Sta=4975.6,4979.6
Exp/Cntr=0.3,0.1

Chan Stop Cuts=-1