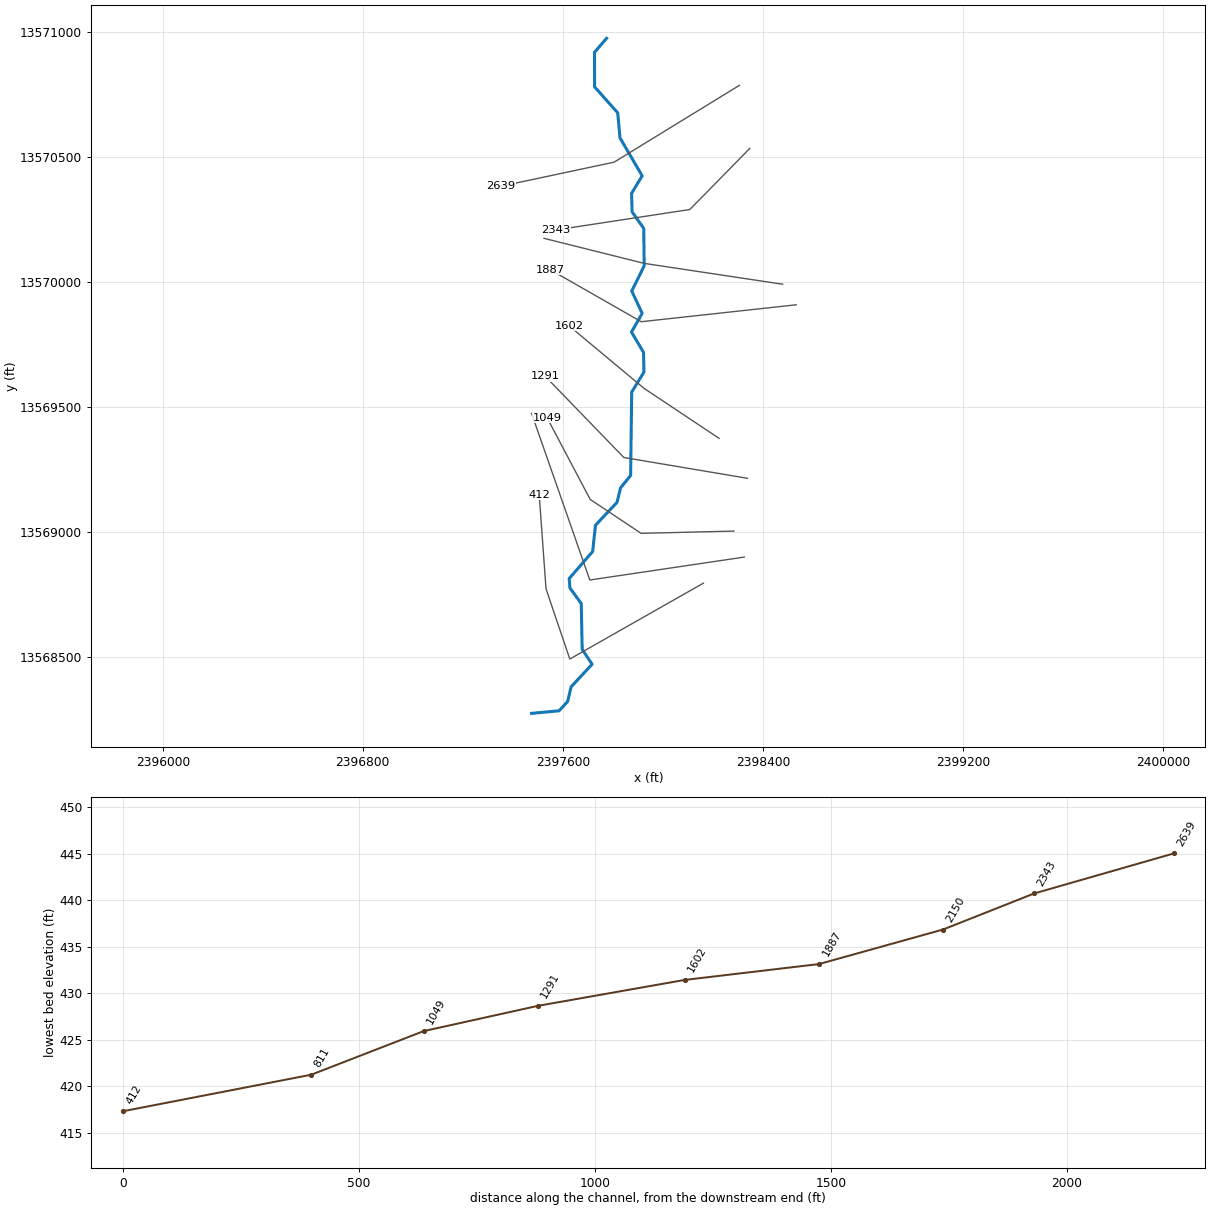
--- TRIB 7 TO THOMAS CREEK.prj (project) ---

Proj Title=TRIB 7 TO THOMAS CREEK Base Level Engineering
Current Plan=p01
Default Exp/Contr=0.3,0.1
English Units
Geom File=g01
Flow File=f01
Plan File=p01
BEGIN DESCRIPTION:
TRIB 7 TO THOMAS CREEK
END DESCRIPTION:

--- TRIB 7 TO THOMAS CREEK.p01 (plan) ---

Plan Title=Multiple Run
Short Identifier=Multiple
Geom File=g01
Flow File=f01
Subcritical Flow
K Sum by GR= 0
Std Step Tol= 0.01
Critical Tol= 0.01
Num of Std Step Trials= 20
Max Error Tol= 0.3
Flow Tol Ratio= 0.001
Split Flow NTrial= 30
Split Flow Tol= 0.02
Split Flow Ratio= 0.02
Log Output Level= 0
Friction Slope Method= 1
Unsteady Friction Slope Method= 2
Unsteady Bridges Friction Slope Method= 1
Parabolic Critical Depth
Global Vel Dist=  1 , 1 , 1
Global Log Level= 0
CheckData=True
Encroach Param= -1, 0, 0, 0
BEGIN DESCRIPTION:
Multiple Run
END DESCRIPTION:

--- TRIB 7 TO THOMAS CREEK.f01 (steady flow) ---

Flow Title=Multiple
Number of Profiles=7
Profile Names=10-year,25-year,50-year,1pct_min,100-year,1pct_plu,500-year
River Rch & RM= TRIB 7 TO THOMAS,Reach-1,2639
     425     681     911     592    1182    2358    1967
Boundary for River Rch & Prof#=TRIB 7 TO THOMAS,Reach-1,1
Up Type=0
Dn Type=3
Dn Slope=0.005
Boundary for River Rch & Prof#=TRIB 7 TO THOMAS,Reach-1,2
Up Type=0
Dn Type=3
Dn Slope=0.005
Boundary for River Rch & Prof#=TRIB 7 TO THOMAS,Reach-1,3
Up Type=0
Dn Type=3
Dn Slope=0.005
Boundary for River Rch & Prof#=TRIB 7 TO THOMAS,Reach-1,4
Up Type=0
Dn Type=3
Dn Slope=0.005
Boundary for River Rch & Prof#=TRIB 7 TO THOMAS,Reach-1,5
Up Type=0
Dn Type=3
Dn Slope=0.005
Boundary for River Rch & Prof#=TRIB 7 TO THOMAS,Reach-1,6
Up Type=0
Dn Type=3
Dn Slope=0.005
Boundary for River Rch & Prof#=TRIB 7 TO THOMAS,Reach-1,7
Up Type=0
Dn Type=3
Dn Slope=0.005

--- TRIB 7 TO THOMAS CREEK.g01 (geometry) ---

Geom Title=Existing Conditions

River Reach=TRIB 7 TO THOMAS,Reach-1
Reach XY= 30
      2397775.00     13570975.00      2397726.88     13570919.21
      2397727.05     13570780.86      2397819.46     13570677.42
      2397828.83     13570576.59      2397917.47     13570425.01
      2397875.02     13570354.95      2397877.17     13570280.98
      2397923.78     13570214.50      2397925.45     13570064.81
      2397875.82     13569964.29      2397917.38     13569875.00
      2397874.69     13569800.04      2397922.81     13569719.03
      2397924.62     13569640.27      2397875.52     13569559.78
      2397871.25     13569226.55      2397831.14     13569177.17
      2397816.84     13569118.95      2397730.54     13569027.42
      2397719.46     13568922.58      2397625.60     13568814.38
      2397628.34     13568776.75      2397673.76     13568714.50
      2397677.47     13568530.85      2397717.19     13568471.59
      2397633.20     13568381.03      2397619.27     13568322.43
      2397585.18     13568285.29      2397475.00     13568275.00

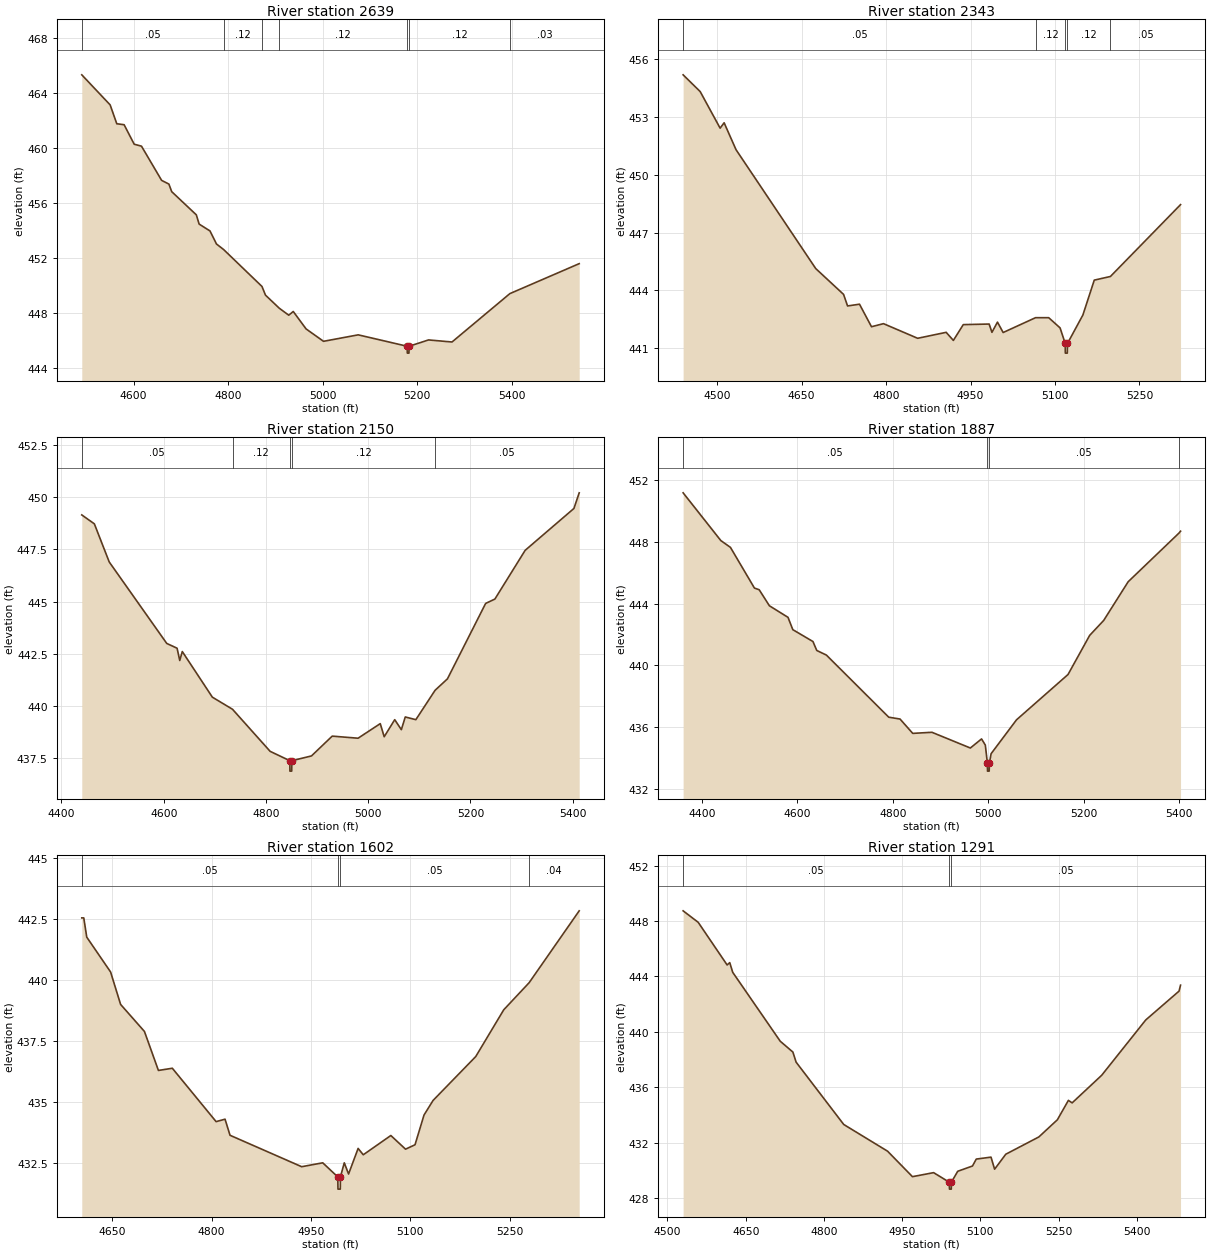
Type RM Length L Ch R = 1,2639,296,296,296
BEGIN DESCRIPTION:
Mapping XS 47150b27
END DESCRIPTION:
XS GIS Cut Line= 3
      2398306.14     13570786.84      2397805.14     13570479.69
      2397351.24     13570383.19
#Sta/Elev= 30
  4490.5  465.30  4550.5  463.11  4564.5  461.74  4580.0  461.67  4601.3  460.25
  4616.7  460.11  4659.3  457.62  4674.7  457.35  4680.6  456.80  4732.7  455.11
  4738.6  454.44  4761.6  453.94  4775.3  452.99  4790.3  452.59  4871.5  449.90
  4878.9  449.27  4908.0  448.32  4928.1  447.81  4937.6  448.08  4964.8  446.81
  5001.6  445.91  5075.0  446.38  5178.5  445.55  5178.8  445.05  5182.3  445.05
  5182.5  445.55  5223.7  446.01  5273.3  445.86  5395.6  449.38  5542.2  451.56
#Mann=7,-1,0
  4490.5    0.05       0  4790.3    0.12       0  4871.5    0.05       0
  4908.0    0.12       0  5178.5    0.05       0  5182.5    0.12       0
  5395.6    0.03       0
Bank Sta=5178.5,5182.5
Exp/Cntr=0.3,0.1

Type RM Length L Ch R = 1,2343,193,193,193
BEGIN DESCRIPTION:
4892
END DESCRIPTION:
XS GIS Cut Line= 3
      2398348.04     13570534.89      2398108.00     13570290.32
      2397573.57     13570208.80
#Sta/Elev= 30
  4439.6  455.19  4469.9  454.32  4505.3  452.42  4512.4  452.70  4533.6  451.30
  4675.1  445.13  4724.5  443.79  4731.6  443.19  4752.8  443.28  4774.1  442.11
  4795.4  442.27  4856.1  441.51  4906.7  441.82  4919.5  441.40  4937.1  442.22
  4983.0  442.25  4988.0  441.82  4997.8  442.35  5007.9  441.81  5065.4  442.58
  5088.8  442.58  5109.0  442.05  5118.1  441.24  5118.3  440.74  5121.8  440.74
  5122.1  441.24  5149.5  442.72  5169.7  444.53  5198.4  444.72  5322.9  448.45
#Mann=5,-1,0
  4439.6    0.05       0  5065.4    0.12       0  5118.1    0.05       0
  5122.1    0.12       0  5198.4    0.05       0
Bank Sta=5118.1,5122.1
Exp/Cntr=0.3,0.1

Type RM Length L Ch R = 1,2150,263,263,263
BEGIN DESCRIPTION:
TRIB 7 TO THOMAS CREEK 3.0
END DESCRIPTION:
XS GIS Cut Line= 3
      2398479.33     13569991.43      2397925.00     13570075.00
      2397525.00     13570175.00
#Sta/Elev= 30
  4439.8  449.16  4464.4  448.73  4493.5  446.90  4606.0  442.99  4626.2  442.76
  4631.4  442.17  4636.4  442.60  4695.2  440.41  4734.6  439.83  4808.2  437.81
  4846.7  437.36  4846.9  436.86  4850.4  436.86  4850.7  437.36  4889.1  437.59
  4929.6  438.54  4980.2  438.44  5023.6  439.14  5031.3  438.51  5051.9  439.33
  5064.8  438.85  5072.5  439.46  5093.2  439.33  5130.8  440.74  5155.0  441.29
  5229.7  444.91  5247.8  445.12  5307.0  447.46  5402.4  449.47  5412.7  450.22
#Mann=5,-1,0
  4439.8    0.05       0  4734.6    0.12       0  4846.7    0.05       0
  4850.7    0.12       0  5130.8    0.05       0
Bank Sta=4846.7,4850.7
Exp/Cntr=0.3,0.1

Type RM Length L Ch R = 1,1887,285,285,285
BEGIN DESCRIPTION:
Mapping XS 0b69b7f6
END DESCRIPTION:
XS GIS Cut Line= 3
      2398533.59     13569909.24      2397913.78     13569841.53
      2397549.64     13570049.61
#Sta/Elev= 30
  4360.3  451.20  4439.4  448.10  4459.5  447.66  4509.8  445.02  4519.8  444.91
  4541.2  443.87  4580.2  443.12  4590.3  442.32  4632.5  441.55  4640.5  440.97
  4660.7  440.67  4791.4  436.64  4815.1  436.52  4841.7  435.59  4882.0  435.66
  4962.5  434.64  4986.0  435.23  4993.9  434.83  4998.3  433.64  4998.5  433.14
  5002.0  433.14  5002.3  433.64  5006.0  434.27  5059.3  436.47  5167.3  439.41
  5212.7  441.95  5242.1  442.92  5293.4  445.43  5400.0  448.59  5403.2  448.71
#Mann=4,-1,0
  4360.3    0.05       0  4998.3    0.05       0  5002.3    0.05       0
  5400.0    0.04       0
Bank Sta=4998.3,5002.3
Exp/Cntr=0.3,0.1

Type RM Length L Ch R = 1,1602,311,311,311
BEGIN DESCRIPTION:
TRIB 7 TO THOMAS CREEK 2.0
END DESCRIPTION:
XS GIS Cut Line= 3
      2398224.98     13569375.01      2397925.00     13569575.00
      2397625.04     13569824.97
#Sta/Elev= 30
  4604.0  442.56  4607.0  442.56  4611.5  441.77  4647.5  440.34  4662.6  439.01
  4698.6  437.90  4719.7  436.30  4740.7  436.39  4806.8  434.20  4820.3  434.30
  4827.8  433.64  4936.0  432.35  4967.8  432.51  4990.5  431.93  4990.8  431.43
  4994.3  431.43  4994.5  431.93  5000.3  432.51  5006.8  432.05  5021.2  433.10
  5029.0  432.84  5070.6  433.63  5092.8  433.07  5107.1  433.25  5120.7  434.47
  5134.4  435.07  5198.8  436.87  5241.1  438.79  5279.4  439.90  5355.0  442.85
#Mann=4,-1,0
  4604.0    0.05       0  4990.5    0.05       0  4994.5    0.05       0
  5279.4    0.04       0
Bank Sta=4990.5,4994.5
Exp/Cntr=0.3,0.1

Type RM Length L Ch R = 1,1291,242,242,242
BEGIN DESCRIPTION:
Mapping XS 78f55931
END DESCRIPTION:
XS GIS Cut Line= 3
      2398338.73     13569215.23      2397843.98     13569298.56
      2397529.41     13569623.53
#Sta/Elev= 30
  4530.0  448.74  4558.9  447.91  4614.4  444.83  4619.4  445.00  4625.1  444.30
  4716.3  439.32  4740.5  438.54  4746.7  437.81  4838.0  433.31  4922.1  431.38
  4969.8  429.54  5010.4  429.83  5040.5  429.14  5040.8  428.64  5044.3  428.64
  5044.5  429.14  5056.7  429.93  5085.0  430.31  5092.2  430.81  5120.5  430.95
  5127.4  430.08  5148.8  431.16  5212.3  432.41  5247.8  433.65  5268.9  435.05
  5276.1  434.87  5332.7  436.86  5417.3  440.86  5481.1  442.94  5484.0  443.37
#Mann=3,-1,0
  4530.0    0.05       0  5040.5    0.05       0  5044.5    0.05       0
Bank Sta=5040.5,5044.5
Exp/Cntr=0.3,0.1

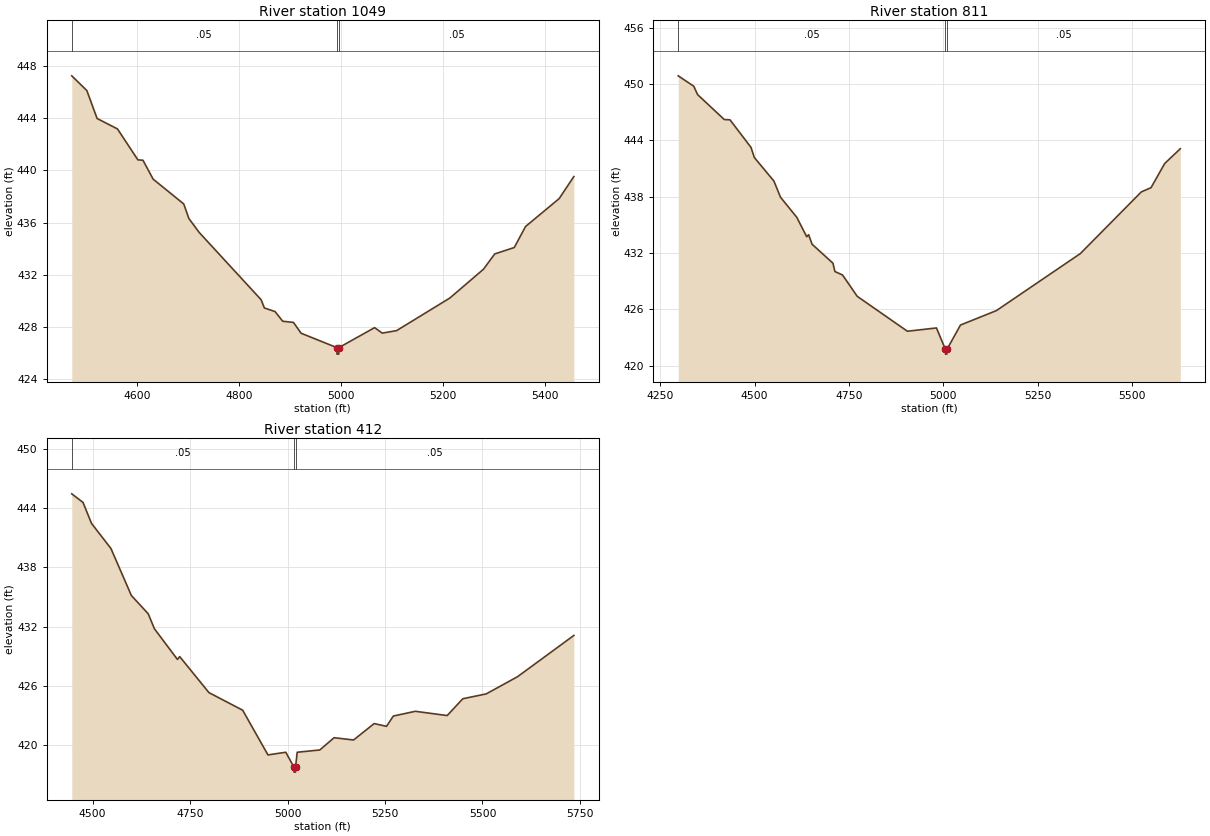
Type RM Length L Ch R = 1,1049,238,238,238
BEGIN DESCRIPTION:
4891
END DESCRIPTION:
XS GIS Cut Line= 4
      2398284.64     13569004.14      2397913.26     13568995.08
      2397709.46     13569130.95      2397537.38     13569457.00
#Sta/Elev= 30
  4471.3  447.25  4500.9  446.12  4521.0  443.98  4561.0  443.18  4601.0  440.81
  4611.0  440.78  4631.0  439.33  4691.0  437.43  4701.0  436.32  4721.0  435.26
  4842.8  430.09  4849.2  429.46  4870.2  429.18  4885.2  428.44  4906.3  428.35
  4921.3  427.52  4991.4  426.42  4991.7  425.92  4995.2  425.92  4995.4  426.42
  5065.5  427.95  5080.5  427.53  5108.6  427.72  5213.1  430.22  5278.9  432.42
  5301.2  433.60  5339.5  434.09  5361.6  435.70  5427.6  437.84  5456.4  439.53
#Mann=3,-1,0
  4471.3    0.05       0  4991.4    0.05       0  4995.4    0.05       0
Bank Sta=4991.4,4995.4
Exp/Cntr=0.3,0.1

Type RM Length L Ch R = 1,811,399,399,399
BEGIN DESCRIPTION:
TRIB 7 TO THOMAS CREEK 1.0
END DESCRIPTION:
XS GIS Cut Line= 3
      2398325.76     13568900.12      2397707.98     13568808.48
      2397475.00     13569474.99
#Sta/Elev= 30
  4297.5  450.89  4338.7  449.78  4348.8  448.89  4419.6  446.23  4434.7  446.20
  4490.4  443.26  4499.1  442.19  4551.0  439.68  4568.6  437.95  4611.7  435.81
  4638.0  433.74  4643.1  433.96  4652.1  432.95  4707.5  430.92  4712.8  430.03
  4733.0  429.66  4771.9  427.39  4904.8  423.67  4981.9  424.02  5005.6  421.73
  5005.9  421.23  5009.4  421.23  5009.6  421.73  5045.5  424.33  5140.8  425.87
  5363.3  431.95  5524.8  438.52  5550.5  438.97  5586.8  441.55  5628.1  443.12
#Mann=3,-1,0
  4297.5    0.05       0  5005.6    0.05       0  5009.6    0.05       0
Bank Sta=5005.6,5009.6
Exp/Cntr=0.3,0.1

Type RM Length L Ch R = 1,412,0,0,0
BEGIN DESCRIPTION:
4890
END DESCRIPTION:
XS GIS Cut Line= 4
      2398162.37     13568795.82      2397627.95     13568492.38
      2397532.84     13568773.17      2397505.67     13569149.07
#Sta/Elev= 30
  4446.5  445.44  4475.4  444.57  4497.0  442.46  4547.0  439.91  4599.4  435.16
  4642.6  433.31  4658.5  431.80  4717.6  428.69  4723.4  428.98  4798.4  425.34
  4884.9  423.56  4949.8  419.04  4995.5  419.31  5016.5  417.80  5016.7  417.30
  5020.2  417.30  5020.5  417.80  5024.8  419.31  5082.7  419.54  5119.4  420.78
  5169.4  420.55  5222.2  422.21  5253.9  421.93  5271.3  422.97  5327.8  423.45
  5409.5  423.02  5449.6  424.72  5509.7  425.21  5590.0  426.95  5734.4  431.12
#Mann=3,-1,0
  4446.5    0.05       0  5016.5    0.05       0  5020.5    0.05       0
Bank Sta=5016.5,5020.5
Exp/Cntr=0.3,0.1

Chan Stop Cuts=-1