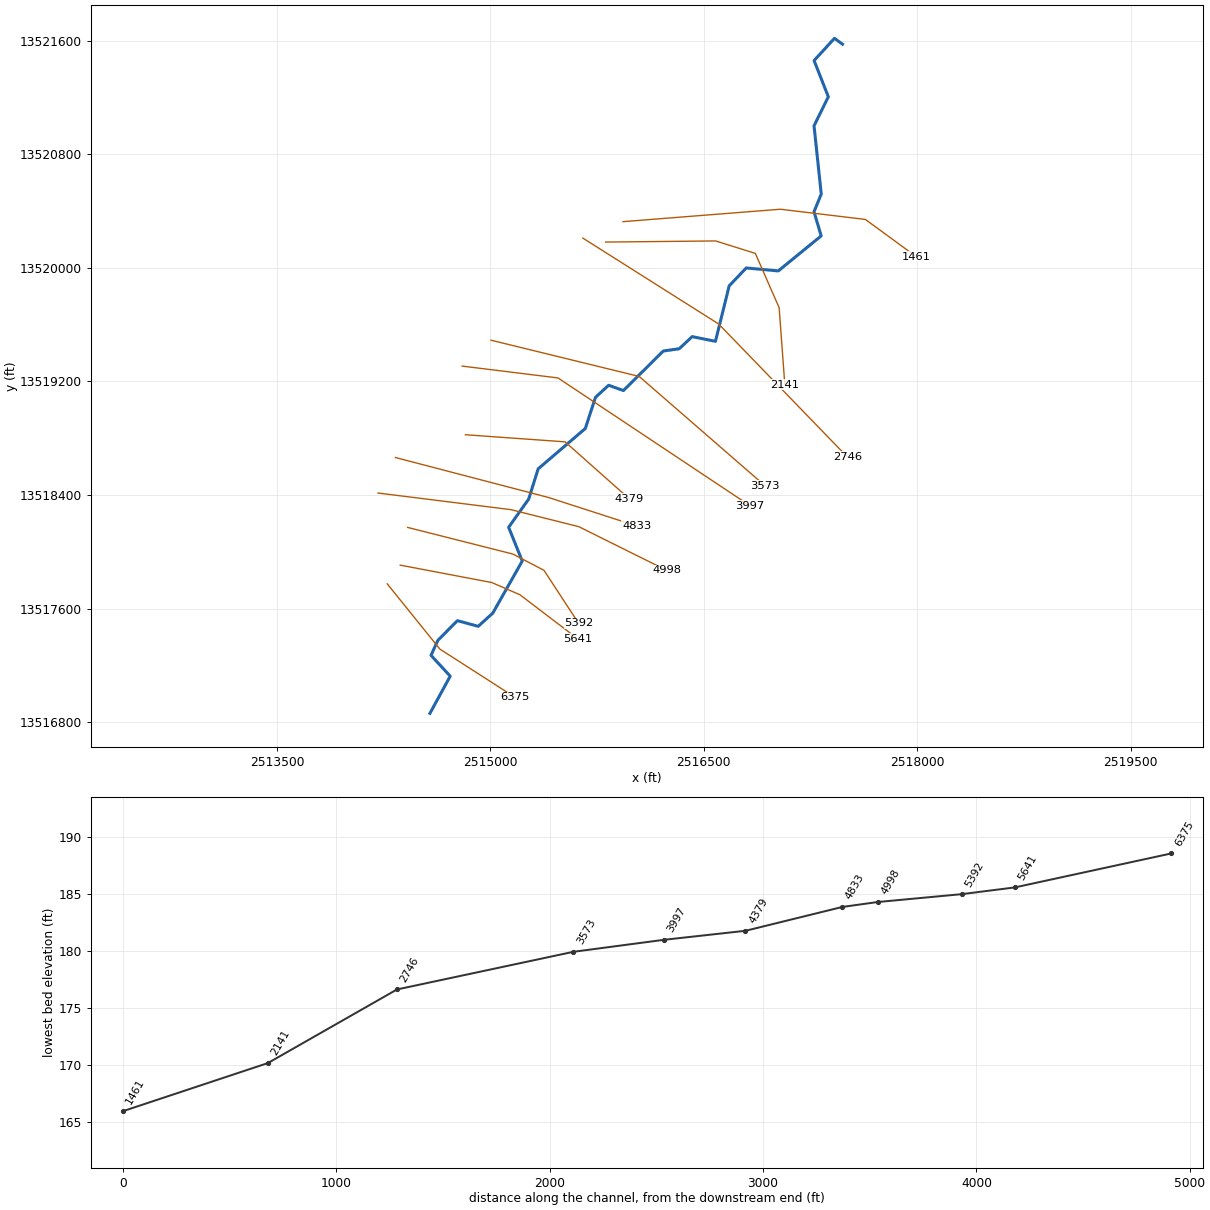
--- TRIB 7 TO TWELVEMILE CREEK.prj (project) ---

Proj Title=TRIB 7 TO TWELVEMILE CREEK Base Level Engineering
Current Plan=p01
Default Exp/Contr=0.3,0.1
English Units
Geom File=g01
Flow File=f01
Plan File=p01
Y Axis Title=Elevation
X Axis Title(PF)=Main Channel Distance
X Axis Title(XS)=Station
BEGIN DESCRIPTION:
TRIB 7 TO TWELVEMILE CREEK
END DESCRIPTION:
DSS Export Rating Curves= 0
DSS Export Rating Curve Sorted= 0
DSS Export Volume Flow Curves= 0
DXF OffsetX= 0
DXF OffsetY= 0
DXF ScaleX= 1
DXF ScaleY= 10

--- TRIB 7 TO TWELVEMILE CREEK.p01 (plan) ---

Plan Title=Multiple Run
Short Identifier=Multiple
Geom File=g01
Flow File=f01
Subcritical Flow
K Sum by GR= 0
Std Step Tol= 0.01
Critical Tol= 0.01
Num of Std Step Trials= 20
Max Error Tol= 0.3
Flow Tol Ratio= 0.001
Split Flow NTrial= 30
Split Flow Tol= 0.02
Split Flow Ratio= 0.02
Log Output Level= 0
Friction Slope Method= 1
Unsteady Friction Slope Method= 2
Unsteady Bridges Friction Slope Method= 1
Parabolic Critical Depth
Global Vel Dist=  1 , 1 , 1
Global Log Level= 0
CheckData=True
Encroach Param= -1, 0, 0, 0
BEGIN DESCRIPTION:
Multiple Run
END DESCRIPTION:

--- TRIB 7 TO TWELVEMILE CREEK.f01 (steady flow) ---

Flow Title=Multiple
Number of Profiles=7
Profile Names=10-year,25-year,50-year,1pct_min,100-year,1pct_plu,500-year
River Rch & RM= TRIB 7 TO TWELVE,Reach-1,6375
     721    1157    1550    1004    2004    3998    3311
River Rch & RM= TRIB 7 TO TWELVE,Reach-1,1461
    1279    2123    2906    1921    3833    7649    6601
Boundary for River Rch & Prof#=TRIB 7 TO TWELVE,Reach-1,1
Up Type=0
Dn Type=3
Dn Slope=0.005
Boundary for River Rch & Prof#=TRIB 7 TO TWELVE,Reach-1,2
Up Type=0
Dn Type=3
Dn Slope=0.005
Boundary for River Rch & Prof#=TRIB 7 TO TWELVE,Reach-1,3
Up Type=0
Dn Type=3
Dn Slope=0.005
Boundary for River Rch & Prof#=TRIB 7 TO TWELVE,Reach-1,4
Up Type=0
Dn Type=3
Dn Slope=0.005
Boundary for River Rch & Prof#=TRIB 7 TO TWELVE,Reach-1,5
Up Type=0
Dn Type=3
Dn Slope=0.005
Boundary for River Rch & Prof#=TRIB 7 TO TWELVE,Reach-1,6
Up Type=0
Dn Type=3
Dn Slope=0.005
Boundary for River Rch & Prof#=TRIB 7 TO TWELVE,Reach-1,7
Up Type=0
Dn Type=3
Dn Slope=0.005

--- TRIB 7 TO TWELVEMILE CREEK.g01 (geometry) ---

Geom Title=Existing Conditions
Program Version=4.10

River Reach=TRIB 7 TO TWELVE,Reach-1
Reach XY= 30
        2514575.     13516863.02      2514717.69      13517125.1
      2514582.77     13517271.59       2514630.8     13517377.29
      2514768.26     13517515.87      2514914.52     13517475.94
      2515016.87     13517568.92      2515223.92     13517935.55
      2515128.31     13518173.27      2515269.46     13518372.58
      2515335.76     13518584.68      2515667.15     13518868.81
      2515738.61     13519088.25      2515831.04     13519173.35
      2515935.05     13519136.11      2516215.21     13519414.48
      2516327.43     13519430.55      2516418.27     13519515.85
       2516581.8     13519482.76      2516678.61      13519873.5
      2516798.31     13519999.28      2517023.53     13519978.53
        2517325.       13520225.       2517274.7     13520395.18
       2517325.5     13520519.84      2517274.79     13521000.09
       2517375.3     13521204.82      2517275.24     13521459.78
      2517418.33     13521616.23        2517475.       13521575.

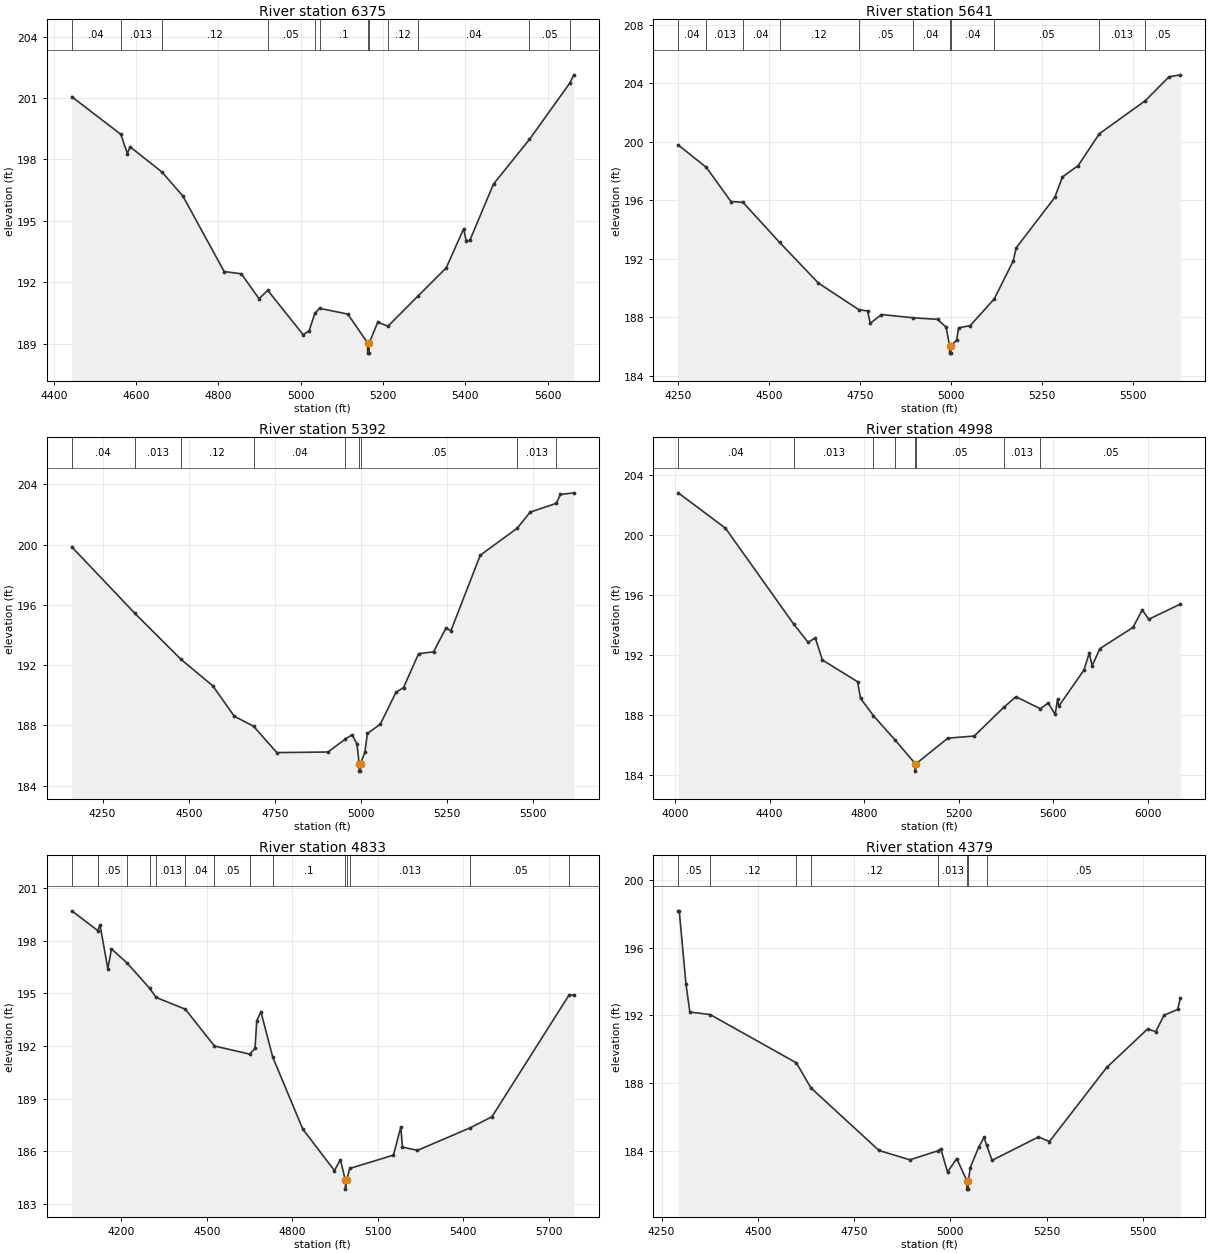
Type RM Length L Ch R = 1 ,6375    ,734,734,734
BEGIN DESCRIPTION:
TRIB 7_1 TO TWELVEMILE CREEK 7.0
END DESCRIPTION:
XS GIS Cut Line= 3
      2514274.98     13517775.03      2514645.03      13517315.6
      2515174.99     13516975.01
#Sta/Elev= 30
  4443.6  201.07  4562.8  199.23  4578.8  198.29  4585.2  198.62  4662.6  197.39
  4713.3  196.22  4813.9  192.52  4855.6  192.41  4898.7  191.19  4919.8   191.6
  5005.9  189.43  5020.3  189.62  5034.1  190.47  5045.6  190.72  5114.3  190.44
  5162.3  189.03  5162.5  188.53    5166  188.53  5166.3  189.03    5187  190.04
    5212  189.85  5283.7   191.3  5353.4   192.7  5395.7  194.61    5402  194.03
  5410.9  194.05  5468.3   196.8  5555.6  198.98  5653.8  201.74  5663.5  202.14
#Mann= 12 ,-1 , 0
  4443.6     .04       0  4562.8    .013       0  4662.6     .12       0
  4919.8     .05       0  5034.1     .12       0  5045.6      .1       0
  5162.3     .05       0  5166.3      .1       0    5212     .12       0
  5283.7     .04       0  5555.6     .05       0  5653.8     .04       0
Bank Sta=5162.3,5166.3
XS Rating Curve= 0 ,0
Exp/Cntr=0.3,0.1

Type RM Length L Ch R = 1 ,5641    ,249,249,249
BEGIN DESCRIPTION:
Mapping XS a95531c4
END DESCRIPTION:
XS GIS Cut Line= 4
      2514366.27     13517906.81      2515009.47     13517784.42
      2515207.39     13517698.49      2515612.71      13517389.3
#Sta/Elev= 30
  4250.5  199.79  4327.7  198.26  4395.4  195.92  4428.4  195.87    4529  193.13
    4636  190.34  4746.5  188.53  4770.9  188.43  4778.5  187.59  4809.1  188.19
  4895.3  187.97  4963.4  187.86  4986.9  187.33  4996.5  186.05  4996.7  185.55
  5000.2  185.55  5000.5  186.05  5015.8  186.44  5021.3  187.28    5053  187.43
  5119.3  189.26  5171.3  191.85  5179.5  192.75  5285.6   196.2  5306.7   197.6
    5350  198.38  5408.2  200.56  5534.6  202.82  5599.5  204.45  5630.8  204.59
#Mann= 11 ,-1 , 0
  4250.5     .04       0  4327.7    .013       0  4428.4     .04       0
    4529     .12       0  4746.5     .05       0  4895.3     .04       0
  4996.5     .04       0  5000.5     .04       0  5119.3     .05       0
  5408.2    .013       0  5534.6     .05       0
Bank Sta=4996.5,5000.5
XS Rating Curve= 0 ,0
Exp/Cntr=0.3,0.1

Type RM Length L Ch R = 1 ,5392    ,394,394,394
BEGIN DESCRIPTION:
Mapping XS d11cf0f4
END DESCRIPTION:
XS GIS Cut Line= 4
      2514418.29     13518172.45      2515157.91     13517984.94
      2515376.66     13517870.36      2515620.75     13517496.44
#Sta/Elev= 30
  4160.8  199.85  4343.8  195.44  4477.8  192.38  4570.1  190.62    4632  188.61
  4688.2  187.94  4755.8  186.19  4904.3  186.23  4954.2  187.09  4974.5  187.38
  4988.3  186.74  4994.5  185.46  4994.8  184.96  4998.3  184.96  4998.5  185.46
  5010.8   186.2  5018.6  187.46    5056  188.08  5101.2  190.19  5123.3  190.51
    5167  192.76  5210.2  192.88  5246.4  194.46  5260.8  194.29  5345.9   199.3
    5453  201.09  5490.7  202.16  5566.2  202.74  5578.3  203.33  5617.3  203.44
#Mann= 9 ,-1 , 0
  4160.8     .04       0  4343.8    .013       0  4477.8     .12       0
  4688.2     .04       0  4954.2     .05       0  4994.5     .05       0
  4998.5     .05       0    5453    .013       0  5566.2     .05       0
Bank Sta=4994.5,4998.5
XS Rating Curve= 0 ,0
Exp/Cntr=0.3,0.1

Type RM Length L Ch R = 1 ,4998    ,165,165,165
BEGIN DESCRIPTION:
Mapping XS 9f27a849
END DESCRIPTION:
XS GIS Cut Line= 4
        2514210.     13518414.63      2515144.89     13518297.44
      2515621.45     13518177.65       2516238.6     13517870.38
#Sta/Elev= 30
  4013.9  202.83  4213.7  200.47  4502.4  194.07  4563.2  192.86  4593.4  193.16
  4623.6  191.68  4772.3  190.23  4784.9  189.12  4839.3  187.97  4932.2  186.32
  5016.1  184.77  5016.3  184.27  5020.1  184.77    5154  186.47  5265.5  186.61
  5390.5  188.53  5441.9  189.23  5545.4  188.43  5578.4  188.82  5607.8  188.05
  5617.6  189.06  5623.2  188.61  5729.5  191.01  5751.9  192.14  5764.2   191.3
  5796.7  192.44  5936.6  193.85  5975.8  195.02  6003.8   194.4  6136.9  195.41
#Mann= 8 ,-1 , 0
  4013.9     .04       0  4502.4    .013       0  4839.3     .04       0
  4932.2     .05       0  5016.1     .05       0  5020.1     .05       0
  5390.5    .013       0  5545.4     .05       0
Bank Sta=5016.1,5020.1
XS Rating Curve= 0 ,0
Exp/Cntr=0.3,0.1

Type RM Length L Ch R = 1 ,4833    ,454,454,454
BEGIN DESCRIPTION:
Mapping XS cbae4a4a
END DESCRIPTION:
XS GIS Cut Line= 3
      2514332.41     13518664.62      2515407.91     13518383.38
      2516027.72     13518182.86
#Sta/Elev= 30
  4025.6  199.71  4117.2  198.58  4124.7  198.92  4152.3   196.4  4165.1  197.54
  4219.6  196.74  4298.7   195.3    4322  194.77  4424.3   194.1  4526.7     192
  4650.4  191.54  4669.1  191.87  4675.3  193.45  4689.8  193.95  4731.5  191.36
    4837  187.26    4948   184.9  4968.9  185.52  4986.4  184.34  4986.7  183.84
  4990.4  184.34  5002.1  185.02  5155.2  185.78  5181.1  187.38  5186.8  186.24
  5239.3  186.05  5425.4  187.34  5501.2  187.97  5771.1  194.89  5788.7  194.92
#Mann= 14 ,-1 , 0
  4025.6     .12       0  4117.2     .05       0  4219.6    .013       0
  4298.7     .04       0    4322    .013       0  4424.3     .04       0
  4526.7     .05       0  4650.4     .04       0  4731.5      .1       0
  4986.4     .05       0  4990.4      .1       0  5002.1    .013       0
  5425.4     .05       0  5771.1     .04       0
Bank Sta=4986.4,4990.4
XS Rating Curve= 0 ,0
Exp/Cntr=0.3,0.1

Type RM Length L Ch R = 1 ,4379    ,382,382,382
BEGIN DESCRIPTION:
TRIB 7_1 TO TWELVEMILE CREEK 3.0
END DESCRIPTION:
XS GIS Cut Line= 3
      2514824.95       13518825.        2515525.       13518775.
      2515974.99     13518375.01
#Sta/Elev= 30
  4293.2  198.17  4295.8  198.17  4313.3  193.86  4323.3   192.2  4376.1  192.05
  4600.1   189.2  4637.5  187.73  4814.6  184.03  4894.8  183.48  4968.7  184.02
    4975  184.14  4992.5  182.76  5016.4  183.55  5042.8  182.25    5043  181.75
  5046.5  181.75  5046.8  182.25  5051.5  183.02  5073.2  184.21  5087.4  184.81
    5094  184.35  5108.3  183.45  5228.8  184.83  5257.2  184.56    5406  188.93
  5512.2   191.2  5533.1  191.04  5554.9  192.01    5590  192.35  5597.1  193.01
#Mann= 8 ,-1 , 0
  4293.2     .05       0  4376.1     .12       0  4600.1     .05       0
  4637.5     .12       0  4968.7    .013       0  5042.8     .03       0
  5046.8    .013       0    5094     .05       0
Bank Sta=5042.8,5046.8
XS Rating Curve= 0 ,0
Exp/Cntr=0.3,0.1

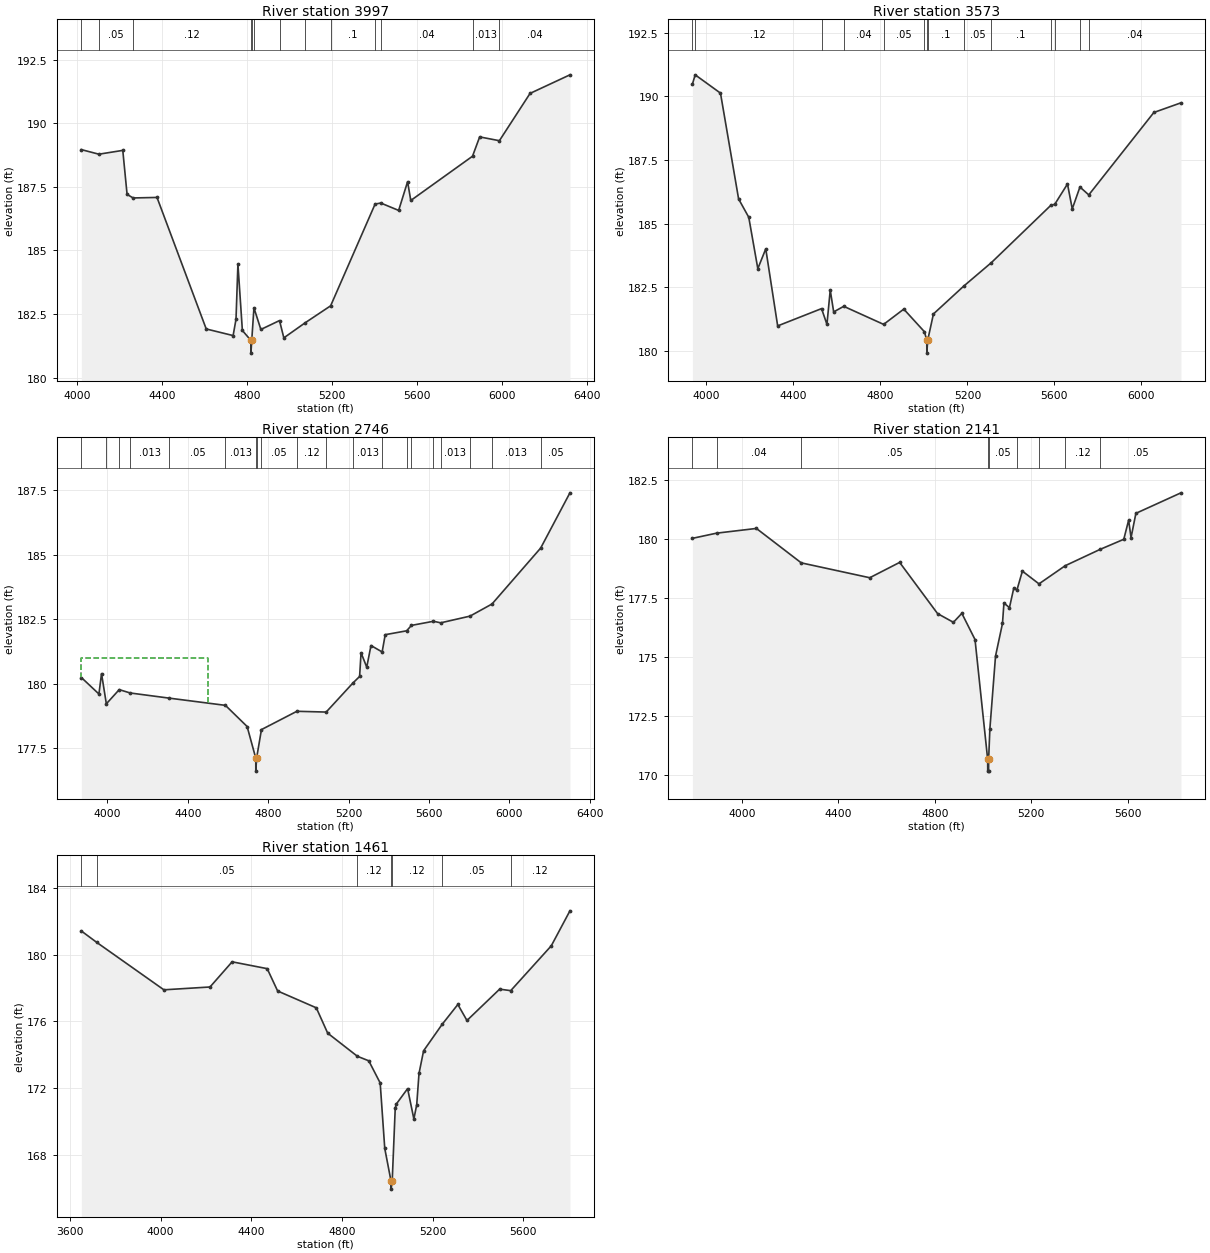
Type RM Length L Ch R = 1 ,3997    ,424,424,424
BEGIN DESCRIPTION:
TRIB 7_1 TO TWELVEMILE CREEK 2.0
END DESCRIPTION:
XS GIS Cut Line= 3
      2514801.26     13519308.39        2515475.       13519225.
      2516825.02     13518324.99
#Sta/Elev= 30
  4019.9  188.96  4102.6  188.78  4215.1  188.93  4235.3   187.2  4263.8  187.06
  4376.3  187.08  4608.1  181.91  4734.8  181.65  4748.4  182.29  4757.4  184.46
  4778.4  181.85  4818.5  181.46  4818.7  180.96  4822.5  181.46  4832.9  182.74
  4865.5  181.89  4953.3  182.24  4973.7  181.56  5073.7  182.15  5194.1  182.82
  5403.6  186.82  5430.3  186.86  5514.5  186.57  5556.6   187.7  5571.6  186.96
  5862.4   188.7  5896.1  189.46    5989  189.31  6133.5  191.17  6321.3   191.9
#Mann= 13 ,-1 , 0
  4019.9     .12       0  4102.6     .05       0  4263.8     .12       0
  4818.5     .04       0  4822.5     .12       0  4832.9    .013       0
  4953.3     .04       0  5073.7     .12       0  5194.1      .1       0
  5403.6     .05       0  5430.3     .04       0  5862.4    .013       0
    5989     .04       0
Bank Sta=4818.5,4822.5
XS Rating Curve= 0 ,0
Exp/Cntr=0.3,0.1

Type RM Length L Ch R = 1 ,3573    ,827,827,827
BEGIN DESCRIPTION:
Mapping XS 25c0cad9
END DESCRIPTION:
XS GIS Cut Line= 3
      2515004.36     13519490.68      2516046.04     13519235.47
      2516930.75     13518465.25
#Sta/Elev= 30
  3936.2  190.48    3949  190.85  4065.3  190.13  4148.6  185.97  4195.3  185.25
  4236.9  183.23  4273.4  184.01  4328.1  180.98  4529.8  181.66  4554.6  181.04
  4569.7  182.39  4585.5  181.53  4631.8  181.75  4815.1  181.04  4907.7  181.64
  5002.7  180.75  5013.5  180.41  5013.7  179.91  5017.5  180.41    5044  181.45
  5182.7  182.54  5310.6  183.47  5583.6  185.72  5601.5  185.76  5660.1  186.56
    5682  185.58  5717.3  186.44  5757.9  186.13    6057  189.37  6181.7  189.75
#Mann= 14 ,-1 , 0
  3936.2     .05       0    3949     .12       0  4529.8    .013       0
  4631.8     .04       0  4815.1     .05       0  5002.7      .1       0
  5013.5     .05       0  5017.5      .1       0  5182.7     .05       0
  5310.6      .1       0  5583.6     .12       0  5601.5    .013       0
  5717.3     .12       0  5757.9     .04       0
Bank Sta=5013.5,5017.5
XS Rating Curve= 0 ,0
Exp/Cntr=0.3,0.1

Type RM Length L Ch R = 1 ,2746    ,605,605,605
BEGIN DESCRIPTION:
LGII4560
END DESCRIPTION:
XS GIS Cut Line= 3
      2515650.18     13520209.44      2516604.48     13519604.84
      2517508.53     13518668.85
#Sta/Elev= 30
  3870.3  180.24  3957.8   179.6  3970.7  180.39  3994.7  179.22  4058.8  179.77
  4113.2  179.64  4307.4  179.44  4587.2  179.16  4695.1  178.34  4738.2  177.11
  4738.4  176.61  4742.2  177.11  4766.4  178.22  4942.7  178.93  5088.5   178.9
  5221.9  180.03  5254.8  180.28    5262   181.2  5290.3  180.64  5311.4  181.48
  5366.9  181.23  5382.2   181.9  5488.7  182.05  5512.7  182.26  5622.1  182.42
  5658.4  182.36  5804.2  182.62  5913.6  183.09  6155.8  185.26  6301.3   187.4
#Mann= 20 ,-1 , 0
  3870.3     .04       0  3994.7    .013       0  4058.8     .04       0
  4113.2    .013       0  4307.4     .05       0  4587.2    .013       0
  4738.2     .05       0  4742.2    .013       0  4766.4     .05       0
  4942.7     .12       0  5088.5    .013       0  5221.9    .013       0
  5366.9    .013       0  5488.7     .12       0  5512.7    .013       0
  5622.1     .12       0  5658.4    .013       0  5804.2     .12       0
  5913.6    .013       0  6155.8     .05       0
#XS Ineff= 2 , 0
       0    4500     181               0
Permanent Ineff=
       F       F
Bank Sta=4738.2,4742.2
XS Rating Curve= 0 ,0
Exp/Cntr=0.3,0.1

Type RM Length L Ch R = 1 ,2141    ,680,680,680
BEGIN DESCRIPTION:
4893
END DESCRIPTION:
XS GIS Cut Line= 5
       2515809.6     13520181.65      2516583.09     13520189.63
      2516862.18     13520101.91      2517029.63     13519719.16
      2517069.39     13519178.48
#Sta/Elev= 30
  3794.9  180.03  3895.2  180.25  4060.3  180.45  4246.4  178.99  4530.3  178.36
  4654.3  179.01  4811.5  176.84  4877.2  176.47  4912.2  176.85  4966.8  175.74
  5019.3  170.66  5019.6  170.16  5023.1  170.16  5023.3  170.66  5028.5  171.96
  5051.9  175.04  5080.7  176.42  5086.8  177.29  5109.6  177.09  5127.5  177.92
  5140.7  177.84  5163.2  178.64  5232.1   178.1  5340.9  178.87  5485.1  179.56
  5583.7  179.99  5603.8   180.8  5613.8  180.06  5633.9  181.09  5820.9  181.96
#Mann= 9 ,-1 , 0
  3794.9    .013       0  3895.2     .04       0  4246.4     .05       0
  5019.3     .05       0  5023.3     .05       0  5140.7     .12       0
  5232.1     .05       0  5340.9     .12       0  5485.1     .05       0
Bank Sta=5019.3,5023.3
XS Rating Curve= 0 ,0
Exp/Cntr=0.3,0.1

Type RM Length L Ch R = 1 ,1461    ,0,0,0
BEGIN DESCRIPTION:
4894
END DESCRIPTION:
XS GIS Cut Line= 4
      2515932.13      13520325.4      2517037.61      13520412.9
      2517635.66     13520341.13      2517993.16     13520078.97
#Sta/Elev= 30
  3650.9  181.43  3719.4  180.74  4014.9   177.9  4218.3  178.07  4315.8  179.58
  4470.5  179.17  4516.5  177.83    4687  176.82  4737.2   175.3  4868.4  173.91
  4918.4  173.64  4968.7  172.31  4988.9  168.38  5016.3  166.44  5016.8  165.94
  5021.8  166.44  5035.1   170.8  5040.1  171.05  5089.6  171.97  5117.3  170.15
  5129.9  171.01  5139.9  172.88  5160.1  174.24  5241.5  175.82  5311.2  177.02
  5351.4  176.06  5495.5  177.94  5544.4  177.85  5723.2  180.54  5805.5  182.64
#Mann= 7 ,-1 , 0
  3650.9     .04       0  3719.4     .05       0  4868.4     .12       0
  5016.3     .05       0  5021.8     .12       0  5241.5     .05       0
  5544.4     .12       0
Bank Sta=5016.3,5021.8
XS Rating Curve= 0 ,0
Exp/Cntr=0.3,0.1

Chan Stop Cuts=-1
Use User Specified Reach Order=0
Composite Channel Slope=5