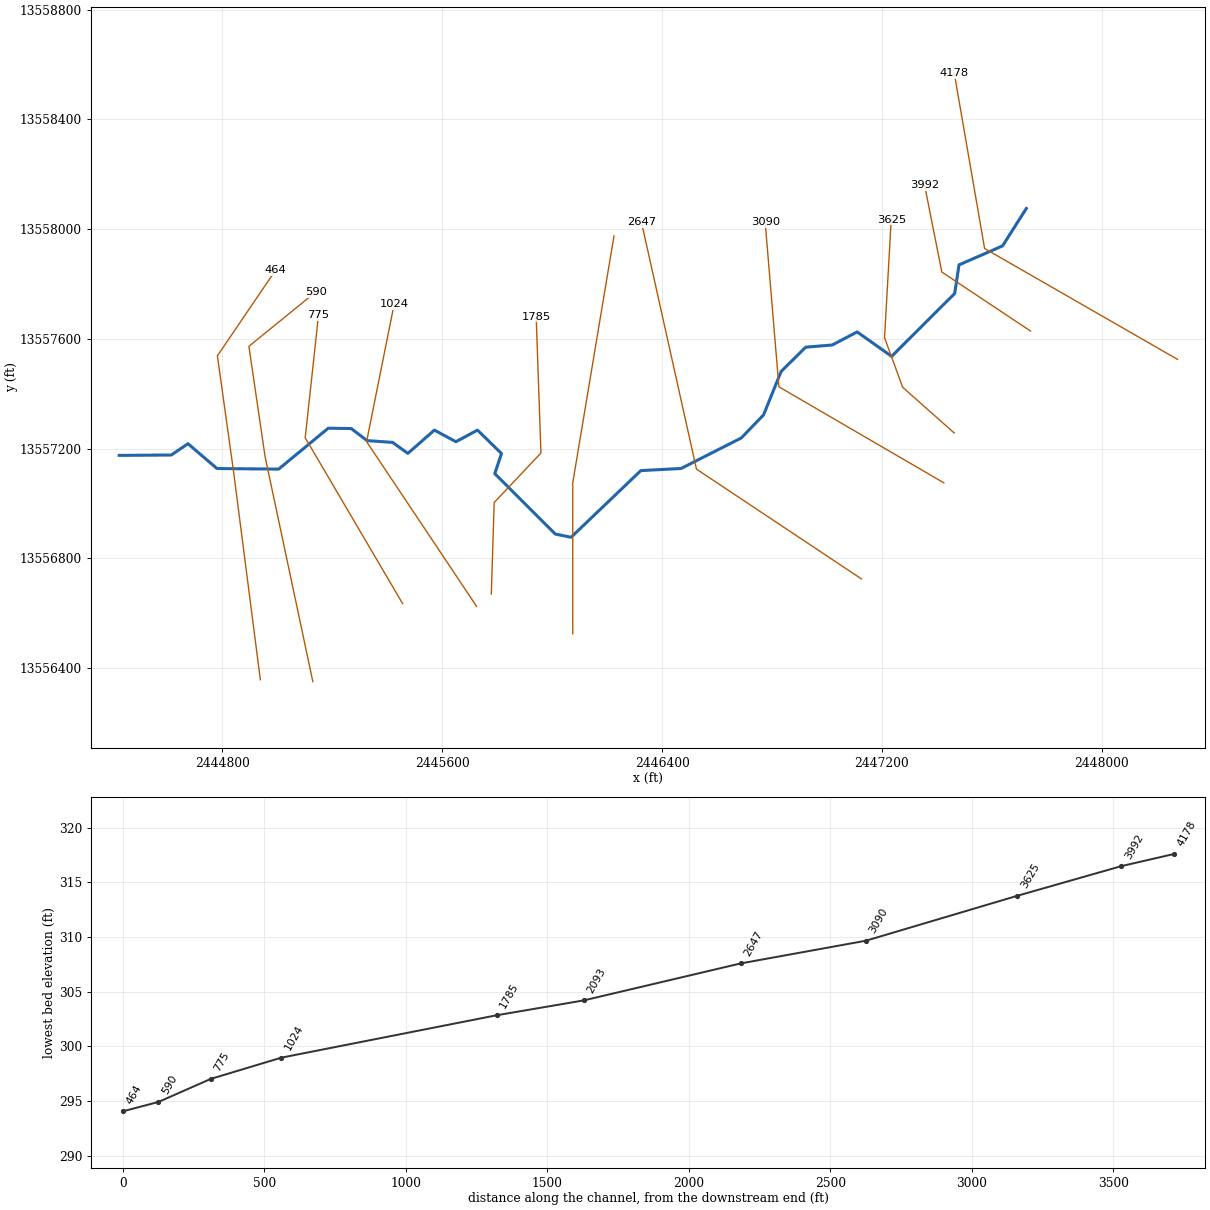
--- TRIB 7 TO YORKTOWN CREEK.prj (project) ---

Proj Title=TRIB 7 TO YORKTOWN CREEK Base Level Engineering
Current Plan=p01
Default Exp/Contr=0.3,0.1
English Units
Geom File=g01
Flow File=f01
Plan File=p01
BEGIN DESCRIPTION:
TRIB 7 TO YORKTOWN CREEK
END DESCRIPTION:

--- TRIB 7 TO YORKTOWN CREEK.p01 (plan) ---

Plan Title=Multiple Run
Short Identifier=Multiple
Geom File=g01
Flow File=f01
Subcritical Flow
K Sum by GR= 0
Std Step Tol= 0.01
Critical Tol= 0.01
Num of Std Step Trials= 20
Max Error Tol= 0.3
Flow Tol Ratio= 0.001
Split Flow NTrial= 30
Split Flow Tol= 0.02
Split Flow Ratio= 0.02
Log Output Level= 0
Friction Slope Method= 1
Unsteady Friction Slope Method= 2
Unsteady Bridges Friction Slope Method= 1
Parabolic Critical Depth
Global Vel Dist=  1 , 1 , 1
Global Log Level= 0
CheckData=True
Encroach Param= -1, 0, 0, 0
BEGIN DESCRIPTION:
Multiple Run
END DESCRIPTION:

--- TRIB 7 TO YORKTOWN CREEK.f01 (steady flow) ---

Flow Title=Multiple
Number of Profiles=7
Profile Names=10-year,25-year,50-year,1pct_min,100-year,1pct_plu,500-year
River Rch & RM= TRIB 7 TO YORKTO,Reach-1,4178
     600     970    1305     851    1697    3386    2843
Boundary for River Rch & Prof#=TRIB 7 TO YORKTO,Reach-1,1
Up Type=0
Dn Type=3
Dn Slope=0.005
Boundary for River Rch & Prof#=TRIB 7 TO YORKTO,Reach-1,2
Up Type=0
Dn Type=3
Dn Slope=0.005
Boundary for River Rch & Prof#=TRIB 7 TO YORKTO,Reach-1,3
Up Type=0
Dn Type=3
Dn Slope=0.005
Boundary for River Rch & Prof#=TRIB 7 TO YORKTO,Reach-1,4
Up Type=0
Dn Type=3
Dn Slope=0.005
Boundary for River Rch & Prof#=TRIB 7 TO YORKTO,Reach-1,5
Up Type=0
Dn Type=3
Dn Slope=0.005
Boundary for River Rch & Prof#=TRIB 7 TO YORKTO,Reach-1,6
Up Type=0
Dn Type=3
Dn Slope=0.005
Boundary for River Rch & Prof#=TRIB 7 TO YORKTO,Reach-1,7
Up Type=0
Dn Type=3
Dn Slope=0.005

--- TRIB 7 TO YORKTOWN CREEK.g01 (geometry) ---

Geom Title=Existing Conditions

River Reach=TRIB 7 TO YORKTO,Reach-1
Reach XY= 30
      2447725.00     13558075.00      2447638.57     13557938.46
      2447480.25     13557869.56      2447464.47     13557765.25
      2447235.00     13557535.96      2447109.66     13557625.04
      2447019.03     13557577.38      2446922.56     13557569.48
      2446833.13     13557481.07      2446769.17     13557322.69
      2446688.24     13557238.61      2446469.07     13557127.25
      2446322.55     13557119.53      2446068.95     13556876.58
      2446011.79     13556888.11      2445791.39     13557108.33
      2445815.70     13557181.70      2445728.44     13557267.18
      2445650.00     13557224.79      2445571.59     13557267.15
      2445475.10     13557182.34      2445419.11     13557222.44
      2445326.60     13557228.86      2445269.02     13557272.84
      2445185.48     13557274.07      2445005.02     13557124.96
      2444780.85     13557127.07      2444675.10     13557217.67
      2444614.57     13557176.38      2444425.00     13557175.00

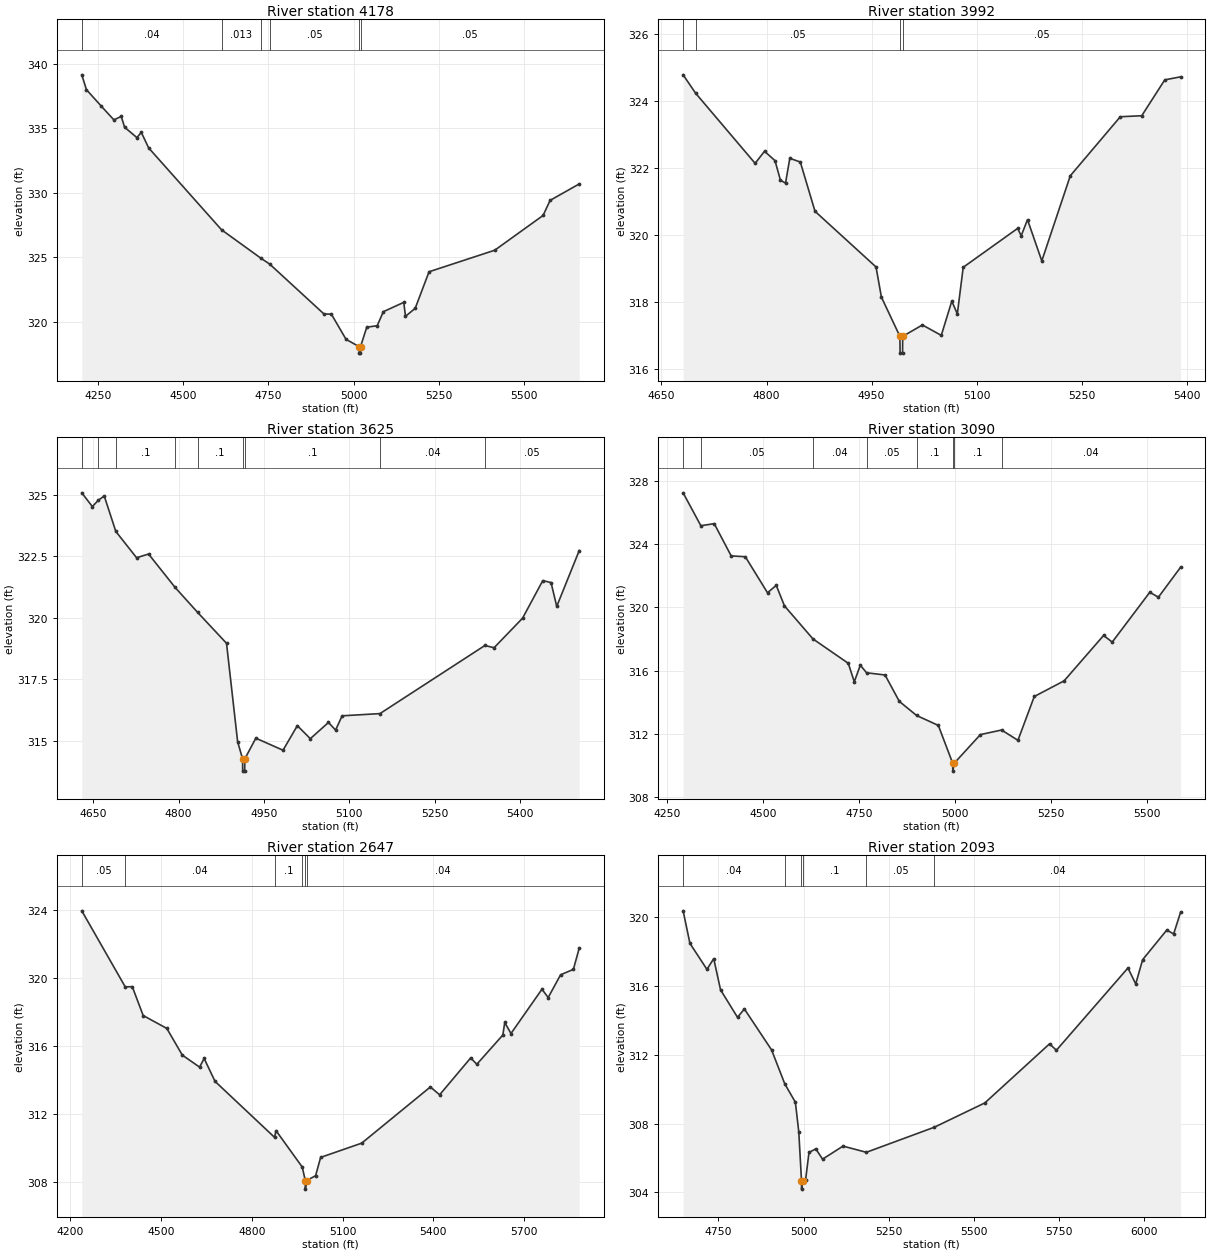
Type RM Length L Ch R = 1,4178,186,186,186
BEGIN DESCRIPTION:
TRIB 7 TO YORKTOWN CREEK 8.0
END DESCRIPTION:
XS GIS Cut Line= 3
      2448275.03     13557524.99      2447573.25     13557929.22
      2447462.75     13558569.08
#Sta/Elev= 30
  4202.7  339.13  4216.4  337.98  4260.4  336.69  4296.9  335.64  4318.4  335.91
  4328.4  335.07  4364.3  334.27  4377.3  334.67  4398.9  333.47  4612.7  327.13
  4728.1  324.93  4753.7  324.48  4913.2  320.61  4934.8  320.60  4977.9  318.65
  5016.4  318.08  5016.7  317.58  5020.2  317.58  5020.4  318.08  5038.7  319.59
  5069.2  319.70  5087.4  320.79  5147.2  321.51  5152.3  320.43  5180.8  321.05
  5221.4  323.88  5414.2  325.55  5555.9  328.24  5576.6  329.41  5661.9  330.68
#Mann=6,-1,0
  4202.7    0.04       0  4612.7   0.013       0  4728.1    0.04       0
  4753.7    0.05       0  5016.4    0.05       0  5020.4    0.05       0
Bank Sta=5016.4,5020.4
Exp/Cntr=0.3,0.1

Type RM Length L Ch R = 1,3992,367,367,367
BEGIN DESCRIPTION:
Mapping XS 2c123f21
END DESCRIPTION:
XS GIS Cut Line= 3
      2447740.56     13557628.12      2447417.61     13557843.42
      2447355.11     13558159.36
#Sta/Elev= 30
  4680.9  324.77  4698.8  324.22  4783.7  322.13  4797.1  322.49  4812.1  322.21
  4819.8  321.63  4827.1  321.54  4833.2  322.28  4848.2  322.17  4869.2  320.70
  4956.3  319.04  4964.0  318.14  4990.4  316.97  4990.7  316.47  4994.2  316.47
  4994.4  316.97  5022.5  317.31  5049.5  317.00  5064.5  318.02  5072.4  317.64
  5080.8  319.03  5158.5  320.19  5163.6  319.97  5172.6  320.45  5193.0  319.22
  5233.7  321.76  5305.1  323.52  5335.7  323.55  5368.6  324.62  5391.1  324.71
#Mann=4,-1,0
  4680.9   0.013       0  4698.8    0.05       0  4990.4    0.05       0
  4994.4    0.05       0
Bank Sta=4990.4,4994.4
Exp/Cntr=0.3,0.1

Type RM Length L Ch R = 1,3625,535,535,535
BEGIN DESCRIPTION:
Mapping XS 1f32ccbd
END DESCRIPTION:
XS GIS Cut Line= 4
      2447462.71     13557256.64      2447275.25     13557423.28
      2447209.28     13557603.83      2447233.58     13558034.40
#Sta/Elev= 30
  4629.7  325.08  4648.3  324.52  4658.8  324.78  4669.2  324.95  4689.5  323.51
  4726.0  322.44  4747.1  322.59  4793.8  321.23  4833.2  320.22  4884.1  318.96
  4903.6  314.96  4912.3  314.26  4912.5  313.76  4916.0  313.76  4916.3  314.26
  4935.6  315.10  4983.4  314.61  5008.6  315.61  5031.4  315.08  5063.3  315.74
  5075.8  315.43  5087.3  316.01  5153.8  316.10  5338.2  318.87  5354.4  318.78
  5404.4  319.98  5440.0  321.51  5454.5  321.43  5464.5  320.46  5504.0  322.73
#Mann=9,-1,0
  4629.7   0.013       0  4658.8    0.05       0  4689.5     0.1       0
  4793.8    0.04       0  4833.2     0.1       0  4912.3    0.05       0
  4916.3     0.1       0  5153.8    0.04       0  5338.2    0.05       0
Bank Sta=4912.3,4916.3
Exp/Cntr=0.3,0.1

Type RM Length L Ch R = 1,3090,443,443,443
BEGIN DESCRIPTION:
TRIB 7 TO YORKTOWN CREEK 5.0
END DESCRIPTION:
XS GIS Cut Line= 3
      2447425.04     13557074.98      2446825.00     13557425.00
      2446775.00     13558024.95
#Sta/Elev= 30
  4291.1  327.25  4337.3  325.17  4372.2  325.30  4416.4  323.26  4453.2  323.21
  4511.1  320.93  4533.8  321.40  4555.3  320.10  4629.6  318.01  4721.6  316.47
  4737.3  315.30  4753.0  316.35  4769.3  315.87  4817.5  315.73  4854.7  314.06
  4899.7  313.17  4956.4  312.54  4993.8  310.15  4994.1  309.65  4997.8  310.15
  5066.0  311.96  5121.2  312.25  5163.9  311.60  5206.5  314.37  5284.3  315.36
  5387.2  318.23  5409.7  317.81  5507.6  320.96  5530.1  320.65  5587.8  322.54
#Mann=8,-1,0
  4291.1   0.013       0  4337.3    0.05       0  4629.6    0.04       0
  4769.3    0.05       0  4899.7     0.1       0  4993.8    0.05       0
  4997.8     0.1       0  5121.2    0.04       0
Bank Sta=4993.8,4997.8
Exp/Cntr=0.3,0.1

Type RM Length L Ch R = 1,2647,554,554,554
BEGIN DESCRIPTION:
TRIB 7 TO YORKTOWN CREEK 4.0
END DESCRIPTION:
XS GIS Cut Line= 3
      2447125.00     13556725.00      2446525.00     13557125.00
      2446324.99     13558025.03
#Sta/Elev= 30
  4238.5  323.97  4382.0  319.49  4405.3  319.50  4441.3  317.80  4519.4  317.04
  4570.5  315.47  4627.6  314.76  4642.6  315.27  4678.7  313.92  4875.4  310.62
  4880.0  311.02  4966.8  308.87  4976.8  308.07  4977.1  307.57  4980.8  308.07
  5010.8  308.36  5027.5  309.44  5163.2  310.28  5389.9  313.59  5420.6  313.13
  5523.0  315.30  5543.5  314.93  5629.3  316.65  5635.7  317.39  5656.2  316.74
  5758.6  319.35  5779.1  318.86  5820.1  320.20  5862.4  320.52  5881.6  321.77
#Mann=6,-1,0
  4238.5    0.05       0  4382.0    0.04       0  4875.4     0.1       0
  4966.8    0.04       0  4976.8    0.04       0  4980.8    0.04       0
Bank Sta=4976.8,4980.8
Exp/Cntr=0.3,0.1

Type RM Length L Ch R = 1,2093,308,308,308
BEGIN DESCRIPTION:
TRIB 7 TO YORKTOWN CREEK 3.0
END DESCRIPTION:
XS GIS Cut Line= 3
      2446075.00     13556525.02      2446075.00     13557075.00
      2446225.00     13557975.00
#Sta/Elev= 30
  4646.1  320.36  4666.1  318.47  4716.1  316.96  4736.1  317.58  4756.1  315.77
  4806.1  314.17  4826.1  314.66  4906.1  312.28  4945.1  310.30  4976.1  309.24
  4986.1  307.52  4994.1  304.69  4994.3  304.19  4998.1  304.69  5006.1  304.72
  5016.1  306.32  5036.1  306.53  5056.1  305.93  5116.1  306.69  5184.8  306.33
  5385.0  307.79  5533.2  309.20  5723.3  312.63  5743.5  312.26  5953.9  317.04
  5976.7  316.11  5997.0  317.52  6067.9  319.24  6088.2  319.02  6108.5  320.27
#Mann=6,-1,0
  4646.1    0.04       0  4945.1     0.1       0  4994.1    0.05       0
  4998.1     0.1       0  5184.8    0.05       0  5385.0    0.04       0
Bank Sta=4994.1,4998.1
Exp/Cntr=0.3,0.1

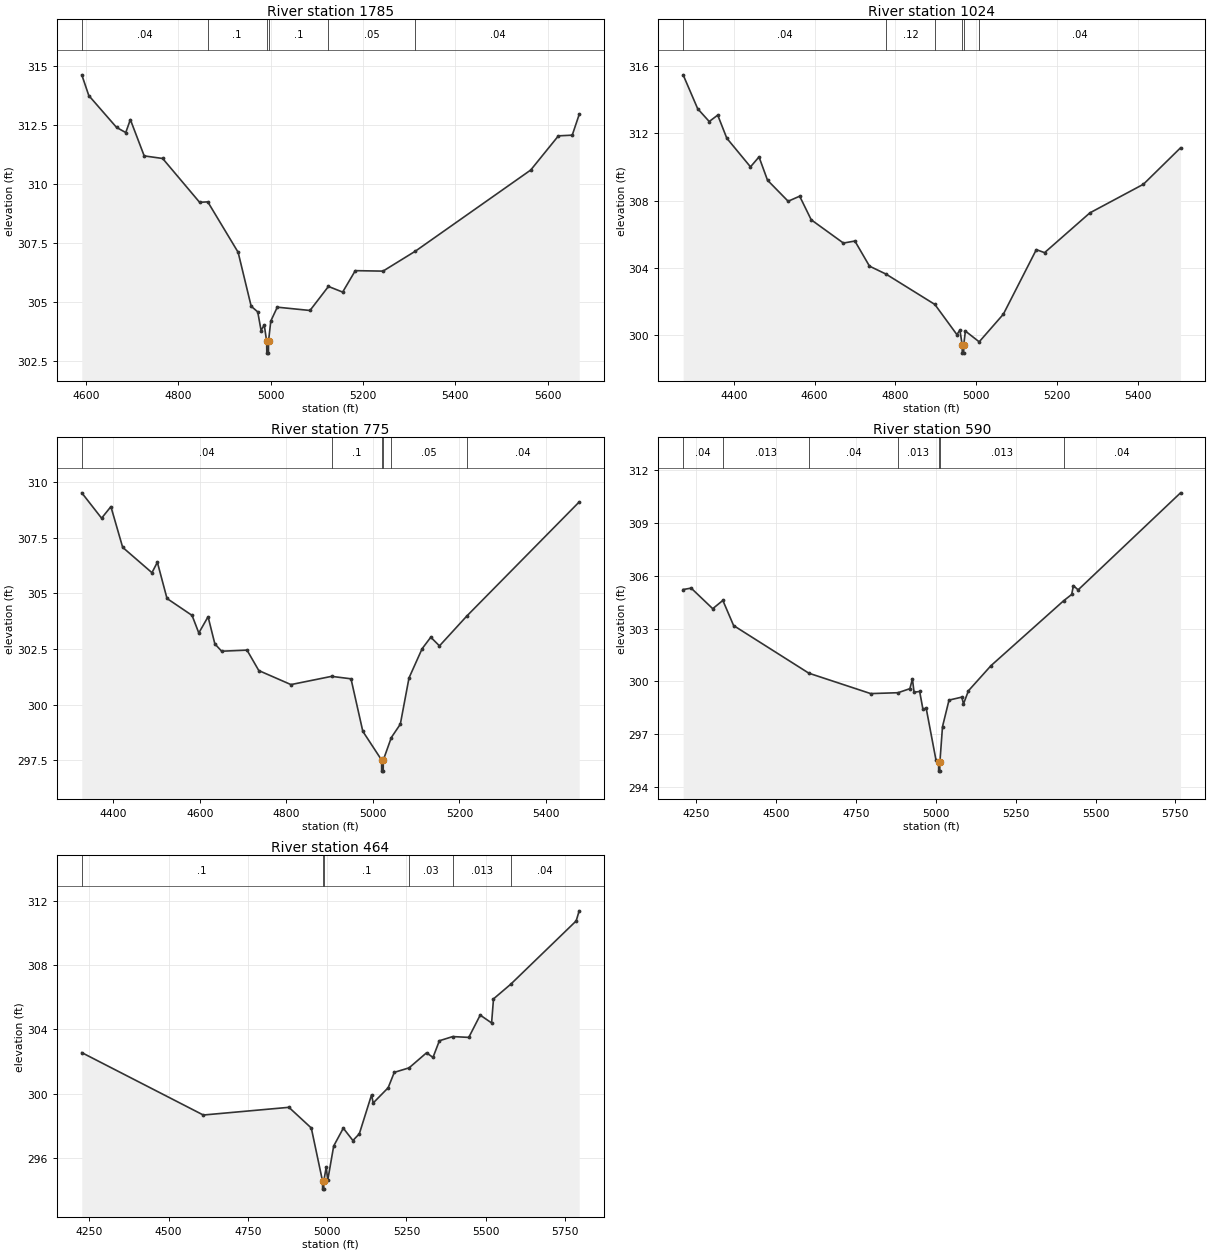
Type RM Length L Ch R = 1,1785,761,761,761
BEGIN DESCRIPTION:
Mapping XS b335ec95
END DESCRIPTION:
XS GIS Cut Line= 4
      2445778.72     13556669.76      2445789.14     13557003.14
      2445959.28     13557183.70      2445941.92     13557680.06
#Sta/Elev= 30
  4590.4  314.64  4605.6  313.76  4665.7  312.41  4685.7  312.19  4695.7  312.74
  4725.7  311.20  4765.7  311.09  4845.8  309.23  4863.5  309.25  4929.3  307.11
  4957.6  304.82  4971.8  304.58  4979.1  303.79  4985.9  304.03  4991.2  303.33
  4991.5  302.83  4995.0  302.83  4995.2  303.33  5000.1  304.19  5014.2  304.78
  5085.1  304.64  5125.1  305.66  5155.9  305.42  5183.3  306.33  5243.4  306.31
  5313.8  307.16  5563.6  310.60  5623.6  312.05  5653.6  312.08  5668.7  312.96
#Mann=6,-1,0
  4590.4    0.04       0  4863.5     0.1       0  4991.2    0.05       0
  4995.2     0.1       0  5125.1    0.05       0  5313.8    0.04       0
Bank Sta=4991.2,4995.2
Exp/Cntr=0.3,0.1

Type RM Length L Ch R = 1,1024,249,249,249
BEGIN DESCRIPTION:
TRIB 7 TO YORKTOWN CREEK 2.0
END DESCRIPTION:
XS GIS Cut Line= 3
      2445724.99     13556625.02      2445325.00     13557225.00
      2445425.00     13557725.01
#Sta/Elev= 30
  4274.6  315.46  4310.6  313.45  4339.2  312.69  4360.2  313.07  4382.7  311.70
  4441.3  310.00  4462.4  310.59  4483.4  309.21  4534.5  307.96  4563.0  308.26
  4591.6  306.86  4671.2  305.48  4699.7  305.60  4735.8  304.11  4776.6  303.64
  4897.5  301.84  4952.1  300.05  4959.6  300.32  4965.1  299.45  4965.4  298.95
  4968.9  298.95  4969.1  299.45  4973.1  300.26  5007.3  299.62  5067.1  301.26
  5148.7  305.09  5169.1  304.91  5281.2  307.27  5413.8  308.97  5505.6  311.13
#Mann=6,-1,0
  4274.6    0.04       0  4776.6    0.12       0  4897.5     0.1       0
  4965.1    0.05       0  4969.1     0.1       0  5007.3    0.04       0
Bank Sta=4965.1,4969.1
Exp/Cntr=0.3,0.1

Type RM Length L Ch R = 1,775,185,185,185
BEGIN DESCRIPTION:
Mapping XS 9657c5f8
END DESCRIPTION:
XS GIS Cut Line= 3
      2445455.82     13556635.06      2445101.64     13557239.25
      2445150.13     13557686.07
#Sta/Elev= 30
  4327.0  309.52  4372.8  308.38  4394.3  308.90  4421.5  307.07  4489.2  305.93
  4501.7  306.40  4524.0  304.77  4581.9  304.01  4597.5  303.22  4618.9  303.95
  4634.6  302.73  4650.3  302.40  4708.9  302.45  4736.2  301.53  4810.5  300.90
  4904.4  301.27  4949.3  301.16  4976.6  298.80  5020.0  297.51  5020.2  297.01
  5023.7  297.01  5024.0  297.51  5042.5  298.52  5063.3  299.12  5083.4  301.20
  5113.6  302.51  5133.7  303.03  5153.8  302.64  5216.9  303.98  5476.8  309.11
#Mann=6,-1,0
  4327.0    0.04       0  4904.4     0.1       0  5020.0    0.05       0
  5024.0     0.1       0  5042.5    0.05       0  5216.9    0.04       0
Bank Sta=5020,5024
Exp/Cntr=0.3,0.1

Type RM Length L Ch R = 1,590,126,126,126
BEGIN DESCRIPTION:
Mapping XS 4afcca94
END DESCRIPTION:
XS GIS Cut Line= 4
      2445129.42     13556350.32      2444955.80     13557169.81
      2444896.78     13557572.58      2445139.52     13557770.25
#Sta/Elev= 30
  4208.5  305.23  4233.7  305.31  4301.2  304.14  4332.9  304.61  4366.6  303.18
  4602.3  300.47  4795.9  299.31  4881.5  299.36  4918.6  299.59  4926.6  300.14
  4931.7  299.39  4949.3  299.43  4959.5  298.42  4969.7  298.48  5000.4  295.53
  5008.6  295.40  5008.8  294.90  5012.3  294.90  5012.6  295.40  5020.8  297.43
  5041.2  298.94  5081.4  299.11  5086.5  298.72  5102.0  299.47  5172.7  300.90
  5400.1  304.59  5425.4  304.95  5430.7  305.45  5445.6  305.21  5766.3  310.73
#Mann=7,-1,0
  4208.5    0.04       0  4332.9   0.013       0  4602.3    0.04       0
  4881.5   0.013       0  5008.6    0.03       0  5012.6   0.013       0
  5400.1    0.04       0
Bank Sta=5008.6,5012.6
Exp/Cntr=0.3,0.1

Type RM Length L Ch R = 1,464,0,0,0
BEGIN DESCRIPTION:
Mapping XS 909c4b28
END DESCRIPTION:
XS GIS Cut Line= 4
      2444938.44     13556357.30      2444841.22     13557114.25
      2444782.19     13557537.86      2444993.89     13557850.20
#Sta/Elev= 30
  4226.3  302.55  4609.4  298.66  4879.3  299.14  4949.9  297.85  4985.3  294.54
  4985.6  294.04  4989.1  294.04  4989.3  294.54  4996.8  295.41  5001.8  294.61
  5020.5  296.73  5050.8  297.84  5081.1  297.07  5101.3  297.49  5139.9  299.92
  5145.0  299.41  5192.2  300.36  5211.5  301.32  5258.1  301.60  5313.3  302.54
  5333.5  302.25  5353.7  303.29  5395.7  303.55  5446.4  303.50  5482.4  304.89
  5518.3  304.40  5524.3  305.90  5578.4  306.81  5784.9  310.76  5794.5  311.39
#Mann=6,-1,0
  4226.3     0.1       0  4985.3    0.05       0  4989.3     0.1       0
  5258.1    0.03       0  5395.7   0.013       0  5578.4    0.04       0
Bank Sta=4985.3,4989.3
Exp/Cntr=0.3,0.1

Chan Stop Cuts=-1