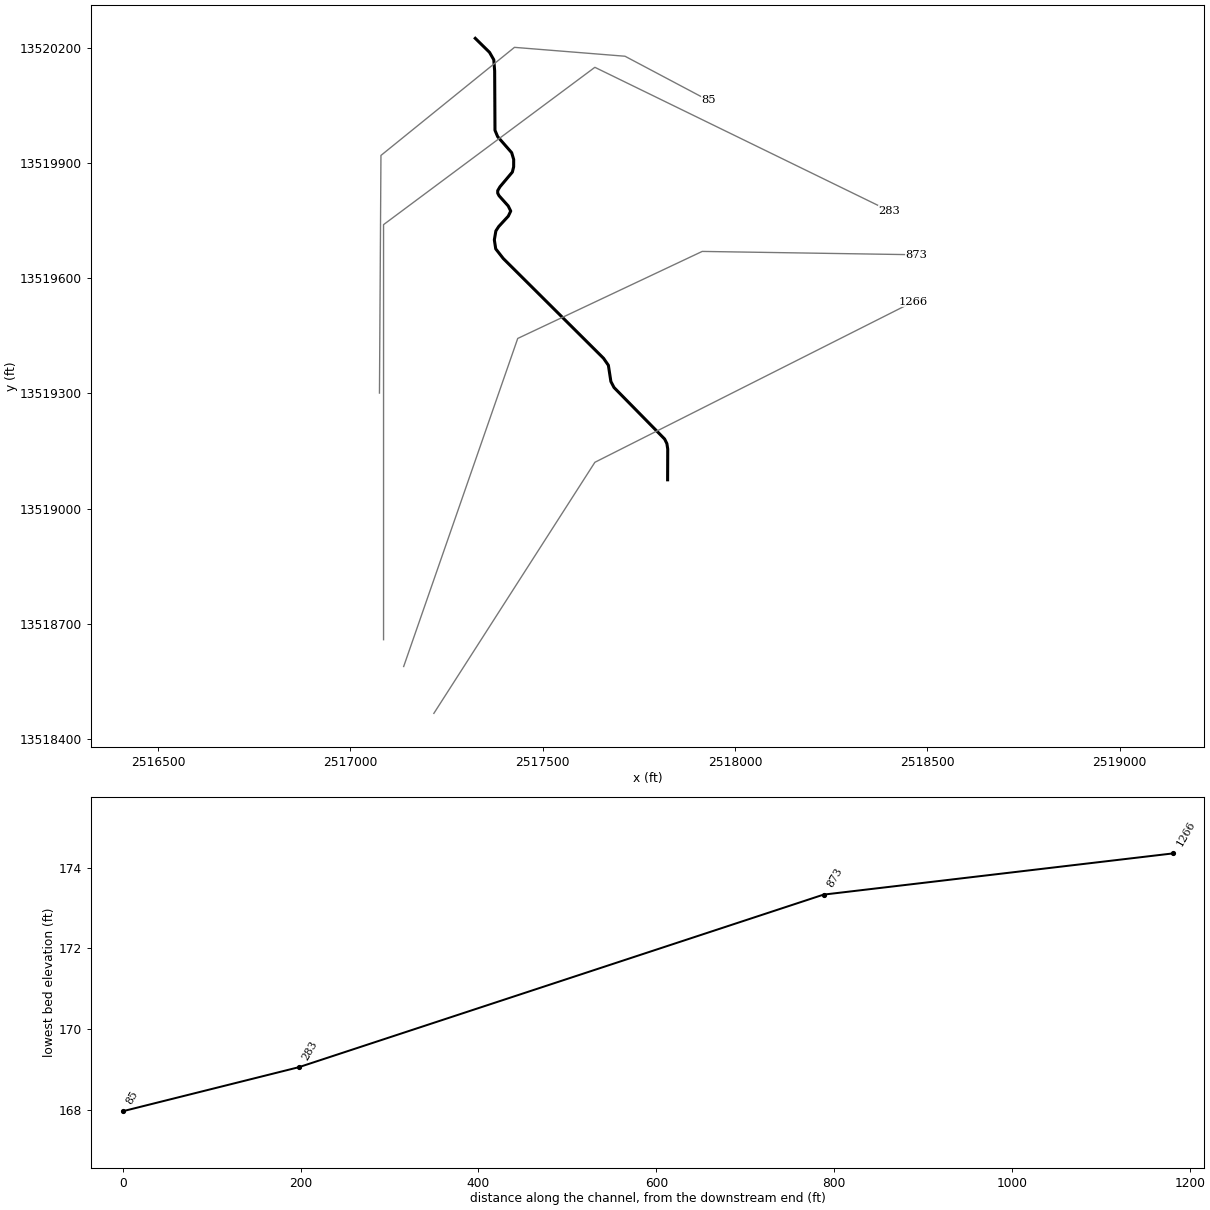
--- TRIB 7_1 TO TWELVEMILE CREEK.prj (project) ---

Proj Title=TRIB 7_1 TO TWELVEMILE CREEK Base Level Engineering
Current Plan=p01
Default Exp/Contr=0.3,0.1
English Units
Geom File=g01
Flow File=f01
Plan File=p01
BEGIN DESCRIPTION:
TRIB 7_1 TO TWELVEMILE CREEK
END DESCRIPTION:

--- TRIB 7_1 TO TWELVEMILE CREEK.p01 (plan) ---

Plan Title=Multiple Run
Short Identifier=Multiple
Geom File=g01
Flow File=f01
Subcritical Flow
K Sum by GR= 0
Std Step Tol= 0.01
Critical Tol= 0.01
Num of Std Step Trials= 20
Max Error Tol= 0.3
Flow Tol Ratio= 0.001
Split Flow NTrial= 30
Split Flow Tol= 0.02
Split Flow Ratio= 0.02
Log Output Level= 0
Friction Slope Method= 1
Unsteady Friction Slope Method= 2
Unsteady Bridges Friction Slope Method= 1
Parabolic Critical Depth
Global Vel Dist=  1 , 1 , 1
Global Log Level= 0
CheckData=True
Encroach Param= -1, 0, 0, 0
BEGIN DESCRIPTION:
Multiple Run
END DESCRIPTION:

--- TRIB 7_1 TO TWELVEMILE CREEK.f01 (steady flow) ---

Flow Title=Multiple
Number of Profiles=7
Profile Names=10-year,25-year,50-year,1pct_min,100-year,1pct_plu,500-year
River Rch & RM= TRIB 7_1 TO TWEL,Reach-1,1266
     522     822    1086     695    1386    2766    2233
Boundary for River Rch & Prof#=TRIB 7_1 TO TWEL,Reach-1,1
Up Type=0
Dn Type=3
Dn Slope=0.005
Boundary for River Rch & Prof#=TRIB 7_1 TO TWEL,Reach-1,2
Up Type=0
Dn Type=3
Dn Slope=0.005
Boundary for River Rch & Prof#=TRIB 7_1 TO TWEL,Reach-1,3
Up Type=0
Dn Type=3
Dn Slope=0.005
Boundary for River Rch & Prof#=TRIB 7_1 TO TWEL,Reach-1,4
Up Type=0
Dn Type=3
Dn Slope=0.005
Boundary for River Rch & Prof#=TRIB 7_1 TO TWEL,Reach-1,5
Up Type=0
Dn Type=3
Dn Slope=0.005
Boundary for River Rch & Prof#=TRIB 7_1 TO TWEL,Reach-1,6
Up Type=0
Dn Type=3
Dn Slope=0.005
Boundary for River Rch & Prof#=TRIB 7_1 TO TWEL,Reach-1,7
Up Type=0
Dn Type=3
Dn Slope=0.005

--- TRIB 7_1 TO TWELVEMILE CREEK.g01 (geometry) ---

Geom Title=Existing Conditions

River Reach=TRIB 7_1 TO TWEL,Reach-1
Reach XY= 30
      2517825.00     13519075.00      2517825.33     13519155.14
      2517823.14     13519169.23      2517817.26     13519181.22
      2517685.78     13519315.32      2517677.54     13519331.05
      2517671.02     13519373.35      2517658.35     13519391.67
      2517397.71     13519651.53      2517378.16     13519676.65
      2517374.59     13519700.00      2517378.56     13519723.35
      2517385.88     13519734.68      2517410.86     13519761.81
      2517417.17     13519775.08      2517410.64     13519788.37
      2517386.84     13519814.96      2517383.38     13519821.60
      2517383.32     13519828.23      2517389.14     13519838.19
      2517421.41     13519876.63      2517424.78     13519890.34
      2517424.85     13519909.58      2517419.60     13519927.17
      2517383.19     13519968.92      2517376.24     13519985.50
      2517375.41     13520140.17      2517373.11     13520169.22
      2517362.08     13520188.50      2517325.00     13520225.00

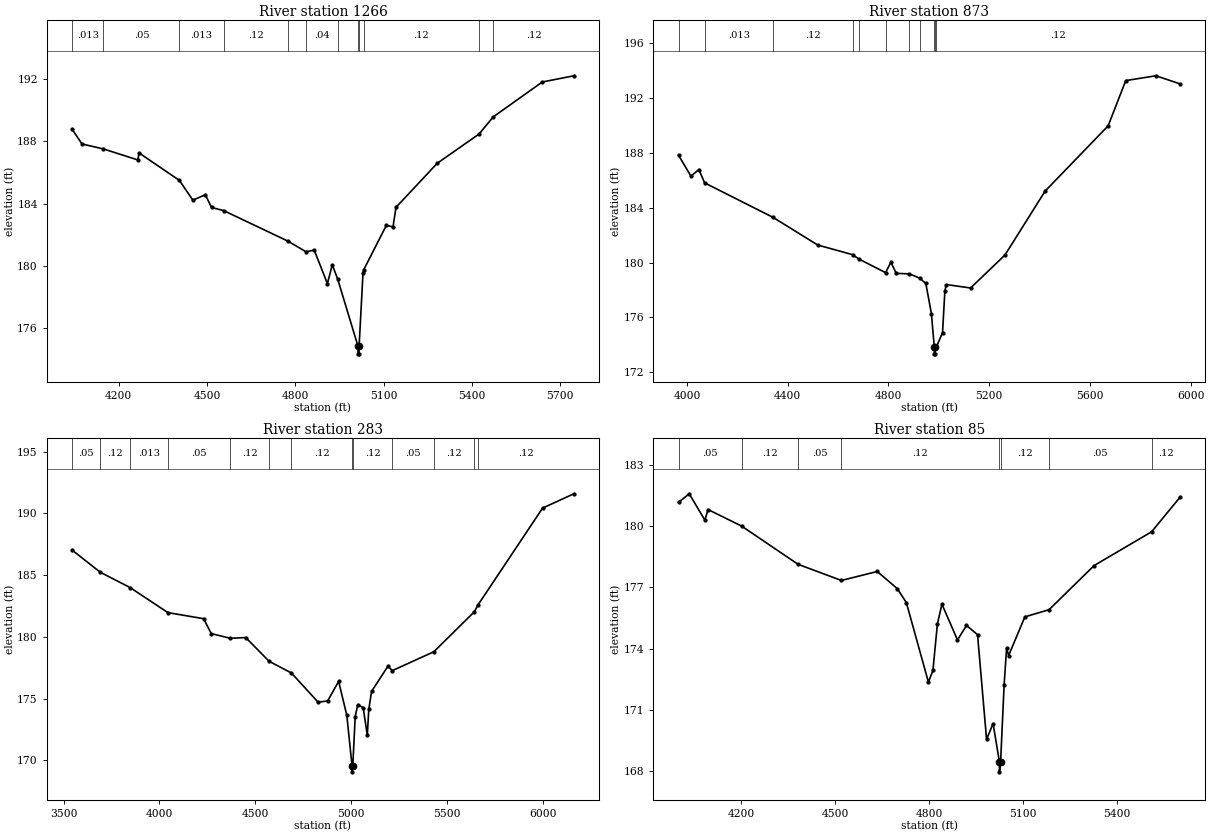
Type RM Length L Ch R = 1,1266,393,393,393
BEGIN DESCRIPTION:
LGII4558
END DESCRIPTION:
XS GIS Cut Line= 3
      2517217.35     13518466.58      2517635.92     13519120.60
      2518464.30     13519539.15
#Sta/Elev= 30
  4041.8  188.78  4075.5  187.83  4148.3  187.51  4264.4  186.81  4270.4  187.24
  4406.4  185.49  4452.2  184.22  4494.5  184.57  4515.6  183.75  4556.8  183.55
  4774.0  181.60  4836.2  180.91  4864.5  181.01  4909.1  178.86  4925.8  180.07
  4944.3  179.14  5012.9  174.85  5013.2  174.35  5016.7  174.35  5016.9  174.85
  5030.1  179.52  5032.5  179.75  5109.7  182.61  5132.0  182.50  5142.2  183.76
  5282.4  186.59  5424.5  188.47  5472.5  189.57  5639.1  191.81  5746.4  192.21
#Mann=12,-1,0
  4041.8   0.013       0  4148.3    0.05       0  4406.4   0.013       0
  4556.8    0.12       0  4774.0    0.05       0  4836.2    0.04       0
  4944.3    0.05       0  5012.9    0.05       0  5016.9    0.05       0
  5032.5    0.12       0  5424.5    0.03       0  5472.5    0.12       0
Bank Sta=5012.9,5016.9
Exp/Cntr=0.3,0.1

Type RM Length L Ch R = 1,873,590,590,590
BEGIN DESCRIPTION:
LGII4557
END DESCRIPTION:
XS GIS Cut Line= 4
      2517138.88     13518588.65      2517435.37     13519443.23
      2517914.96     13519669.94      2518471.56     13519661.25
#Sta/Elev= 30
  3966.7  187.84  4015.8  186.31  4047.5  186.79  4070.1  185.82  4341.6  183.30
  4518.9  181.28  4658.2  180.57  4683.1  180.25  4788.5  179.26  4809.6  180.02
  4830.8  179.21  4883.3  179.17  4923.8  178.86  4948.3  178.47  4970.4  176.27
  4981.8  173.83  4982.1  173.33  4985.6  173.33  4985.8  173.83  4990.6  173.85
  5014.6  174.88  5023.8  177.91  5029.4  178.39  5125.9  178.14  5262.5  180.55
  5421.8  185.22  5671.8  189.98  5741.8  193.29  5861.8  193.64  5958.4  193.04
#Mann=11,-1,0
  3966.7    0.05       0  4070.1   0.013       0  4341.6    0.12       0
  4658.2    0.05       0  4683.1    0.04       0  4788.5    0.05       0
  4883.3    0.04       0  4923.8    0.05       0  4981.8    0.05       0
  4985.8    0.05       0  4990.6    0.12       0
Bank Sta=4981.8,4985.8
Exp/Cntr=0.3,0.1

Type RM Length L Ch R = 1,283,198,198,198
BEGIN DESCRIPTION:
LGII4556
END DESCRIPTION:
XS GIS Cut Line= 4
      2517086.57     13518658.45      2517086.57     13519739.70
      2517635.92     13520149.53      2518401.67     13519775.36
#Sta/Elev= 30
  3543.8  187.03  3691.3  185.23  3846.9  183.99  4044.1  181.96  4230.3  181.47
  4270.3  180.26  4369.8  179.88  4450.3  179.94  4572.0  178.02  4688.6  177.07
  4827.6  174.71  4877.6  174.80  4935.0  176.39  4977.7  173.64  5004.9  169.56
  5005.1  169.06  5008.9  169.56  5021.5  173.53  5034.8  174.50  5063.2  174.26
  5084.7  172.03  5092.4  174.13  5107.0  175.58  5192.4  177.62  5215.0  177.26
  5431.8  178.79  5642.8  182.02  5663.5  182.61  5999.5  190.43  6162.7  191.59
#Mann=13,-1,0
  3543.8    0.05       0  3691.3    0.12       0  3846.9   0.013       0
  4044.1    0.05       0  4369.8    0.12       0  4572.0    0.05       0
  4688.6    0.12       0  5004.9    0.05       0  5008.9    0.12       0
  5215.0    0.05       0  5431.8    0.12       0  5642.8    0.05       0
  5663.5    0.12       0
Bank Sta=5004.9,5008.9
Exp/Cntr=0.3,0.1

Type RM Length L Ch R = 1,85,0,0,0
BEGIN DESCRIPTION:
4895
END DESCRIPTION:
XS GIS Cut Line= 5
      2517075.95     13519300.97      2517079.81     13519919.97
      2517426.91     13520201.51      2517714.24     13520178.37
      2517931.07     13520063.24
#Sta/Elev= 30
  4001.3  181.15  4035.3  181.57  4085.3  180.28  4095.3  180.80  4202.4  179.99
  4382.4  178.12  4520.6  177.33  4634.8  177.77  4698.8  176.93  4727.5  176.25
  4797.9  172.36  4812.3  172.93  4826.6  175.21  4841.0  176.17  4890.6  174.42
  4919.3  175.13  4954.5  174.68  4983.3  169.56  5004.1  170.33  5024.1  168.47
  5024.4  167.97  5028.1  168.47  5039.3  172.23  5047.2  174.02  5053.7  173.66
  5105.4  175.55  5182.5  175.90  5326.2  178.06  5509.4  179.71  5601.0  181.42
#Mann=8,-1,0
  4001.3    0.05       0  4202.4    0.12       0  4382.4    0.05       0
  4520.6    0.12       0  5024.1    0.05       0  5028.1    0.12       0
  5182.5    0.05       0  5509.4    0.12       0
Bank Sta=5024.1,5028.1
Exp/Cntr=0.3,0.1

Chan Stop Cuts=-1