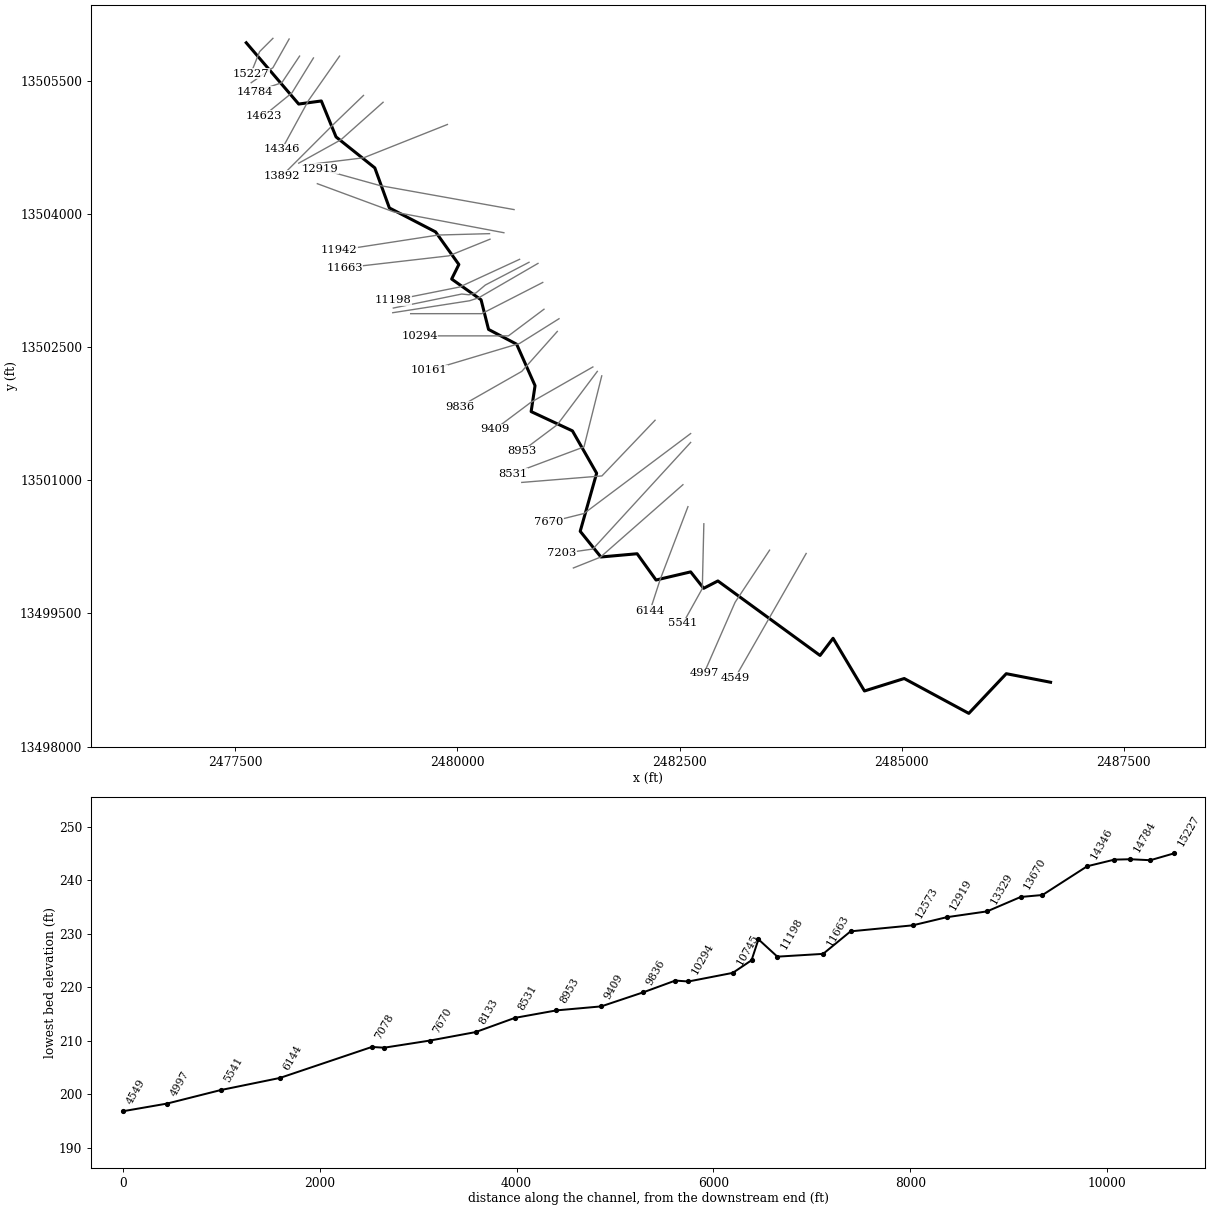
--- TRIB 8 TO EIGHTEENMILE CREEK.prj (project) ---

Proj Title=TRIB 8 TO EIGHTEENMILE CREEK Base Level Engineering
Current Plan=p01
Default Exp/Contr=0.3,0.1
English Units
Geom File=g01
Flow File=f01
Plan File=p01
Y Axis Title=Elevation
X Axis Title(PF)=Main Channel Distance
X Axis Title(XS)=Station
BEGIN DESCRIPTION:
TRIB 8 TO EIGHTEENMILE CREEK
END DESCRIPTION:
DSS Export Rating Curves= 0
DSS Export Rating Curve Sorted= 0
DSS Export Volume Flow Curves= 0
DXF OffsetX= 0
DXF OffsetY= 0
DXF ScaleX= 1
DXF ScaleY= 10

--- TRIB 8 TO EIGHTEENMILE CREEK.p01 (plan) ---

Plan Title=Multiple Run
Short Identifier=Multiple
Geom File=g01
Flow File=f01
Subcritical Flow
K Sum by GR= 0
Std Step Tol= 0.01
Critical Tol= 0.01
Num of Std Step Trials= 20
Max Error Tol= 0.3
Flow Tol Ratio= 0.001
Split Flow NTrial= 30
Split Flow Tol= 0.02
Split Flow Ratio= 0.02
Log Output Level= 0
Friction Slope Method= 1
Unsteady Friction Slope Method= 2
Unsteady Bridges Friction Slope Method= 1
Parabolic Critical Depth
Global Vel Dist=  1 , 1 , 1
Global Log Level= 0
CheckData=True
Encroach Param= -1, 0, 0, 0
BEGIN DESCRIPTION:
Multiple Run
END DESCRIPTION:

--- TRIB 8 TO EIGHTEENMILE CREEK.f01 (steady flow) ---

Flow Title=Multiple
Number of Profiles=7
Profile Names=10-year,25-year,50-year,1pct_min,100-year,1pct_plu,500-year
River Rch & RM= TRIB 8 TO EIGHTE,Reach-1,15227
     465     732     965     617    1231    2457    1981
River Rch & RM= TRIB 8 TO EIGHTE,Reach-1,14988
     538     854    1134     729    1455    2904    2370
River Rch & RM= TRIB 8 TO EIGHTE,Reach-1,12919
     860    1397    1885    1229    2451    4891    4104
River Rch & RM= TRIB 8 TO EIGHTE,Reach-1,7670
    1055    1732    2353    1543    3079    6144    5222
Boundary for River Rch & Prof#=TRIB 8 TO EIGHTE,Reach-1,1
Up Type=0
Dn Type=3
Dn Slope=0.005
Boundary for River Rch & Prof#=TRIB 8 TO EIGHTE,Reach-1,2
Up Type=0
Dn Type=3
Dn Slope=0.005
Boundary for River Rch & Prof#=TRIB 8 TO EIGHTE,Reach-1,3
Up Type=0
Dn Type=3
Dn Slope=0.005
Boundary for River Rch & Prof#=TRIB 8 TO EIGHTE,Reach-1,4
Up Type=0
Dn Type=3
Dn Slope=0.005
Boundary for River Rch & Prof#=TRIB 8 TO EIGHTE,Reach-1,5
Up Type=0
Dn Type=3
Dn Slope=0.005
Boundary for River Rch & Prof#=TRIB 8 TO EIGHTE,Reach-1,6
Up Type=0
Dn Type=3
Dn Slope=0.005
Boundary for River Rch & Prof#=TRIB 8 TO EIGHTE,Reach-1,7
Up Type=0
Dn Type=3
Dn Slope=0.005

--- TRIB 8 TO EIGHTEENMILE CREEK.g01 (geometry) ---

Geom Title=Existing Conditions
Program Version=4.10

River Reach=TRIB 8 TO EIGHTE,Reach-1
Reach XY= 30
        2477625.       13505925.        2478215.     13505235.06
      2478469.56     13505269.83      2478635.34     13504864.88
      2479071.49     13504516.52      2479235.48      13504065.2
      2479755.41     13503795.57      2480017.23     13503428.41
      2479936.07     13503264.92      2480267.19     13503031.19
      2480351.09      13502697.7      2480667.19     13502531.19
       2480874.4     13502064.38      2480830.45     13501772.53
       2481295.2     13501555.39      2481567.41     13501078.33
      2481382.53     13500424.99       2481615.2     13500135.48
      2482023.05     13500171.98       2482235.5      13499876.2
       2482625.3      13499967.8      2482771.58     13499782.76
      2482931.66     13499865.63       2484081.2     13499026.76
      2484227.51     13499220.05      2484580.89     13498626.96
      2485028.23     13498767.16      2485754.83      13498374.7
       2486176.5     13498821.53        2486675.       13498725.

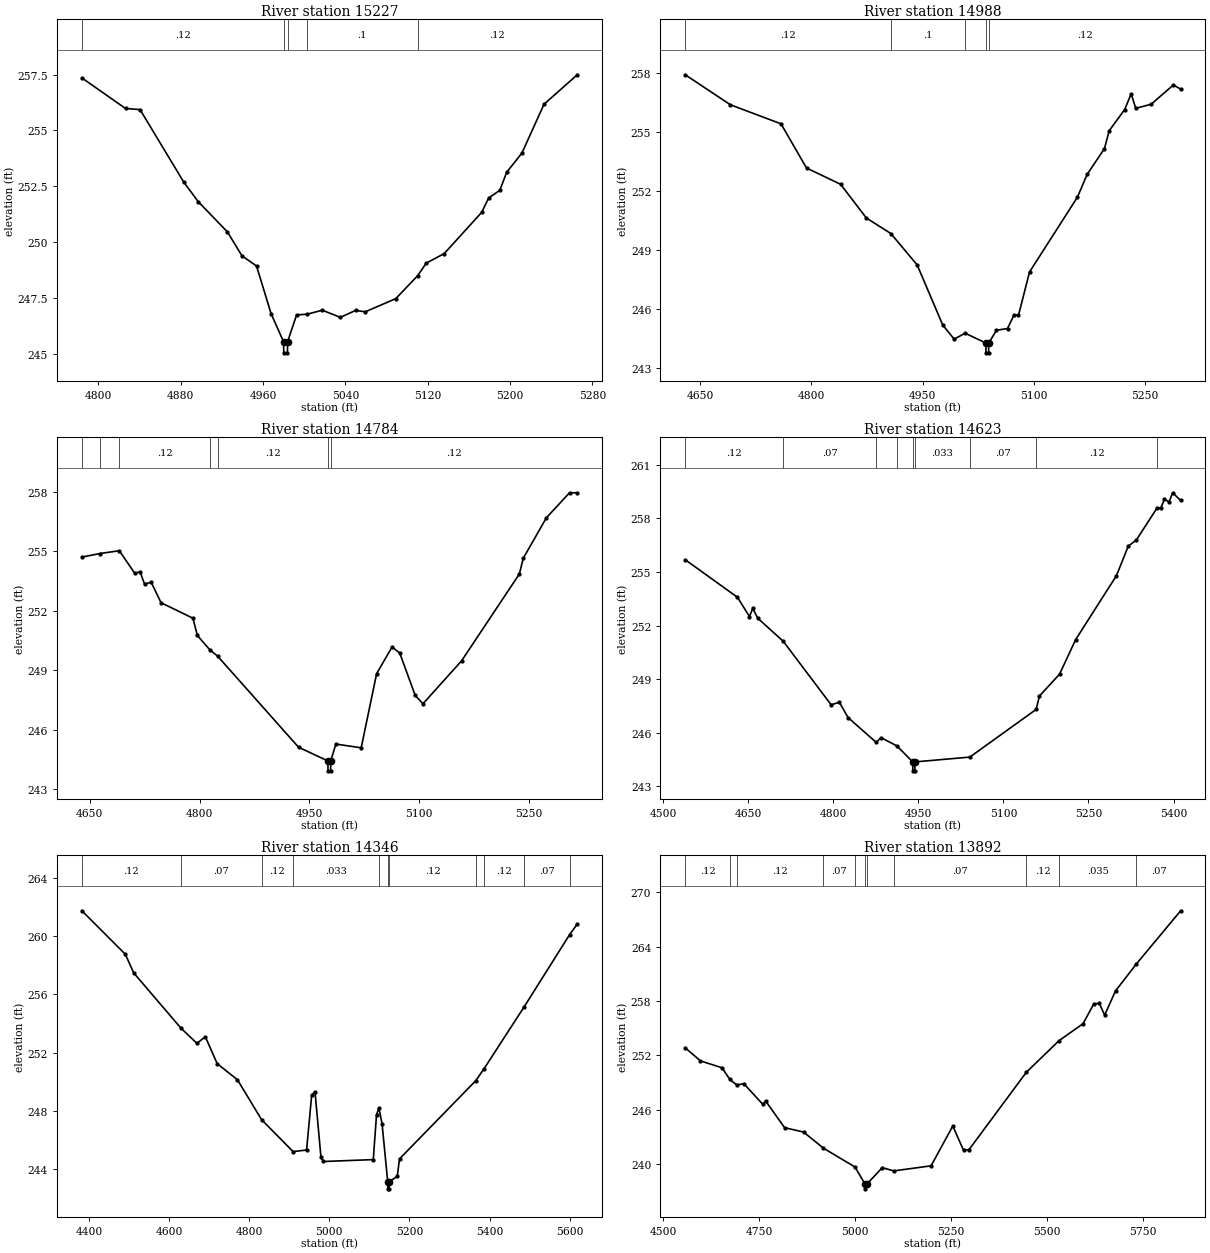
Type RM Length L Ch R = 1 ,15227   ,239,239,239
BEGIN DESCRIPTION:
TRIB 8 TO EIGHTEENMILE CREEK 28.0
END DESCRIPTION:
XS GIS Cut Line= 3
      2477924.97     13505974.97        2477775.       13505825.
      2477675.02     13505575.04
#Sta/Elev= 30
    4784  257.35  4826.4  255.98  4840.5  255.93    4883  252.68  4897.1   251.8
  4925.4  250.45  4939.5  249.38  4953.7  248.92  4967.8  246.79  4979.9  245.53
  4980.2  245.03  4983.7  245.03  4983.9  245.53  4992.6  246.73  5002.7  246.76
  5017.6  246.94  5035.1  246.62  5049.9  246.93  5059.4  246.87    5089  247.46
  5110.1  248.48  5118.6  249.05  5136.1  249.48  5172.5  251.33  5179.2  251.97
    5190  252.31  5196.7  253.12  5211.5  253.98    5233  256.17  5265.3  257.49
#Mann= 5 ,-1 , 0
    4784     .12       0  4979.9     .05       0  4983.9     .12       0
  5002.7      .1       0  5110.1     .12       0
Bank Sta=4979.9,4983.9
XS Rating Curve= 0 ,0
Exp/Cntr=0.3,0.1

Type RM Length L Ch R = 1 ,14988   ,204,204,204
BEGIN DESCRIPTION:
Mapping XS cd935fd3
END DESCRIPTION:
XS GIS Cut Line= 3
      2478107.49      13505967.5      2477925.21      13505644.6
      2477680.43     13505475.34
#Sta/Elev= 30
  4629.8  257.93  4690.8   256.4    4759  255.43  4793.4  253.18  4839.4  252.35
  4874.2  250.63  4907.2  249.84  4942.7  248.24  4977.2  245.18  4992.6  244.46
  5007.5  244.76  5035.3  244.26  5035.6  243.76  5039.1  243.76  5039.3  244.26
  5049.7  244.91  5064.6     245  5073.4  245.69  5079.4  245.67  5094.3  247.88
  5158.9  251.69    5172  252.85  5195.4  254.17  5201.8  255.08  5222.7  256.16
  5231.5  256.96  5237.6  256.22  5258.5  256.43  5288.3  257.41  5298.2   257.2
#Mann= 5 ,-1 , 0
  4629.8     .12       0  4907.2      .1       0  5007.5     .12       0
  5035.3     .05       0  5039.3     .12       0
Bank Sta=5035.3,5039.3
XS Rating Curve= 0 ,0
Exp/Cntr=0.3,0.1

Type RM Length L Ch R = 1 ,14784   ,161,161,161
BEGIN DESCRIPTION:
TRIB 8 TO EIGHTEENMILE CREEK 27.0
END DESCRIPTION:
XS GIS Cut Line= 3
        2478225.     13505775.01        2478025.       13505475.
      2477724.99       13505375.
#Sta/Elev= 30
  4639.2  254.71    4664  254.89  4690.4  255.03  4711.3   253.9  4718.8  253.96
  4724.8  253.35  4733.9  253.44  4747.4  252.41  4790.9  251.63    4797  250.76
  4813.7  250.05  4824.6  249.72  4935.2  245.13  4975.2  244.44  4975.5  243.94
    4979  243.94  4979.2  244.44  4986.2  245.29  5020.8   245.1  5041.9  248.84
    5063  250.18  5073.5  249.87  5094.6  247.74  5105.2  247.32  5157.9  249.48
  5236.9  253.86  5242.2  254.65  5273.8  256.69  5305.4  257.95    5316  257.95
#Mann= 7 ,-1 , 0
  4639.2     .12       0    4664     .07       0  4690.4     .12       0
  4813.7     .07       0  4824.6     .12       0  4975.2     .05       0
  4979.2     .12       0
Bank Sta=4975.2,4979.2
XS Rating Curve= 0 ,0
Exp/Cntr=0.3,0.1

Type RM Length L Ch R = 1 ,14623   ,277,277,277
BEGIN DESCRIPTION:
Mapping XS 92020f81
END DESCRIPTION:
XS GIS Cut Line= 3
      2478380.93     13505753.96      2478138.75     13505360.75
      2477819.23     13505100.97
#Sta/Elev= 30
  4538.9  255.69  4630.9  253.59  4652.2  252.51    4658  252.97  4666.9  252.41
  4711.6  251.13  4796.1  247.57  4810.7  247.71  4826.1  246.85  4875.8  245.46
    4884  245.73    4912  245.27    4940  244.37  4940.2  243.87  4943.7  243.87
    4944  244.37  5040.8  244.64  5157.7  247.31  5163.5  248.06  5198.9  249.28
  5227.4  251.22  5299.3   254.8  5320.1  256.45  5334.5   256.8  5371.3  258.61
  5377.6  258.59    5384  259.09    5392  258.92  5398.4  259.44  5412.5  259.01
#Mann= 9 ,-1 , 0
  4538.9     .12       0  4711.6     .07       0  4875.8     .12       0
    4912    .033       0    4940    .033       0    4944    .033       0
  5040.8     .07       0  5157.7     .12       0  5371.3     .07       0
Bank Sta=4940,4944
XS Rating Curve= 0 ,0
Exp/Cntr=0.3,0.1

Type RM Length L Ch R = 1 ,14346   ,454,454,454
BEGIN DESCRIPTION:
TRIB 8 TO EIGHTEENMILE CREEK 26.0
END DESCRIPTION:
XS GIS Cut Line= 3
      2478674.98     13505774.98        2478325.       13505275.
        2478025.       13504725.
#Sta/Elev= 30
  4382.2  261.75  4490.7  258.76  4511.6  257.48  4629.2  253.69  4669.5  252.63
  4690.4  253.09    4720  251.24  4770.6  250.13  4830.8  247.39  4909.5  245.19
  4943.2   245.3  4955.9  249.07  4964.2  249.32    4979  244.83  4985.1  244.51
  5109.7  244.64  5117.8  247.72  5123.8  248.19  5131.6  247.12  5145.7  243.13
    5146  242.63  5149.5  242.63  5149.7  243.13  5169.5  243.48  5175.2  244.69
  5365.7  250.07  5386.5   250.9  5485.8  255.12  5599.9  260.11    5619  260.84
#Mann= 11 ,-1 , 0
  4382.2     .12       0  4629.2     .07       0  4830.8     .12       0
  4909.5    .033       0  5123.8     .12       0  5145.7    .033       0
  5149.7     .12       0  5365.7     .07       0  5386.5     .12       0
  5485.8     .07       0  5599.9    .035       0
Bank Sta=5145.7,5149.7
XS Rating Curve= 0 ,0
Exp/Cntr=0.3,0.1

Type RM Length L Ch R = 1 ,13892   ,222,222,222
BEGIN DESCRIPTION:
TRIB 8 TO EIGHTEENMILE CREEK 25.0
END DESCRIPTION:
XS GIS Cut Line= 3
      2478943.99     13505331.96        2478625.       13505025.
      2478025.02     13504425.02
#Sta/Elev= 30
  4557.9  252.82  4597.6  251.38  4653.9  250.62  4674.1  249.33  4692.3  248.72
  4710.5  248.87  4760.2  246.58  4767.1  246.98  4816.8  244.01  4866.2  243.53
  4918.1  241.75  5000.3  239.67  5026.9  237.76  5027.1  237.26  5030.9  237.76
  5071.3   239.6  5101.3  239.24  5198.6   239.8  5255.2  244.19  5283.4   241.5
  5297.6  241.59  5446.6  250.11  5531.9  253.61  5594.6  255.48  5622.9  257.68
    5637  257.72  5651.1  256.44  5679.4  259.11  5733.5  262.07  5849.1  267.95
#Mann= 11 ,-1 , 0
  4557.9     .12       0  4674.1     .07       0  4692.3     .12       0
  4918.1     .07       0  5000.3     .12       0  5026.9     .05       0
  5030.9     .12       0  5101.3     .07       0  5446.6     .12       0
  5531.9    .035       0  5733.5     .07       0
Bank Sta=5026.9,5030.9
XS Rating Curve= 0 ,0
Exp/Cntr=0.3,0.1

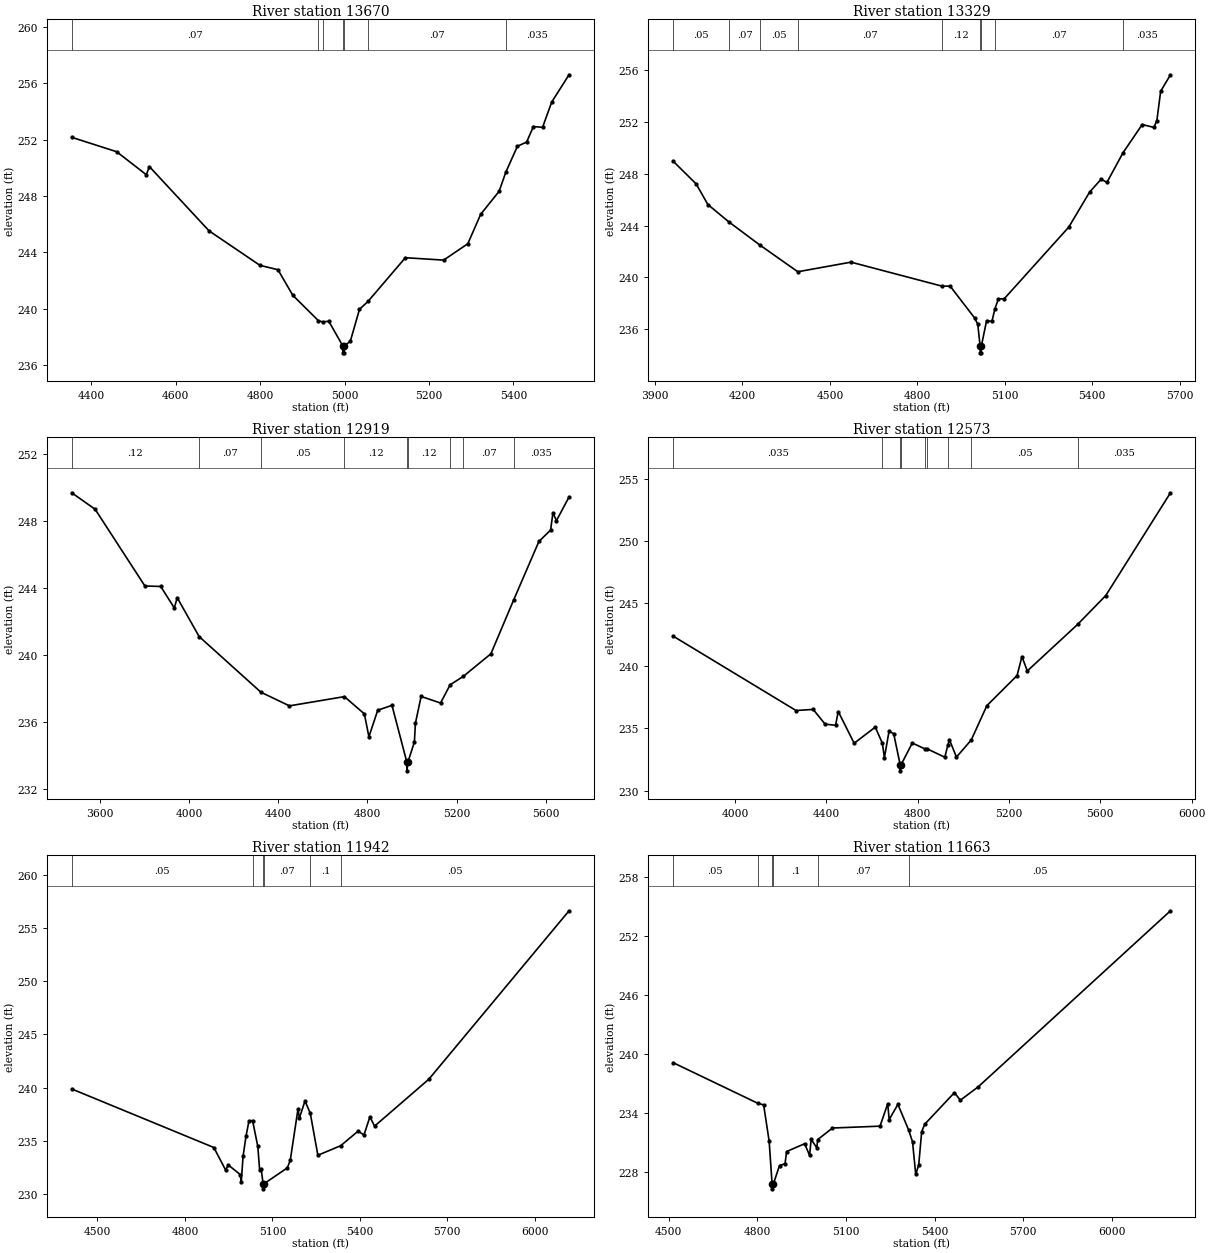
Type RM Length L Ch R = 1 ,13670   ,341,341,341
BEGIN DESCRIPTION:
Mapping XS 667b1ad0
END DESCRIPTION:
XS GIS Cut Line= 3
      2479164.48     13505255.13      2478690.49     13504833.23
      2478215.36     13504569.46
#Sta/Elev= 30
  4353.8  252.16  4460.2  251.14  4530.4  249.51  4537.9  250.08  4679.2  245.53
  4799.6  243.09  4842.3  242.78  4877.4  240.97  4938.1  239.17  4948.2  239.08
  4962.7  239.13  4995.7  237.39  4995.9  236.89  4999.4  236.89  4999.7  237.39
  5013.7  237.71  5035.4  239.97  5055.8  240.54  5144.1  243.63  5234.8  243.46
    5292  244.62  5322.6  246.71  5366.1  248.33  5382.2   249.7  5409.6  251.53
  5431.3  251.82  5447.3  252.92  5469.1  252.87  5490.8  254.66  5531.8  256.59
#Mann= 7 ,-1 , 0
  4353.8     .07       0  4938.1     .12       0  4948.2      .1       0
  4995.7     .05       0  4999.7      .1       0  5055.8     .07       0
  5382.2    .035       0
Bank Sta=4995.7,4999.7
XS Rating Curve= 0 ,0
Exp/Cntr=0.3,0.1

Type RM Length L Ch R = 1 ,13329   ,410,410,410
BEGIN DESCRIPTION:
Mapping XS b1f86266
END DESCRIPTION:
XS GIS Cut Line= 3
      2479888.36     13505005.09      2478945.69      13504630.1
      2478258.68     13504545.63
#Sta/Elev= 30
    3962  248.95    4041   247.2  4081.3  245.61  4154.8  244.25  4259.4   242.5
  4389.8  240.44  4572.3  241.18  4883.4  239.34  4912.7  239.33  4997.4  236.86
  5007.4  236.39  5015.5   234.7  5015.8   234.2  5019.3   234.2  5019.5   234.7
  5037.7  236.68    5056  236.62    5066  237.57    5078  238.35  5098.1  238.36
  5319.8  243.88  5391.2  246.57  5430.6  247.56  5450.7  247.32  5505.6  249.59
  5571.7  251.77    5612  251.55    5622  252.08    5635  254.33  5668.7   255.6
#Mann= 9 ,-1 , 0
    3962     .05       0  4154.8     .07       0  4259.4     .05       0
  4389.8     .07       0  4883.4     .12       0  5015.5     .05       0
  5019.5     .12       0    5066     .07       0  5505.6    .035       0
Bank Sta=5015.5,5019.5
XS Rating Curve= 0 ,0
Exp/Cntr=0.3,0.1

Type RM Length L Ch R = 1 ,12919   ,346,346,346
BEGIN DESCRIPTION:
Mapping XS 72b8b948
END DESCRIPTION:
XS GIS Cut Line= 3
      2480638.39     13504046.77      2479127.99      13504317.6
      2478455.22     13504505.11
#Sta/Elev= 30
  3472.3  249.67  3577.3  248.69  3800.8  244.12    3872  244.09  3932.9  242.81
    3946  243.42  4044.2  241.11  4321.9  237.79  4449.9  236.98  4696.6  237.53
  4786.3   236.5  4806.6  235.14  4846.3  236.72  4910.2  237.01  4977.3  233.61
  4977.6  233.11  4981.3  233.61  5010.9  234.83  5015.4  235.94    5041  237.54
  5128.4  237.15  5171.1  238.23  5230.8  238.74  5354.3  240.08    5456  243.27
  5569.9  246.77  5622.4  247.45  5632.8  248.47  5648.6  248.01  5705.2  249.42
#Mann= 9 ,-1 , 0
  3472.3     .12       0  4044.2     .07       0  4321.9     .05       0
  4696.6     .12       0  4977.3     .05       0  4981.3     .12       0
  5171.1    .035       0  5230.8     .07       0    5456    .035       0
Bank Sta=4977.3,4981.3
XS Rating Curve= 0 ,0
Exp/Cntr=0.3,0.1

Type RM Length L Ch R = 1 ,12573   ,631,631,631
BEGIN DESCRIPTION:
Mapping XS 7c1495a2
END DESCRIPTION:
XS GIS Cut Line= 3
      2480523.86     13503786.35      2479284.24     13504020.73
      2478424.87     13504338.43
#Sta/Elev= 30
  3729.4  242.38  4267.6  236.42  4342.6  236.51  4394.9  235.33  4440.6  235.24
  4452.4  236.34  4522.1   233.8  4614.5  235.09  4645.7   233.8  4654.4  232.64
  4674.7  234.75  4695.1  234.57  4723.5  232.09  4723.8  231.59  4727.7  232.09
  4776.7  233.82  4831.4  233.35  4840.8  233.36    4919  232.68    4932  233.63
  4939.3  234.08  4969.9  232.69  5034.8  234.06  5103.2  236.81  5235.4  239.22
  5256.7  240.74  5280.3  239.59  5500.8  243.32  5623.9  245.63  5907.2  253.86
#Mann= 9 ,-1 , 0
  3729.4    .035       0  4645.7      .1       0  4723.5     .05       0
  4727.7      .1       0  4831.4     .05       0  4840.8    .035       0
    4932      .1       0  5034.8     .05       0  5500.8    .035       0
Bank Sta=4723.5,4727.7
XS Rating Curve= 0 ,0
Exp/Cntr=0.3,0.1

Type RM Length L Ch R = 1 ,11942   ,279,279,279
BEGIN DESCRIPTION:
Mapping XS 780d579f
END DESCRIPTION:
XS GIS Cut Line= 3
      2480362.36     13503775.94      2479784.24     13503760.31
      2478669.84     13503588.47
#Sta/Elev= 30
  4411.6  239.87  4899.1  234.36  4939.1  232.26  4949.2   232.7  4989.9  231.81
  4993.1  231.08  4999.3  233.52  5009.4  235.42  5019.5  236.85  5031.9   236.9
  5049.9  234.46  5056.3   232.2  5061.3  232.37    5068  230.97  5068.3  230.47
  5072.3  230.97  5151.1  232.44  5161.2  233.15  5187.6  237.95  5192.7  237.15
  5211.8  238.74    5230  237.57  5255.9  233.63  5334.3  234.53  5393.9   235.9
  5414.1  235.54  5434.4  237.25  5450.4  236.37  5636.7  240.79  6117.5  256.64
#Mann= 6 ,-1 , 0
  4411.6     .05       0  5031.9     .07       0    5068     .05       0
  5072.3     .07       0    5230      .1       0  5334.3     .05       0
Bank Sta=5068,5072.3
XS Rating Curve= 0 ,0
Exp/Cntr=0.3,0.1

Type RM Length L Ch R = 1 ,11663   ,465,465,465
BEGIN DESCRIPTION:
Mapping XS b5ce3b53
END DESCRIPTION:
XS GIS Cut Line= 3
      2480367.53     13503713.42      2479904.03     13503525.94
      2478728.47      13503390.7
#Sta/Elev= 30
  4515.1   239.1  4800.7  234.98  4821.4   234.8  4840.1   231.1    4850  226.76
  4850.3  226.26  4854.4  226.76  4875.1  228.63  4893.8  228.82  4899.2  230.06
  4960.1  230.85  4976.9  229.67  4982.3  231.29  5001.1  230.45  5004.7  231.28
  5054.4  232.45  5215.4  232.64  5241.3  234.92  5246.3  233.31  5275.8  234.86
  5311.9  232.27  5325.3  231.05  5336.2  227.72  5346.3  228.71  5356.3  232.07
  5366.4  232.83  5467.1  236.05  5487.2  235.28  5547.6  236.64  6198.4  254.56
#Mann= 6 ,-1 , 0
  4515.1     .05       0  4800.7      .1       0    4850     .05       0
  4854.4      .1       0  5004.7     .07       0  5311.9     .05       0
Bank Sta=4850,4854.4
XS Rating Curve= 0 ,0
Exp/Cntr=0.3,0.1

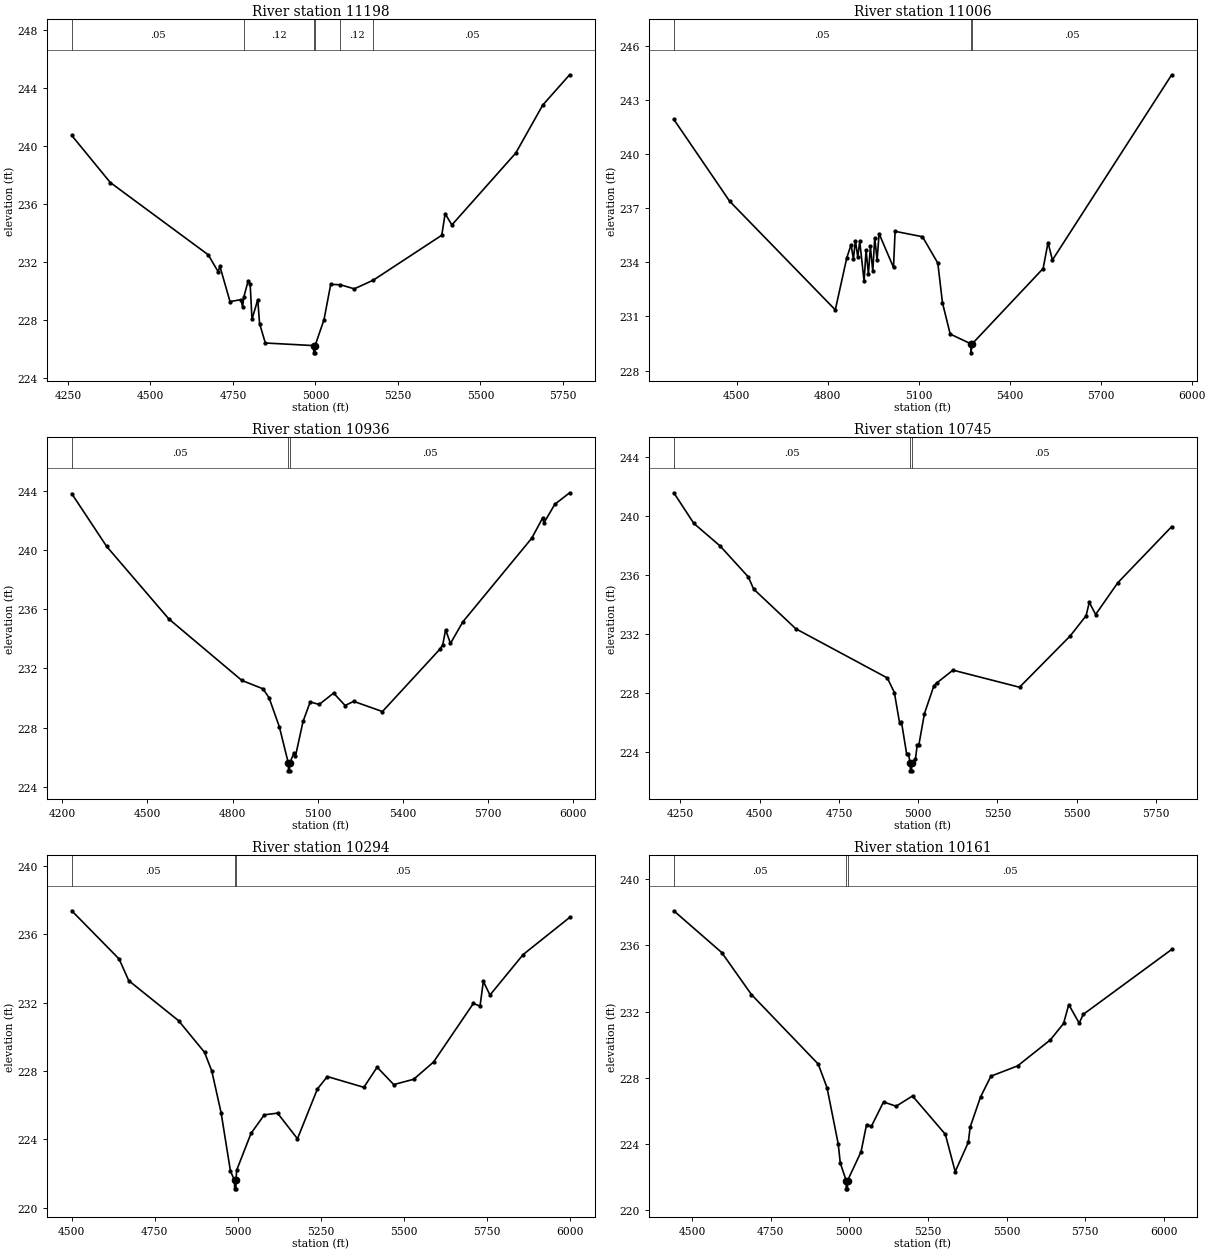
Type RM Length L Ch R = 1 ,11198   ,192,192,192
BEGIN DESCRIPTION:
TRIB 8 TO EIGHTEENMILE CREEK 19.0
END DESCRIPTION:
XS GIS Cut Line= 3
      2480700.47     13503486.88        2480025.       13503175.
      2479275.05     13503025.01
#Sta/Elev= 30
  4261.7  240.75  4378.5   237.5  4675.3  232.51  4705.1  231.35  4710.7  231.71
  4741.3  229.28    4774  229.41  4779.5  228.93  4783.3  229.61  4796.4  230.72
  4802.4  230.47  4807.9  228.06  4825.4  229.41  4830.9  227.76  4848.3  226.42
  4994.8  226.24  4995.1  225.74  4998.9  225.74  4999.2  226.24  5026.1  228.03
  5046.5  230.47  5075.9  230.44  5117.9  230.16  5175.6  230.76    5383  233.86
  5393.2  235.35  5413.6  234.57  5607.4  239.54    5689  242.85  5770.5  244.94
#Mann= 6 ,-1 , 0
  4261.7     .05       0  4783.3     .12       0  4994.8     .05       0
  4999.2     .12       0  5075.9     .12       0  5175.6     .05       0
Bank Sta=4994.8,4999.2
XS Rating Curve= 0 ,0
Exp/Cntr=0.3,0.1

Type RM Length L Ch R = 1 ,11006   ,70,70,70
BEGIN DESCRIPTION:
Mapping XS e3487c5c
END DESCRIPTION:
XS GIS Cut Line= 6
      2480806.63     13503453.63      2480314.43     13503197.02
      2480209.26     13503108.67      2480131.44     13503087.64
       2480049.4     13503096.05      2479279.81     13502938.35
#Sta/Elev= 30
  4293.1  241.91  4477.5  237.37  4825.4  231.36  4863.1  234.23  4877.4  234.97
  4885.1  234.17  4891.7  235.19  4899.4  234.29    4906  235.15  4920.3  232.94
  4926.8  234.67  4934.6  233.34  4941.1  234.87  4948.9   233.5  4955.4  235.35
  4963.2  234.11  4969.7  235.58  5017.3  233.71  5022.5  235.71  5112.8  235.41
  5163.3  233.95  5178.7  231.75  5204.1  230.02  5272.2  229.48  5272.5  228.98
  5276.7  229.48  5510.4  233.65  5526.6  235.09    5541  234.12  5934.2  244.38
#Mann= 3 ,-1 , 0
  4293.1     .05       0  5272.2     .05       0  5276.7     .05       0
Bank Sta=5272.2,5276.7
XS Rating Curve= 0 ,0
Exp/Cntr=0.3,0.1

Type RM Length L Ch R = 1 ,10936   ,191,191,191
BEGIN DESCRIPTION:
Mapping XS 19b2bc90
END DESCRIPTION:
XS GIS Cut Line= 4
      2480907.63     13503441.03      2480240.81     13503053.98
      2480137.75     13503020.33       2479273.2      13502885.7
#Sta/Elev= 30
  4233.3  243.82  4356.3  240.25  4575.7  235.34  4832.4  231.19  4906.9  230.62
  4928.4  230.02  4964.8  228.05  4996.7  225.57    4997  225.07  5000.9  225.07
  5001.2  225.57  5016.4   226.3  5021.7  226.07  5048.3  228.41  5073.5  229.73
  5105.1  229.56    5156  230.33  5196.5  229.49  5226.8  229.77    5328  229.08
  5530.5   233.3  5540.6   233.6  5550.7  234.61  5567.8  233.69  5611.4  235.15
  5854.3  240.81  5892.3  242.17  5897.3  241.85  5935.3   243.1  5987.7  243.88
#Mann= 3 ,-1 , 0
  4233.3     .05       0  4996.7     .05       0  5001.2     .05       0
Bank Sta=4996.7,5001.2
XS Rating Curve= 0 ,0
Exp/Cntr=0.3,0.1

Type RM Length L Ch R = 1 ,10745   ,451,451,451
BEGIN DESCRIPTION:
TRIB 8 TO EIGHTEENMILE CREEK 18.0
END DESCRIPTION:
XS GIS Cut Line= 3
      2480960.89     13503226.46        2480275.       13502875.
        2479475.       13502875.
#Sta/Elev= 30
  4228.9   241.6  4292.1  239.52  4375.3  237.98  4464.1  235.88  4480.7  235.06
  4613.9  232.36  4902.5  229.02  4924.7  228.03  4941.3  225.95  4946.9  226.06
  4963.5  223.85  4969.1  223.85  4974.9  223.21  4975.2  222.71  4979.1  222.71
  4979.4  223.21  4991.3  223.51  4996.8  224.49  5002.1  224.49  5019.6   226.6
  5049.6   228.5  5059.6   228.7  5109.6  229.55  5319.6  228.39  5479.6  231.88
  5529.6  233.25  5539.6  234.16  5559.6  233.33  5629.6  235.49  5799.6   239.3
#Mann= 3 ,-1 , 0
  4228.9     .05       0  4974.9     .05       0  4979.4     .05       0
Bank Sta=4974.9,4979.4
XS Rating Curve= 0 ,0
Exp/Cntr=0.3,0.1

Type RM Length L Ch R = 1 ,10294   ,133,133,133
BEGIN DESCRIPTION:
TRIB 8 TO EIGHTEENMILE CREEK 17.0
END DESCRIPTION:
XS GIS Cut Line= 3
      2480974.97     13502924.98        2480575.       13502625.
      2479574.96       13502625.
#Sta/Elev= 30
  4500.3  237.37    4643  234.55  4672.1  233.28  4822.1  230.94  4900.3  229.09
  4922.1     228  4950.3  225.55  4978.4  222.14  4990.7   221.6    4991   221.1
  4994.9   221.1  4995.2   221.6  4997.1  222.19  5040.3  224.34  5080.3  225.43
  5120.3  225.53  5180.3  224.03  5240.3  226.94  5270.3  227.67  5380.3  227.04
  5420.3  228.22  5470.3   227.2  5530.3  227.51  5590.3  228.52  5710.3  231.95
  5730.3  231.79  5740.3  233.24  5760.3  232.44  5860.3  234.81  6000.3  236.98
#Mann= 3 ,-1 , 0
  4500.3     .05       0  4990.7     .05       0  4995.2     .05       0
Bank Sta=4990.7,4995.2
XS Rating Curve= 0 ,0
Exp/Cntr=0.3,0.1

Type RM Length L Ch R = 1 ,10161   ,325,325,325
BEGIN DESCRIPTION:
Mapping XS 63fc7438
END DESCRIPTION:
XS GIS Cut Line= 3
      2481143.99     13502818.04      2480701.29     13502540.27
      2479685.68     13502236.46
#Sta/Elev= 30
  4442.4   238.1  4594.9  235.57  4689.2  233.03  4901.6  228.82  4929.5  227.39
    4965  223.99  4971.6  222.84  4990.2  221.77  4990.5  221.27  4994.4  221.27
  4994.8  221.77  5037.6  223.51  5055.1  225.16  5070.7  225.06    5109  226.53
    5149  226.27  5201.2  226.89  5305.6  224.57  5336.9  222.31  5378.7  224.09
  5384.3     225  5417.4  226.83  5450.5  228.09  5535.2  228.71  5639.6  230.29
  5681.4  231.28  5697.9  232.42    5731   231.3    5744  231.83  6025.1  235.76
#Mann= 3 ,-1 , 0
  4442.4     .05       0  4990.2     .05       0  4994.8     .05       0
Bank Sta=4990.2,4994.8
XS Rating Curve= 0 ,0
Exp/Cntr=0.3,0.1

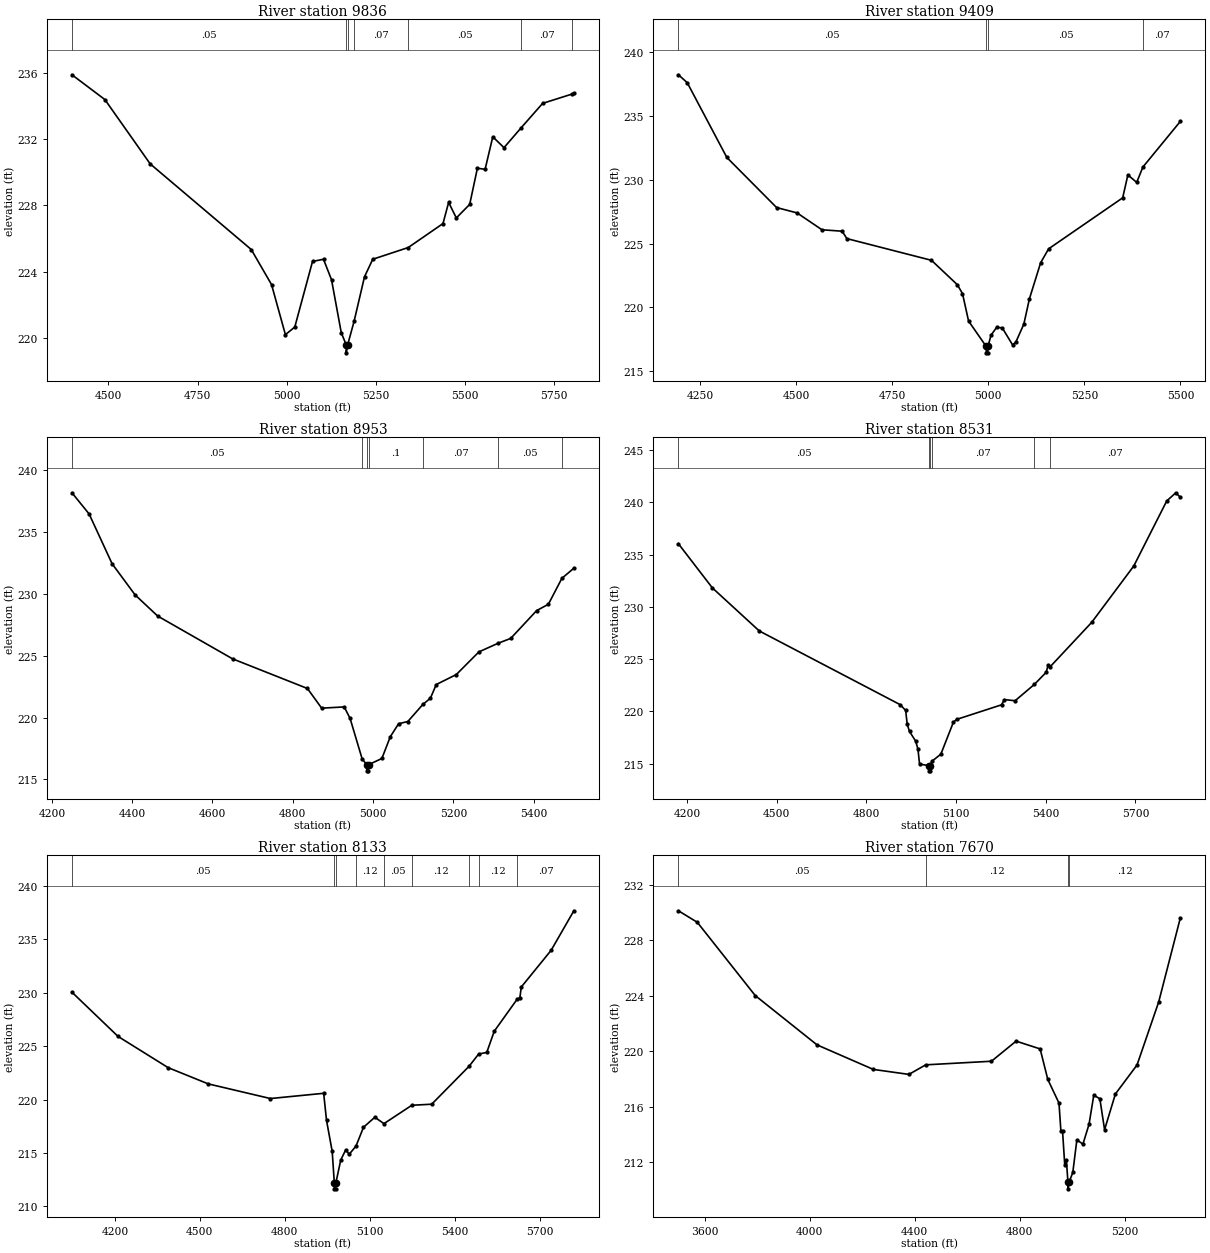
Type RM Length L Ch R = 1 ,9836    ,427,427,427
BEGIN DESCRIPTION:
TRIB 8 TO EIGHTEENMILE CREEK 16.0
END DESCRIPTION:
XS GIS Cut Line= 3
      2481125.02     13502675.02        2480725.       13502225.
      2480024.69     13501826.21
#Sta/Elev= 30
  4397.6   235.9    4490   234.4  4617.1  230.51  4900.6  225.33  4957.5  223.21
  4996.4  220.18  5022.7  220.64  5072.5  224.61  5103.3  224.74  5125.8   223.5
  5153.2  220.29  5166.7  219.58  5167.1  219.08  5171.3  219.58    5189  220.98
  5218.3  223.68  5241.4  224.74    5341  225.45  5438.5   226.9  5454.3  228.18
  5475.9  227.24  5513.4  228.06    5535  230.25  5556.6  230.18  5578.2  232.15
  5609.6  231.49  5656.4  232.66    5718  234.17  5801.4  234.74  5805.6  234.78
#Mann= 7 ,-1 , 0
  4397.6     .05       0  5166.7     .05       0  5171.3     .05       0
    5189     .07       0    5341     .05       0  5656.4     .07       0
  5801.4     .05       0
Bank Sta=5166.7,5171.3
XS Rating Curve= 0 ,0
Exp/Cntr=0.3,0.1

Type RM Length L Ch R = 1 ,9409    ,456,456,456
BEGIN DESCRIPTION:
TRIB 8 TO EIGHTEENMILE CREEK 15.0
END DESCRIPTION:
XS GIS Cut Line= 3
      2481524.98     13502274.99        2480825.       13501875.
      2480425.01       13501575.
#Sta/Elev= 30
  4193.6  238.21  4216.6  237.59  4319.6  231.74  4449.1  227.82  4502.4   227.4
  4567.2  226.08  4619.7  225.97    4632  225.39  4852.2  223.69  4919.2  221.79
  4932.9  221.09  4948.7  218.94  4994.6  216.95  4994.9  216.45  4998.9  216.45
  4999.3  216.95  5007.1  217.83  5021.7  218.44  5036.3  218.41  5063.3  217.07
  5071.7  217.29  5092.5  218.69  5107.1  220.68  5136.3   223.5  5157.1  224.59
  5349.8  228.58  5363.3  230.37  5386.3  229.79  5402.4  230.99  5499.8  234.56
#Mann= 4 ,-1 , 0
  4193.6     .05       0  4994.6     .05       0  4999.3     .05       0
  5402.4     .07       0
Bank Sta=4994.6,4999.3
XS Rating Curve= 0 ,0
Exp/Cntr=0.3,0.1

Type RM Length L Ch R = 1 ,8953    ,422,422,422
BEGIN DESCRIPTION:
TRIB 8 TO EIGHTEENMILE CREEK 14.0
END DESCRIPTION:
XS GIS Cut Line= 3
        2481575.     13502224.99        2481125.       13501625.
      2480724.99       13501325.
#Sta/Elev= 30
    4250  238.19  4292.7  236.48    4350  232.45  4407.3  229.93  4463.5  228.22
    4650  224.76  4836.5  222.36  4871.9  220.77  4928.1  220.87  4942.7  219.94
  4972.7  216.67    4984   216.2  4984.4   215.7  4988.5   215.7  4988.9   216.2
  5021.9   216.7  5042.7  218.45  5063.5  219.51  5086.5  219.69  5124.2  221.08
  5142.7  221.57  5157.3  222.68  5207.3  223.49  5263.5  225.32  5311.4  226.02
  5342.7  226.41  5407.3  228.66  5436.5  229.17  5470.2  231.27    5500  232.09
#Mann= 7 ,-1 , 0
    4250     .05       0  4972.7      .1       0    4984     .05       0
  4988.9      .1       0  5124.2     .07       0  5311.4     .05       0
  5470.2     .07       0
Bank Sta=4984,4988.9
XS Rating Curve= 0 ,0
Exp/Cntr=0.3,0.1

Type RM Length L Ch R = 1 ,8531    ,398,398,398
BEGIN DESCRIPTION:
TRIB 8 TO EIGHTEENMILE CREEK 13.0
END DESCRIPTION:
XS GIS Cut Line= 3
        2481625.       13502175.        2481425.       13501375.
      2480625.02     13501075.01
#Sta/Elev= 30
  4171.3  236.04  4284.7  231.82  4441.9  227.69  4913.5  220.63  4931.5  220.08
  4936.7  218.75  4944.4  218.07    4965  217.14  4972.7  216.37  4977.9  214.95
  5008.6   214.8    5009   214.3  5013.2   214.3  5013.5   214.8  5019.6  215.22
  5049.3   215.9  5091.2  218.96  5102.7  219.23  5252.2  220.62    5262  221.12
  5297.6  221.01  5361.9  222.57  5401.8  223.74    5408  224.43  5415.4  224.28
    5554  228.52  5694.6  233.91  5804.9  240.14  5835.2  240.92  5850.3  240.49
#Mann= 6 ,-1 , 0
  4171.3     .05       0  5008.6     .05       0  5013.5     .05       0
  5019.6     .07       0  5361.9     .12       0  5415.4     .07       0
Bank Sta=5008.6,5013.5
XS Rating Curve= 0 ,0
Exp/Cntr=0.3,0.1

Type RM Length L Ch R = 1 ,8133    ,463,463,463
BEGIN DESCRIPTION:
TRIB 8 TO EIGHTEENMILE CREEK 12.0
END DESCRIPTION:
XS GIS Cut Line= 3
        2482225.       13501675.      2481627.03     13501048.25
      2480725.05       13500975.
#Sta/Elev= 30
  4048.7  230.05  4211.5  225.91  4388.2  222.99  4529.8  221.47    4749   220.1
    4937  220.59  4947.1  218.05  4967.1  215.16  4974.7  212.15  4975.1  211.65
  4979.3  211.65  4979.6  212.15  4997.2  214.34  5014.6  215.29  5027.3  214.89
  5051.3  215.66  5077.5  217.41  5117.6  218.35  5149.7  217.75  5248.1  219.47
  5318.3  219.57  5450.2  223.12  5484.1  224.27  5512.5  224.41    5539   226.4
  5619.4  229.38  5629.3  229.52  5634.5  230.54  5739.7  233.97  5819.9  237.67
#Mann= 9 ,-1 , 0
  4048.7     .05       0  4974.7     .05       0  4979.6     .05       0
  5051.3     .12       0  5149.7     .05       0  5248.1     .12       0
  5450.2     .07       0  5484.1     .12       0  5619.4     .07       0
Bank Sta=4974.7,4979.6
XS Rating Curve= 0 ,0
Exp/Cntr=0.3,0.1

Type RM Length L Ch R = 1 ,7670    ,467,467,467
BEGIN DESCRIPTION:
TRIB 8 TO EIGHTEENMILE CREEK 11.0
END DESCRIPTION:
XS GIS Cut Line= 3
      2482625.02     13501525.02        2481425.       13500625.
      2481025.04     13500525.01
#Sta/Elev= 30
    3500  230.14  3571.9  229.31  3792.7  224.02  4028.2  220.46  4242.7  218.69
  4378.2  218.33  4442.2  219.02  4692.7  219.28  4786.5  220.73  4878.2  220.17
  4907.3  217.97    4950  216.26  4957.3  214.24  4963.6  214.23  4971.9  211.81
  4978.2  212.15    4984  210.57  4984.4  210.07    4989  210.57  5002.6  211.25
  5018.1   213.6  5041.3   213.3  5064.5  214.73  5082.5  216.82  5105.7  216.58
  5123.7  214.34    5165  216.92  5247.4  219.01  5329.9  223.56  5412.3  229.62
#Mann= 4 ,-1 , 0
    3500     .05       0  4442.2     .12       0    4984     .05       0
    4989     .12       0
Bank Sta=4984,4989
XS Rating Curve= 0 ,0
Exp/Cntr=0.3,0.1

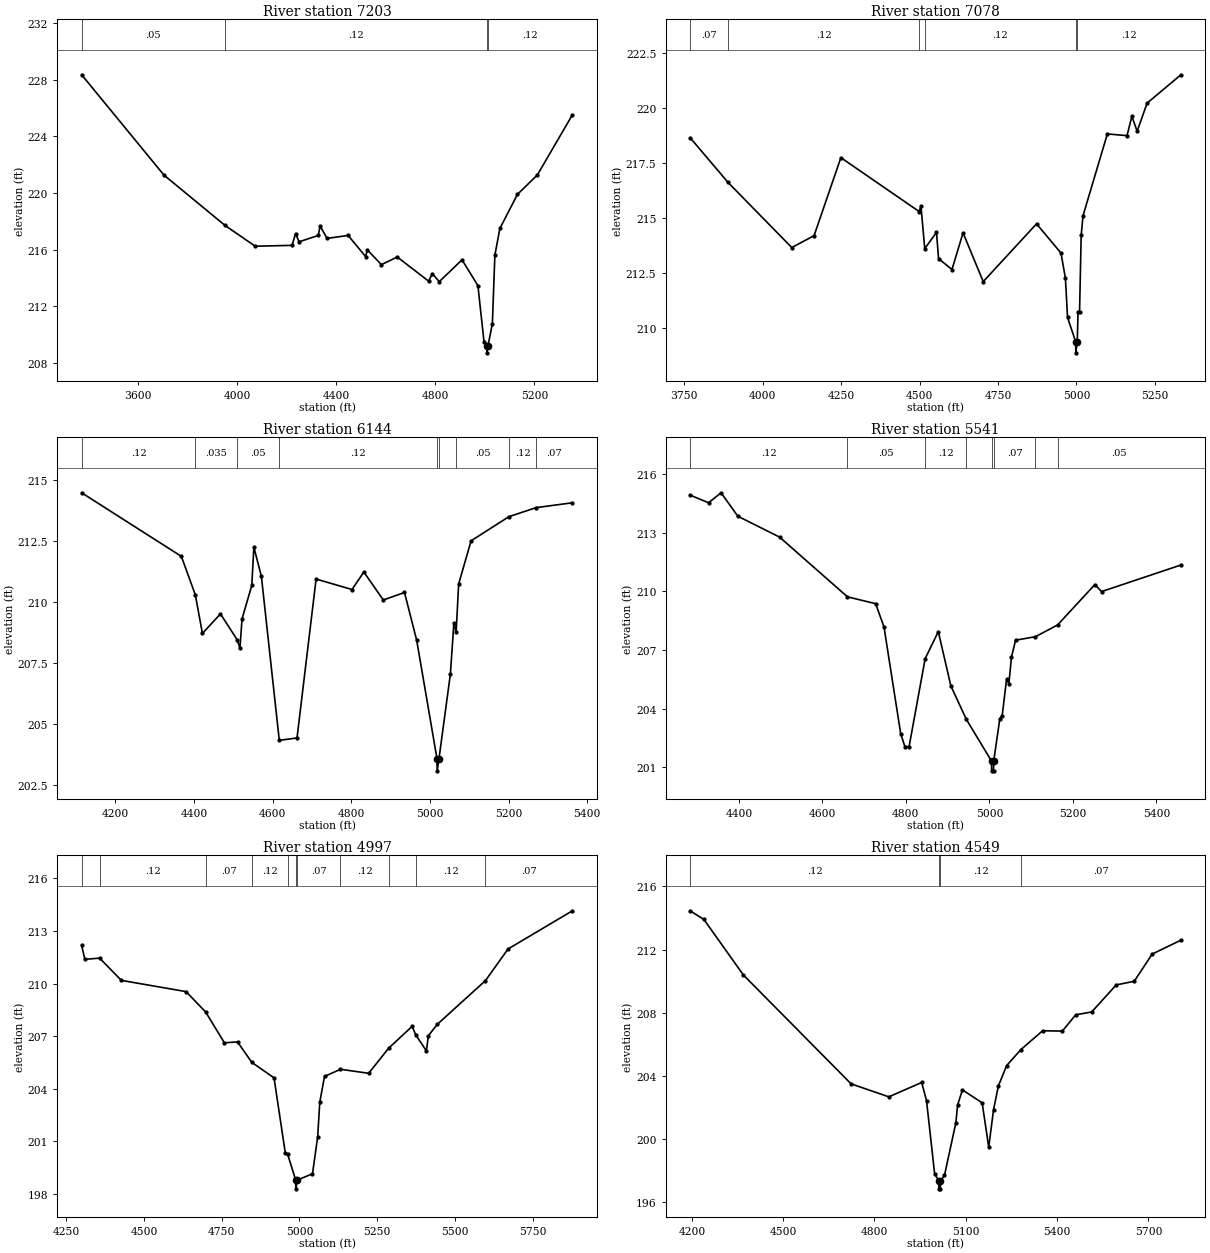
Type RM Length L Ch R = 1 ,7203    ,125,125,125
BEGIN DESCRIPTION:
TRIB 8 TO EIGHTEENMILE CREEK 10.0
END DESCRIPTION:
XS GIS Cut Line= 3
      2482624.98     13501424.98        2481525.       13500225.
      2481175.01       13500175.
#Sta/Elev= 30
  3372.1  228.34  3704.7  221.26  3950.7  217.72  4072.9  216.25  4221.5  216.31
  4235.7  217.14  4249.8  216.56  4327.5  217.01  4334.9  217.68  4362.7   216.8
  4447.8  217.01  4518.7  215.52  4525.5  215.99  4582.2  214.95  4646.3  215.49
  4773.3  213.78  4787.5  214.32  4815.9  213.75  4907.8  215.29  4971.9  213.47
  4996.6  209.51  5007.6  209.23  5007.9  208.73  5012.6  209.23  5030.3  210.79
  5040.4  215.62  5060.6   217.5  5131.3   219.9  5212.1  221.28  5353.5  225.52
#Mann= 4 ,-1 , 0
  3372.1     .05       0  3950.7     .12       0  5007.6     .05       0
  5012.6     .12       0
Bank Sta=5007.6,5012.6
XS Rating Curve= 0 ,0
Exp/Cntr=0.3,0.1

Type RM Length L Ch R = 1 ,7078    ,934,934,934
BEGIN DESCRIPTION:
Mapping XS 1bb611bf
END DESCRIPTION:
XS GIS Cut Line= 3
      2482538.32     13500949.33      2481609.48     13500133.34
      2481305.64      13500011.8
#Sta/Elev= 30
    3769  218.66  3889.4  216.63  4092.9  213.66    4164   214.2  4249.4  217.75
  4498.6   215.3  4504.6  215.54  4516.6  213.61    4554  214.35  4560.6  213.16
  4603.3  212.66  4638.6  214.33  4702.9  212.11  4872.8  214.74  4950.6  213.41
  4964.8  212.26  4971.5  210.48  4997.5  209.37  4997.8  208.87  5002.5  209.37
    5005  210.74  5009.8  210.74    5015  214.22  5020.9  215.11  5098.4  218.83
    5161  218.75  5176.5  219.63  5193.3  218.95    5225  220.23  5332.6  221.52
#Mann= 6 ,-1 , 0
    3769     .07       0  3889.4     .12       0  4498.6    .035       0
  4516.6     .12       0  4997.5     .05       0  5002.5     .12       0
Bank Sta=4997.5,5002.5
XS Rating Curve= 0 ,0
Exp/Cntr=0.3,0.1

Type RM Length L Ch R = 1 ,6144    ,603,603,603
BEGIN DESCRIPTION:
Mapping XS 50ffa541
END DESCRIPTION:
XS GIS Cut Line= 3
      2482594.87     13500701.91      2482282.22      13499881.6
      2482167.78     13499530.03
#Sta/Elev= 30
  4114.8  214.49  4368.3  211.88  4403.8   210.3  4421.8  208.72  4467.7  209.52
  4510.5  208.45  4517.2  208.11  4522.5  209.31  4547.3  210.69  4552.6  212.26
  4571.7  211.06  4617.2  204.33  4662.3  204.43  4710.8  210.95  4802.1  210.52
  4832.1  211.24  4881.6  210.09  4935.5   210.4  4966.6  208.43  5018.1  203.58
  5018.5  203.08  5023.2  203.58  5052.2  207.06    5061  209.14  5066.8  208.77
  5073.2  210.75  5104.8  212.52  5201.1  213.51  5269.9  213.88  5362.4  214.08
#Mann= 9 ,-1 , 0
  4114.8     .12       0  4403.8    .035       0  4510.5     .05       0
  4617.2     .12       0  5018.1     .05       0  5023.2     .12       0
  5066.8     .05       0  5201.1     .12       0  5269.9     .07       0
Bank Sta=5018.1,5023.2
XS Rating Curve= 0 ,0
Exp/Cntr=0.3,0.1

Type RM Length L Ch R = 1 ,5541    ,544,544,544
BEGIN DESCRIPTION:
Mapping XS 01e508ad
END DESCRIPTION:
XS GIS Cut Line= 3
      2482773.69     13500509.24      2482756.33     13499780.04
      2482539.83     13499390.34
#Sta/Elev= 30
  4283.3  214.93  4327.5  214.54  4357.6  215.05  4397.6  213.85  4497.6  212.78
  4660.2  209.72  4727.7  209.37  4747.7  208.17  4787.7   202.7  4797.7  202.05
  4807.7  202.05  4846.2  206.56  4877.7  207.94  4907.7  205.16  4944.9  203.44
  5005.1  201.31  5005.5  200.81  5009.9  200.81  5010.4  201.31    5025  203.49
  5030.7  203.64    5041  205.49  5046.7  205.28  5052.8  206.63  5062.7   207.5
  5110.3  207.68  5163.2  208.28  5252.6  210.35  5268.6  209.99  5458.5  211.35
#Mann= 8 ,-1 , 0
  4283.3     .12       0  4660.2     .05       0  4846.2     .12       0
  4944.9     .07       0  5005.1     .05       0  5010.4     .07       0
  5110.3     .12       0  5163.2     .05       0
Bank Sta=5005.1,5010.4
XS Rating Curve= 0 ,0
Exp/Cntr=0.3,0.1

Type RM Length L Ch R = 1 ,4997    ,448,448,448
BEGIN DESCRIPTION:
TRIB 8 TO EIGHTEENMILE CREEK 5.0
END DESCRIPTION:
XS GIS Cut Line= 3
      2483513.26     13500212.32        2483125.       13499625.
      2482774.99     13498824.97
#Sta/Elev= 30
  4299.9  212.17  4310.2  211.38  4357.6  211.45  4427.6  210.18  4635.3  209.54
  4698.3  208.38  4758.7  206.62  4800.8  206.67    4847   205.5  4918.2  204.62
  4954.3  200.35  4961.8  200.27  4987.8  198.79  4988.2  198.29  4993.1  198.79
  5041.8  199.15  5058.5  201.26  5065.2  203.23  5080.4   204.7  5131.7  205.11
  5222.3  204.88    5287  206.32  5362.2  207.56  5373.3  207.08  5407.8  206.16
  5414.4  207.03  5443.3  207.68  5597.8  210.17  5670.2  211.97  5877.2  214.15
#Mann= 11 ,-1 , 0
  4299.9    .035       0  4357.6     .12       0  4698.3     .07       0
    4847     .12       0  4961.8     .07       0  4987.8     .05       0
  4993.1     .07       0  5131.7     .12       0    5287     .07       0
  5373.3     .12       0  5597.8     .07       0
Bank Sta=4987.8,4993.1
XS Rating Curve= 0 ,0
Exp/Cntr=0.3,0.1

Type RM Length L Ch R = 1 ,4549    ,416,416,416
BEGIN DESCRIPTION:
TRIB 8 TO EIGHTEENMILE CREEK 4.0
END DESCRIPTION:
XS GIS Cut Line= 3
      2483925.02     13500175.04        2483525.       13499475.
        2483125.       13498775.
#Sta/Elev= 30
  4194.2  214.45  4239.6   213.9  4369.2  210.39  4723.3   203.5  4847.1  202.68
  4955.1  203.59    4971  202.44  4997.6  197.82  5011.5  197.36  5011.9  196.86
  5016.4  196.86  5016.8  197.36    5030  197.71  5067.4  201.04  5073.2  202.17
    5089  203.12  5153.8   202.3  5175.4  199.49  5191.2  201.87  5207.1  203.37
  5234.4  204.66  5281.1  205.67  5352.5  206.86  5417.3  206.84  5461.2  207.87
  5513.7  208.05  5594.3  209.76  5653.4  209.99  5712.4  211.71  5806.7  212.59
#Mann= 4 ,-1 , 0
  4194.2     .12       0  5011.5     .05       0  5016.8     .12       0
  5281.1     .07       0
Bank Sta=5011.5,5016.8
XS Rating Curve= 0 ,0
Exp/Cntr=0.3,0.1