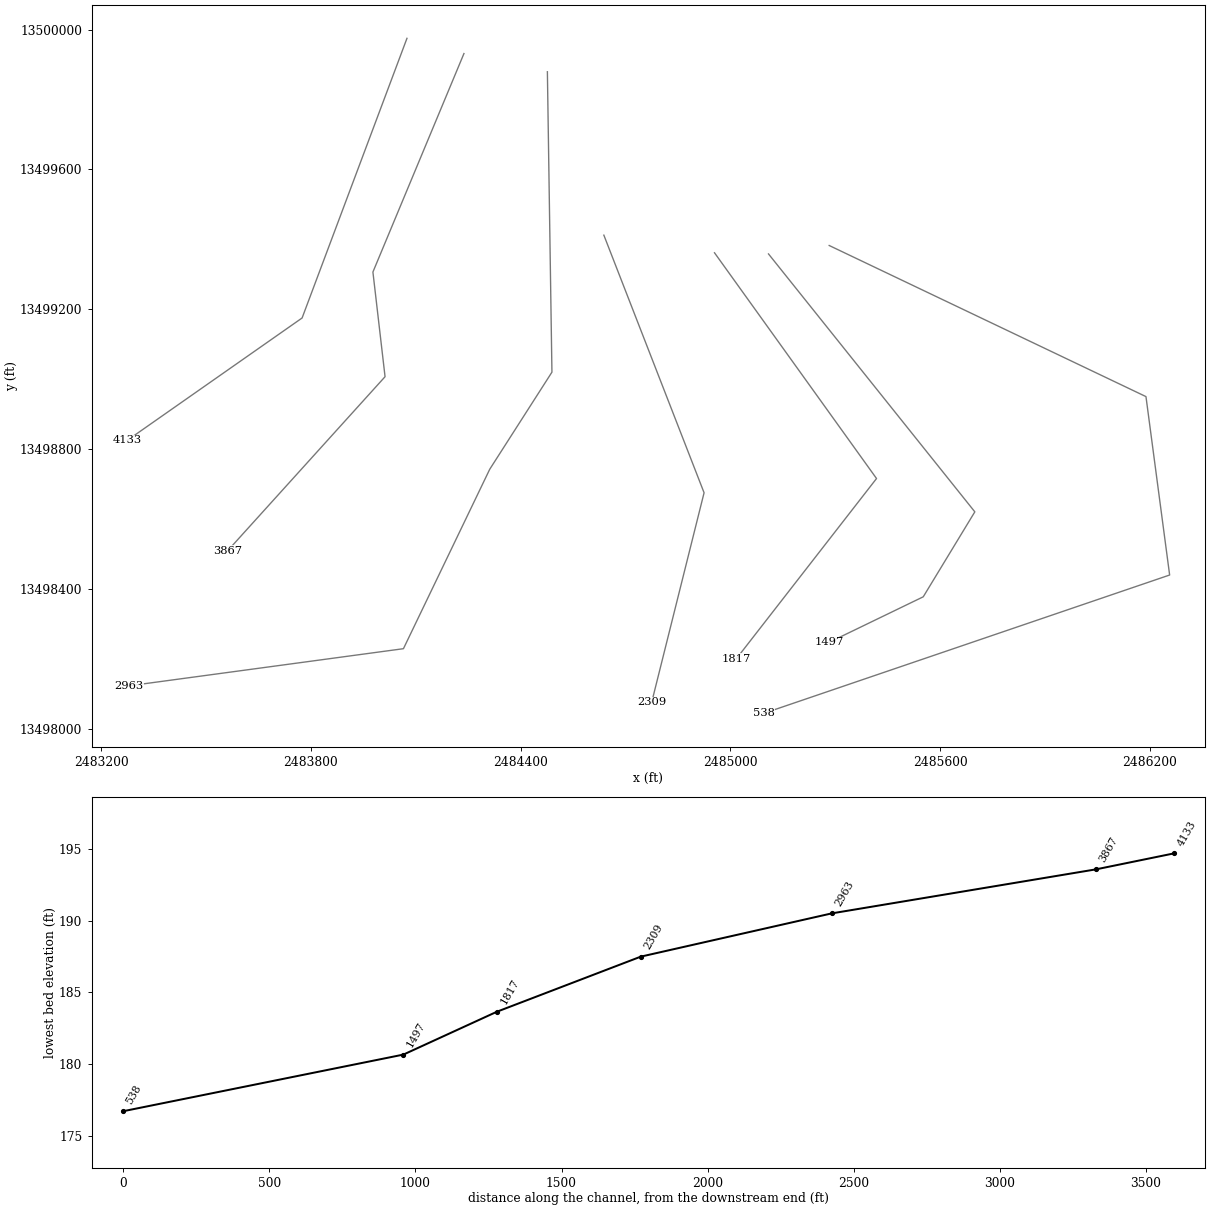
HEC-RAS study TRIB 8 TO EIGHTEENMILE CREEK.prj: TRIB 8 TO EIGHTEENMILE CREEK Base Level Engineering

--- TRIB 8 TO EIGHTEENMILE CREEK.g01 (geometry) --- (continued)

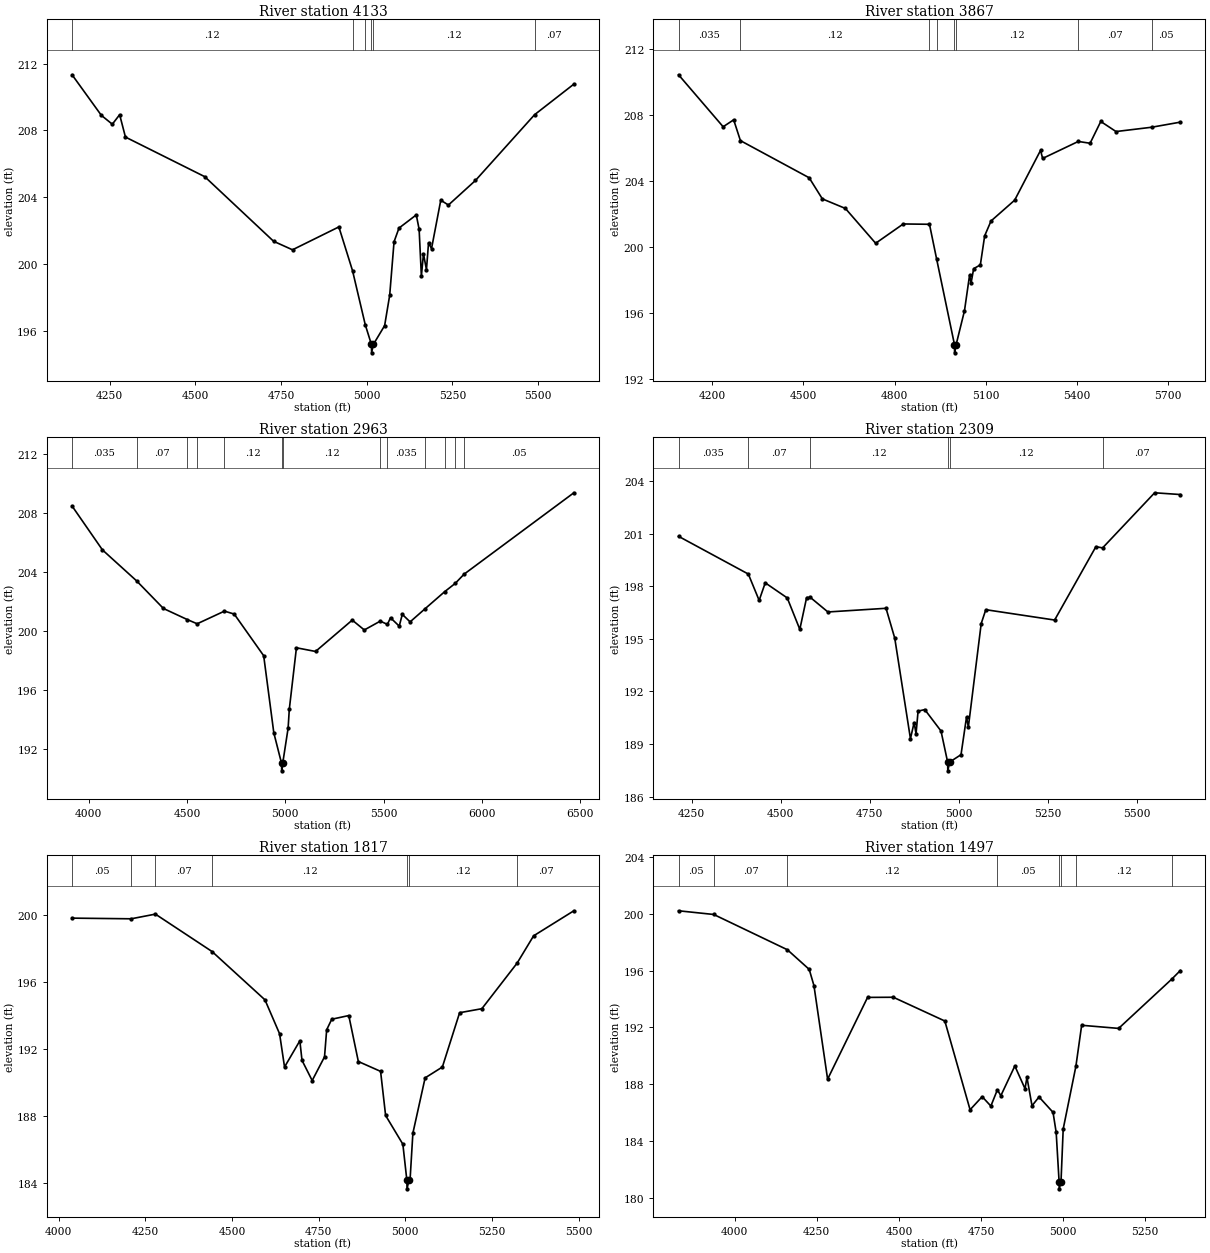
Type RM Length L Ch R = 1 ,4133    ,266,266,266
BEGIN DESCRIPTION:
TRIB 8 TO EIGHTEENMILE CREEK 3.0
END DESCRIPTION:
XS GIS Cut Line= 3
      2484075.01     13499975.04        2483775.       13499175.
      2483274.98     13498824.98
#Sta/Elev= 30
  4139.9  211.33  4225.4   208.9  4257.4  208.37  4278.8  208.94  4295.7   207.6
  4527.1  205.23  4728.2  201.36  4783.4  200.85  4918.7  202.22  4958.6   199.6
  4995.8  196.36  5013.8  195.18  5014.3  194.68  5019.3  195.18  5052.3  196.31
  5067.1  198.13  5079.8  201.33  5094.2  202.15  5144.7  202.94    5153  202.08
  5159.6  199.28  5165.7  200.61  5174.4  199.66  5180.5  201.27  5189.2  200.92
  5216.2  203.82  5238.5  203.53  5317.4     205  5490.1  208.94  5604.7  210.77
#Mann= 6 ,-1 , 0
  4139.9     .12       0  4958.6     .07       0  4995.8     .12       0
  5013.8     .05       0  5019.3     .12       0  5490.1     .07       0
Bank Sta=5013.8,5019.3
XS Rating Curve= 0 ,0
Exp/Cntr=0.3,0.1

Type RM Length L Ch R = 1 ,3867    ,904,904,904
BEGIN DESCRIPTION:
Mapping XS e8cbe32d
END DESCRIPTION:
XS GIS Cut Line= 4
      2484238.02      13499931.5      2483977.59     13499306.48
      2484012.32       13499007.      2483561.91     13498508.95
#Sta/Elev= 30
  4089.4  210.42  4236.1  207.27  4270.7  207.69  4292.9  206.43  4518.9  204.18
  4562.3   202.9  4638.1  202.32  4737.6  200.21  4828.4  201.38  4914.6  201.36
  4938.4  199.23  4996.8  194.07  4997.2  193.57  5002.3  194.07  5029.7  196.12
  5046.4  198.27  5051.4   197.8  5059.9  198.67  5081.9   198.9  5096.1  200.66
    5117  201.56  5194.7  202.82  5279.9  205.84  5286.7  205.35    5404  206.38
  5442.8  206.27  5477.9  207.59    5528  206.98  5644.9  207.24  5739.5  207.55
#Mann= 8 ,-1 , 0
  4089.4    .035       0  4292.9     .12       0  4914.6     .07       0
  4938.4     .12       0  4996.8     .05       0  5002.3     .12       0
    5404     .07       0  5644.9     .05       0
Bank Sta=4996.8,5002.3
XS Rating Curve= 0 ,0
Exp/Cntr=0.3,0.1

Type RM Length L Ch R = 1 ,2963    ,654,654,654
BEGIN DESCRIPTION:
Mapping XS d061d947
END DESCRIPTION:
XS GIS Cut Line= 5
      2484476.73     13499879.41      2484489.75     13499020.02
       2484311.8     13498742.25      2484064.92     13498228.89
      2483279.68     13498122.65
#Sta/Elev= 30
  3915.9  208.49  4070.3  205.51  4243.7  203.41  4380.4  201.53  4501.2  200.78
    4552  200.49  4690.7  201.35  4740.4  201.15  4890.2  198.32  4941.7  193.08
  4981.2     191  4981.7   190.5  4986.8     191  5014.4   193.4  5020.4  194.68
  5056.7  198.86  5153.9  198.61  5340.5  200.74  5401.8  200.07  5482.9  200.67
  5519.3  200.45    5535   200.9  5579.4  200.33    5595  201.13  5634.7  200.62
  5711.5  201.52  5810.3  202.67  5864.6  203.24  5909.1  203.86  6467.3  209.39
#Mann= 13 ,-1 , 0
  3915.9    .035       0  4243.7     .07       0  4501.2    .035       0
    4552     .07       0  4690.7     .12       0  4981.2     .05       0
  4986.8     .12       0  5482.9     .07       0  5519.3    .035       0
  5711.5     .07       0  5810.3     .05       0  5864.6     .07       0
  5909.1     .05       0
Bank Sta=4981.2,4986.8
XS Rating Curve= 0 ,0
Exp/Cntr=0.3,0.1

Type RM Length L Ch R = 1 ,2309    ,492,492,492
BEGIN DESCRIPTION:
TRIB 8 TO EIGHTEENMILE CREEK 2.0
END DESCRIPTION:
XS GIS Cut Line= 3
      2484638.29     13499411.95        2484925.       13498675.
      2484775.01     13498075.02
#Sta/Elev= 30
  4213.1  200.84  4409.1  198.69  4439.5  197.19  4456.6  198.19  4518.4  197.33
  4553.7  195.54  4572.8  197.35  4583.2  197.36  4632.6  196.53  4795.8  196.74
  4820.3  195.04  4864.4  189.31  4874.7  190.23  4880.1  189.59  4885.8  190.88
  4904.6  190.97  4950.2  189.75  4968.8  187.98  4969.3  187.48  4974.5  187.98
  5006.4   188.4  5021.9  190.55    5027  189.97  5063.1  195.87    5076  196.66
  5269.3  196.07  5385.2  200.25    5404  200.18  5550.2  203.32  5622.3  203.22
#Mann= 6 ,-1 , 0
  4213.1    .035       0  4409.1     .07       0  4583.2     .12       0
  4968.8     .05       0  4974.5     .12       0    5404     .07       0
Bank Sta=4968.8,4974.5
XS Rating Curve= 0 ,0
Exp/Cntr=0.3,0.1

Type RM Length L Ch R = 1 ,1817    ,320,320,320
BEGIN DESCRIPTION:
Mapping XS d2d87ae7
END DESCRIPTION:
XS GIS Cut Line= 3
      2484954.84     13499361.53      2485418.37     13498715.71
      2485017.31     13498200.07
#Sta/Elev= 30
  4038.1  199.84  4208.7   199.8  4278.6  200.08  4442.2  197.84  4594.8  194.95
    4637  192.92  4651.3  190.93  4695.5   192.5  4701.7  191.33  4731.1  190.12
  4766.7  191.54  4772.9  193.16  4787.6  193.79  4836.7  194.01  4864.3  191.26
  4928.5  190.67    4943  188.03  4992.8  186.31  5004.4  184.14  5004.8  183.64
  5010.2  184.14  5013.6  184.19  5021.7  186.97    5057  190.28  5106.8  190.93
  5156.6  194.18  5220.8  194.42  5322.6  197.15  5370.1  198.78  5486.3  200.28
#Mann= 7 ,-1 , 0
  4038.1     .05       0  4208.7     .12       0  4278.6     .07       0
  4442.2     .12       0  5004.4     .05       0  5010.2     .12       0
  5322.6     .07       0
Bank Sta=5004.4,5010.2
XS Rating Curve= 0 ,0
Exp/Cntr=0.3,0.1

Type RM Length L Ch R = 1 ,1497    ,959,959,959
BEGIN DESCRIPTION:
Mapping XS ca185c47
END DESCRIPTION:
XS GIS Cut Line= 4
      2485109.32     13499358.25       2485699.6      13498620.4
      2485552.03     13498377.35      2485282.93     13498247.14
#Sta/Elev= 30
  3828.9   200.2  3936.1  199.94  4160.4  197.46  4226.9  196.08  4241.3  194.94
  4282.9  188.36  4404.6  194.11    4483  194.12  4639.9  192.45  4716.8  186.21
  4753.6  187.13  4780.1  186.47  4799.9  187.61  4810.5   187.2  4853.1  189.29
  4884.1  187.69    4890  188.49  4905.4  186.49  4926.8  187.11  4969.4  186.03
    4979  184.62  4987.9  181.15  4988.3  180.65  4993.7  181.15  5000.4  184.86
    5039  189.26  5056.6  192.15  5169.2  191.93  5331.7  195.41  5357.1     196
#Mann= 8 ,-1 , 0
  3828.9     .05       0  3936.1     .07       0  4160.4     .12       0
  4799.9     .05       0  4987.9     .05       0  4993.7     .05       0
    5039     .12       0  5331.7     .05       0
Bank Sta=4987.9,4993.7
XS Rating Curve= 0 ,0
Exp/Cntr=0.3,0.1

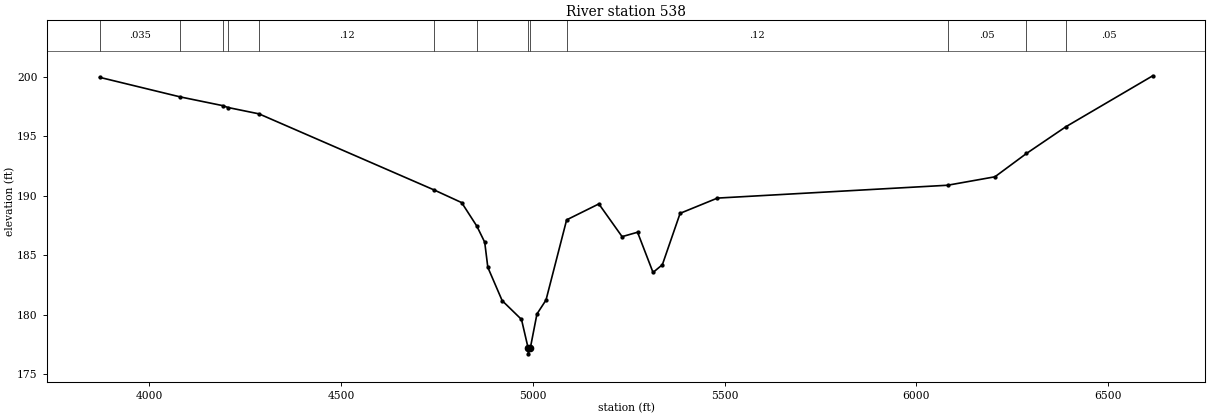
Type RM Length L Ch R = 1 ,538     ,0,0,0
BEGIN DESCRIPTION:
TRIB 8 TO EIGHTEENMILE CREEK 1.0
END DESCRIPTION:
XS GIS Cut Line= 4
      2485282.95     13499382.38       2486189.2     13498950.08
      2486256.91     13498439.67      2485095.47     13498043.84
#Sta/Elev= 30
  3870.4  199.94  4081.1  198.29  4191.5  197.56  4205.6   197.4  4285.9  196.87
  4743.5  190.46  4814.4  189.41    4854  187.43  4874.5  186.08  4882.6  183.97
    4920  181.17  4970.4  179.59  4987.6   177.2  4988.1   176.7  4993.5   177.2
  5010.7  180.05  5034.3  181.22  5088.1  187.96  5172.1   189.3  5232.7  186.55
    5273  186.92  5313.4  183.54  5337.7  184.19    5384  188.51  5481.3  189.79
  6081.4  190.87  6204.9  191.58  6287.1  193.54    6390  195.79  6616.4  200.07
#Mann= 13 ,-1 , 0
  3870.4    .035       0  4081.1     .07       0  4191.5    .035       0
  4205.6     .07       0  4285.9     .12       0  4743.5     .07       0
    4854     .05       0  4987.6     .05       0  4993.5     .05       0
  5088.1     .12       0  6081.4     .05       0  6287.1     .12       0
    6390     .05       0
Bank Sta=4987.6,4993.5
XS Rating Curve= 0 ,0
Exp/Cntr=0.3,0.1

Chan Stop Cuts=-1
Use User Specified Reach Order=0
Composite Channel Slope=5