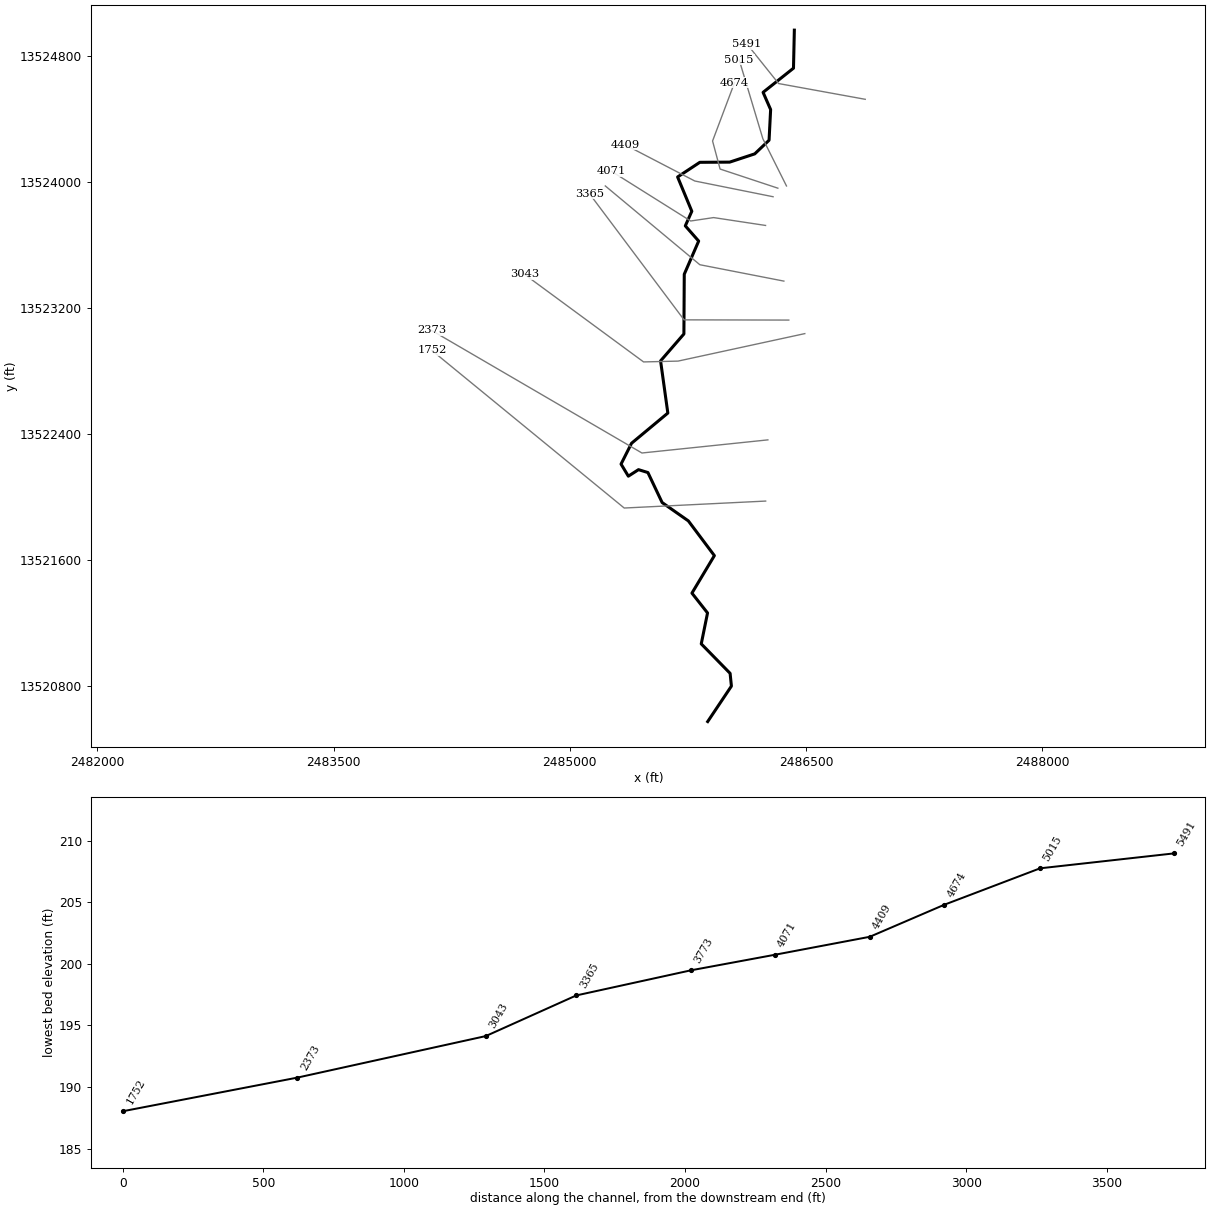
--- TRIB 8 TO FIFTEENMILE CREEK.prj (project) ---

Proj Title=TRIB 8 TO FIFTEENMILE CREEK Base Level Engineering
Current Plan=p01
Default Exp/Contr=0.3,0.1
English Units
Geom File=g01
Flow File=f01
Plan File=p01
BEGIN DESCRIPTION:
TRIB 8 TO FIFTEENMILE CREEK
END DESCRIPTION:

--- TRIB 8 TO FIFTEENMILE CREEK.p01 (plan) ---

Plan Title=Multiple Run
Short Identifier=Multiple
Geom File=g01
Flow File=f01
Subcritical Flow
K Sum by GR= 0
Std Step Tol= 0.01
Critical Tol= 0.01
Num of Std Step Trials= 20
Max Error Tol= 0.3
Flow Tol Ratio= 0.001
Split Flow NTrial= 30
Split Flow Tol= 0.02
Split Flow Ratio= 0.02
Log Output Level= 0
Friction Slope Method= 1
Unsteady Friction Slope Method= 2
Unsteady Bridges Friction Slope Method= 1
Parabolic Critical Depth
Global Vel Dist=  1 , 1 , 1
Global Log Level= 0
CheckData=True
Encroach Param= -1, 0, 0, 0
BEGIN DESCRIPTION:
Multiple Run
END DESCRIPTION:

--- TRIB 8 TO FIFTEENMILE CREEK.f01 (steady flow) ---

Flow Title=Multiple
Number of Profiles=7
Profile Names=10-year,25-year,50-year,1pct_min,100-year,1pct_plu,500-year
River Rch & RM= TRIB 8 TO FIFTEE,Reach-1,5491
     557     894    1197     777    1550    3093    2571
River Rch & RM= TRIB 8 TO FIFTEE,Reach-1,4409
    1026    1696    2316    1528    3049    6083    5232
Boundary for River Rch & Prof#=TRIB 8 TO FIFTEE,Reach-1,1
Up Type=0
Dn Type=3
Dn Slope=0.005
Boundary for River Rch & Prof#=TRIB 8 TO FIFTEE,Reach-1,2
Up Type=0
Dn Type=3
Dn Slope=0.005
Boundary for River Rch & Prof#=TRIB 8 TO FIFTEE,Reach-1,3
Up Type=0
Dn Type=3
Dn Slope=0.005
Boundary for River Rch & Prof#=TRIB 8 TO FIFTEE,Reach-1,4
Up Type=0
Dn Type=3
Dn Slope=0.005
Boundary for River Rch & Prof#=TRIB 8 TO FIFTEE,Reach-1,5
Up Type=0
Dn Type=3
Dn Slope=0.005
Boundary for River Rch & Prof#=TRIB 8 TO FIFTEE,Reach-1,6
Up Type=0
Dn Type=3
Dn Slope=0.005
Boundary for River Rch & Prof#=TRIB 8 TO FIFTEE,Reach-1,7
Up Type=0
Dn Type=3
Dn Slope=0.005

--- TRIB 8 TO FIFTEENMILE CREEK.g01 (geometry) ---

Geom Title=Existing Conditions

River Reach=TRIB 8 TO FIFTEE,Reach-1
Reach XY= 30
      2486425.00     13524964.02      2486419.55     13524722.53
      2486226.54     13524569.15      2486274.46     13524459.79
      2486264.53     13524265.17      2486173.52     13524178.61
      2486014.50     13524126.21      2485825.00     13524125.00
      2485683.98     13524032.02      2485774.18     13523814.29
      2485732.85     13523721.59      2485817.66     13523625.10
      2485726.22     13523414.50      2485723.95     13523035.43
      2485575.93     13522864.52      2485621.93     13522533.30
      2485391.64     13522341.68      2485325.01     13522209.47
      2485371.27     13522132.72      2485435.68     13522174.13
      2485495.47     13522155.73      2485585.76     13521965.30
      2485752.14     13521848.84      2485917.40     13521628.34
      2485774.95     13521390.34      2485873.96     13521264.56
      2485834.13     13521068.26      2486017.24     13520881.17
      2486025.50     13520799.97      2485875.00     13520575.00

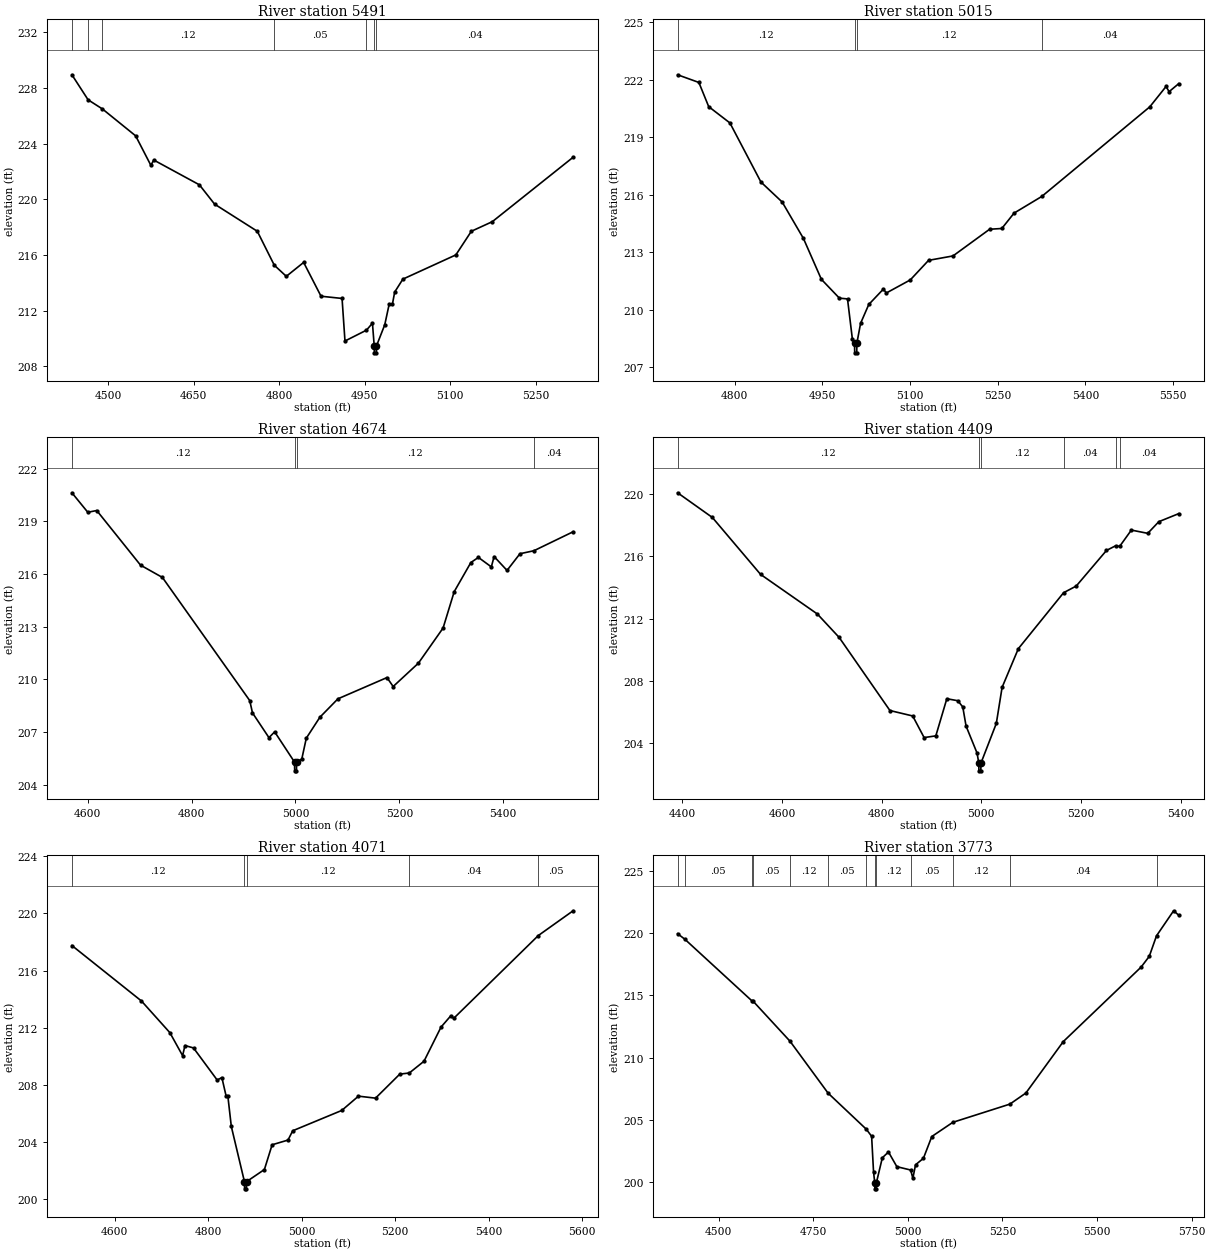
Type RM Length L Ch R = 1,5491,476,476,476
BEGIN DESCRIPTION:
TRIB 8 TO FIFTEENMILE CREEK 9.0
END DESCRIPTION:
XS GIS Cut Line= 3
      2486874.98     13524525.00      2486325.00     13524625.00
      2486124.97     13524875.03
#Sta/Elev= 30
  4436.4  228.96  4464.8  227.16  4490.0  226.50  4548.2  224.57  4574.9  222.45
  4580.0  222.83  4660.0  221.05  4686.7  219.66  4761.6  217.71  4791.4  215.27
  4812.5  214.47  4842.9  215.47  4873.4  213.04  4910.3  212.88  4915.4  209.82
  4953.1  210.60  4963.6  211.10  4966.7  209.47  4967.0  208.97  4970.5  208.97
  4970.7  209.47  4985.2  210.99  4992.9  212.46  4998.6  212.46  5002.6  213.34
  5017.0  214.27  5109.9  216.01  5137.1  217.71  5173.9  218.40  5315.6  223.03
#Mann=7,-1,0
  4436.4    0.04       0  4464.8    0.05       0  4490.0    0.12       0
  4791.4    0.05       0  4953.1    0.04       0  4966.7    0.04       0
  4970.7    0.04       0
Bank Sta=4966.7,4970.7
Exp/Cntr=0.3,0.1

Type RM Length L Ch R = 1,5015,341,341,341
BEGIN DESCRIPTION:
TRIB 8 TO FIFTEENMILE CREEK 8.0
END DESCRIPTION:
XS GIS Cut Line= 3
      2486375.02     13523974.96      2486225.00     13524275.00
      2486074.99     13524775.03
#Sta/Elev= 30
  4702.4  222.25  4738.8  221.85  4755.6  220.59  4791.9  219.74  4845.0  216.66
  4881.3  215.62  4917.7  213.72  4948.4  211.59  4979.2  210.61  4993.1  210.57
  5001.5  208.46  5005.1  208.26  5005.4  207.76  5008.9  207.76  5009.1  208.26
  5015.5  209.30  5029.5  210.28  5054.4  211.08  5059.6  210.88  5100.5  211.56
  5131.8  212.58  5173.6  212.81  5236.2  214.20  5257.1  214.24  5278.0  215.04
  5325.5  215.91  5510.3  220.58  5538.1  221.64  5543.3  221.37  5559.9  221.79
#Mann=4,-1,0
  4702.4    0.12       0  5005.1    0.05       0  5009.1    0.12       0
  5325.5    0.04       0
Bank Sta=5005.1,5009.1
Exp/Cntr=0.3,0.1

Type RM Length L Ch R = 1,4674,265,265,265
BEGIN DESCRIPTION:
Mapping XS 02baf52f
END DESCRIPTION:
XS GIS Cut Line= 4
      2486320.36     13523960.82      2485953.61     13524082.35
      2485905.87     13524260.30      2486044.76     13524629.22
#Sta/Elev= 30
  4569.7  220.63  4600.3  219.52  4617.5  219.62  4701.8  216.51  4743.9  215.81
  4912.0  208.80  4917.3  208.10  4949.0  206.69  4960.0  207.02  4998.2  205.30
  4998.5  204.80  5002.0  204.80  5002.2  205.30  5012.2  205.47  5020.9  206.66
  5047.0  207.85  5081.8  208.90  5176.2  210.11  5188.1  209.60  5236.7  210.93
  5284.2  212.93  5305.6  215.00  5337.7  216.66  5352.2  216.95  5377.1  216.41
  5382.4  217.00  5407.3  216.21  5432.2  217.16  5459.0  217.33  5534.5  218.41
#Mann=4,-1,0
  4569.7    0.12       0  4998.2    0.05       0  5002.2    0.12       0
  5459.0    0.04       0
Bank Sta=4998.2,5002.2
Exp/Cntr=0.3,0.1

Type RM Length L Ch R = 1,4409,338,338,338
BEGIN DESCRIPTION:
Mapping XS a9d6fc7e
END DESCRIPTION:
XS GIS Cut Line= 3
      2486290.02     13523906.56      2485793.02     13524006.39
      2485350.34     13524236.41
#Sta/Elev= 30
  4390.7  220.09  4460.5  218.50  4557.2  214.84  4671.2  212.29  4715.0  210.78
  4816.8  206.08  4862.5  205.73  4885.4  204.34  4908.9  204.45  4931.0  206.84
  4953.1  206.71  4963.0  206.31  4969.6  205.08  4991.7  203.34  4995.1  202.70
  4995.4  202.20  4999.2  202.20  4999.5  202.70  5030.3  205.25  5041.9  207.57
  5074.5  210.06  5165.3  213.66  5190.7  214.09  5251.4  216.38  5269.7  216.68
  5277.8  216.64  5301.3  217.69  5334.2  217.48  5356.4  218.23  5396.5  218.75
#Mann=6,-1,0
  4390.7    0.12       0  4995.1    0.05       0  4999.5    0.12       0
  5165.3    0.04       0  5269.7    0.05       0  5277.8    0.04       0
Bank Sta=4995.1,4999.5
Exp/Cntr=0.3,0.1

Type RM Length L Ch R = 1,4071,298,298,298
BEGIN DESCRIPTION:
Mapping XS 54165479
END DESCRIPTION:
XS GIS Cut Line= 4
      2486242.26     13523724.27      2485912.38     13523774.19
      2485766.98     13523752.48      2485265.70     13524067.14
#Sta/Elev= 30
  4508.5  217.75  4657.4  213.87  4718.1  211.66  4745.4  210.05  4750.4  210.76
  4768.7  210.59  4819.3  208.35  4829.4  208.52  4838.3  207.25  4842.1  207.25
  4849.6  205.10  4877.7  201.24  4878.0  200.74  4881.8  200.74  4882.1  201.24
  4920.4  202.09  4936.9  203.82  4970.9  204.15  4981.0  204.80  5085.9  206.22
  5121.7  207.22  5158.2  207.08  5210.1  208.76  5230.5  208.84  5261.9  209.66
  5298.4  212.05  5319.6  212.85  5325.5  212.66  5506.6  218.45  5581.0  220.18
#Mann=5,-1,0
  4508.5    0.12       0  4877.7    0.05       0  4882.1    0.12       0
  5230.5    0.04       0  5506.6    0.05       0
Bank Sta=4877.7,4882.1
Exp/Cntr=0.3,0.1

Type RM Length L Ch R = 1,3773,408,408,408
BEGIN DESCRIPTION:
TRIB 8 TO FIFTEENMILE CREEK 5.0
END DESCRIPTION:
XS GIS Cut Line= 3
      2486358.61     13523370.96      2485825.00     13523475.00
      2485224.99     13523975.01
#Sta/Elev= 30
  4391.4  219.96  4410.4  219.52  4587.8  214.57  4591.0  214.54  4688.5  211.33
  4789.2  207.16  4890.0  204.27  4904.2  203.70  4909.3  200.84  4912.4  199.98
  4912.8  199.48  4916.6  199.48  4916.9  199.98  4932.5  201.97  4948.7  202.44
  4970.9  201.26  5007.4  200.99  5013.2  200.33  5020.3  201.41  5041.1  201.93
  5063.3  203.68  5118.9  204.82  5269.6  206.28  5311.9  207.17  5410.8  211.30
  5616.5  217.28  5638.0  218.14  5657.2  219.79  5702.4  221.80  5716.1  221.44
#Mann=13,-1,0
  4391.4    0.12       0  4410.4    0.05       0  4587.8    0.12       0
  4591.0    0.05       0  4688.5    0.12       0  4789.2    0.05       0
  4890.0    0.12       0  4912.4    0.05       0  4916.9    0.12       0
  5007.4    0.05       0  5118.9    0.12       0  5269.6    0.04       0
  5657.2    0.05       0
Bank Sta=4912.4,4916.9
Exp/Cntr=0.3,0.1

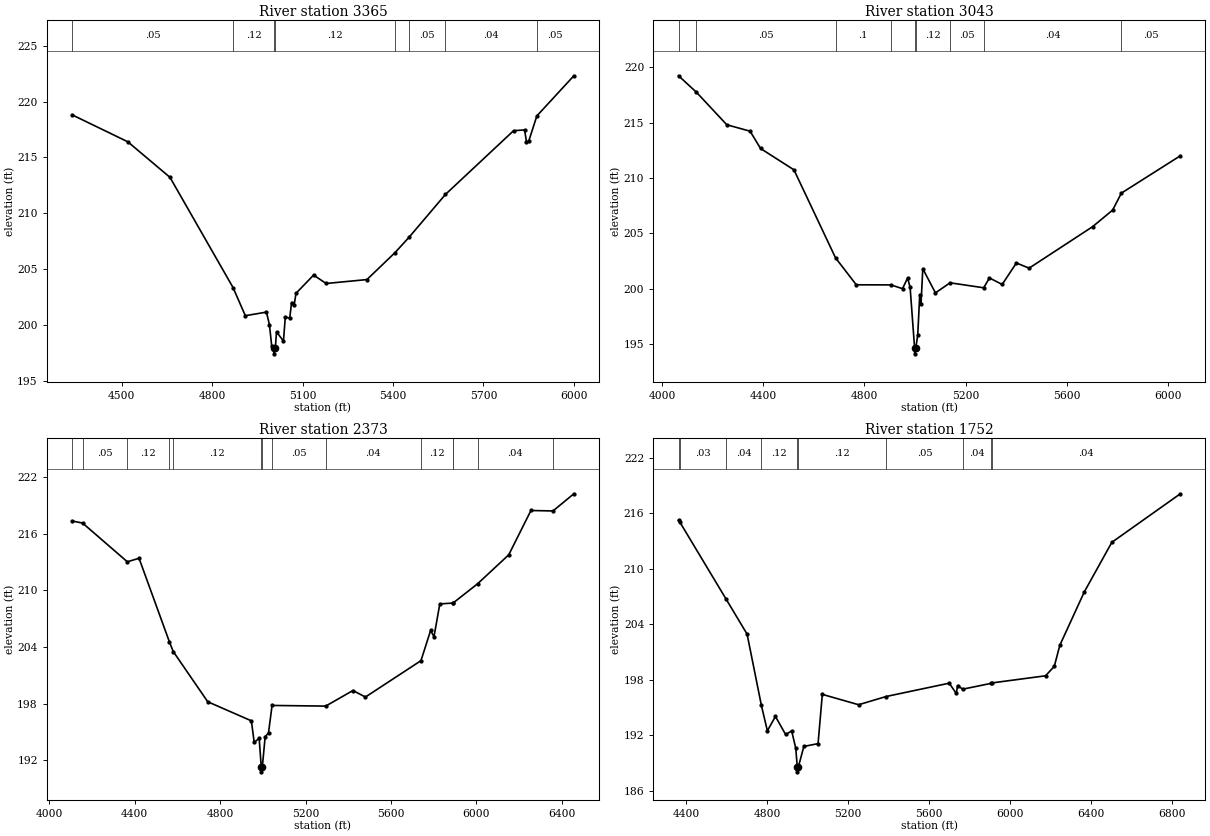
Type RM Length L Ch R = 1,3365,322,322,322
BEGIN DESCRIPTION:
TRIB 8 TO FIFTEENMILE CREEK 4.0
END DESCRIPTION:
XS GIS Cut Line= 3
      2486389.79     13523123.58      2485725.00     13523125.00
      2485125.00     13523925.00
#Sta/Elev= 30
  4335.3  218.81  4520.1  216.40  4660.1  213.22  4869.3  203.37  4910.1  200.85
  4980.1  201.17  4990.1  200.05  4997.6  198.15  5005.1  197.94  5005.4  197.44
  5009.6  197.94  5013.6  199.41  5036.6  198.58  5042.8  200.74  5057.4  200.63
  5063.6  202.03  5072.0  201.78  5078.2  202.85  5136.6  204.48  5178.2  203.73
  5313.6  204.08  5406.4  206.48  5453.3  207.86  5574.0  211.69  5800.1  217.39
  5836.6  217.46  5842.8  216.41  5850.1  216.43  5877.3  218.71  6000.1  222.30
#Mann=8,-1,0
  4335.3    0.05       0  4869.3    0.12       0  5005.1    0.05       0
  5009.6    0.12       0  5406.4    0.04       0  5453.3    0.05       0
  5574.0    0.04       0  5877.3    0.05       0
Bank Sta=5005.1,5009.6
Exp/Cntr=0.3,0.1

Type RM Length L Ch R = 1,3043,670,670,670
BEGIN DESCRIPTION:
Mapping XS 14c400eb
END DESCRIPTION:
XS GIS Cut Line= 4
      2486491.42     13523037.65      2485686.69     13522863.16
      2485467.94     13522857.95      2484710.13     13523415.24
#Sta/Elev= 30
  4065.2  219.23  4135.7  217.75  4255.9  214.81  4348.0  214.23  4389.3  212.67
  4521.4  210.74  4685.6  202.80  4767.6  200.37  4904.7  200.36  4950.3  200.02
  4970.3  200.98  4980.3  200.15  4998.1  194.64  4998.4  194.14  5002.6  194.64
  5010.4  195.82  5018.4  199.49  5023.4  198.63  5030.4  201.82  5080.4  199.64
  5138.2  200.55  5271.1  200.10  5293.8  200.99  5344.0  200.40  5400.3  202.34
  5450.5  201.87  5701.2  205.61  5780.6  207.11  5815.1  208.64  6048.1  212.01
#Mann=9,-1,0
  4065.2    0.12       0  4135.7    0.05       0  4685.6     0.1       0
  4904.7    0.12       0  4998.1    0.05       0  5002.6    0.12       0
  5138.2    0.05       0  5271.1    0.04       0  5815.1    0.05       0
Bank Sta=4998.1,5002.6
Exp/Cntr=0.3,0.1

Type RM Length L Ch R = 1,2373,621,621,621
BEGIN DESCRIPTION:
Mapping XS a8c7831b
END DESCRIPTION:
XS GIS Cut Line= 3
      2486257.02     13522363.16      2485457.52     13522279.83
      2484121.60     13523058.46
#Sta/Elev= 30
  4106.2  217.33  4155.4  217.11  4365.0  213.01  4419.9  213.38  4562.1  204.53
  4580.0  203.51  4741.6  198.19  4946.0  196.17  4959.2  193.88  4982.4  194.33
  4992.4  191.27  4992.7  190.77  4997.2  191.27  5010.5  194.48  5026.2  194.90
  5042.9  197.80  5294.0  197.73  5421.6  199.38  5480.1  198.69  5740.2  202.54
  5785.5  205.74  5801.2  205.07  5828.5  208.55  5889.9  208.64  5890.5  208.64
  6005.9  210.69  6151.4  213.75  6255.3  218.44  6358.4  218.39  6456.3  220.21
#Mann=14,-1,0
  4106.2    0.04       0  4155.4    0.05       0  4365.0    0.12       0
  4562.1    0.05       0  4580.0    0.12       0  4992.4    0.05       0
  4997.2    0.12       0  5042.9    0.05       0  5294.0    0.04       0
  5740.2    0.12       0  5889.9    0.04       0  5890.5    0.05       0
  6005.9    0.04       0  6358.4    0.05       0
Bank Sta=4992.4,4997.2
Exp/Cntr=0.3,0.1

Type RM Length L Ch R = 1,1752,0,0,0
BEGIN DESCRIPTION:
4896
END DESCRIPTION:
XS GIS Cut Line= 3
      2486242.97     13521974.67      2485345.09     13521930.51
      2484124.26     13522930.71
#Sta/Elev= 30
  4362.3  215.25  4367.8  215.09  4595.3  206.79  4700.7  202.94  4771.4  195.22
  4800.8  192.48  4840.8  194.03  4890.9  192.08  4920.9  192.46  4941.0  190.59
  4948.6  188.54  4948.9  188.04  4953.4  188.54  4981.0  190.79  5051.1  191.09
  5072.1  196.42  5251.3  195.30  5387.2  196.19  5698.4  197.63  5733.5  196.52
  5740.0  197.38  5764.9  196.98  5902.8  197.60  5909.8  197.66  6174.2  198.43
  6217.3  199.45  6244.6  201.73  6365.8  207.52  6501.5  212.87  6839.5  218.12
#Mann=10,-1,0
  4362.3    0.12       0  4367.8    0.03       0  4595.3    0.04       0
  4771.4    0.12       0  4948.6    0.05       0  4953.4    0.12       0
  5387.2    0.05       0  5764.9    0.04       0  5902.8    0.05       0
  5909.8    0.04       0
Bank Sta=4948.6,4953.4
Exp/Cntr=0.3,0.1

Chan Stop Cuts=-1