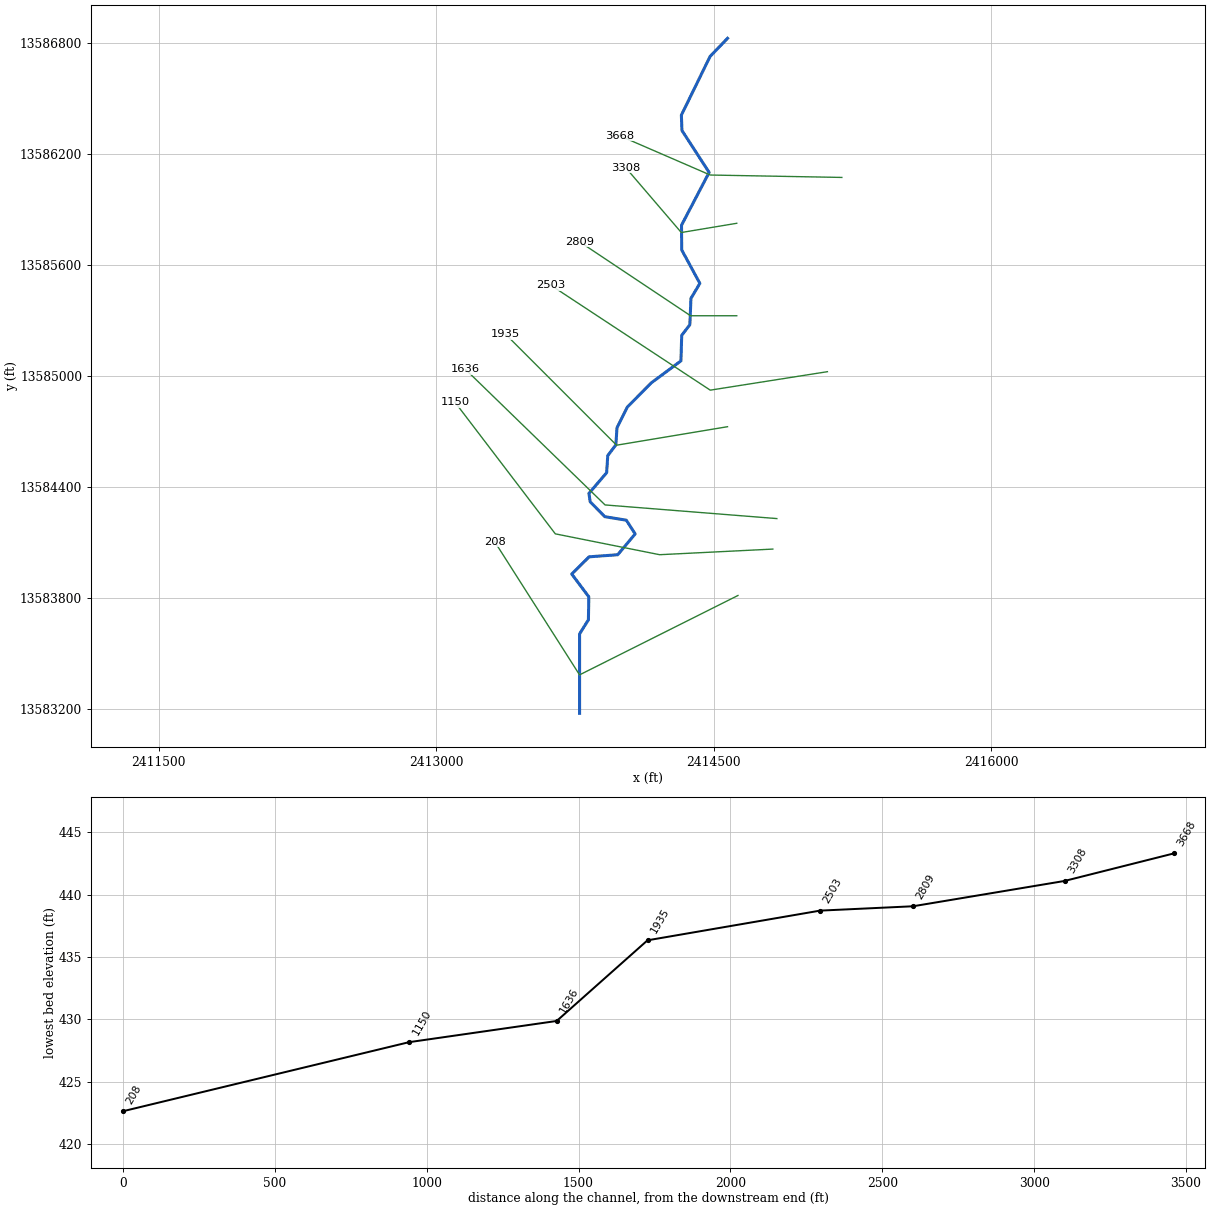
--- TRIB 8 TO LITTLE SALT CREEK.prj (project) ---

Proj Title=TRIB 8 TO LITTLE SALT CREEK Base Level Engineering
Current Plan=p01
Default Exp/Contr=0.3,0.1
English Units
Geom File=g01
Flow File=f01
Plan File=p01
BEGIN DESCRIPTION:
TRIB 8 TO LITTLE SALT CREEK
END DESCRIPTION:

--- TRIB 8 TO LITTLE SALT CREEK.p01 (plan) ---

Plan Title=Multiple Run
Short Identifier=Multiple
Geom File=g01
Flow File=f01
Subcritical Flow
K Sum by GR= 0
Std Step Tol= 0.01
Critical Tol= 0.01
Num of Std Step Trials= 20
Max Error Tol= 0.3
Flow Tol Ratio= 0.001
Split Flow NTrial= 30
Split Flow Tol= 0.02
Split Flow Ratio= 0.02
Log Output Level= 0
Friction Slope Method= 1
Unsteady Friction Slope Method= 2
Unsteady Bridges Friction Slope Method= 1
Parabolic Critical Depth
Global Vel Dist=  1 , 1 , 1
Global Log Level= 0
CheckData=True
Encroach Param= -1, 0, 0, 0
BEGIN DESCRIPTION:
Multiple Run
END DESCRIPTION:

--- TRIB 8 TO LITTLE SALT CREEK.f01 (steady flow) ---

Flow Title=Multiple
Number of Profiles=7
Profile Names=10-year,25-year,50-year,1pct_min,100-year,1pct_plu,500-year
River Rch & RM= TRIB 8 TO LITTLE,Reach-1,3668
     677    1113    1515    1000    1995    3981    3428
Boundary for River Rch & Prof#=TRIB 8 TO LITTLE,Reach-1,1
Up Type=0
Dn Type=3
Dn Slope=0.005
Boundary for River Rch & Prof#=TRIB 8 TO LITTLE,Reach-1,2
Up Type=0
Dn Type=3
Dn Slope=0.005
Boundary for River Rch & Prof#=TRIB 8 TO LITTLE,Reach-1,3
Up Type=0
Dn Type=3
Dn Slope=0.005
Boundary for River Rch & Prof#=TRIB 8 TO LITTLE,Reach-1,4
Up Type=0
Dn Type=3
Dn Slope=0.005
Boundary for River Rch & Prof#=TRIB 8 TO LITTLE,Reach-1,5
Up Type=0
Dn Type=3
Dn Slope=0.005
Boundary for River Rch & Prof#=TRIB 8 TO LITTLE,Reach-1,6
Up Type=0
Dn Type=3
Dn Slope=0.005
Boundary for River Rch & Prof#=TRIB 8 TO LITTLE,Reach-1,7
Up Type=0
Dn Type=3
Dn Slope=0.005

--- TRIB 8 TO LITTLE SALT CREEK.g01 (geometry) ---

Geom Title=Existing Conditions

River Reach=TRIB 8 TO LITTLE,Reach-1
Reach XY= 30
      2414575.00     13586825.00      2414480.79     13586727.32
      2414325.37     13586409.73      2414328.67     13586326.58
      2414475.50     13586100.03      2414326.19     13585814.50
      2414327.23     13585680.93      2414425.41     13585500.00
      2414377.30     13585419.07      2414371.21     13585276.57
      2414327.27     13585219.06      2414322.94     13585080.85
      2414161.79     13584961.37      2414033.14     13584831.06
      2413977.33     13584719.03      2413971.15     13584626.60
      2413927.36     13584569.02      2413921.38     13584476.50
      2413825.55     13584364.35      2413832.45     13584318.93
      2413911.67     13584238.39      2414027.75     13584219.58
      2414075.51     13584145.23      2413981.21     13584032.81
      2413826.44     13584021.46      2413732.59     13583928.35
      2413825.05     13583805.01      2413822.75     13583680.94
      2413775.07     13583604.97      2413775.00     13583175.00

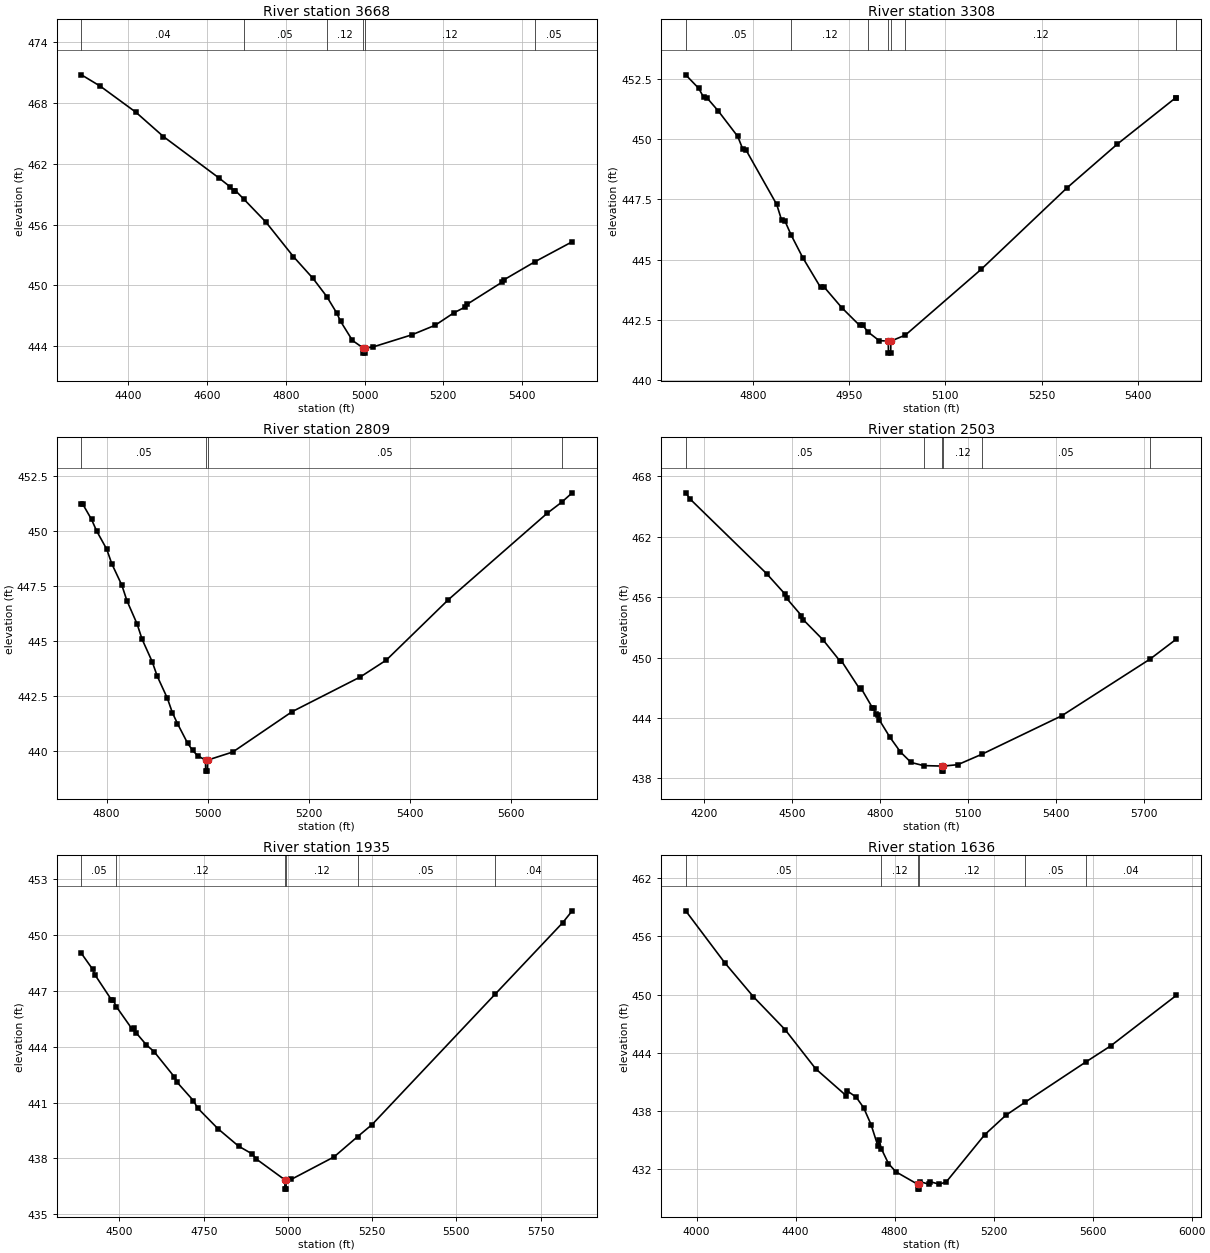
Type RM Length L Ch R = 1,3668,360,360,360
BEGIN DESCRIPTION:
Mapping XS b3bbef8a
END DESCRIPTION:
XS GIS Cut Line= 3
      2415193.23     13586072.88      2414481.46     13586085.90
      2413990.98     13586298.59
#Sta/Elev= 30
  4280.8  470.76  4329.0  469.63  4419.1  467.07  4489.1  464.67  4629.1  460.62
  4659.1  459.70  4667.0  459.31  4672.0  459.34  4692.6  458.53  4749.1  456.25
  4819.1  452.84  4869.1  450.68  4903.9  448.90  4929.1  447.28  4939.1  446.45
  4969.1  444.57  4996.6  443.82  4996.9  443.32  5000.4  443.32  5000.6  443.82
  5021.5  443.93  5119.6  445.12  5179.3  446.07  5226.2  447.28  5255.1  447.86
  5261.3  448.16  5348.5  450.30  5354.4  450.56  5433.5  452.35  5527.3  454.30
#Mann=6,-1,0
  4280.8    0.04       0  4692.6    0.05       0  4903.9    0.12       0
  4996.6    0.05       0  5000.6    0.12       0  5433.5    0.05       0
Bank Sta=4996.6,5000.6
Exp/Cntr=0.3,0.1

Type RM Length L Ch R = 1,3308,499,499,499
BEGIN DESCRIPTION:
TRIB 8 TO LITTLE SALT CREEK 6.0
END DESCRIPTION:
XS GIS Cut Line= 3
      2414624.97     13585825.00      2414325.00     13585775.00
      2414024.99     13586125.01
#Sta/Elev= 30
  4695.2  452.68  4715.4  452.12  4723.1  451.75  4728.1  451.73  4745.9  451.18
  4776.3  450.12  4783.9  449.61  4788.9  449.57  4837.1  447.29  4844.7  446.64
  4849.8  446.61  4859.4  446.03  4877.7  445.08  4905.5  443.84  4910.6  443.87
  4938.5  443.00  4966.4  442.26  4971.4  442.26  4979.4  441.99  4996.8  441.63
  5011.0  441.61  5011.3  441.11  5014.8  441.11  5015.0  441.61  5037.7  441.86
  5155.7  444.59  5289.6  447.98  5368.1  449.80  5459.3  451.73  5460.3  451.73
#Mann=7,-1,0
  4695.2    0.05       0  4859.4    0.12       0  4979.4    0.05       0
  5011.0    0.05       0  5015.0    0.05       0  5037.7    0.12       0
  5459.3    0.05       0
Bank Sta=5011,5015
Exp/Cntr=0.3,0.1

Type RM Length L Ch R = 1,2809,306,306,306
BEGIN DESCRIPTION:
TRIB 8 TO LITTLE SALT CREEK 5.0
END DESCRIPTION:
XS GIS Cut Line= 3
      2414625.01     13585325.00      2414375.00     13585325.00
      2413775.02     13585724.99
#Sta/Elev= 30
  4750.3  451.21  4752.8  451.21  4770.3  450.51  4780.3  449.99  4800.3  449.16
  4810.3  448.50  4830.3  447.52  4840.3  446.82  4860.3  445.77  4870.3  445.07
  4890.3  444.05  4900.3  443.39  4920.3  442.39  4930.3  441.73  4940.3  441.24
  4960.3  440.35  4970.3  440.02  4980.3  439.78  4995.8  439.58  4996.1  439.08
  4999.6  439.08  4999.8  439.58  5049.9  439.95  5167.1  441.78  5302.3  443.36
  5353.4  444.12  5476.5  446.87  5671.8  450.79  5700.4  451.29  5721.4  451.72
#Mann=4,-1,0
  4750.3    0.05       0  4995.8    0.05       0  4999.8    0.05       0
  5700.4    0.04       0
Bank Sta=4995.8,4999.8
Exp/Cntr=0.3,0.1

Type RM Length L Ch R = 1,2503,568,568,568
BEGIN DESCRIPTION:
Mapping XS f56dba71
END DESCRIPTION:
XS GIS Cut Line= 3
      2415115.10     13585022.53      2414481.46     13584922.71
      2413617.76     13585491.27
#Sta/Elev= 30
  4136.2  466.35  4152.0  465.71  4412.1  458.34  4474.6  456.32  4480.5  455.89
  4531.1  454.17  4537.1  453.77  4604.7  451.77  4662.1  449.69  4667.2  449.70
  4729.7  446.91  4734.7  446.97  4773.3  445.04  4777.7  445.04  4785.2  444.40
  4791.1  444.28  4797.4  443.80  4833.3  442.10  4869.4  440.63  4905.6  439.59
  4948.2  439.28  5012.0  439.23  5012.3  438.73  5015.8  438.73  5016.0  439.23
  5065.2  439.37  5146.9  440.40  5419.9  444.22  5721.6  449.85  5811.7  451.84
#Mann=6,-1,0
  4136.2    0.05       0  4948.2    0.12       0  5012.0    0.05       0
  5016.0    0.12       0  5146.9    0.05       0  5721.6    0.04       0
Bank Sta=5012,5016
Exp/Cntr=0.3,0.1

Type RM Length L Ch R = 1,1935,299,299,299
BEGIN DESCRIPTION:
TRIB 8 TO LITTLE SALT CREEK 3.0
END DESCRIPTION:
XS GIS Cut Line= 3
      2414574.99     13584725.00      2413975.00     13584625.00
      2413374.99     13585225.01
#Sta/Elev= 30
  4387.1  449.01  4420.0  448.17  4427.6  447.85  4475.8  446.53  4480.9  446.51
  4491.1  446.14  4536.6  444.97  4541.7  445.02  4549.3  444.75  4579.7  444.10
  4602.5  443.74  4663.3  442.37  4671.0  442.09  4719.1  441.11  4731.8  440.71
  4792.6  439.59  4853.4  438.66  4894.0  438.24  4906.7  437.96  4990.8  436.85
  4991.1  436.35  4994.6  436.35  4994.8  436.85  5009.5  436.87  5136.8  438.08
  5206.9  439.17  5249.9  439.82  5614.5  446.81  5815.6  450.66  5843.9  451.30
#Mann=6,-1,0
  4387.1    0.05       0  4491.1    0.12       0  4990.8    0.05       0
  4994.8    0.12       0  5206.9    0.05       0  5614.5    0.04       0
Bank Sta=4990.8,4994.8
Exp/Cntr=0.3,0.1

Type RM Length L Ch R = 1,1636,486,486,486
BEGIN DESCRIPTION:
Mapping XS feff90c4
END DESCRIPTION:
XS GIS Cut Line= 3
      2414841.68     13584228.27      2413912.88     13584302.05
      2413158.83     13585034.43
#Sta/Elev= 30
  3955.7  458.65  4112.9  453.30  4229.2  449.77  4357.5  446.36  4480.9  442.32
  4604.2  439.54  4609.2  440.02  4644.5  439.39  4674.6  438.30  4704.7  436.55
  4732.5  434.32  4737.5  434.92  4746.3  434.05  4775.0  432.52  4805.0  431.67
  4893.1  430.38  4893.4  429.88  4896.9  429.88  4897.1  430.38  4902.1  430.66
  4937.6  430.39  4944.5  430.64  4980.0  430.39  5008.3  430.62  5163.7  435.50
  5248.6  437.50  5326.8  438.86  5573.4  443.04  5673.0  444.69  5938.6  449.92
#Mann=6,-1,0
  3955.7    0.05       0  4746.3    0.12       0  4893.1    0.05       0
  4897.1    0.12       0  5326.8    0.05       0  5573.4    0.04       0
Bank Sta=4893.1,4897.1
Exp/Cntr=0.3,0.1

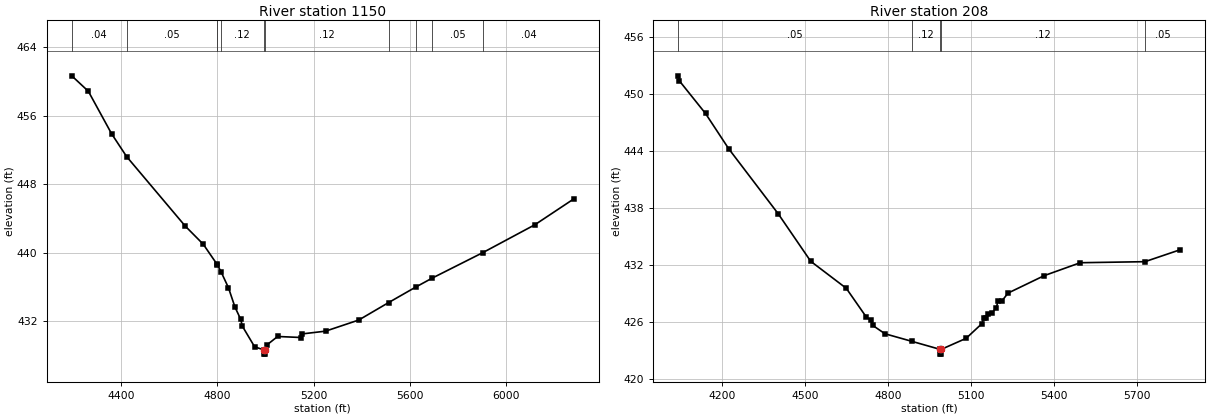
Type RM Length L Ch R = 1,1150,942,942,942
BEGIN DESCRIPTION:
Mapping XS fde1741b
END DESCRIPTION:
XS GIS Cut Line= 4
      2414820.02     13584063.34      2414208.02     13584032.95
      2413643.78     13584145.80      2413101.22     13584857.64
#Sta/Elev= 30
  4196.6  460.66  4265.3  458.86  4361.8  453.90  4424.3  451.23  4667.2  443.13
  4742.3  441.00  4798.0  438.72  4800.9  438.59  4816.3  437.77  4846.7  435.93
  4873.6  433.68  4897.7  432.23  4904.2  431.45  4955.2  429.04  4992.6  428.68
  4992.8  428.18  4996.3  428.18  4996.6  428.68  5006.2  429.25  5050.7  430.24
  5147.5  430.12  5152.6  430.54  5249.5  430.86  5387.4  432.16  5510.8  434.19
  5624.0  436.01  5692.0  437.05  5903.1  440.04  6118.1  443.28  6279.8  446.30
#Mann=11,-1,0
  4196.6    0.04       0  4424.3    0.05       0  4798.0    0.12       0
  4800.9    0.05       0  4816.3    0.12       0  4992.6    0.05       0
  4996.6    0.12       0  5510.8    0.05       0  5624.0    0.12       0
  5692.0    0.05       0  5903.1    0.04       0
Bank Sta=4992.6,4996.6
Exp/Cntr=0.3,0.1

Type RM Length L Ch R = 1,208,0,0,0
BEGIN DESCRIPTION:
TRIB 8 TO LITTLE SALT CREEK 1.0
END DESCRIPTION:
XS GIS Cut Line= 3
      2414631.42     13583812.47      2413774.98     13583383.20
      2413315.43     13584104.08
#Sta/Elev= 30
  4042.0  451.90  4045.6  451.39  4140.5  447.94  4224.3  444.23  4403.1  437.39
  4520.4  432.40  4648.8  429.56  4721.5  426.52  4738.2  426.19  4743.8  425.67
  4788.5  424.78  4886.1  423.98  4987.6  423.14  4987.9  422.64  4991.4  422.64
  4991.6  423.14  5081.5  424.30  5139.0  425.86  5144.9  426.44  5154.2  426.44
  5160.2  426.91  5175.4  426.98  5190.6  427.54  5196.6  428.21  5211.8  428.27
  5232.9  429.06  5363.3  430.89  5493.6  432.25  5727.2  432.36  5854.9  433.62
#Mann=5,-1,0
  4042.0    0.05       0  4886.1    0.12       0  4987.6    0.05       0
  4991.6    0.12       0  5727.2    0.05       0
Bank Sta=4987.6,4991.6
Exp/Cntr=0.3,0.1

Chan Stop Cuts=-1