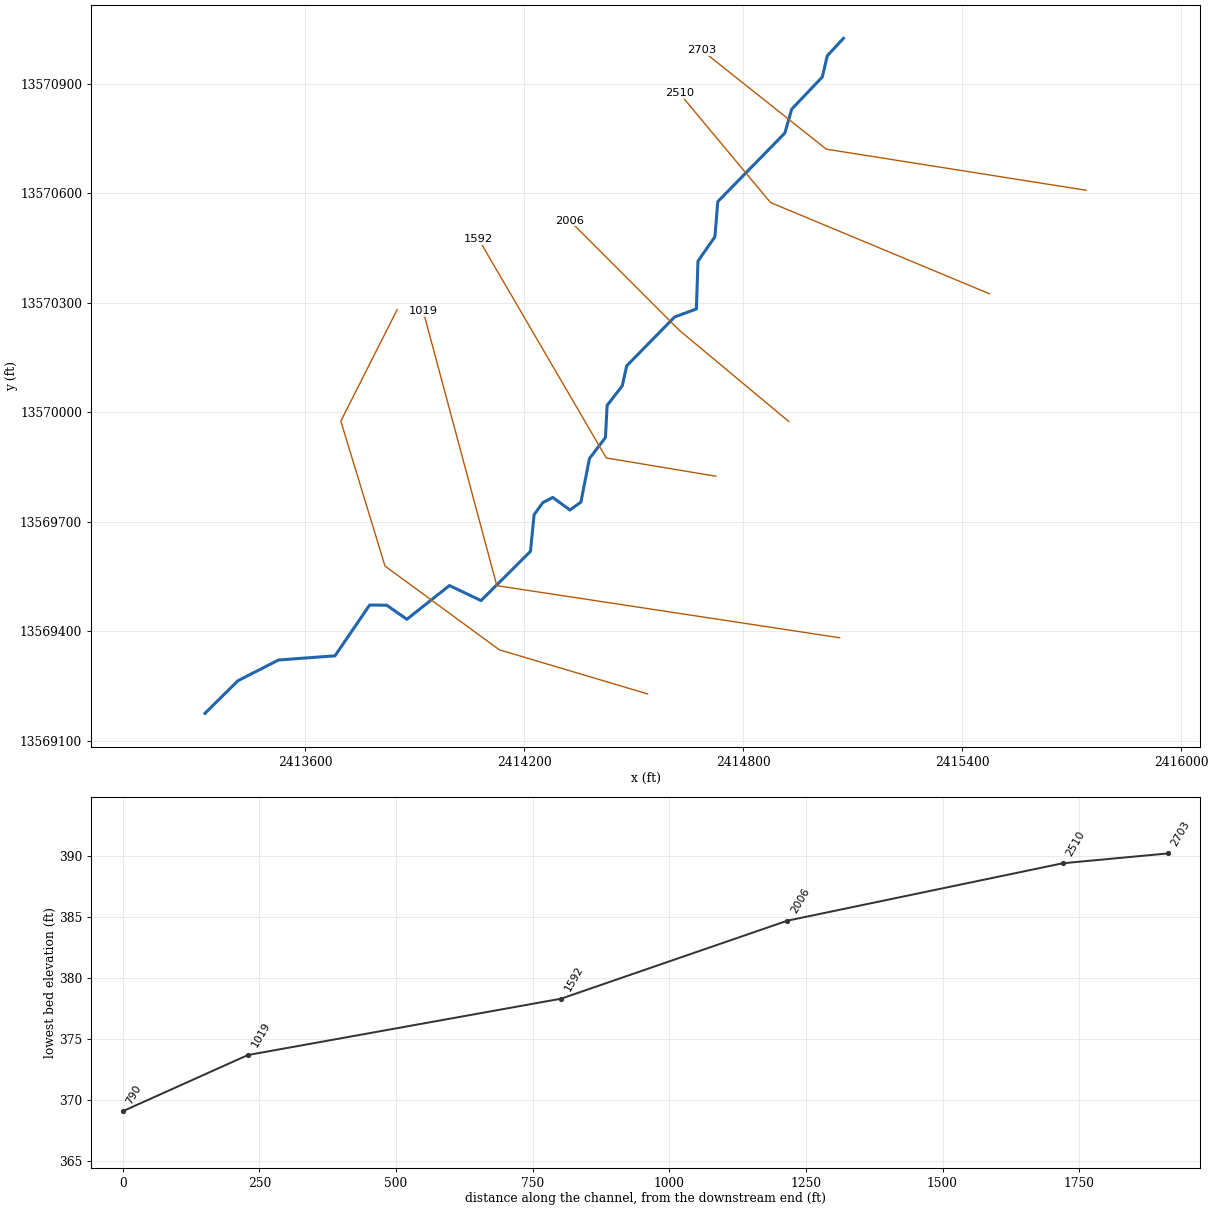
--- TRIB 8 TO SALT CREEK.prj (project) ---

Proj Title=TRIB 8 TO SALT CREEK Base Level Engineering
Current Plan=p01
Default Exp/Contr=0.3,0.1
English Units
Geom File=g01
Flow File=f01
Plan File=p01
BEGIN DESCRIPTION:
TRIB 8 TO SALT CREEK
END DESCRIPTION:

--- TRIB 8 TO SALT CREEK.p01 (plan) ---

Plan Title=Multiple Run
Short Identifier=Multiple
Geom File=g01
Flow File=f01
Subcritical Flow
K Sum by GR= 0
Std Step Tol= 0.01
Critical Tol= 0.01
Num of Std Step Trials= 20
Max Error Tol= 0.3
Flow Tol Ratio= 0.001
Split Flow NTrial= 30
Split Flow Tol= 0.02
Split Flow Ratio= 0.02
Log Output Level= 0
Friction Slope Method= 1
Unsteady Friction Slope Method= 2
Unsteady Bridges Friction Slope Method= 1
Parabolic Critical Depth
Global Vel Dist=  1 , 1 , 1
Global Log Level= 0
CheckData=True
Encroach Param= -1, 0, 0, 0
BEGIN DESCRIPTION:
Multiple Run
END DESCRIPTION:

--- TRIB 8 TO SALT CREEK.f01 (steady flow) ---

Flow Title=Multiple
Number of Profiles=7
Profile Names=10-year,25-year,50-year,1pct_min,100-year,1pct_plu,500-year
River Rch & RM= TRIB 8 TO SALT C,Reach-1,2703
     448     721     967     630    1257    2509    2103
Boundary for River Rch & Prof#=TRIB 8 TO SALT C,Reach-1,1
Up Type=0
Dn Type=3
Dn Slope=0.005
Boundary for River Rch & Prof#=TRIB 8 TO SALT C,Reach-1,2
Up Type=0
Dn Type=3
Dn Slope=0.005
Boundary for River Rch & Prof#=TRIB 8 TO SALT C,Reach-1,3
Up Type=0
Dn Type=3
Dn Slope=0.005
Boundary for River Rch & Prof#=TRIB 8 TO SALT C,Reach-1,4
Up Type=0
Dn Type=3
Dn Slope=0.005
Boundary for River Rch & Prof#=TRIB 8 TO SALT C,Reach-1,5
Up Type=0
Dn Type=3
Dn Slope=0.005
Boundary for River Rch & Prof#=TRIB 8 TO SALT C,Reach-1,6
Up Type=0
Dn Type=3
Dn Slope=0.005
Boundary for River Rch & Prof#=TRIB 8 TO SALT C,Reach-1,7
Up Type=0
Dn Type=3
Dn Slope=0.005

--- TRIB 8 TO SALT CREEK.g01 (geometry) ---

Geom Title=Existing Conditions

River Reach=TRIB 8 TO SALT C,Reach-1
Reach XY= 30
      2415075.00     13571025.00      2415030.70     13570977.35
      2415016.93     13570918.92      2414933.18     13570831.04
      2414914.22     13570765.32      2414730.52     13570577.43
      2414722.64     13570480.98      2414676.24     13570414.48
      2414671.92     13570283.31      2414612.05     13570261.26
      2414480.83     13570127.30      2414468.86     13570072.83
      2414427.33     13570019.03      2414422.65     13569930.97
      2414378.86     13569873.40      2414355.37     13569753.95
      2414325.23     13569732.47      2414278.14     13569766.92
      2414251.18     13569752.68      2414227.15     13569719.50
      2414217.14     13569618.83      2414081.73     13569484.15
      2413995.16     13569525.31      2413878.40     13569432.84
      2413823.32     13569471.43      2413776.43     13569471.93
      2413681.47     13569332.70      2413526.56     13569321.24
      2413415.29     13569264.30      2413325.00     13569175.00

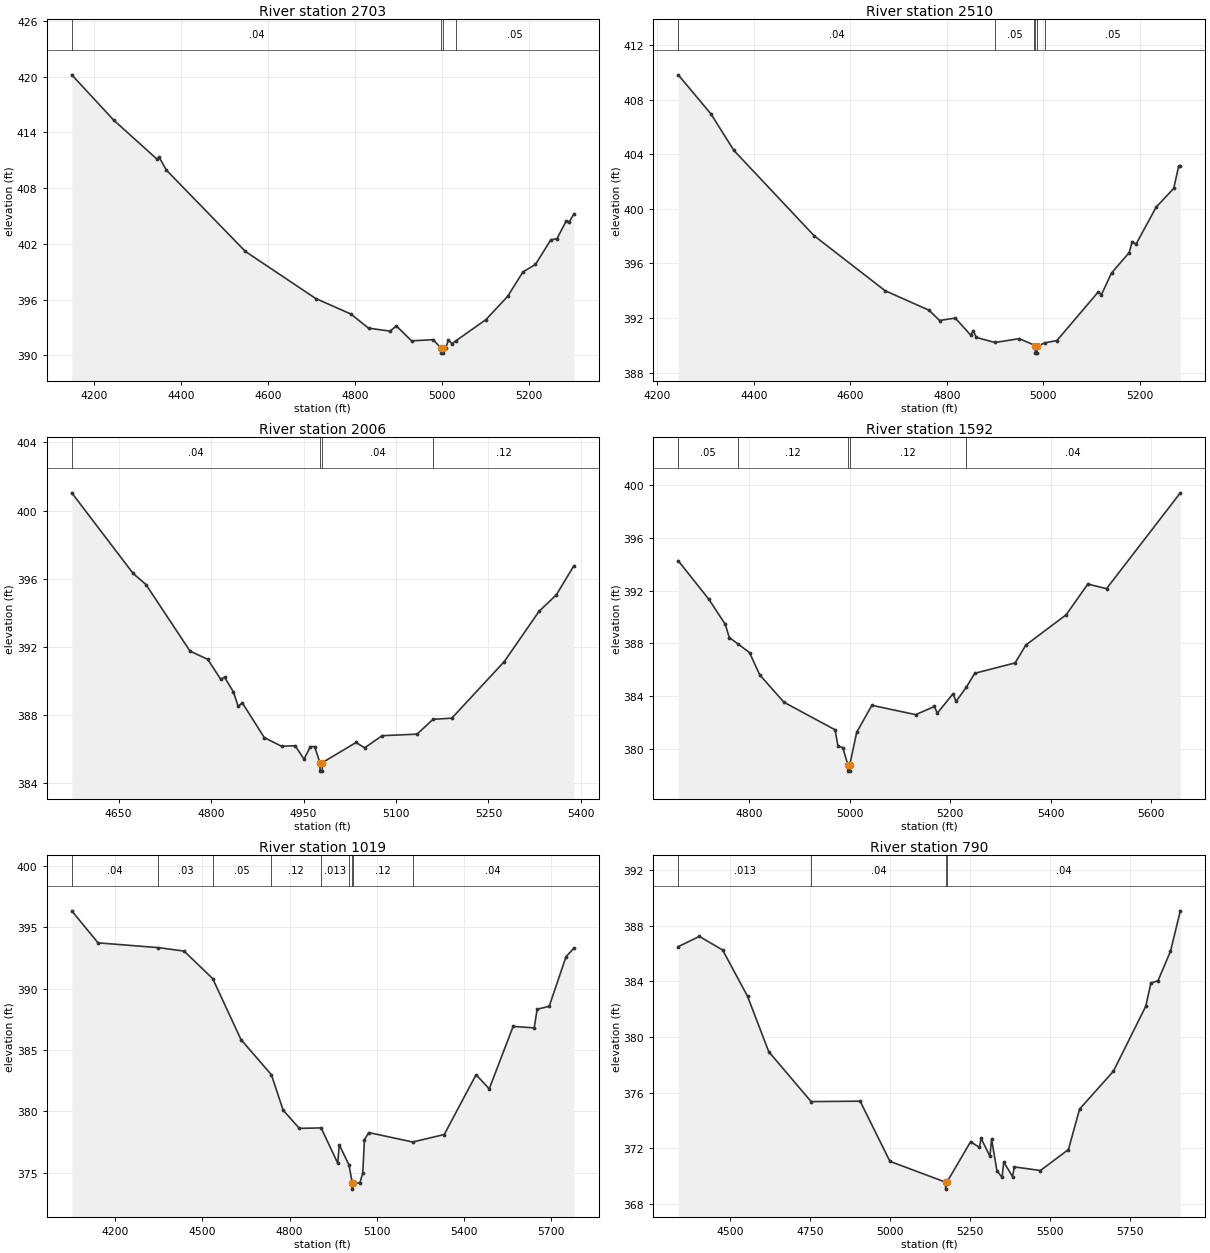
Type RM Length L Ch R = 1,2703,193,193,193
BEGIN DESCRIPTION:
Mapping XS 91563407
END DESCRIPTION:
XS GIS Cut Line= 3
      2415740.04     13570608.65      2415027.96     13570721.25
      2414687.10     13570992.11
#Sta/Elev= 30
  4147.9  420.21  4244.1  415.35  4344.5  411.12  4349.5  411.31  4365.6  409.96
  4547.8  401.19  4709.8  396.12  4790.8  394.45  4831.3  392.93  4880.9  392.61
  4895.4  393.17  4930.6  391.56  4980.3  391.69  4999.1  390.74  4999.3  390.24
  5002.8  390.24  5003.1  390.74  5009.1  390.80  5015.5  391.66  5023.5  391.26
  5033.3  391.59  5102.0  393.86  5151.7  396.35  5186.9  398.98  5215.8  399.79
  5251.0  402.43  5265.4  402.57  5286.2  404.44  5294.1  404.41  5304.2  405.21
#Mann=4,-1,0
  4147.9    0.04       0  4999.1    0.04       0  5003.1    0.04       0
  5033.3    0.05       0
Bank Sta=4999.1,5003.1
Exp/Cntr=0.3,0.1

Type RM Length L Ch R = 1,2510,504,504,504
BEGIN DESCRIPTION:
TRIB 8 TO SALT CREEK 4.0
END DESCRIPTION:
XS GIS Cut Line= 3
      2415475.04     13570324.98      2414875.00     13570575.00
      2414624.97     13570875.04
#Sta/Elev= 30
  4243.4  409.82  4311.1  406.96  4358.8  404.28  4525.1  398.03  4671.9  394.01
  4763.4  392.57  4785.1  391.82  4817.6  392.00  4849.6  390.75  4855.0  391.08
  4860.9  390.58  4900.1  390.21  4950.1  390.49  4979.9  390.04  4983.2  389.93
  4983.5  389.43  4987.0  389.43  4987.2  389.93  5003.6  390.19  5028.2  390.35
  5114.1  393.92  5120.6  393.72  5141.4  395.30  5177.9  396.79  5184.4  397.60
  5192.2  397.41  5233.8  400.12  5270.3  401.50  5280.7  403.14  5284.0  403.14
#Mann=6,-1,0
  4243.4    0.04       0  4900.1    0.05       0  4979.9    0.04       0
  4983.2    0.04       0  4987.2    0.04       0  5003.6    0.05       0
Bank Sta=4983.2,4987.2
Exp/Cntr=0.3,0.1

Type RM Length L Ch R = 1,2006,414,414,414
BEGIN DESCRIPTION:
TRIB 8 TO SALT CREEK 3.0
END DESCRIPTION:
XS GIS Cut Line= 3
      2414925.03     13569974.98      2414625.00     13570225.00
      2414325.01     13570524.99
#Sta/Elev= 30
  4573.9  401.04  4673.5  396.31  4694.3  395.66  4765.9  391.75  4794.6  391.27
  4815.4  390.11  4821.9  390.22  4836.2  389.36  4844.0  388.51  4850.6  388.72
  4886.3  386.68  4914.3  386.17  4936.5  386.20  4950.8  385.41  4961.2  386.15
  4968.0  386.15  4976.6  385.21  4976.8  384.71  4980.3  384.71  4980.6  385.21
  5035.2  386.39  5049.3  386.08  5077.6  386.79  5134.2  386.88  5160.2  387.75
  5190.7  387.82  5275.6  391.13  5332.1  394.08  5360.4  395.06  5388.7  396.76
#Mann=4,-1,0
  4573.9    0.04       0  4976.6    0.04       0  4980.6    0.04       0
  5160.2    0.12       0
Bank Sta=4976.6,4980.6
Exp/Cntr=0.3,0.1

Type RM Length L Ch R = 1,1592,573,573,573
BEGIN DESCRIPTION:
TRIB 8 TO SALT CREEK 2.0
END DESCRIPTION:
XS GIS Cut Line= 3
      2414725.00     13569825.00      2414425.00     13569875.00
      2414074.98     13570475.04
#Sta/Elev= 30
  4659.1  394.28  4719.9  391.36  4752.9  389.44  4760.5  388.45  4778.1  387.96
  4801.0  387.30  4821.3  385.61  4869.5  383.53  4971.1  381.44  4976.9  380.19
  4986.4  380.09  4996.4  378.80  4996.6  378.30  5000.1  378.30  5000.4  378.80
  5014.1  381.25  5044.3  383.30  5131.5  382.59  5168.7  383.21  5174.5  382.71
  5205.9  384.18  5211.7  383.59  5232.0  384.66  5248.9  385.73  5329.2  386.52
  5350.7  387.88  5430.9  390.18  5473.9  392.51  5511.1  392.16  5657.9  399.44
#Mann=5,-1,0
  4659.1    0.05       0  4778.1    0.12       0  4996.4    0.05       0
  5000.4    0.12       0  5232.0    0.04       0
Bank Sta=4996.4,5000.4
Exp/Cntr=0.3,0.1

Type RM Length L Ch R = 1,1019,229,229,229
BEGIN DESCRIPTION:
TRIB 8 TO SALT CREEK 1.0
END DESCRIPTION:
XS GIS Cut Line= 3
      2415064.47     13569382.27      2414125.00     13569525.00
      2413923.30     13570276.97
#Sta/Elev= 30
  4050.2  396.35  4140.7  393.74  4348.7  393.35  4436.8  393.07  4535.4  390.83
  4632.8  385.86  4737.6  382.99  4777.9  380.11  4833.8  378.62  4908.9  378.66
  4966.1  375.78  4971.2  377.29  5004.9  375.63  5015.9  374.17  5016.1  373.67
  5019.9  374.17  5041.9  374.17  5052.2  374.98  5057.9  377.69  5072.9  378.28
  5224.0  377.51  5332.7  378.12  5442.4  383.00  5487.6  381.84  5569.9  386.93
  5642.4  386.81  5652.7  388.33  5694.1  388.57  5752.1  392.61  5779.0  393.30
#Mann=9,-1,0
  4050.2    0.04       0  4348.7    0.03       0  4535.4    0.05       0
  4737.6    0.12       0  4908.9   0.013       0  5004.9    0.12       0
  5015.9    0.03       0  5019.9    0.12       0  5224.0    0.04       0
Bank Sta=5015.9,5019.9
Exp/Cntr=0.3,0.1

Type RM Length L Ch R = 1,790,0,0,0
BEGIN DESCRIPTION:
4898
END DESCRIPTION:
XS GIS Cut Line= 5
      2414538.14     13569228.30      2414131.75     13569349.28
      2413818.44     13569578.84      2413697.45     13569975.91
      2413851.80     13570281.52
#Sta/Elev= 30
  4337.8  386.50  4403.7  387.24  4476.7  386.26  4554.5  382.93  4620.9  378.94
  4753.3  375.35  4906.6  375.38  4999.7  371.05  5173.8  369.55  5174.0  369.05
  5177.8  369.55  5251.9  372.46  5279.5  372.06  5284.7  372.71  5312.3  371.42
  5317.6  372.65  5334.4  370.36  5350.4  369.90  5355.6  371.00  5383.2  369.95
  5388.5  370.65  5470.3  370.39  5557.9  371.90  5592.7  374.81  5698.6  377.54
  5799.6  382.21  5815.7  383.88  5838.0  384.05  5877.0  386.17  5907.7  389.08
#Mann=4,-1,0
  4337.8   0.013       0  4753.3    0.04       0  5173.8    0.04       0
  5177.8    0.04       0
Bank Sta=5173.8,5177.8
Exp/Cntr=0.3,0.1

Chan Stop Cuts=-1