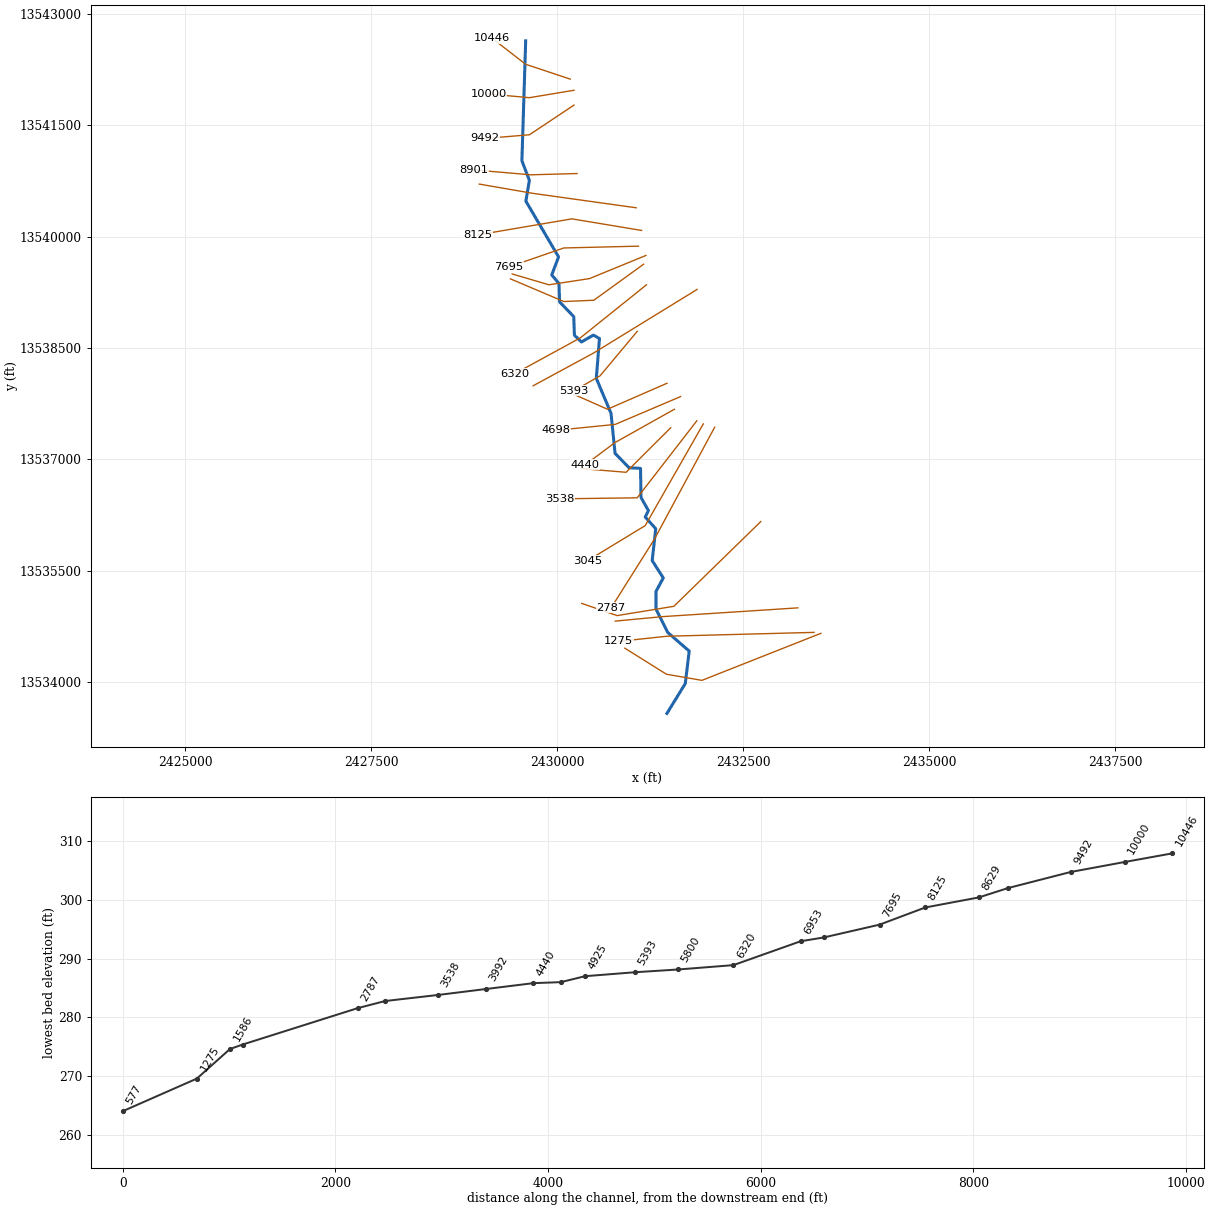
--- TRIB 8 TO SMITH CREEK.prj (project) ---

Proj Title=TRIB 8 TO SMITH CREEK Base Level Engineering
Current Plan=p01
Default Exp/Contr=0.3,0.1
English Units
Geom File=g01
Flow File=f01
Plan File=p01
BEGIN DESCRIPTION:
TRIB 8 TO SMITH CREEK
END DESCRIPTION:

--- TRIB 8 TO SMITH CREEK.p01 (plan) ---

Plan Title=Multiple Run
Short Identifier=Multiple
Geom File=g01
Flow File=f01
Subcritical Flow
K Sum by GR= 0
Std Step Tol= 0.01
Critical Tol= 0.01
Num of Std Step Trials= 20
Max Error Tol= 0.3
Flow Tol Ratio= 0.001
Split Flow NTrial= 30
Split Flow Tol= 0.02
Split Flow Ratio= 0.02
Log Output Level= 0
Friction Slope Method= 1
Unsteady Friction Slope Method= 2
Unsteady Bridges Friction Slope Method= 1
Parabolic Critical Depth
Global Vel Dist=  1 , 1 , 1
Global Log Level= 0
CheckData=True
Encroach Param= -1, 0, 0, 0
BEGIN DESCRIPTION:
Multiple Run
END DESCRIPTION:

--- TRIB 8 TO SMITH CREEK.f01 (steady flow) ---

Flow Title=Multiple
Number of Profiles=7
Profile Names=10-year,25-year,50-year,1pct_min,100-year,1pct_plu,500-year
River Rch & RM= TRIB 8 TO SMITH ,Reach-1,10446
     741    1208    1633    1069    2133    4255    3599
River Rch & RM= TRIB 8 TO SMITH ,Reach-1,6320
    1392    2345    3241    2163    4317    8613    7584
River Rch & RM= TRIB 8 TO SMITH ,Reach-1,4925
    1460    2463    3406    2274    4537    9053    7977
Boundary for River Rch & Prof#=TRIB 8 TO SMITH ,Reach-1,1
Up Type=0
Dn Type=3
Dn Slope=0.005
Boundary for River Rch & Prof#=TRIB 8 TO SMITH ,Reach-1,2
Up Type=0
Dn Type=3
Dn Slope=0.005
Boundary for River Rch & Prof#=TRIB 8 TO SMITH ,Reach-1,3
Up Type=0
Dn Type=3
Dn Slope=0.005
Boundary for River Rch & Prof#=TRIB 8 TO SMITH ,Reach-1,4
Up Type=0
Dn Type=3
Dn Slope=0.005
Boundary for River Rch & Prof#=TRIB 8 TO SMITH ,Reach-1,5
Up Type=0
Dn Type=3
Dn Slope=0.005
Boundary for River Rch & Prof#=TRIB 8 TO SMITH ,Reach-1,6
Up Type=0
Dn Type=3
Dn Slope=0.005
Boundary for River Rch & Prof#=TRIB 8 TO SMITH ,Reach-1,7
Up Type=0
Dn Type=3
Dn Slope=0.005

--- TRIB 8 TO SMITH CREEK.g01 (geometry) ---

Geom Title=Existing Conditions

River Reach=TRIB 8 TO SMITH ,Reach-1
Reach XY= 30
      2429575.00     13542640.99      2429524.21     13541025.01
      2429624.91     13540759.61      2429577.24     13540480.93
      2430017.21     13539728.42      2429925.60     13539485.62
      2430022.93     13539369.14      2430030.46     13539122.55
      2430221.47     13538923.54      2430230.31     13538672.44
      2430324.90     13538582.27      2430485.80     13538674.30
      2430567.11     13538628.66      2430525.09     13538090.39
      2430722.74     13537619.06      2430777.07     13537080.86
      2430964.95     13536886.11      2431119.64     13536877.78
      2431125.80     13536485.70      2431224.86     13536309.59
      2431182.82     13536221.59      2431323.95     13536064.57
      2431276.05     13535635.44      2431425.42     13535400.00
      2431327.24     13535219.07      2431327.24     13534980.93
      2431485.76     13534665.32      2431774.01     13534414.72
      2431721.18     13533976.58      2431475.00     13533575.00

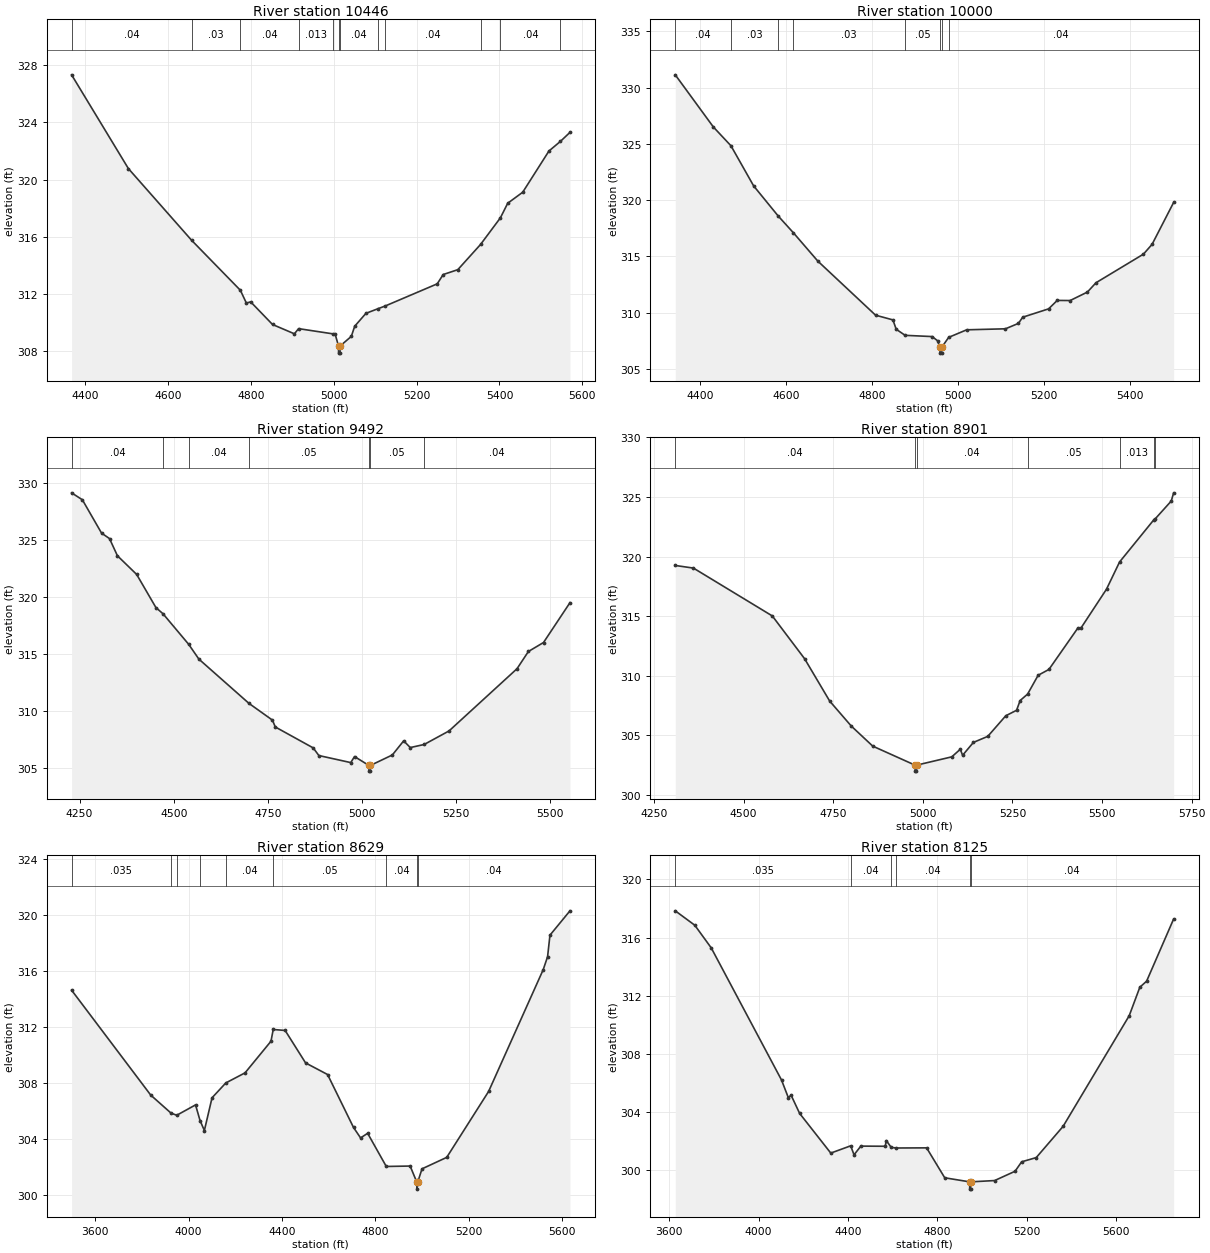
Type RM Length L Ch R = 1,10446,446,446,446
BEGIN DESCRIPTION:
TRIB 8 TO SMITH CREEK 20.0
END DESCRIPTION:
XS GIS Cut Line= 3
      2430175.04     13542124.99      2429575.00     13542325.00
      2429124.99     13542675.01
#Sta/Elev= 30
  4367.5  327.32  4504.6  320.77  4657.2  315.76  4774.8  312.27  4789.2  311.38
  4799.7  311.46  4852.4  309.88  4905.1  309.23  4915.3  309.59  4997.3  309.23
  5003.2  309.23  5011.6  308.38  5011.8  307.88  5015.3  307.88  5015.6  308.38
  5042.5  309.05  5050.7  309.76  5077.8  310.66  5107.5  310.99  5124.1  311.17
  5249.8  312.72  5264.2  313.37  5299.5  313.71  5354.3  315.47  5402.2  317.33
  5419.9  318.35  5456.1  319.12  5519.4  322.00  5547.0  322.67  5570.1  323.30
#Mann=12,-1,0
  4367.5    0.04       0  4657.2    0.03       0  4774.8    0.04       0
  4915.3   0.013       0  4997.3    0.04       0  5011.6    0.04       0
  5015.6    0.04       0  5107.5   0.013       0  5124.1    0.04       0
  5354.3    0.03       0  5402.2    0.04       0  5547.0    0.05       0
Bank Sta=5011.6,5015.6
Exp/Cntr=0.3,0.1

Type RM Length L Ch R = 1,10000,508,508,508
BEGIN DESCRIPTION:
TRIB 8 TO SMITH CREEK 19.0
END DESCRIPTION:
XS GIS Cut Line= 3
      2430225.02     13541975.00      2429625.00     13541875.00
      2429074.97     13541925.00
#Sta/Elev= 30
  4341.5  331.13  4430.2  326.50  4471.2  324.83  4524.0  321.27  4581.3  318.59
  4616.5  317.11  4673.5  314.59  4807.9  309.79  4848.4  309.37  4856.0  308.54
  4876.8  308.00  4939.7  307.89  4952.3  307.52  4957.8  306.92  4958.1  306.42
  4961.6  306.42  4961.8  306.92  4978.2  307.82  5020.1  308.49  5110.5  308.58
  5140.6  309.06  5150.6  309.61  5210.9  310.35  5231.0  311.10  5261.1  311.09
  5301.2  311.84  5321.3  312.67  5431.8  315.21  5451.9  316.08  5502.1  319.80
#Mann=8,-1,0
  4341.5    0.04       0  4471.2    0.03       0  4581.3    0.04       0
  4616.5    0.03       0  4876.8    0.05       0  4957.8    0.04       0
  4961.8    0.05       0  4978.2    0.04       0
Bank Sta=4957.8,4961.8
Exp/Cntr=0.3,0.1

Type RM Length L Ch R = 1,9492,591,591,591
BEGIN DESCRIPTION:
TRIB 8 TO SMITH CREEK 18.0
END DESCRIPTION:
XS GIS Cut Line= 3
      2430225.01     13541775.00      2429625.00     13541375.00
      2429025.00     13541325.00
#Sta/Elev= 30
  4228.8  329.17  4257.4  328.56  4308.4  325.63  4329.5  325.15  4350.5  323.64
  4401.6  322.00  4452.7  319.09  4471.7  318.54  4539.7  315.86  4566.8  314.56
  4699.8  310.67  4762.1  309.20  4769.6  308.60  4870.3  306.76  4885.3  306.09
  4970.0  305.47  4980.0  306.00  5018.2  305.22  5018.4  304.72  5021.9  304.72
  5022.2  305.22  5080.4  306.14  5110.5  307.38  5128.0  306.79  5164.8  307.06
  5230.9  308.25  5411.5  313.72  5441.6  315.23  5481.8  316.02  5552.0  319.52
#Mann=7,-1,0
  4228.8    0.04       0  4471.7   0.013       0  4539.7    0.04       0
  4699.8    0.05       0  5018.2    0.05       0  5022.2    0.05       0
  5164.8    0.04       0
Bank Sta=5018.2,5022.2
Exp/Cntr=0.3,0.1

Type RM Length L Ch R = 1,8901,272,272,272
BEGIN DESCRIPTION:
Mapping XS 5319f3b4
END DESCRIPTION:
XS GIS Cut Line= 3
      2430265.70     13540852.61      2429644.15     13540835.25
      2428878.37     13540901.09
#Sta/Elev= 30
  4309.4  319.25  4360.1  319.03  4580.2  315.01  4670.2  311.42  4740.3  307.86
  4800.3  305.77  4860.3  304.08  4978.5  302.48  4978.8  301.98  4982.3  301.98
  4982.5  302.48  5080.9  303.18  5104.7  303.82  5111.0  303.31  5141.1  304.39
  5181.3  304.90  5231.5  306.63  5261.6  307.09  5271.6  307.91  5292.4  308.45
  5321.8  310.03  5351.9  310.52  5432.2  313.98  5442.2  314.04  5512.5  317.26
  5548.9  319.54  5645.2  323.11  5647.6  323.14  5693.1  324.66  5699.8  325.35
#Mann=7,-1,0
  4309.4    0.04       0  4978.5    0.04       0  4982.5    0.04       0
  5292.4    0.05       0  5548.9   0.013       0  5645.2    0.05       0
  5647.6    0.04       0
Bank Sta=4978.5,4982.5
Exp/Cntr=0.3,0.1

Type RM Length L Ch R = 1,8629,504,504,504
BEGIN DESCRIPTION:
Mapping XS 5e6c8b76
END DESCRIPTION:
XS GIS Cut Line= 3
      2431060.77     13540390.81      2429671.92     13540585.25
      2428950.54     13540710.11
#Sta/Elev= 30
  3499.0  314.62  3838.0  307.12  3925.1  305.83  3949.5  305.68  4029.9  306.42
  4049.2  305.30  4067.7  304.59  4100.6  306.93  4159.6  307.99  4241.9  308.71
  4353.0  310.97  4362.6  311.81  4413.6  311.74  4501.2  309.42  4595.4  308.59
  4706.4  304.81  4736.7  304.06  4767.0  304.39  4846.8  302.02  4949.0  302.05
  4977.5  300.90  4977.7  300.40  4981.5  300.90  4999.8  301.85  5105.7  302.67
  5285.0  307.38  5519.0  316.09  5537.6  317.01  5547.8  318.55  5633.5  320.29
#Mann=9,-1,0
  3499.0   0.035       0  3925.1   0.013       0  3949.5    0.04       0
  4049.2   0.035       0  4159.6    0.04       0  4362.6    0.05       0
  4846.8    0.04       0  4977.5    0.04       0  4981.5    0.04       0
Bank Sta=4977.5,4981.5
Exp/Cntr=0.3,0.1

Type RM Length L Ch R = 1,8125,430,430,430
BEGIN DESCRIPTION:
Mapping XS 3f24795a
END DESCRIPTION:
XS GIS Cut Line= 3
      2431133.75     13540085.25      2430196.23     13540241.50
      2428935.83     13540026.23
#Sta/Elev= 30
  3627.3  317.84  3714.6  316.85  3788.2  315.29  4102.5  306.20  4132.9  304.99
  4145.5  305.15  4183.6  303.90  4322.9  301.17  4411.9  301.67  4426.9  301.05
  4457.3  301.65  4566.2  301.64  4571.3  302.03  4593.3  301.56  4615.9  301.52
  4751.5  301.53  4832.6  299.47  4944.2  299.19  4944.4  298.69  4947.9  298.69
  4948.2  299.19  5055.8  299.28  5147.1  299.92  5176.6  300.57  5241.8  300.86
  5362.0  303.01  5657.6  310.62  5705.1  312.58  5735.5  313.00  5856.4  317.28
#Mann=6,-1,0
  3627.3   0.035       0  4411.9    0.04       0  4593.3    0.05       0
  4615.9    0.04       0  4944.2    0.04       0  4948.2    0.04       0
Bank Sta=4944.2,4948.2
Exp/Cntr=0.3,0.1

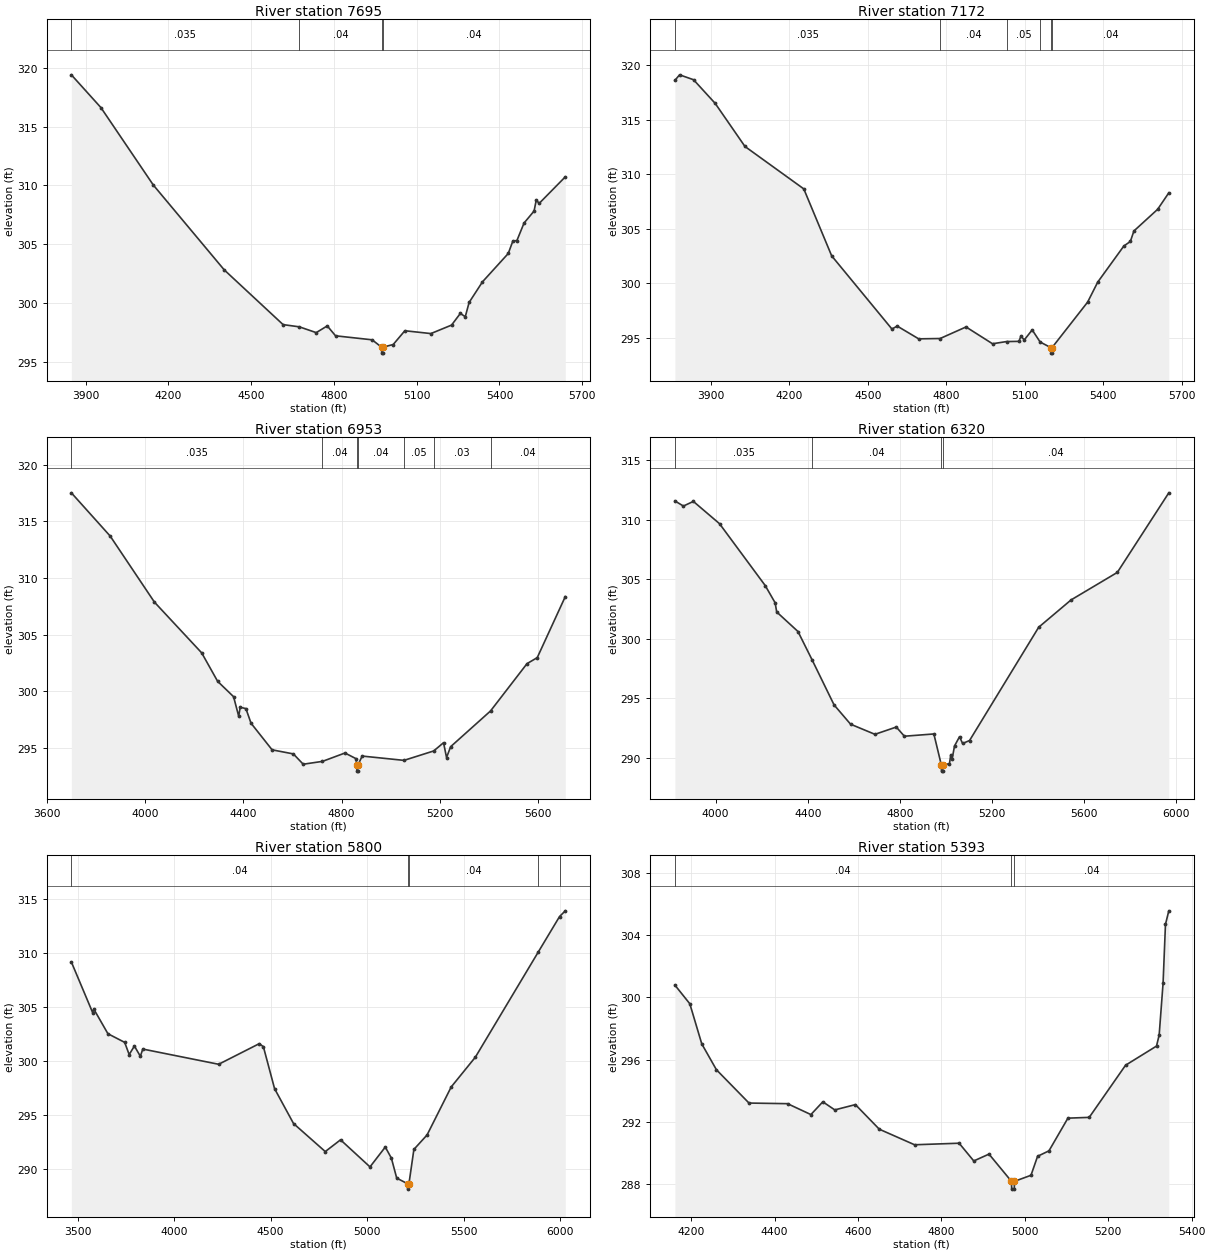
Type RM Length L Ch R = 1,7695,523,523,523
BEGIN DESCRIPTION:
Mapping XS 34afdf7b
END DESCRIPTION:
XS GIS Cut Line= 3
      2431092.10     13539873.45      2430088.59     13539849.14
      2429345.56     13539592.21
#Sta/Elev= 30
  3848.6  319.39  3955.7  316.61  4145.8  310.03  4402.4  302.84  4615.9  298.19
  4675.0  298.00  4736.0  297.51  4776.0  298.08  4806.0  297.24  4938.6  296.90
  4973.0  296.27  4973.3  295.77  4976.8  295.77  4977.0  296.27  5014.9  296.50
  5057.2  297.67  5151.5  297.43  5226.5  298.15  5258.3  299.14  5276.2  298.86
  5290.0  300.07  5338.5  301.82  5432.0  304.23  5448.7  305.29  5463.2  305.32
  5489.1  306.81  5525.5  307.83  5533.4  308.76  5544.0  308.48  5638.6  310.73
#Mann=4,-1,0
  3848.6   0.035       0  4675.0    0.04       0  4973.0    0.04       0
  4977.0    0.04       0
Bank Sta=4973,4977
Exp/Cntr=0.3,0.1

Type RM Length L Ch R = 1,7172,219,219,219
BEGIN DESCRIPTION:
Mapping XS 7321070f
END DESCRIPTION:
XS GIS Cut Line= 4
      2431192.79     13539748.46      2430432.34     13539435.95
      2429887.20     13539352.61      2429394.15     13539498.45
#Sta/Elev= 30
  3762.3  318.61  3780.3  319.12  3833.7  318.67  3916.4  316.50  4030.2  312.55
  4255.0  308.66  4361.6  302.52  4591.9  295.81  4612.1  296.08  4694.1  294.91
  4776.1  294.94  4875.1  296.00  4976.3  294.46  5029.9  294.66  5077.5  294.68
  5084.8  295.16  5097.7  294.81  5128.0  295.73  5158.3  294.62  5199.6  294.10
  5199.9  293.60  5203.4  293.60  5203.6  294.10  5339.9  298.28  5378.4  300.11
  5478.2  303.42  5503.2  303.84  5516.7  304.80  5607.5  306.79  5650.1  308.30
#Mann=6,-1,0
  3762.3   0.035       0  4776.1    0.04       0  5029.9    0.05       0
  5158.3    0.04       0  5199.6    0.04       0  5203.6    0.04       0
Bank Sta=5199.6,5203.6
Exp/Cntr=0.3,0.1

Type RM Length L Ch R = 1,6953,633,633,633
BEGIN DESCRIPTION:
Mapping XS 0b8b683e
END DESCRIPTION:
XS GIS Cut Line= 4
      2431161.52     13539630.40      2430491.37     13539144.28
      2430088.59     13539126.92      2429369.89     13539432.45
#Sta/Elev= 30
  3699.4  317.52  3857.6  313.70  4037.8  307.87  4230.3  303.39  4295.2  300.88
  4360.2  299.52  4381.0  297.80  4387.2  298.59  4410.4  298.47  4431.3  297.18
  4517.1  294.83  4603.7  294.47  4643.8  293.56  4722.1  293.81  4813.9  294.55
  4859.0  294.05  4862.0  293.45  4862.2  292.95  4865.7  292.95  4866.0  293.45
  4884.0  294.28  5054.3  293.90  5175.3  294.73  5215.5  295.46  5227.7  294.15
  5244.5  295.11  5406.8  298.26  5555.5  302.44  5597.2  302.97  5711.4  308.36
#Mann=7,-1,0
  3699.4   0.035       0  4722.1    0.04       0  4862.0    0.04       0
  4866.0    0.04       0  5054.3    0.05       0  5175.3    0.03       0
  5406.8    0.04       0
Bank Sta=4862,4866
Exp/Cntr=0.3,0.1

Type RM Length L Ch R = 1,6320,520,520,520
BEGIN DESCRIPTION:
TRIB 8 TO SMITH CREEK 12.0
END DESCRIPTION:
XS GIS Cut Line= 3
      2431199.71     13539352.62      2430311.30     13538638.18
      2429429.43     13538155.01
#Sta/Elev= 30
  3822.9  311.57  3860.0  311.14  3903.2  311.53  4016.8  309.66  4215.2  304.47
  4258.4  303.02  4265.2  302.25  4357.6  300.61  4418.7  298.24  4514.4  294.45
  4586.1  292.83  4692.0  291.98  4784.7  292.59  4819.9  291.82  4947.9  292.01
  4980.6  289.39  4981.1  288.89  4986.1  288.89  4986.6  289.39  5015.7  289.52
  5021.5  290.27  5027.2  289.90  5037.6  291.00  5059.4  291.78  5072.8  291.21
  5103.0  291.46  5403.4  300.97  5543.9  303.26  5744.9  305.57  5968.5  312.25
#Mann=4,-1,0
  3822.9   0.035       0  4418.7    0.04       0  4980.6    0.04       0
  4986.6    0.04       0
Bank Sta=4980.6,4986.6
Exp/Cntr=0.3,0.1

Type RM Length L Ch R = 1,5800,407,407,407
BEGIN DESCRIPTION:
Mapping XS fd2abed5
END DESCRIPTION:
XS GIS Cut Line= 3
      2431880.22     13539290.09      2430487.90     13538432.48
      2429675.41     13537991.51
#Sta/Elev= 30
  3467.5  309.20  3577.8  304.51  3583.6  304.84  3657.0  302.55  3743.8  301.75
  3767.1  300.62  3794.2  301.41  3825.0  300.46  3837.7  301.13  4230.8  299.72
  4441.3  301.63  4462.6  301.35  4520.6  297.46  4618.8  294.23  4783.3  291.63
  4862.5  292.72  5015.1  290.21  5094.4  292.05  5126.0  291.02  5153.6  289.17
  5209.9  288.65  5210.4  288.15  5217.0  288.65  5242.6  291.83  5310.9  293.17
  5436.0  297.62  5561.2  300.38  5887.4  310.13  5997.5  313.41  6027.2  313.94
#Mann=5,-1,0
  3467.5    0.04       0  5209.9    0.04       0  5217.0    0.04       0
  5887.4    0.05       0  5997.5   0.013       0
Bank Sta=5209.9,5217
Exp/Cntr=0.3,0.1

Type RM Length L Ch R = 1,5393,468,468,468
BEGIN DESCRIPTION:
TRIB 8 TO SMITH CREEK 10.0
END DESCRIPTION:
XS GIS Cut Line= 3
      2431075.02     13538725.02      2430575.00     13538125.00
      2430224.97     13537924.98
#Sta/Elev= 30
  4161.0  300.79  4196.8  299.59  4225.5  297.01  4260.6  295.35  4338.7  293.21
  4431.1  293.17  4487.1  292.47  4515.7  293.29  4544.4  292.77  4593.8  293.11
  4651.1  291.53  4735.7  290.53  4842.5  290.63  4877.6  289.49  4914.1  289.93
  4968.0  288.18  4968.5  287.68  4974.7  287.68  4975.2  288.18  5014.8  288.57
  5030.6  289.79  5057.9  290.14  5103.3  292.24  5154.4  292.29  5241.5  295.64
  5315.7  296.87  5322.1  297.58  5331.5  300.93  5337.2  304.69  5345.2  305.56
#Mann=3,-1,0
  4161.0    0.04       0  4968.0    0.04       0  4975.2    0.04       0
Bank Sta=4968,4975.2
Exp/Cntr=0.3,0.1

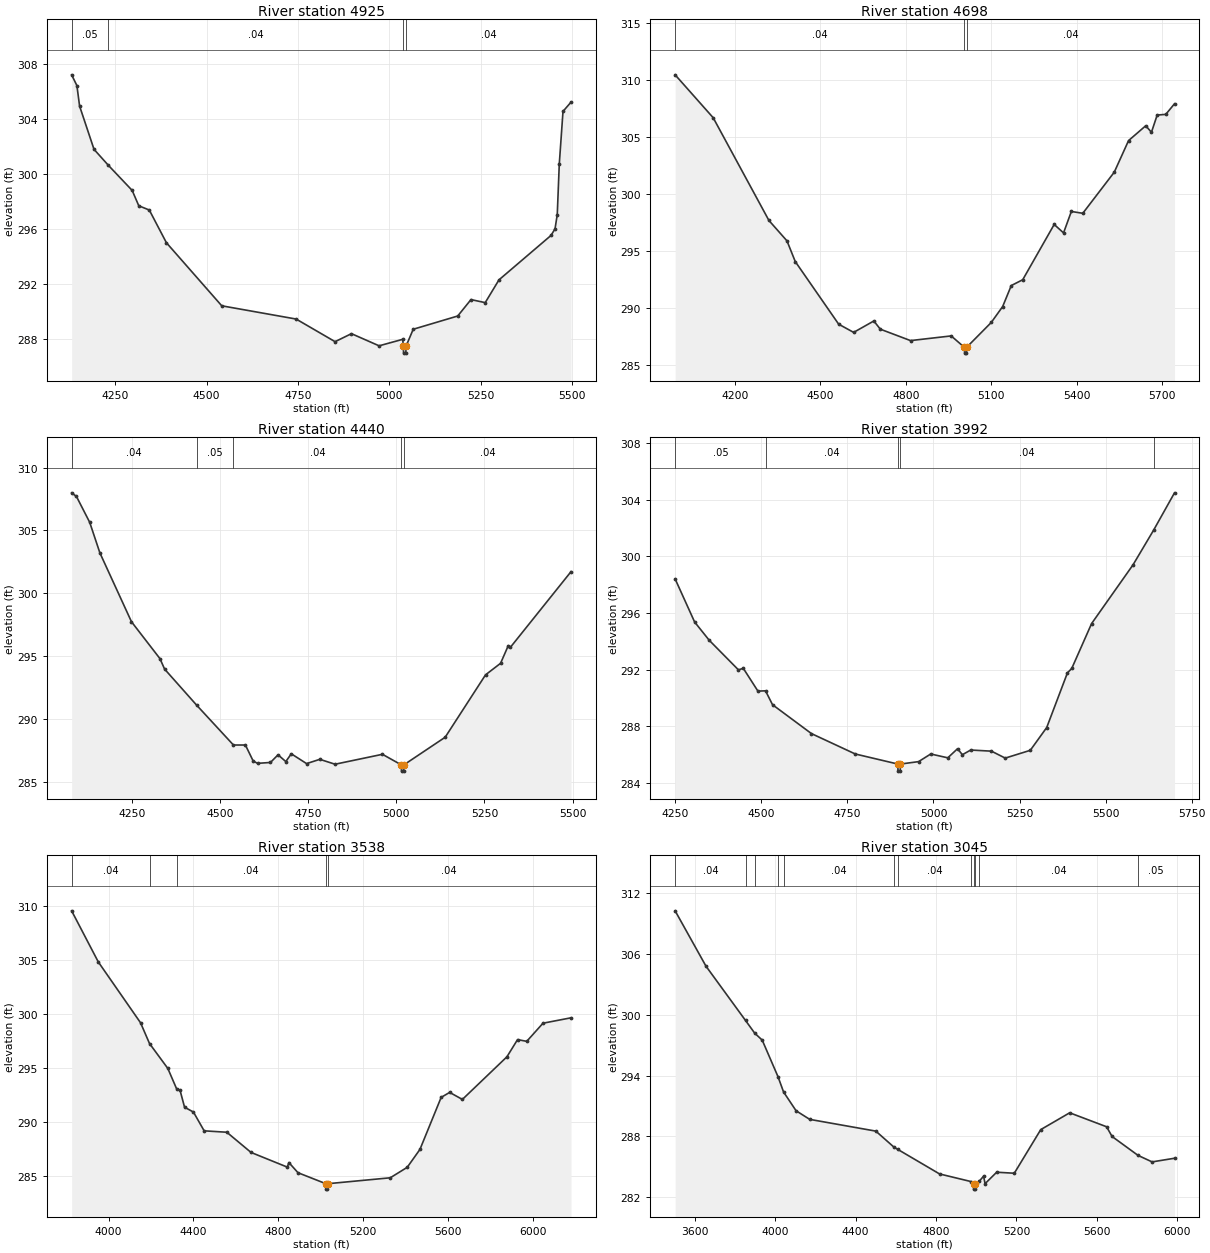
Type RM Length L Ch R = 1,4925,227,227,227
BEGIN DESCRIPTION:
TRIB 8 TO SMITH CREEK 9.0
END DESCRIPTION:
XS GIS Cut Line= 3
      2431474.97     13538024.99      2430675.00     13537675.00
      2430225.02     13537874.99
#Sta/Elev= 30
  4131.0  307.18  4145.4  306.40  4152.8  304.91  4192.2  301.78  4231.5  300.62
  4296.6  298.80  4314.6  297.69  4343.4  297.38  4390.2  295.01  4541.5  290.44
  4744.9  289.48  4851.4  287.84  4896.2  288.42  4971.8  287.54  5036.3  288.01
  5038.2  287.51  5038.7  287.01  5044.9  287.01  5045.4  287.51  5065.1  288.74
  5186.8  289.70  5223.0  290.89  5262.0  290.67  5299.6  292.32  5441.9  295.54
  5452.9  296.02  5459.0  297.05  5464.5  300.70  5474.7  304.53  5496.6  305.20
#Mann=4,-1,0
  4131.0    0.05       0  4231.5    0.04       0  5038.2    0.04       0
  5045.4    0.04       0
Bank Sta=5038.2,5045.4
Exp/Cntr=0.3,0.1

Type RM Length L Ch R = 1,4698,258,258,258
BEGIN DESCRIPTION:
Mapping XS f7139185
END DESCRIPTION:
XS GIS Cut Line= 3
      2431658.04     13537845.67      2430779.56     13537470.67
      2429984.43     13537390.81
#Sta/Elev= 30
  3990.0  310.42  4123.8  306.65  4319.5  297.64  4382.9  295.85  4411.9  294.04
  4564.5  288.54  4617.1  287.82  4688.0  288.82  4710.9  288.10  4816.9  287.10
  4959.8  287.51  5006.5  286.50  5007.0  286.00  5013.2  286.00  5013.7  286.50
  5100.5  288.69  5140.7  290.09  5170.9  291.93  5211.1  292.44  5321.6  297.29
  5354.5  296.55  5381.9  298.43  5422.1  298.27  5532.7  301.88  5582.9  304.65
  5643.2  305.95  5663.3  305.38  5683.4  306.89  5713.6  306.95  5744.3  307.88
#Mann=3,-1,0
  3990.0    0.04       0  5006.5    0.04       0  5013.7    0.04       0
Bank Sta=5006.5,5013.7
Exp/Cntr=0.3,0.1

Type RM Length L Ch R = 1,4440,448,448,448
BEGIN DESCRIPTION:
TRIB 8 TO SMITH CREEK 8.0
END DESCRIPTION:
XS GIS Cut Line= 3
      2431575.02     13537675.01      2430775.00     13537225.00
      2430375.00     13536925.00
#Sta/Elev= 30
  4077.8  308.00  4091.5  307.71  4129.1  305.65  4158.1  303.21  4247.7  297.73
  4328.6  294.79  4341.7  293.96  4433.2  291.07  4537.2  287.91  4571.2  287.91
  4593.2  286.64  4605.6  286.45  4642.3  286.52  4663.9  287.13  4685.9  286.59
  4701.5  287.21  4744.9  286.43  4782.5  286.77  4825.8  286.38  4960.3  287.17
  5013.9  286.33  5014.4  285.83  5020.7  285.83  5021.2  286.33  5138.4  288.53
  5253.0  293.50  5295.7  294.42  5317.6  295.83  5323.8  295.70  5495.7  301.72
#Mann=5,-1,0
  4077.8    0.04       0  4433.2    0.05       0  4537.2    0.04       0
  5013.9    0.04       0  5021.2    0.04       0
Bank Sta=5013.9,5021.2
Exp/Cntr=0.3,0.1

Type RM Length L Ch R = 1,3992,454,454,454
BEGIN DESCRIPTION:
TRIB 8 TO SMITH CREEK 7.0
END DESCRIPTION:
XS GIS Cut Line= 3
      2431525.03     13537425.03      2430925.00     13536825.00
      2430325.04     13536875.00
#Sta/Elev= 30
  4249.6  298.40  4306.2  295.36  4348.6  294.07  4433.5  291.98  4447.6  292.09
  4490.1  290.48  4512.2  290.50  4532.5  289.52  4645.6  287.48  4772.9  286.04
  4896.5  285.33  4897.0  284.83  4903.4  284.83  4903.9  285.33  4956.7  285.50
  4992.1  286.04  5041.6  285.77  5069.9  286.41  5084.0  285.99  5108.2  286.32
  5168.4  286.24  5208.5  285.75  5281.3  286.30  5329.0  287.91  5389.2  291.77
  5401.7  292.08  5459.4  295.25  5579.8  299.40  5639.4  301.84  5700.2  304.48
#Mann=5,-1,0
  4249.6    0.05       0  4512.2    0.04       0  4896.5    0.04       0
  4903.9    0.04       0  5639.4    0.03       0
Bank Sta=4896.5,4903.9
Exp/Cntr=0.3,0.1

Type RM Length L Ch R = 1,3538,493,493,493
BEGIN DESCRIPTION:
Mapping XS 6b2de980
END DESCRIPTION:
XS GIS Cut Line= 3
      2431876.79     13537519.29      2431074.70     13536481.09
      2430033.05     13536467.20
#Sta/Elev= 30
  3826.2  309.59  3951.7  304.86  4151.0  299.22  4193.2  297.30  4279.6  294.99
  4320.6  293.12  4337.1  292.97  4358.4  291.40  4400.3  290.95  4450.8  289.21
  4557.6  289.08  4671.7  287.21  4842.6  285.85  4850.2  286.27  4893.1  285.33
  5024.8  284.31  5025.3  283.81  5031.8  283.81  5032.3  284.31  5327.9  284.86
  5407.9  285.83  5467.9  287.49  5567.9  292.31  5607.9  292.77  5667.9  292.12
  5877.9  296.07  5927.9  297.66  5971.3  297.50  6047.9  299.18  6179.9  299.68
#Mann=5,-1,0
  3826.2    0.04       0  4193.2    0.05       0  4320.6    0.04       0
  5024.8    0.04       0  5032.3    0.04       0
Bank Sta=5024.8,5032.3
Exp/Cntr=0.3,0.1

Type RM Length L Ch R = 1,3045,258,258,258
BEGIN DESCRIPTION:
Mapping XS f85be124
END DESCRIPTION:
XS GIS Cut Line= 3
      2431963.58     13537477.60      2431182.34     13536106.09
      2430409.91     13535635.30
#Sta/Elev= 30
  3503.0  310.28  3656.5  304.81  3853.0  299.45  3898.9  298.19  3936.0  297.51
  4014.2  293.91  4042.1  292.39  4104.4  290.53  4172.3  289.68  4500.9  288.52
  4590.9  286.94  4609.6  286.72  4817.8  284.29  4975.7  283.53  4986.9  283.29
  4987.4  282.79  4994.0  282.79  4994.5  283.29  5016.2  283.59  5036.6  284.07
  5044.1  283.33  5101.7  284.46  5189.4  284.36  5321.0  288.67  5464.8  290.33
  5648.3  288.95  5675.6  287.99  5804.8  286.12  5874.6  285.48  5986.0  285.84
#Mann=12,-1,0
  3503.0    0.04       0  3853.0    0.05       0  3898.9    0.04       0
  4014.2   0.013       0  4042.1    0.04       0  4590.9   0.013       0
  4609.6    0.04       0  4975.7   0.013       0  4986.9    0.03       0
  4994.5   0.013       0  5016.2    0.04       0  5804.8    0.05       0
Bank Sta=4986.9,4994.5
Exp/Cntr=0.3,0.1

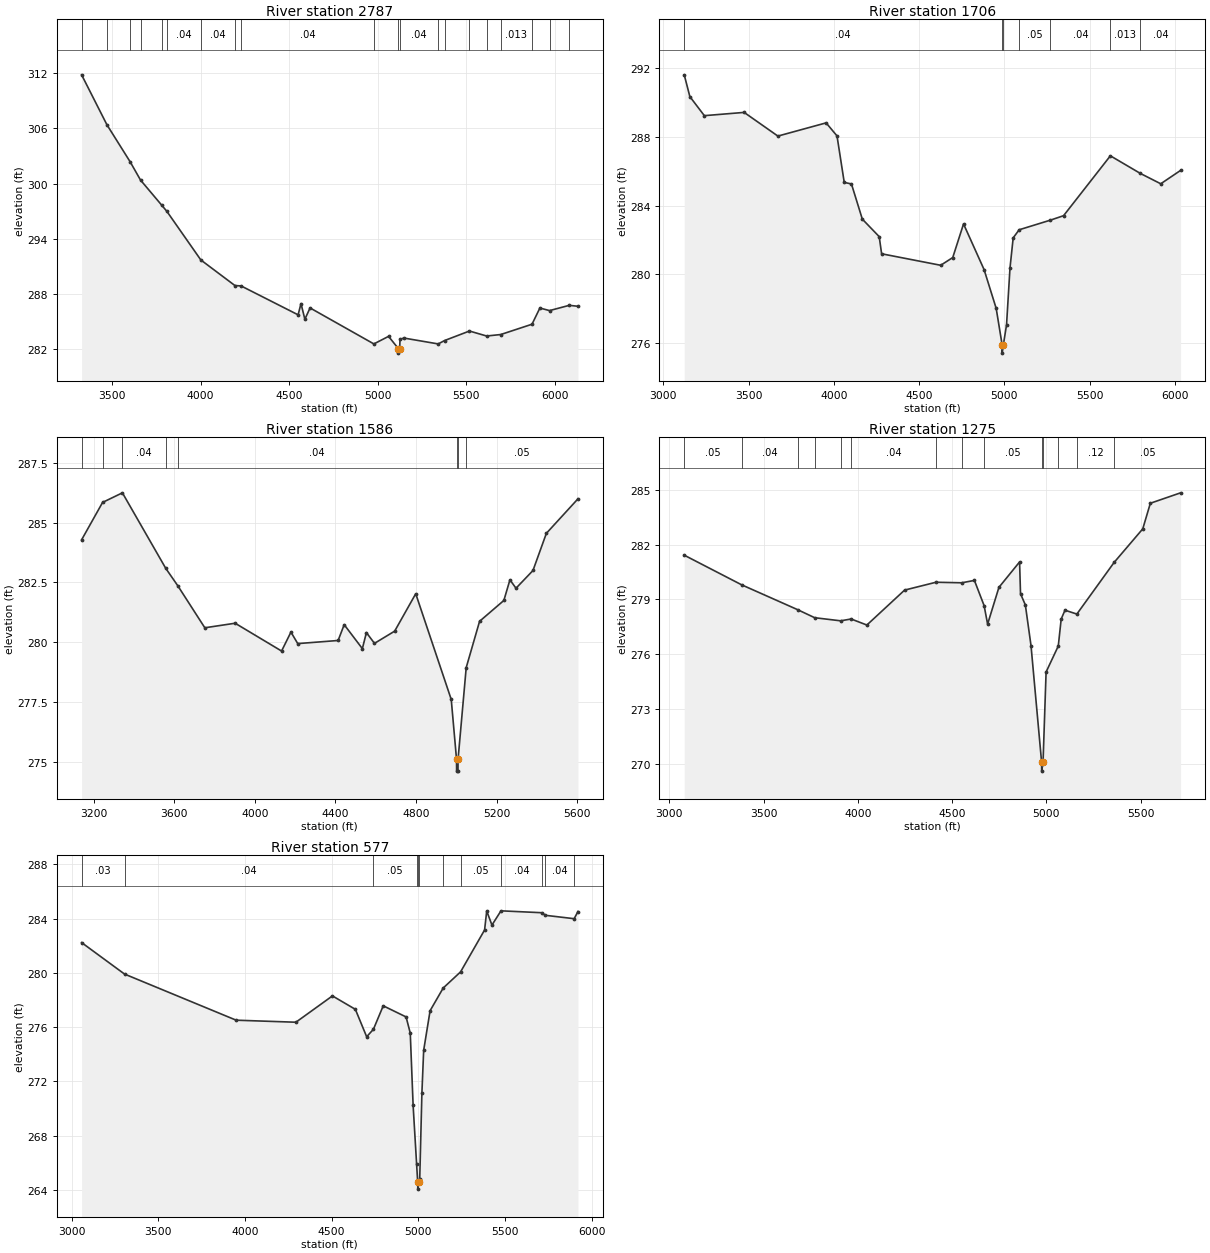
Type RM Length L Ch R = 1,2787,1081,1081,1081
BEGIN DESCRIPTION:
Mapping XS c7e6a0df
END DESCRIPTION:
XS GIS Cut Line= 3
      2432116.35     13537432.44      2431307.34     13535925.53
      2430724.96     13534998.65
#Sta/Elev= 30
  3327.4  311.81  3470.6  306.38  3601.8  302.36  3660.3  300.38  3780.9  297.63
  3809.2  296.98  4001.2  291.70  4193.9  288.92  4228.5  288.88  4550.9  285.74
  4567.2  286.96  4589.1  285.26  4618.4  286.49  4979.0  282.58  5062.0  283.40
  5117.1  282.08  5117.6  281.58  5124.8  282.08  5126.8  283.07  5148.0  283.22
  5342.5  282.58  5379.0  282.95  5519.2  283.98  5616.2  283.44  5696.0  283.60
  5872.7  284.72  5917.2  286.48  5971.8  286.20  6083.0  286.77  6132.4  286.67
#Mann=20,-1,0
  3327.4   0.013       0  3470.6    0.03       0  3601.8   0.013       0
  3660.3    0.03       0  3780.9    0.05       0  3809.2    0.04       0
  4001.2    0.04       0  4193.9   0.013       0  4228.5    0.04       0
  4979.0    0.04       0  5117.1    0.04       0  5124.8    0.04       0
  5342.5   0.013       0  5379.0    0.04       0  5519.2   0.013       0
  5616.2    0.04       0  5696.0   0.013       0  5872.7   0.013       0
  5971.8    0.04       0  6083.0   0.013       0
Bank Sta=5117.1,5124.8
Exp/Cntr=0.3,0.1

Type RM Length L Ch R = 1,1706,120,120,120
BEGIN DESCRIPTION:
Mapping XS 1876c01c
END DESCRIPTION:
XS GIS Cut Line= 4
      2432736.27     13536160.47      2431567.76     13535018.41
      2430804.81     13534893.08      2430328.72     13535057.55
#Sta/Elev= 30
  3123.0  291.62  3156.0  290.35  3240.9  289.24  3474.4  289.43  3672.2  288.05
  3955.1  288.82  4018.9  288.06  4061.3  285.35  4103.6  285.26  4167.3  283.21
  4266.3  282.19  4280.5  281.19  4626.9  280.52  4697.6  280.97  4760.9  282.93
  4881.3  280.27  4952.3  278.01  4987.0  275.90  4987.5  275.40  4994.7  275.90
  5013.1  277.05  5033.3  280.36  5052.1  282.12  5087.1  282.59  5270.1  283.15
  5347.5  283.41  5622.0  286.90  5798.4  285.87  5917.4  285.27  6033.8  286.05
#Mann=7,-1,0
  3123.0    0.04       0  4987.0    0.04       0  4994.7    0.04       0
  5087.1    0.05       0  5270.1    0.04       0  5622.0   0.013       0
  5798.4    0.04       0
Bank Sta=4987,4994.7
Exp/Cntr=0.3,0.1

Type RM Length L Ch R = 1,1586,311,311,311
BEGIN DESCRIPTION:
Mapping XS 43e8f23f
END DESCRIPTION:
XS GIS Cut Line= 3
      2433235.16     13534997.41      2431420.19     13534879.52
      2430778.95     13534818.87
#Sta/Elev= 30
  3140.5  284.28  3244.6  285.84  3342.9  286.24  3558.0  283.09  3618.0  282.36
  3751.9  280.61  3902.3  280.80  4132.7  279.64  4179.2  280.43  4212.9  279.95
  4413.3  280.08  4443.4  280.74  4533.6  279.74  4553.6  280.41  4593.7  279.96
  4693.9  280.47  4798.4  282.03  4974.6  277.62  5000.8  275.13  5001.3  274.63
  5008.0  274.63  5008.5  275.13  5048.9  278.95  5115.2  280.88  5235.7  281.75
  5265.8  282.61  5296.0  282.26  5380.2  283.00  5446.6  284.55  5603.4  285.99
#Mann=8,-1,0
  3140.5    0.04       0  3244.6    0.05       0  3342.9    0.04       0
  3558.0    0.05       0  3618.0    0.04       0  5000.8    0.04       0
  5008.5    0.04       0  5048.9    0.05       0
Bank Sta=5000.8,5008.5
Exp/Cntr=0.3,0.1

Type RM Length L Ch R = 1,1275,698,698,698
BEGIN DESCRIPTION:
Mapping XS 0d852efa
END DESCRIPTION:
XS GIS Cut Line= 3
      2433453.04     13534666.90      2431472.27     13534614.77
      2430825.54     13534545.32
#Sta/Elev= 30
  3079.7  281.42  3383.9  279.80  3680.9  278.44  3771.4  278.00  3909.0  277.83
  3964.6  277.93  4048.1  277.60  4248.1  279.51  4414.7  279.94  4551.2  279.91
  4618.3  280.04  4669.8  278.66  4688.3  277.65  4748.3  279.66  4857.8  281.05
  4862.8  279.31  4888.4  278.70  4918.4  276.48  4974.5  270.11  4975.0  269.61
  4982.3  270.11  4998.4  275.03  5063.0  276.45  5078.5  277.93  5098.6  278.41
  5161.6  278.20  5358.8  281.02  5511.0  282.86  5551.2  284.26  5711.6  284.83
#Mann=14,-1,0
  3079.7    0.05       0  3383.9    0.04       0  3680.9    0.05       0
  3771.4    0.04       0  3909.0    0.05       0  3964.6    0.04       0
  4414.7    0.05       0  4551.2    0.04       0  4669.8    0.05       0
  4974.5    0.05       0  4982.3    0.05       0  5063.0    0.04       0
  5161.6    0.12       0  5358.8    0.05       0
Bank Sta=4974.5,4982.3
Exp/Cntr=0.3,0.1

Type RM Length L Ch R = 1,577,0,0,0
BEGIN DESCRIPTION:
Mapping XS 9fdb13bc
END DESCRIPTION:
XS GIS Cut Line= 4
      2433544.25     13534653.90      2431945.36     13534020.15
      2431467.93     13534102.61      2430908.99     13534453.58
#Sta/Elev= 30
  3057.0  282.23  3304.6  279.91  3949.0  276.51  4293.7  276.36  4504.5  278.30
  4636.8  277.31  4702.0  275.29  4741.0  275.84  4797.6  277.57  4929.5  276.75
  4953.6  275.56  4970.1  270.23  4990.3  265.89  4996.6  264.56  4997.1  264.06
  5004.4  264.56  5008.3  264.84  5020.8  271.15  5031.0  274.29  5068.1  277.21
  5143.6  278.88  5243.9  280.07  5382.6  283.16  5394.8  284.56  5425.0  283.52
  5477.2  284.57  5713.7  284.43  5733.1  284.24  5899.4  283.99  5921.4  284.52
#Mann=12,-1,0
  3057.0    0.03       0  3304.6    0.04       0  4741.0    0.05       0
  4990.3    0.12       0  4996.6    0.05       0  5004.4    0.12       0
  5143.6    0.12       0  5243.9    0.05       0  5477.2    0.04       0
  5713.7    0.05       0  5733.1    0.04       0  5899.4    0.05       0
Bank Sta=4996.6,5004.4
Exp/Cntr=0.3,0.1

Chan Stop Cuts=-1