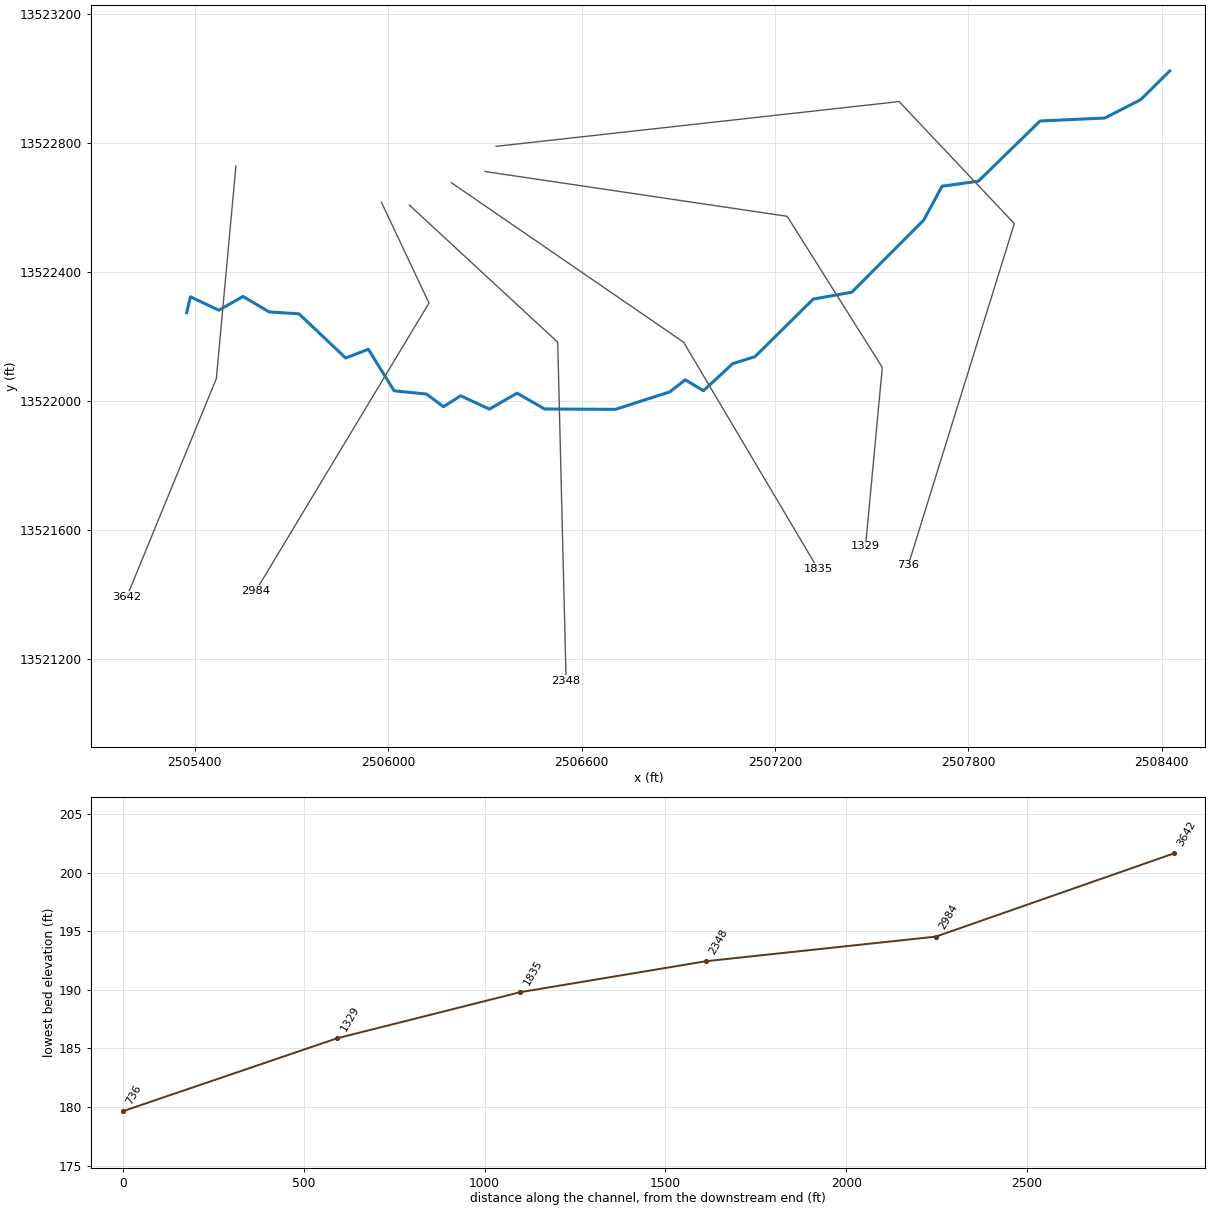
--- TRIB 8 TO TWELVEMILE CREEK.prj (project) ---

Proj Title=TRIB 8 TO TWELVEMILE CREEK Base Level Engineering
Current Plan=p01
Default Exp/Contr=0.3,0.1
English Units
Geom File=g01
Flow File=f01
Plan File=p01
BEGIN DESCRIPTION:
TRIB 8 TO TWELVEMILE CREEK
END DESCRIPTION:

--- TRIB 8 TO TWELVEMILE CREEK.p01 (plan) ---

Plan Title=Multiple Run
Short Identifier=Multiple
Geom File=g01
Flow File=f01
Subcritical Flow
K Sum by GR= 0
Std Step Tol= 0.01
Critical Tol= 0.01
Num of Std Step Trials= 20
Max Error Tol= 0.3
Flow Tol Ratio= 0.001
Split Flow NTrial= 30
Split Flow Tol= 0.02
Split Flow Ratio= 0.02
Log Output Level= 0
Friction Slope Method= 1
Unsteady Friction Slope Method= 2
Unsteady Bridges Friction Slope Method= 1
Parabolic Critical Depth
Global Vel Dist=  1 , 1 , 1
Global Log Level= 0
CheckData=True
Encroach Param= -1, 0, 0, 0
BEGIN DESCRIPTION:
Multiple Run
END DESCRIPTION:

--- TRIB 8 TO TWELVEMILE CREEK.f01 (steady flow) ---

Flow Title=Multiple
Number of Profiles=7
Profile Names=10-year,25-year,50-year,1pct_min,100-year,1pct_plu,500-year
River Rch & RM= TRIB 8 TO TWELVE,Reach-1,3642
     517     820    1089     701    1399    2792    2283
River Rch & RM= TRIB 8 TO TWELVE,Reach-1,1835
     533     848    1127     726    1449    2891    2367
Boundary for River Rch & Prof#=TRIB 8 TO TWELVE,Reach-1,1
Up Type=0
Dn Type=3
Dn Slope=0.005
Boundary for River Rch & Prof#=TRIB 8 TO TWELVE,Reach-1,2
Up Type=0
Dn Type=3
Dn Slope=0.005
Boundary for River Rch & Prof#=TRIB 8 TO TWELVE,Reach-1,3
Up Type=0
Dn Type=3
Dn Slope=0.005
Boundary for River Rch & Prof#=TRIB 8 TO TWELVE,Reach-1,4
Up Type=0
Dn Type=3
Dn Slope=0.005
Boundary for River Rch & Prof#=TRIB 8 TO TWELVE,Reach-1,5
Up Type=0
Dn Type=3
Dn Slope=0.005
Boundary for River Rch & Prof#=TRIB 8 TO TWELVE,Reach-1,6
Up Type=0
Dn Type=3
Dn Slope=0.005
Boundary for River Rch & Prof#=TRIB 8 TO TWELVE,Reach-1,7
Up Type=0
Dn Type=3
Dn Slope=0.005

--- TRIB 8 TO TWELVEMILE CREEK.g01 (geometry) ---

Geom Title=Existing Conditions

River Reach=TRIB 8 TO TWELVE,Reach-1
Reach XY= 30
      2505375.00     13522275.00      2505386.76     13522324.22
      2505474.98     13522282.58      2505549.96     13522325.31
      2505630.97     13522277.38      2505723.50     13522271.39
      2505868.34     13522134.31      2505938.68     13522161.49
      2506018.55     13522032.75      2506119.10     13522022.45
      2506171.78     13521983.27      2506224.92     13522017.17
      2506314.30     13521975.83      2506400.00     13522025.39
      2506485.50     13521976.24      2506704.97     13521975.07
      2506873.50     13522029.08      2506921.78     13522066.71
      2506978.33     13522033.01      2507068.95     13522116.80
      2507138.21     13522138.63      2507318.83     13522317.14
      2507438.30     13522338.40      2507661.36     13522561.80
      2507718.55     13522667.25      2507831.17     13522682.86
      2508022.55     13522869.54      2508223.45     13522878.75
      2508334.71     13522935.70      2508425.00     13523025.00

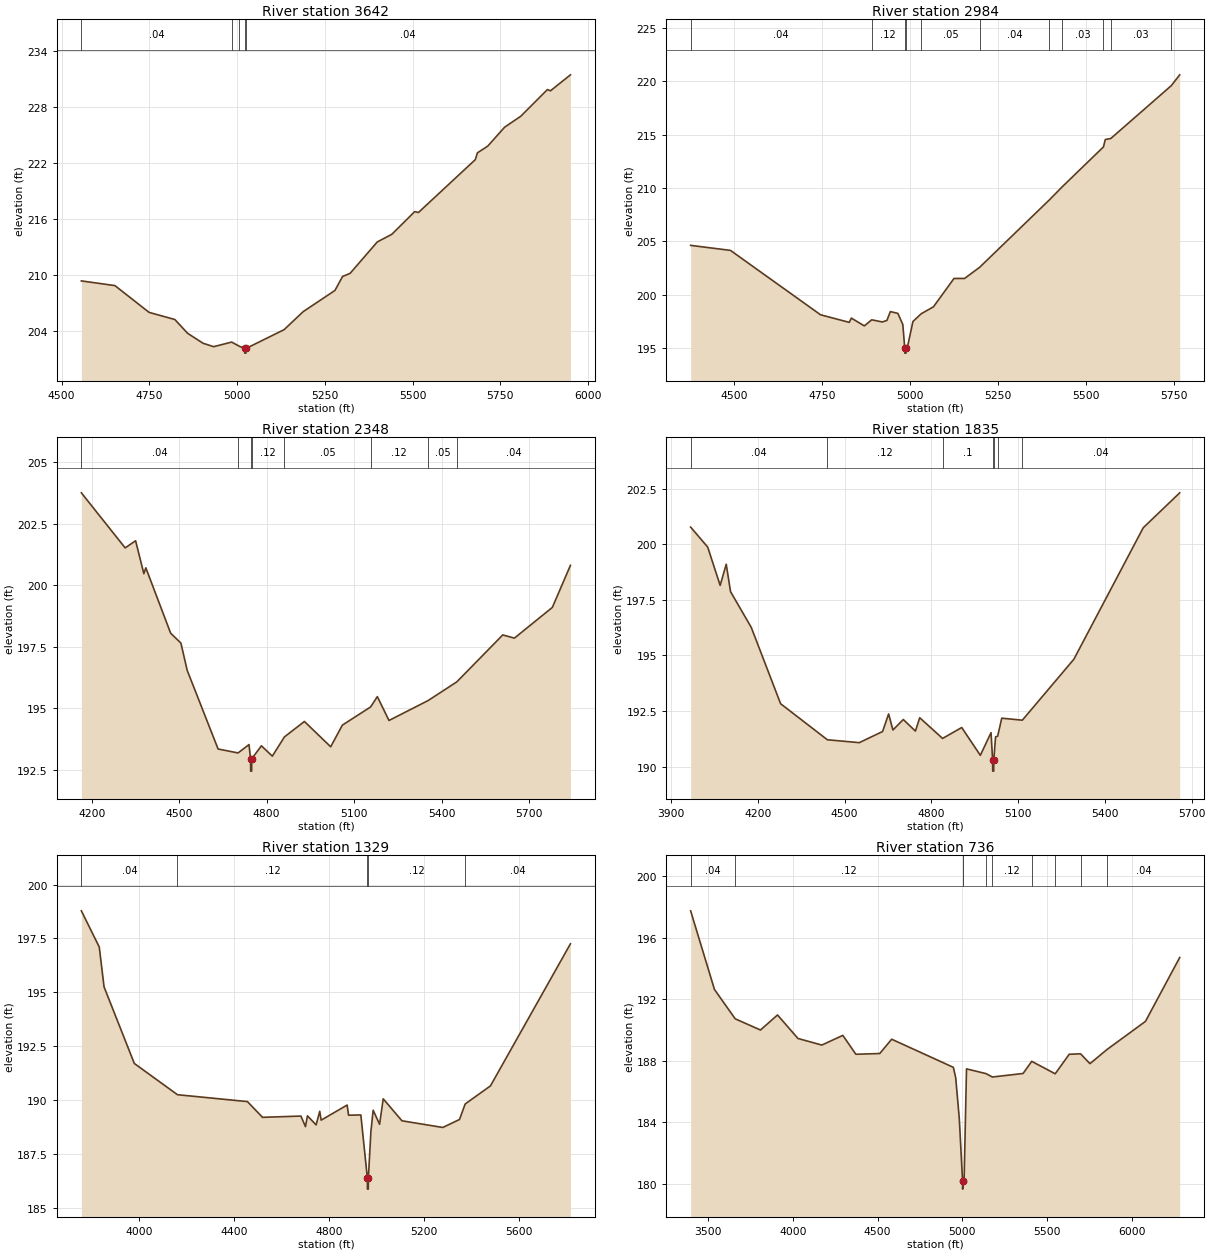
Type RM Length L Ch R = 1,3642,658,658,658
BEGIN DESCRIPTION:
LGII4566
END DESCRIPTION:
XS GIS Cut Line= 3
      2505527.89     13522730.18      2505467.13     13522070.46
      2505189.68     13521394.17
#Sta/Elev= 30
  4556.2  209.37  4651.8  208.87  4749.2  206.00  4822.5  205.24  4859.0  203.76
  4902.8  202.70  4933.0  202.33  4984.4  202.82  5006.6  202.37  5021.3  202.14
  5021.6  201.64  5025.1  201.64  5025.3  202.14  5133.8  204.15  5188.2  206.08
  5278.7  208.35  5300.3  209.84  5321.9  210.18  5399.3  213.54  5440.8  214.36
  5506.0  216.79  5516.5  216.69  5678.6  222.35  5684.7  223.08  5714.1  223.80
  5762.0  225.82  5808.3  227.00  5884.0  229.85  5892.8  229.72  5949.7  231.43
#Mann=5,-1,0
  4556.2    0.04       0  4984.4    0.12       0  5006.6    0.04       0
  5021.3    0.05       0  5025.3    0.04       0
Bank Sta=5021.3,5025.3
Exp/Cntr=0.3,0.1

Type RM Length L Ch R = 1,2984,636,636,636
BEGIN DESCRIPTION:
LGII4565
END DESCRIPTION:
XS GIS Cut Line= 3
      2505979.30     13522617.31      2506126.85     13522304.84
      2505589.35     13521411.89
#Sta/Elev= 30
  4377.3  204.63  4490.4  204.16  4746.0  198.13  4827.5  197.42  4833.3  197.82
  4870.2  197.09  4891.1  197.66  4921.1  197.46  4934.3  197.60  4944.0  198.43
  4965.4  198.26  4979.4  197.22  4984.8  195.04  4985.0  194.54  4988.5  194.54
  4988.8  195.04  4992.6  195.12  5008.1  197.50  5031.3  198.22  5066.4  198.88
  5124.6  201.53  5154.5  201.53  5197.5  202.58  5395.6  208.90  5431.6  210.11
  5548.7  213.85  5553.9  214.54  5569.7  214.64  5741.3  219.59  5765.1  220.60
#Mann=11,-1,0
  4377.3    0.04       0  4891.1    0.12       0  4984.8    0.05       0
  4988.8    0.12       0  5031.3    0.05       0  5197.5    0.04       0
  5395.6    0.05       0  5431.6    0.03       0  5548.7    0.04       0
  5569.7    0.03       0  5741.3    0.04       0
Bank Sta=4984.8,4988.8
Exp/Cntr=0.3,0.1

Type RM Length L Ch R = 1,2348,513,513,513
BEGIN DESCRIPTION:
LGII4564
END DESCRIPTION:
XS GIS Cut Line= 3
      2506066.09     13522608.66      2506526.16     13522183.31
      2506552.20     13521133.00
#Sta/Elev= 30
  4164.7  203.76  4314.9  201.52  4350.7  201.81  4379.0  200.47  4385.8  200.71
  4470.9  198.05  4506.0  197.65  4527.6  196.54  4633.6  193.34  4702.1  193.18
  4739.6  193.52  4745.0  192.94  4745.2  192.44  4748.7  192.44  4749.0  192.94
  4782.1  193.47  4819.6  193.05  4861.0  193.83  4929.6  194.46  5019.7  193.43
  5059.7  194.31  5156.6  195.05  5179.7  195.47  5219.7  194.50  5353.7  195.31
  5452.2  196.07  5609.8  197.98  5649.8  197.85  5779.9  199.10  5841.9  200.81
#Mann=8,-1,0
  4164.7    0.04       0  4702.1    0.12       0  4745.0    0.05       0
  4749.0    0.12       0  4861.0    0.05       0  5156.6    0.12       0
  5353.7    0.05       0  5452.2    0.04       0
Bank Sta=4745,4749
Exp/Cntr=0.3,0.1

Type RM Length L Ch R = 1,1835,506,506,506
BEGIN DESCRIPTION:
LGII4563
END DESCRIPTION:
XS GIS Cut Line= 3
      2506196.28     13522678.11      2506916.78     13522183.31
      2507333.48     13521480.14
#Sta/Elev= 30
  3967.4  200.77  4026.5  199.87  4069.5  198.15  4090.5  199.10  4105.4  197.87
  4177.1  196.26  4278.6  192.83  4440.3  191.21  4550.6  191.08  4631.2  191.58
  4652.1  192.37  4667.0  191.65  4702.9  192.12  4744.8  191.60  4759.7  192.20
  4838.7  191.27  4905.0  191.76  4969.3  190.51  5006.3  191.53  5011.8  190.30
  5012.1  189.80  5015.6  189.80  5015.8  190.30  5022.0  191.34  5029.2  191.37
  5043.4  192.18  5114.6  192.09  5292.8  194.83  5532.7  200.74  5658.8  202.31
#Mann=7,-1,0
  3967.4    0.04       0  4440.3    0.12       0  4838.7     0.1       0
  5011.8    0.05       0  5015.8     0.1       0  5029.2    0.12       0
  5114.6    0.04       0
Bank Sta=5011.8,5015.8
Exp/Cntr=0.3,0.1

Type RM Length L Ch R = 1,1329,593,593,593
BEGIN DESCRIPTION:
LGII4562
END DESCRIPTION:
XS GIS Cut Line= 4
      2506300.44     13522712.83      2507237.96     13522573.94
      2507533.10     13522105.19      2507481.04     13521549.81
#Sta/Elev= 30
  3757.9  198.78  3833.3  197.10  3853.5  195.25  3980.9  191.70  4162.6  190.25
  4457.3  189.93  4520.7  189.20  4682.4  189.26  4701.6  188.77  4709.9  189.27
  4746.4  188.85  4761.7  189.48  4767.6  189.07  4877.1  189.77  4883.0  189.30
  4934.8  189.31  4962.4  186.37  4962.6  185.87  4966.1  185.87  4966.4  186.37
  4977.2  188.55  4986.6  189.53  5013.7  188.88  5029.0  190.06  5107.9  189.04
  5279.9  188.73  5350.2  189.10  5374.1  189.82  5480.7  190.66  5817.4  197.25
#Mann=5,-1,0
  3757.9    0.04       0  4162.6    0.12       0  4962.4    0.05       0
  4966.4    0.12       0  5374.1    0.04       0
Bank Sta=4962.4,4966.4
Exp/Cntr=0.3,0.1

Type RM Length L Ch R = 1,736,0,0,0
BEGIN DESCRIPTION:
LGII4561
END DESCRIPTION:
XS GIS Cut Line= 4
      2506335.16     13522790.95      2507585.19     13522929.84
      2507942.60     13522551.23      2507613.57     13521491.82
#Sta/Elev= 30
  3396.4  197.76  3537.1  192.64  3659.6  190.73  3808.8  190.00  3909.4  190.98
  4030.1  189.45  4171.0  189.02  4295.1  189.65  4372.2  188.42  4513.1  188.47
  4583.5  189.40  4947.6  187.57  4961.7  186.88  4982.8  184.22  5002.2  180.14
  5002.5  179.64  5006.2  180.14  5011.1  180.24  5025.3  187.47  5140.6  187.16
  5178.2  186.94  5359.3  187.17  5410.5  187.96  5549.0  187.15  5631.6  188.42
  5698.9  188.45  5754.3  187.81  5854.8  188.73  6081.8  190.56  6284.1  194.72
#Mann=10,-1,0
  3396.4    0.04       0  3659.6    0.12       0  5002.2    0.05       0
  5006.2    0.12       0  5140.6    0.05       0  5178.2    0.12       0
  5410.5    0.05       0  5549.0    0.04       0  5698.9    0.05       0
  5854.8    0.04       0
Bank Sta=5002.2,5006.2
Exp/Cntr=0.3,0.1

Chan Stop Cuts=-1