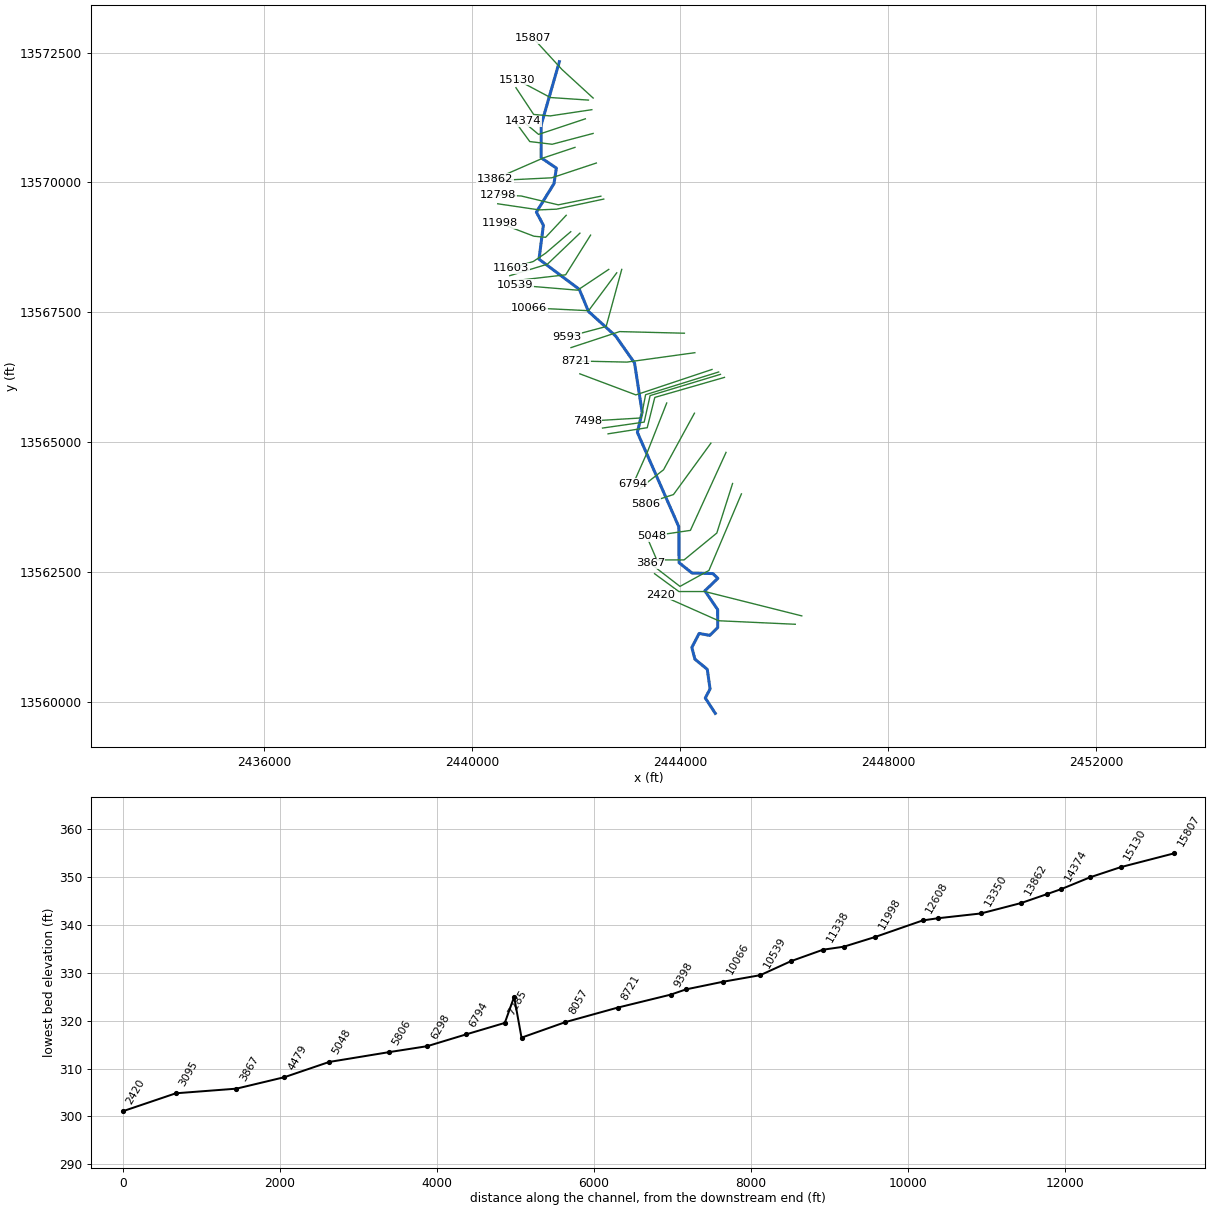
--- TRIB 8 TO YORKTOWN CREEK.prj (project) ---

Proj Title=TRIB 8 TO YORKTOWN CREEK Base Level Engineering
Current Plan=p01
Default Exp/Contr=0.3,0.1
English Units
Geom File=g01
Flow File=f01
Plan File=p01
BEGIN DESCRIPTION:
TRIB 8 TO YORKTOWN CREEK
END DESCRIPTION:

--- TRIB 8 TO YORKTOWN CREEK.p01 (plan) ---

Plan Title=Multiple Run
Short Identifier=Multiple
Geom File=g01
Flow File=f01
Subcritical Flow
K Sum by GR= 0
Std Step Tol= 0.01
Critical Tol= 0.01
Num of Std Step Trials= 20
Max Error Tol= 0.3
Flow Tol Ratio= 0.001
Split Flow NTrial= 30
Split Flow Tol= 0.02
Split Flow Ratio= 0.02
Log Output Level= 0
Friction Slope Method= 1
Unsteady Friction Slope Method= 2
Unsteady Bridges Friction Slope Method= 1
Parabolic Critical Depth
Global Vel Dist=  1 , 1 , 1
Global Log Level= 0
CheckData=True
Encroach Param= -1, 0, 0, 0
BEGIN DESCRIPTION:
Multiple Run
END DESCRIPTION:

--- TRIB 8 TO YORKTOWN CREEK.f01 (steady flow) ---

Flow Title=Multiple
Number of Profiles=7
Profile Names=10-year,25-year,50-year,1pct_min,100-year,1pct_plu,500-year
River Rch & RM= TRIB 8 TO YORKTO,Reach-1,15807
     426     672     889     570    1138    2271    1846
River Rch & RM= TRIB 8 TO YORKTO,Reach-1,13862
     783    1281    1737    1139    2273    4536    3861
River Rch & RM= TRIB 8 TO YORKTO,Reach-1,8721
    1130    1880    2578    1708    3407    6799    5904
River Rch & RM= TRIB 8 TO YORKTO,Reach-1,3095
    1928    3288    4582    3080    6146   12262   10970
Boundary for River Rch & Prof#=TRIB 8 TO YORKTO,Reach-1,1
Up Type=0
Dn Type=3
Dn Slope=0.005
Boundary for River Rch & Prof#=TRIB 8 TO YORKTO,Reach-1,2
Up Type=0
Dn Type=3
Dn Slope=0.005
Boundary for River Rch & Prof#=TRIB 8 TO YORKTO,Reach-1,3
Up Type=0
Dn Type=3
Dn Slope=0.005
Boundary for River Rch & Prof#=TRIB 8 TO YORKTO,Reach-1,4
Up Type=0
Dn Type=3
Dn Slope=0.005
Boundary for River Rch & Prof#=TRIB 8 TO YORKTO,Reach-1,5
Up Type=0
Dn Type=3
Dn Slope=0.005
Boundary for River Rch & Prof#=TRIB 8 TO YORKTO,Reach-1,6
Up Type=0
Dn Type=3
Dn Slope=0.005
Boundary for River Rch & Prof#=TRIB 8 TO YORKTO,Reach-1,7
Up Type=0
Dn Type=3
Dn Slope=0.005

--- TRIB 8 TO YORKTOWN CREEK.g01 (geometry) ---

Geom Title=Existing Conditions

River Reach=TRIB 8 TO YORKTO,Reach-1
Reach XY= 30
      2441675.00     13572325.00      2441325.52     13571109.78
      2441325.00     13570475.00      2441617.77     13570275.32
      2441571.25     13569976.55      2441232.88     13569428.22
      2441367.44     13569175.00      2441282.99     13568521.65
      2442058.35     13567941.67      2442235.52     13567515.21
      2442758.39     13567041.69      2443121.46     13566523.54
      2443267.89     13565575.00      2443176.20     13565185.50
      2443972.94     13563369.14      2443978.61     13562676.48
      2444226.47     13562478.55      2444628.41     13562467.30
      2444725.00     13562375.00      2444474.45     13562135.28
      2444721.25     13561773.45      2444721.46     13561426.46
      2444568.97     13561276.62      2444364.89     13561314.70
      2444224.60     13561045.14      2444283.13     13560818.93
      2444521.47     13560623.55      2444575.11     13560245.09
      2444483.02     13560071.69      2444675.00     13559775.00

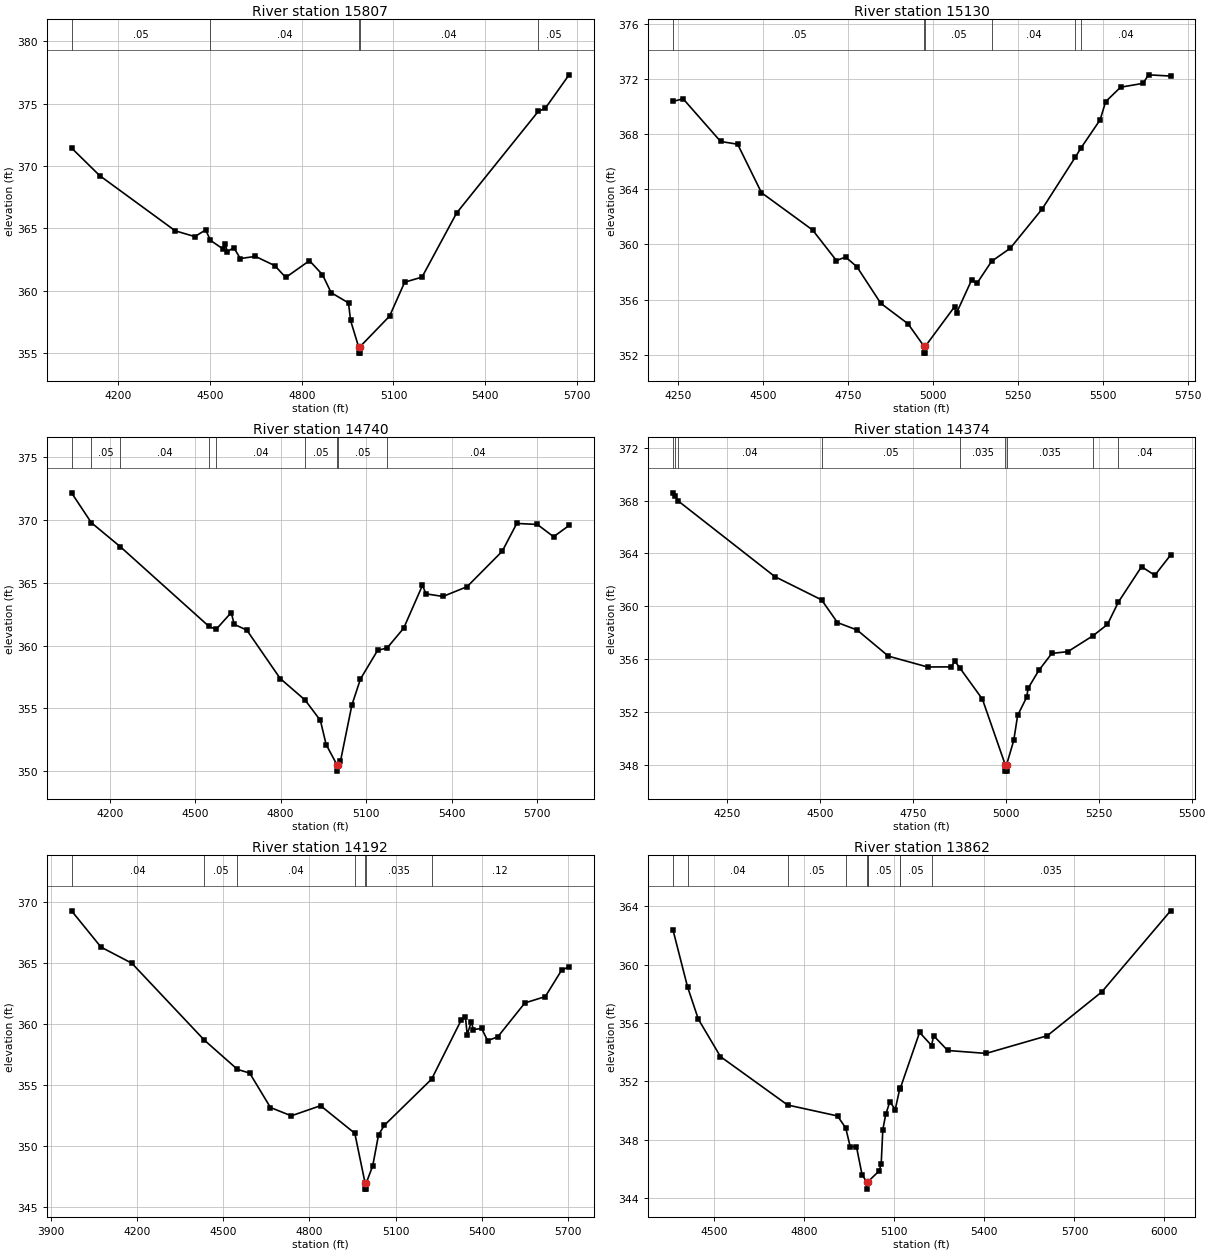
Type RM Length L Ch R = 1,15807,677,677,677
BEGIN DESCRIPTION:
TRIB 8 TO YORKTOWN CREEK 24.0
END DESCRIPTION:
XS GIS Cut Line= 3
      2442325.04     13571624.97      2441725.00     13572175.00
      2441175.02     13572774.98
#Sta/Elev= 30
  4046.7  371.44  4138.9  369.22  4386.2  364.79  4450.3  364.33  4485.5  364.87
  4501.1  364.03  4542.2  363.34  4549.0  363.76  4556.4  363.11  4577.4  363.45
  4598.9  362.57  4648.3  362.74  4711.8  362.00  4747.5  361.05  4825.2  362.40
  4867.8  361.27  4896.1  359.83  4952.9  359.01  4959.7  357.60  4986.0  355.48
  4986.3  354.98  4989.8  354.98  4990.0  355.48  5087.3  357.95  5136.6  360.67
  5193.4  361.08  5306.8  366.23  5573.9  374.38  5596.6  374.62  5674.6  377.31
#Mann=5,-1,0
  4046.7    0.05       0  4501.1    0.04       0  4986.0    0.04       0
  4990.0    0.04       0  5573.9    0.05       0
Bank Sta=4986,4990
Exp/Cntr=0.3,0.1

Type RM Length L Ch R = 1,15130,390,390,390
BEGIN DESCRIPTION:
Mapping XS eeba95e8
END DESCRIPTION:
XS GIS Cut Line= 3
      2442234.64     13571585.66      2441502.88     13571635.13
      2440858.50     13571978.11
#Sta/Elev= 30
  4235.0  370.39  4264.7  370.58  4375.0  367.48  4425.1  367.28  4495.2  363.76
  4645.6  361.05  4715.7  358.83  4742.4  359.09  4775.9  358.38  4846.0  355.73
  4926.2  354.24  4973.2  352.61  4973.5  352.11  4977.0  352.11  4977.2  352.61
  5063.1  355.48  5068.8  355.02  5113.3  357.42  5129.0  357.18  5172.1  358.78
  5226.6  359.72  5321.1  362.59  5417.7  366.32  5435.0  367.01  5491.2  369.05
  5507.5  370.37  5551.4  371.42  5617.3  371.70  5633.7  372.32  5698.4  372.23
#Mann=6,-1,0
  4235.0    0.05       0  4973.2    0.05       0  4977.2    0.05       0
  5172.1    0.04       0  5417.7    0.05       0  5435.0    0.04       0
Bank Sta=4973.2,4977.2
Exp/Cntr=0.3,0.1

Type RM Length L Ch R = 1,14740,366,366,366
BEGIN DESCRIPTION:
Mapping XS 62864188
END DESCRIPTION:
XS GIS Cut Line= 4
      2442299.77     13571400.76      2441497.67     13571280.97
      2441179.96     13571309.61      2440839.40     13571824.35
#Sta/Elev= 30
  4065.7  372.17  4135.2  369.79  4236.7  367.88  4548.5  361.52  4573.5  361.29
  4626.6  362.63  4636.7  361.69  4681.2  361.23  4798.5  357.37  4886.0  355.65
  4939.6  354.03  4959.7  352.11  4997.9  350.49  4998.1  349.99  5001.9  350.49
  5009.9  350.76  5050.1  355.25  5080.2  357.33  5140.4  359.61  5174.1  359.81
  5232.0  361.38  5298.1  364.80  5310.2  364.12  5370.0  363.91  5454.7  364.69
  5578.0  367.51  5629.2  369.73  5701.4  369.65  5758.6  368.67  5812.9  369.57
#Mann=9,-1,0
  4065.7    0.04       0  4135.2    0.05       0  4236.7    0.04       0
  4548.5    0.05       0  4573.5    0.04       0  4886.0    0.05       0
  4997.9    0.05       0  5001.9    0.05       0  5174.1    0.04       0
Bank Sta=4997.9,5001.9
Exp/Cntr=0.3,0.1

Type RM Length L Ch R = 1,14374,182,182,182
BEGIN DESCRIPTION:
TRIB 8 TO YORKTOWN CREEK 21.0
END DESCRIPTION:
XS GIS Cut Line= 3
      2442175.01     13571225.00      2441275.00     13570925.00
      2440975.00     13571175.00
#Sta/Elev= 30
  4104.0  368.59  4109.8  368.36  4117.2  367.99  4378.1  362.25  4503.9  360.49
  4546.7  358.77  4599.4  358.21  4683.8  356.23  4789.2  355.41  4852.4  355.42
  4863.0  355.84  4875.7  355.35  4936.7  352.98  4998.0  348.03  4998.2  347.53
  5001.7  347.53  5002.0  348.03  5021.1  349.85  5031.6  351.75  5055.9  353.12
  5059.8  353.80  5088.5  355.15  5123.6  356.44  5166.6  356.57  5234.7  357.78
  5273.3  358.63  5302.9  360.33  5365.1  363.00  5400.9  362.35  5443.2  363.88
#Mann=9,-1,0
  4104.0    0.04       0  4109.8    0.05       0  4117.2    0.04       0
  4503.9    0.05       0  4875.7   0.035       0  4998.0   0.035       0
  5002.0   0.035       0  5234.7    0.12       0  5302.9    0.04       0
Bank Sta=4998,5002
Exp/Cntr=0.3,0.1

Type RM Length L Ch R = 1,14192,330,330,330
BEGIN DESCRIPTION:
Mapping XS bd423a41
END DESCRIPTION:
XS GIS Cut Line= 4
      2442324.08     13570943.30      2441535.86     13570734.96
      2441105.31     13570787.04      2440820.56     13571175.97
#Sta/Elev= 30
  3972.3  369.26  4074.8  366.29  4182.1  364.97  4434.1  358.68  4549.6  356.28
  4592.0  355.98  4664.4  353.16  4736.8  352.48  4838.8  353.31  4957.8  351.05
  4993.5  346.98  4993.8  346.48  4997.3  346.48  4997.5  346.98  5020.1  348.38
  5040.3  350.92  5060.4  351.70  5225.2  355.49  5328.0  360.32  5342.6  360.58
  5348.8  359.13  5363.5  360.20  5369.7  359.54  5399.0  359.63  5419.9  358.63
  5455.4  358.95  5549.5  361.72  5620.6  362.24  5677.3  364.40  5703.3  364.69
#Mann=7,-1,0
  3972.3    0.04       0  4434.1    0.05       0  4549.6    0.04       0
  4957.8   0.035       0  4993.5   0.035       0  4997.5   0.035       0
  5225.2    0.12       0
Bank Sta=4993.5,4997.5
Exp/Cntr=0.3,0.1

Type RM Length L Ch R = 1,13862,512,512,512
BEGIN DESCRIPTION:
TRIB 8 TO YORKTOWN CREEK 20.0
END DESCRIPTION:
XS GIS Cut Line= 3
      2441974.97     13570674.99      2441375.00     13570475.00
      2440435.13     13570064.81
#Sta/Elev= 30
  4362.3  362.38  4410.6  358.49  4446.6  356.27  4520.4  353.70  4744.2  350.38
  4910.4  349.63  4937.8  348.80  4952.6  347.53  4973.6  347.52  4992.1  345.61
  5007.2  345.11  5007.4  344.61  5011.2  345.11  5011.9  345.12  5049.3  345.86
  5056.0  346.35  5061.4  348.70  5071.1  349.73  5084.8  350.61  5102.8  350.07
  5117.9  351.50  5120.0  351.55  5183.9  355.36  5223.9  354.46  5230.8  355.13
  5277.6  354.12  5405.6  353.92  5609.2  355.13  5791.2  358.14  6020.2  363.70
#Mann=10,-1,0
  4362.3    0.05       0  4410.6    0.04       0  4744.2    0.05       0
  4937.8    0.12       0  5007.2    0.05       0  5011.2    0.12       0
  5011.9    0.05       0  5117.9   0.035       0  5120.0    0.05       0
  5223.9   0.035       0
Bank Sta=5007.2,5011.2
Exp/Cntr=0.3,0.1

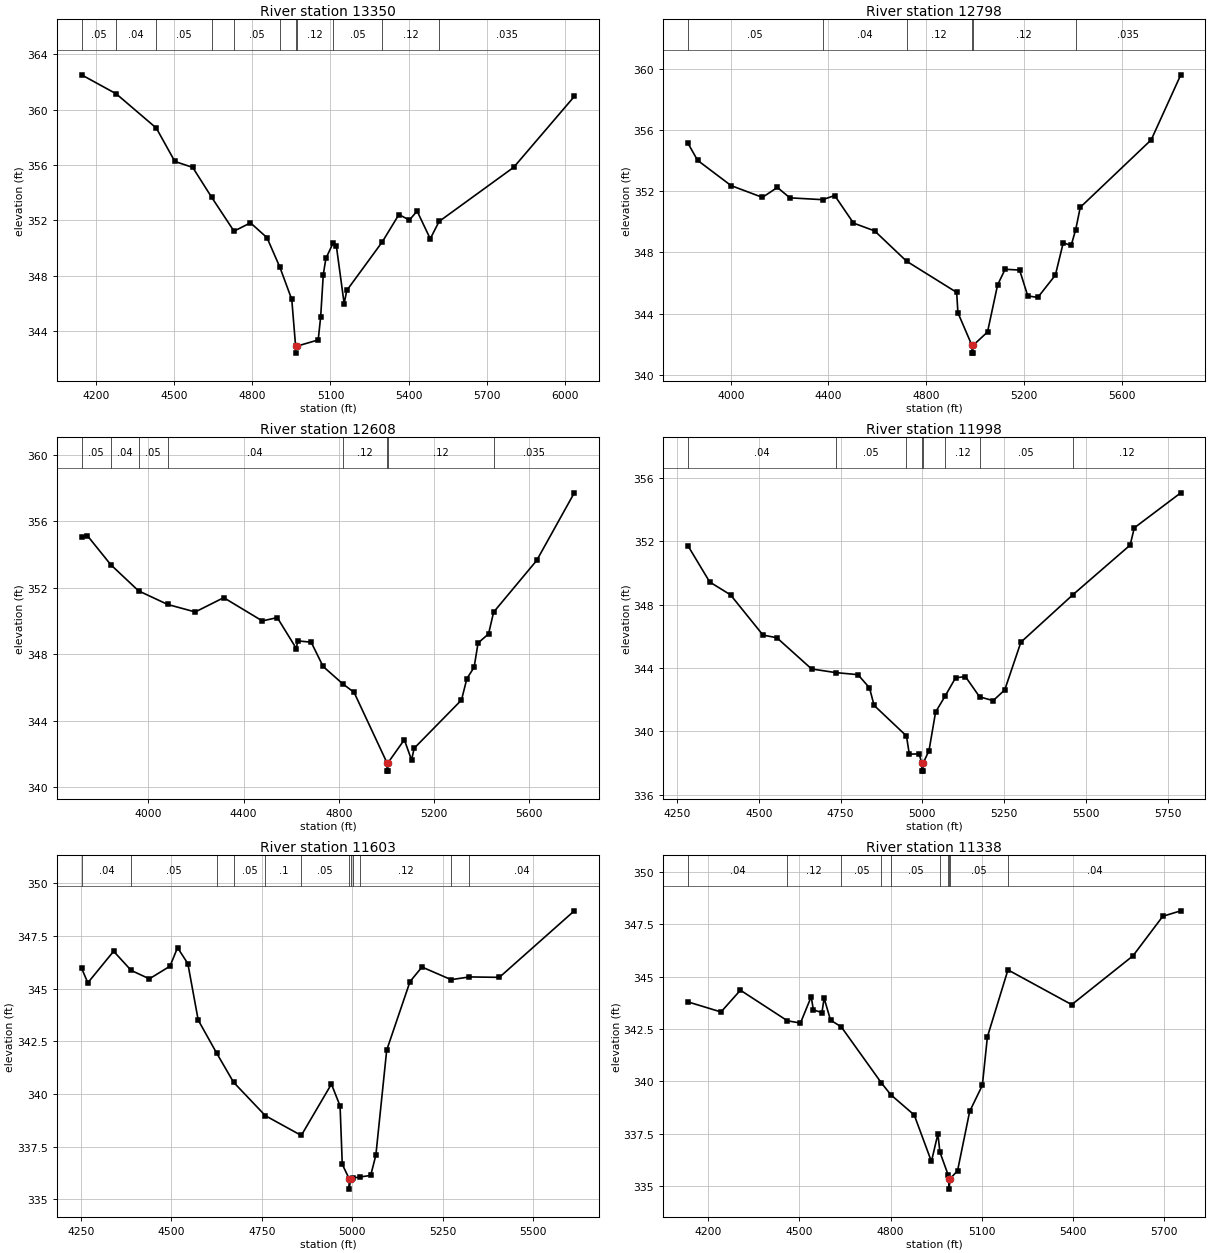
Type RM Length L Ch R = 1,13350,552,552,552
BEGIN DESCRIPTION:
Mapping XS bb4d0d71
END DESCRIPTION:
XS GIS Cut Line= 3
      2442386.54     13570373.84      2441528.92     13570089.13
      2440542.86     13570040.52
#Sta/Elev= 30
  4144.9  362.51  4277.9  361.14  4431.7  358.67  4502.9  356.26  4571.5  355.83
  4643.6  353.69  4729.9  351.23  4793.2  351.83  4856.5  350.76  4906.3  348.61
  4951.6  346.30  4966.3  342.93  4966.6  342.43  4970.4  342.93  5053.0  343.38
  5062.5  345.05  5072.5  348.10  5082.5  349.26  5110.8  350.40  5122.6  350.17
  5152.6  346.00  5162.6  346.95  5299.0  350.46  5362.8  352.43  5402.9  352.03
  5432.5  352.68  5483.0  350.68  5516.9  351.93  5803.4  355.84  6035.8  360.95
#Mann=11,-1,0
  4144.9    0.05       0  4277.9    0.04       0  4431.7    0.05       0
  4643.6    0.04       0  4729.9    0.05       0  4906.3    0.12       0
  4966.3    0.05       0  4970.4    0.12       0  5110.8    0.05       0
  5299.0    0.12       0  5516.9   0.035       0
Bank Sta=4966.3,4970.4
Exp/Cntr=0.3,0.1

Type RM Length L Ch R = 1,12798,190,190,190
BEGIN DESCRIPTION:
Mapping XS 261b3bd1
END DESCRIPTION:
XS GIS Cut Line= 4
      2442473.39     13569734.97      2441653.92     13569568.29
      2440942.11     13569738.43      2440494.18     13569762.74
#Sta/Elev= 30
  3825.2  355.13  3864.4  354.02  4001.4  352.37  4129.7  351.60  4190.9  352.25
  4242.0  351.57  4375.9  351.45  4425.6  351.72  4502.3  349.92  4588.9  349.41
  4719.5  347.43  4924.7  345.39  4929.8  344.06  4987.3  341.92  4987.6  341.42
  4991.2  341.42  4991.4  341.92  5050.9  342.80  5092.2  345.88  5123.0  346.90
  5182.3  346.85  5215.6  345.16  5256.7  345.06  5328.7  346.52  5360.8  348.63
  5393.3  348.46  5411.8  349.49  5430.5  350.95  5720.9  355.36  5841.9  359.61
#Mann=6,-1,0
  3825.2    0.05       0  4375.9    0.04       0  4719.5    0.12       0
  4987.3    0.05       0  4991.4    0.12       0  5411.8   0.035       0
Bank Sta=4987.3,4991.4
Exp/Cntr=0.3,0.1

Type RM Length L Ch R = 1,12608,610,610,610
BEGIN DESCRIPTION:
Mapping XS ecfc02c7
END DESCRIPTION:
XS GIS Cut Line= 4
      2442528.96     13569679.41      2441619.20     13569484.96
      2441285.86     13569471.07      2440488.66     13569588.92
#Sta/Elev= 30
  3719.4  355.07  3743.9  355.14  3842.4  353.39  3958.8  351.82  4081.3  351.00
  4197.0  350.55  4316.6  351.41  4478.6  350.01  4541.5  350.21  4621.9  348.34
  4627.0  348.81  4683.9  348.73  4734.0  347.27  4816.0  346.23  4864.1  345.71
  5002.4  341.47  5002.6  340.97  5006.2  340.97  5006.5  341.47  5075.2  342.86
  5105.5  341.64  5116.7  342.35  5315.3  345.25  5338.0  346.54  5368.3  347.22
  5384.9  348.68  5429.0  349.23  5450.3  350.54  5631.2  353.65  5789.2  357.72
#Mann=8,-1,0
  3719.4    0.05       0  3842.4    0.04       0  3958.8    0.05       0
  4081.3    0.04       0  4816.0    0.12       0  5002.4    0.05       0
  5006.5    0.12       0  5450.3   0.035       0
Bank Sta=5002.4,5006.5
Exp/Cntr=0.3,0.1

Type RM Length L Ch R = 1,11998,395,395,395
BEGIN DESCRIPTION:
Mapping XS 530e8a42
END DESCRIPTION:
XS GIS Cut Line= 4
      2441806.73     13569366.94      2441410.86     13568943.29
      2441185.17     13568964.13      2440532.37     13569214.14
#Sta/Elev= 30
  4283.9  351.71  4350.2  349.43  4413.7  348.62  4512.9  346.08  4555.4  345.91
  4661.4  343.94  4735.2  343.71  4803.1  343.58  4838.3  342.75  4852.4  341.64
  4951.3  339.71  4960.0  338.56  4990.1  338.58  4998.0  337.99  4998.3  337.49
  5002.0  337.49  5002.3  337.99  5020.2  338.79  5040.3  341.22  5069.8  342.24
  5101.3  343.38  5131.4  343.46  5174.7  342.18  5216.2  341.94  5251.6  342.62
  5300.9  345.63  5460.0  348.63  5634.7  351.76  5647.4  352.85  5789.4  355.06
#Mann=8,-1,0
  4283.9    0.04       0  4735.2    0.05       0  4951.3     0.1       0
  4998.0    0.05       0  5002.3     0.1       0  5069.8    0.12       0
  5174.7    0.05       0  5460.0    0.12       0
Bank Sta=4998,5002.3
Exp/Cntr=0.3,0.1

Type RM Length L Ch R = 1,11603,265,265,265
BEGIN DESCRIPTION:
Mapping XS 5493463d
END DESCRIPTION:
XS GIS Cut Line= 4
      2441893.53     13569050.96      2441410.86     13568637.74
      2441174.75     13568478.02      2440751.92     13568349.78
#Sta/Elev= 30
  4251.4  345.98  4268.7  345.28  4340.1  346.78  4388.5  345.87  4438.9  345.47
  4495.9  346.07  4516.8  346.95  4545.3  346.19  4573.9  343.51  4624.6  341.95
  4671.5  340.56  4759.4  338.97  4858.9  338.03  4942.2  340.47  4966.1  339.43
  4972.2  336.66  4991.0  335.98  4991.3  335.48  4995.3  335.98  5002.3  336.01
  5022.1  336.06  5050.8  336.13  5065.1  337.10  5095.0  342.08  5159.5  345.34
  5192.5  346.03  5273.2  345.43  5323.9  345.56  5406.5  345.54  5613.7  348.70
#Mann=12,-1,0
  4251.4    0.04       0  4388.5    0.05       0  4624.6     0.1       0
  4671.5    0.05       0  4759.4     0.1       0  4858.9    0.05       0
  4991.0    0.05       0  4995.3    0.05       0  5002.3     0.1       0
  5022.1    0.12       0  5273.2    0.05       0  5323.9    0.04       0
Bank Sta=4991,4995.3
Exp/Cntr=0.3,0.1

Type RM Length L Ch R = 1,11338,409,409,409
BEGIN DESCRIPTION:
Mapping XS 462666e3
END DESCRIPTION:
XS GIS Cut Line= 3
      2442070.62     13569023.18      2441445.59     13568425.93
      2440719.95     13568203.73
#Sta/Elev= 30
  4132.9  343.79  4241.6  343.31  4305.5  344.35  4460.2  342.89  4503.3  342.78
  4538.8  344.04  4545.8  343.41  4574.1  343.28  4581.3  343.97  4602.4  342.92
  4637.7  342.60  4770.1  339.92  4800.8  339.36  4878.2  338.39  4934.8  336.17
  4956.2  337.49  4962.7  336.62  4989.6  335.54  4992.3  335.35  4992.6  334.85
  4996.6  335.35  5020.9  335.73  5060.8  338.56  5102.6  339.81  5119.2  342.12
  5186.9  345.32  5397.0  343.66  5598.8  345.99  5697.1  347.88  5756.3  348.14
#Mann=10,-1,0
  4132.9    0.04       0  4460.2    0.12       0  4637.7    0.05       0
  4770.1     0.1       0  4800.8    0.05       0  4962.7    0.12       0
  4989.6    0.05       0  4992.3    0.05       0  4996.6    0.05       0
  5186.9    0.04       0
Bank Sta=4992.3,4996.6
Exp/Cntr=0.3,0.1

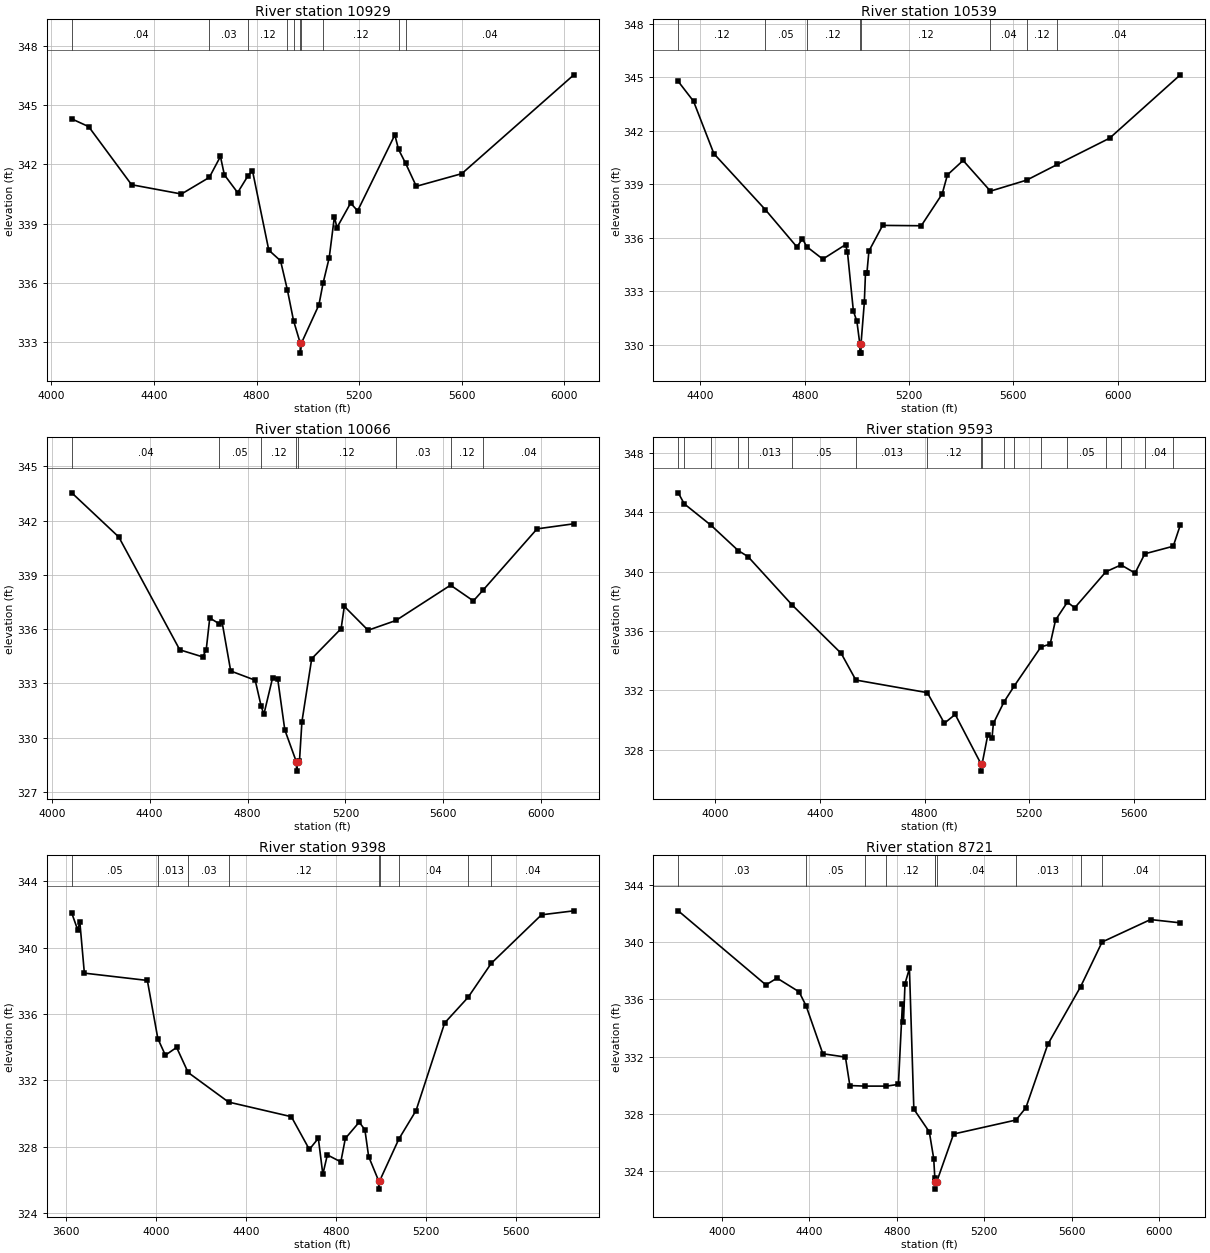
Type RM Length L Ch R = 1,10929,390,390,390
BEGIN DESCRIPTION:
Mapping XS b2ecf82f
END DESCRIPTION:
XS GIS Cut Line= 3
      2442275.46     13568984.98      2441796.28     13568221.07
      2440747.66     13568099.54
#Sta/Elev= 30
  4079.5  344.30  4145.3  343.91  4312.6  340.97  4507.1  340.50  4615.7  341.34
  4659.1  342.40  4674.4  341.47  4726.2  340.57  4766.9  341.43  4784.0  341.68
  4847.6  337.66  4893.5  337.12  4919.9  335.66  4944.0  334.10  4970.3  332.95
  4970.6  332.45  4974.6  332.95  5043.0  334.89  5059.1  335.98  5083.2  337.28
  5103.4  339.35  5113.4  338.80  5166.5  340.04  5194.0  339.65  5339.0  343.49
  5353.3  342.76  5380.8  342.06  5422.7  340.89  5600.1  341.53  6036.9  346.53
#Mann=10,-1,0
  4079.5    0.04       0  4615.7    0.03       0  4766.9    0.12       0
  4919.9    0.03       0  4944.0     0.1       0  4970.3    0.05       0
  4974.6     0.1       0  5059.1    0.12       0  5353.3    0.05       0
  5380.8    0.04       0
Bank Sta=4970.3,4974.6
Exp/Cntr=0.3,0.1

Type RM Length L Ch R = 1,10539,473,473,473
BEGIN DESCRIPTION:
TRIB 8 TO YORKTOWN CREEK 13.0
END DESCRIPTION:
XS GIS Cut Line= 3
      2442625.01     13568325.01      2442025.00     13567925.00
      2440824.99     13568025.00
#Sta/Elev= 30
  4315.1  344.76  4373.7  343.65  4451.8  340.71  4648.6  337.58  4770.3  335.48
  4791.3  335.94  4807.6  335.50  4869.5  334.80  4956.6  335.61  4964.1  335.19
  4986.7  331.89  5000.2  331.31  5011.5  330.03  5011.8  329.53  5015.6  329.53
  5015.9  330.03  5028.7  332.37  5033.2  334.04  5038.7  334.04  5046.3  335.25
  5098.9  336.69  5247.0  336.67  5327.2  338.45  5347.3  339.52  5407.5  340.33
  5512.3  338.61  5651.6  339.23  5769.4  340.11  5969.5  341.58  6240.4  345.13
#Mann=8,-1,0
  4315.1    0.12       0  4648.6    0.05       0  4807.6    0.12       0
  5011.5    0.05       0  5015.9    0.12       0  5512.3    0.04       0
  5651.6    0.12       0  5769.4    0.04       0
Bank Sta=5011.5,5015.9
Exp/Cntr=0.3,0.1

Type RM Length L Ch R = 1,10066,473,473,473
BEGIN DESCRIPTION:
Mapping XS b6a6c077
END DESCRIPTION:
XS GIS Cut Line= 3
      2442778.95     13568259.30      2442237.25     13567530.10
      2441094.89     13567585.66
#Sta/Elev= 30
  4081.6  343.53  4273.8  341.09  4523.0  334.86  4616.4  334.47  4631.0  334.85
  4645.6  336.62  4683.8  336.30  4695.7  336.41  4731.2  333.69  4831.3  333.18
  4855.8  331.74  4866.8  331.30  4902.2  333.30  4923.1  333.27  4952.3  330.44
  4999.9  328.66  5000.3  328.16  5004.6  328.66  5012.3  328.72  5022.3  330.89
  5062.3  334.37  5182.5  336.03  5195.6  337.26  5292.6  335.94  5406.5  336.48
  5629.8  338.43  5723.1  337.56  5762.9  338.16  5983.4  341.54  6133.7  341.82
#Mann=8,-1,0
  4081.6    0.04       0  4683.8    0.05       0  4855.8    0.12       0
  4999.9    0.05       0  5004.6    0.12       0  5406.5    0.03       0
  5629.8    0.12       0  5762.9    0.04       0
Bank Sta=4999.9,5004.6
Exp/Cntr=0.3,0.1

Type RM Length L Ch R = 1,9593,195,195,195
BEGIN DESCRIPTION:
TRIB 8 TO YORKTOWN CREEK 11.0
END DESCRIPTION:
XS GIS Cut Line= 3
      2442874.99     13568324.97      2442575.00     13567225.00
      2441824.95     13567024.99
#Sta/Elev= 30
  3859.9  345.32  3882.8  344.58  3985.8  343.12  4088.7  341.43  4126.2  341.02
  4294.6  337.76  4481.8  334.50  4537.8  332.70  4810.6  331.85  4875.7  329.79
  4917.1  330.38  5015.2  327.06  5015.5  326.56  5019.9  327.06  5041.4  329.00
  5057.6  328.81  5062.8  329.78  5103.5  331.23  5143.2  332.32  5244.2  334.93
  5279.5  335.12  5300.2  336.75  5345.2  337.95  5373.3  337.57  5492.4  340.00
  5550.2  340.46  5603.5  339.91  5640.8  341.21  5749.3  341.72  5776.3  343.15
#Mann=18,-1,0
  3859.9   0.013       0  3882.8    0.05       0  3985.8   0.013       0
  4088.7    0.05       0  4126.2   0.013       0  4294.6    0.05       0
  4537.8   0.013       0  4810.6    0.12       0  5015.2    0.05       0
  5019.9    0.12       0  5103.5    0.04       0  5143.2   0.013       0
  5244.2    0.04       0  5345.2    0.05       0  5492.4    0.04       0
  5550.2    0.03       0  5640.8    0.04       0  5749.3    0.05       0
Bank Sta=5015.2,5019.9
Exp/Cntr=0.3,0.1

Type RM Length L Ch R = 1,9398,677,677,677
BEGIN DESCRIPTION:
TRIB 8 TO YORKTOWN CREEK 10.0
END DESCRIPTION:
XS GIS Cut Line= 3
      2444081.02     13567096.07      2442834.48     13567127.32
      2441898.45     13566818.78
#Sta/Elev= 30
  3625.1  342.07  3651.1  341.08  3661.1  341.52  3681.1  338.46  3961.2  338.02
  4007.8  334.52  4041.3  333.52  4091.3  333.99  4142.5  332.48  4322.2  330.70
  4601.4  329.82  4681.5  327.85  4721.5  328.52  4741.5  326.35  4761.5  327.52
  4821.5  327.10  4841.5  328.51  4903.1  329.49  4928.4  329.04  4945.2  327.42
  4989.6  325.96  4989.9  325.46  4994.3  325.96  5079.3  328.47  5156.0  330.19
  5283.1  335.46  5387.7  337.01  5490.3  339.05  5713.8  341.97  5857.6  342.21
#Mann=9,-1,0
  3625.1    0.05       0  4007.8   0.013       0  4142.5    0.03       0
  4322.2    0.12       0  4989.6    0.05       0  4994.3    0.12       0
  5079.3    0.04       0  5387.7   0.013       0  5490.3    0.04       0
Bank Sta=4989.6,4994.3
Exp/Cntr=0.3,0.1

Type RM Length L Ch R = 1,8721,664,664,664
BEGIN DESCRIPTION:
TRIB 8 TO YORKTOWN CREEK 9.0
END DESCRIPTION:
XS GIS Cut Line= 3
      2444282.43     13566721.08      2442974.96     13566539.98
      2441998.85     13566561.32
#Sta/Elev= 30
  3800.4  342.19  4201.6  337.01  4252.1  337.49  4353.1  336.53  4385.4  335.54
  4461.7  332.20  4565.1  331.97  4585.3  329.98  4654.0  329.94  4752.9  329.94
  4807.4  330.06  4825.6  335.68  4830.6  334.45  4837.6  337.10  4857.8  338.16
  4878.0  328.33  4948.7  326.74  4968.9  324.87  4974.0  323.50  4976.1  323.24
  4976.6  322.74  4982.3  323.24  5059.7  326.59  5345.2  327.57  5390.4  328.43
  5490.4  332.85  5640.5  336.88  5739.0  340.01  5960.5  341.58  6096.7  341.35
#Mann=10,-1,0
  3800.4    0.03       0  4385.4    0.05       0  4654.0   0.013       0
  4752.9    0.12       0  4974.0    0.04       0  4976.1    0.04       0
  4982.3    0.04       0  5345.2   0.013       0  5640.5    0.03       0
  5739.0    0.04       0
Bank Sta=4976.1,4982.3
Exp/Cntr=0.3,0.1

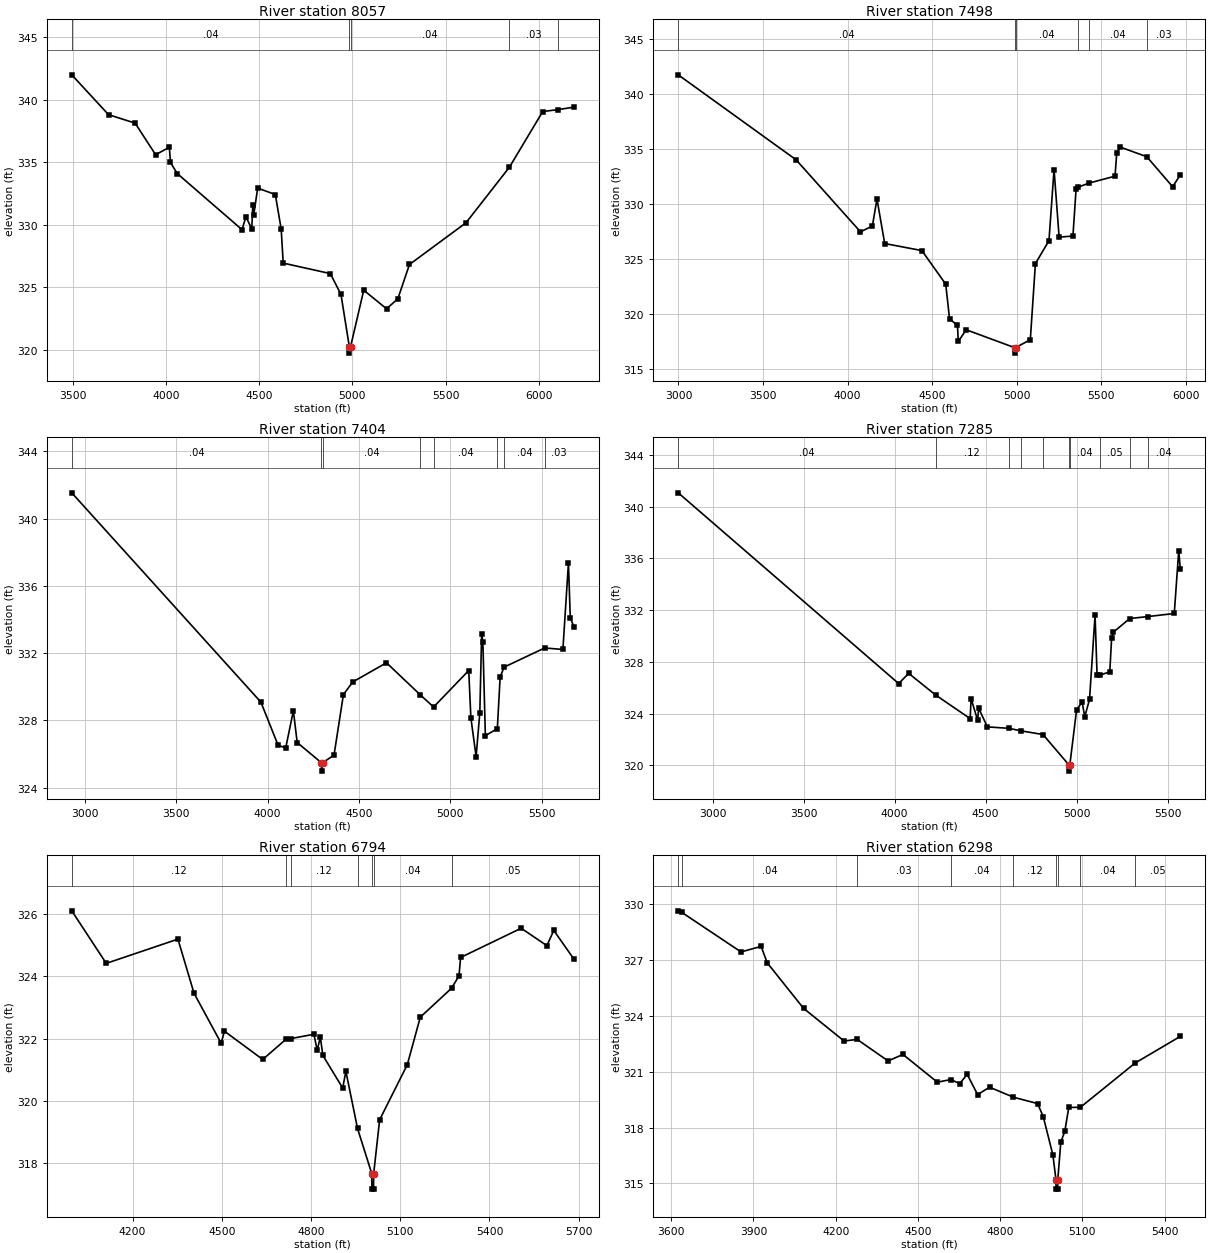
Type RM Length L Ch R = 1,8057,559,559,559
BEGIN DESCRIPTION:
Mapping XS eb4409d4
END DESCRIPTION:
XS GIS Cut Line= 3
      2444612.23     13566398.15      2443146.98     13565908.57
      2442068.54     13566314.28
#Sta/Elev= 30
  3492.3  342.01  3689.7  338.82  3832.8  338.14  3942.7  335.61  4016.5  336.21
  4022.4  334.99  4059.2  334.10  4406.7  329.61  4427.7  330.63  4459.4  329.68
  4464.7  331.60  4469.9  330.80  4491.0  332.94  4585.8  332.42  4617.3  329.65
  4628.1  326.93  4881.1  326.09  4938.5  324.42  4983.4  320.22  4983.9  319.72
  4989.7  320.22  5060.7  324.76  5183.4  323.27  5243.8  324.07  5306.4  326.82
  5610.1  330.16  5843.7  334.62  6022.2  339.07  6103.3  339.22  6189.4  339.42
#Mann=5,-1,0
  3492.3    0.04       0  4983.4    0.04       0  4989.7    0.04       0
  5843.7    0.03       0  6103.3    0.04       0
Bank Sta=4983.4,4989.7
Exp/Cntr=0.3,0.1

Type RM Length L Ch R = 1,7498,94,94,94
BEGIN DESCRIPTION:
Mapping XS eaed5d4f
END DESCRIPTION:
XS GIS Cut Line= 4
      2444740.73     13566349.54      2443334.48     13565912.04
      2443247.67     13565464.13      2442209.74     13565401.64
#Sta/Elev= 30
  2998.6  341.71  3695.8  334.00  4076.2  327.47  4146.5  328.00  4173.8  330.45
  4219.4  326.41  4439.3  325.77  4580.4  322.72  4602.9  319.57  4649.6  319.00
  4654.7  317.53  4701.3  318.59  4987.2  316.97  4987.7  316.47  4993.6  316.97
  5080.5  317.69  5110.6  324.59  5190.7  326.67  5220.8  333.12  5250.8  326.99
  5332.5  327.09  5351.0  331.33  5362.6  331.52  5427.3  331.89  5581.4  332.52
  5591.5  334.61  5611.5  335.16  5769.3  334.28  5922.1  331.56  5967.4  332.64
#Mann=6,-1,0
  2998.6    0.04       0  4987.2    0.04       0  4993.6    0.04       0
  5362.6    0.05       0  5427.3    0.04       0  5769.3    0.03       0
Bank Sta=4987.2,4993.6
Exp/Cntr=0.3,0.1

Type RM Length L Ch R = 1,7404,119,119,119
BEGIN DESCRIPTION:
Mapping XS 2e29069f
END DESCRIPTION:
XS GIS Cut Line= 4
      2444775.43     13566304.40      2443421.28     13565894.68
      2443306.70     13565384.27      2442505.72     13565269.84
#Sta/Elev= 30
  2929.0  341.53  3963.8  329.09  4057.8  326.53  4099.6  326.37  4141.4  328.58
  4162.3  326.69  4294.9  325.49  4295.4  324.99  4301.3  325.49  4363.9  325.94
  4415.2  329.54  4466.4  330.29  4650.9  331.43  4835.2  329.53  4908.7  328.80
  5100.9  330.97  5112.6  328.16  5141.3  325.85  5161.5  328.46  5171.7  333.16
  5178.3  332.65  5191.9  327.10  5257.4  327.51  5272.7  330.58  5294.4  331.17
  5516.4  332.31  5616.1  332.22  5646.4  337.36  5656.5  334.12  5676.0  333.57
#Mann=8,-1,0
  2929.0    0.04       0  4294.9    0.04       0  4301.3    0.04       0
  4835.2    0.12       0  4908.7    0.04       0  5257.4    0.05       0
  5294.4    0.04       0  5516.4    0.03       0
Bank Sta=4294.9,4301.3
Exp/Cntr=0.3,0.1

Type RM Length L Ch R = 1,7285,491,491,491
BEGIN DESCRIPTION:
Mapping XS d76423ff
END DESCRIPTION:
XS GIS Cut Line= 4
      2444851.85     13566245.38      2443511.56     13565859.96
      2443365.73     13565276.63      2442612.21     13565158.56
#Sta/Elev= 30
  2810.8  341.07  4022.0  326.32  4077.0  327.11  4224.5  325.44  4414.8  323.61
  4419.9  325.15  4456.0  323.48  4461.1  324.42  4509.4  322.97  4628.2  322.86
  4692.0  322.67  4814.9  322.38  4956.1  320.05  4956.6  319.55  4962.5  320.05
  4999.7  324.31  5030.1  324.88  5044.3  323.75  5070.6  325.10  5101.0  331.62
  5112.0  327.00  5129.9  326.98  5181.9  327.23  5192.1  329.87  5202.2  330.30
  5291.3  331.35  5390.4  331.50  5536.2  331.74  5560.8  336.61  5569.4  335.15
#Mann=10,-1,0
  2810.8    0.04       0  4224.5    0.12       0  4628.2    0.04       0
  4692.0    0.12       0  4814.9    0.04       0  4956.1    0.04       0
  4962.5    0.04       0  5129.9    0.05       0  5291.3    0.03       0
  5390.4    0.04       0
Bank Sta=4956.1,4962.5
Exp/Cntr=0.3,0.1

Type RM Length L Ch R = 1,6794,496,496,496
BEGIN DESCRIPTION:
Mapping XS bcf950f5
END DESCRIPTION:
XS GIS Cut Line= 3
      2443740.73     13565752.34      2443372.67     13564818.29
      2443094.89     13564193.29
#Sta/Elev= 30
  3995.7  326.11  4111.6  324.42  4352.6  325.20  4406.7  323.46  4498.0  321.85
  4508.8  322.24  4637.7  321.33  4715.9  321.98  4731.4  322.00  4809.7  322.14
  4820.9  321.62  4831.2  322.05  4839.9  321.46  4906.5  320.41  4917.2  320.95
  4956.4  319.11  5004.2  317.66  5004.7  317.16  5010.2  317.16  5010.7  317.66
  5030.7  319.39  5123.6  321.16  5167.4  322.69  5272.4  323.62  5297.5  324.02
  5302.9  324.61  5506.6  325.55  5592.9  324.99  5616.1  325.48  5683.6  324.56
#Mann=7,-1,0
  3995.7    0.12       0  4715.9    0.04       0  4731.4    0.12       0
  4956.4    0.04       0  5004.2    0.04       0  5010.7    0.04       0
  5272.4    0.05       0
Bank Sta=5004.2,5010.7
Exp/Cntr=0.3,0.1

Type RM Length L Ch R = 1,6298,492,492,492
BEGIN DESCRIPTION:
Mapping XS dddc343d
END DESCRIPTION:
XS GIS Cut Line= 3
      2444274.56     13565556.11      2443679.96     13564466.73
      2443215.56     13564102.15
#Sta/Elev= 30
  3625.6  329.65  3638.2  329.57  3854.7  327.44  3928.1  327.74  3949.9  326.86
  4082.6  324.41  4230.7  322.65  4278.1  322.74  4391.2  321.58  4445.3  321.93
  4570.6  320.44  4620.3  320.58  4652.2  320.36  4679.7  320.86  4717.7  319.77
  4761.3  320.17  4848.4  319.63  4936.3  319.29  4957.1  318.59  4992.4  316.52
  5003.5  315.19  5004.0  314.69  5009.6  314.69  5010.1  315.19  5021.3  317.23
  5035.7  317.79  5050.2  319.08  5092.8  319.09  5292.4  321.47  5457.1  322.90
#Mann=9,-1,0
  3625.6    0.03       0  3638.2    0.04       0  4278.1    0.03       0
  4620.3    0.04       0  4848.4    0.12       0  5003.5    0.05       0
  5010.1    0.12       0  5092.8    0.04       0  5292.4    0.05       0
Bank Sta=5003.5,5010.1
Exp/Cntr=0.3,0.1

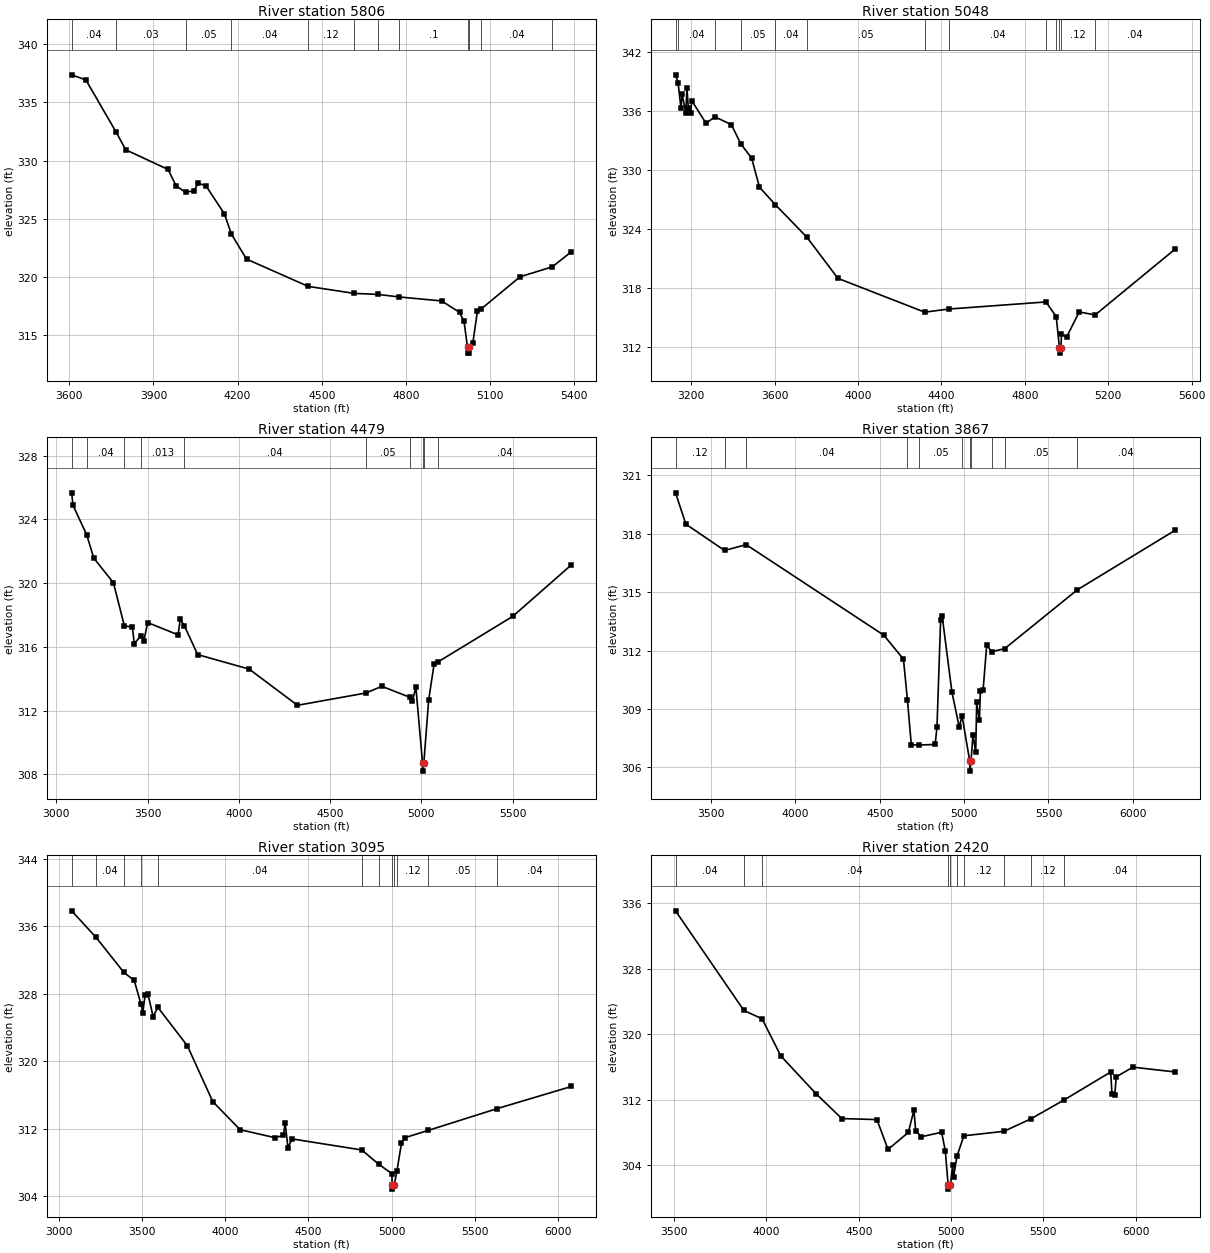
Type RM Length L Ch R = 1,5806,758,758,758
BEGIN DESCRIPTION:
Mapping XS c9b68048
END DESCRIPTION:
XS GIS Cut Line= 3
      2444591.41     13564978.87      2443870.93     13563989.30
      2443341.43     13563815.69
#Sta/Elev= 30
  3608.4  337.37  3659.1  336.93  3767.0  332.44  3801.3  330.92  3952.0  329.23
  3981.3  327.80  4014.4  327.27  4046.1  327.40  4058.6  328.08  4088.0  327.79
  4152.9  325.41  4177.8  323.67  4231.7  321.52  4451.5  319.17  4615.8  318.57
  4700.5  318.48  4776.6  318.26  4927.3  317.92  4991.0  316.94  5007.1  316.16
  5019.5  313.93  5020.0  313.43  5025.6  313.43  5026.1  313.93  5038.7  314.34
  5054.7  317.02  5066.4  317.19  5207.0  320.00  5321.5  320.85  5389.7  322.15
#Mann=12,-1,0
  3608.4    0.04       0  3767.0    0.03       0  4014.4    0.05       0
  4177.8    0.04       0  4451.5    0.12       0  4615.8    0.05       0
  4700.5    0.12       0  4776.6     0.1       0  5019.5    0.05       0
  5026.1     0.1       0  5066.4    0.04       0  5321.5    0.05       0
Bank Sta=5019.5,5026.1
Exp/Cntr=0.3,0.1

Type RM Length L Ch R = 1,5048,569,569,569
BEGIN DESCRIPTION:
Mapping XS fa6caa9c
END DESCRIPTION:
XS GIS Cut Line= 3
      2444882.23     13564800.97      2444196.46     13563299.20
      2443459.32     13563190.80
#Sta/Elev= 30
  3125.3  339.72  3137.4  338.93  3151.5  336.32  3157.0  337.75  3174.6  335.85
  3180.1  338.34  3186.8  336.35  3197.6  335.85  3203.1  337.09  3272.2  334.77
  3313.0  335.45  3392.8  334.66  3437.7  332.71  3490.5  331.23  3527.6  328.29
  3604.2  326.49  3755.2  323.19  3904.0  319.00  4319.9  315.56  4436.1  315.88
  4901.5  316.60  4950.6  315.11  4966.3  311.89  4966.8  311.39  4973.2  311.89
  4975.9  313.31  5000.1  313.01  5060.7  315.58  5137.4  315.28  5521.3  321.99
#Mann=13,-1,0
  3125.3    0.05       0  3137.4    0.04       0  3313.0    0.03       0
  3437.7    0.05       0  3604.2    0.04       0  3755.2    0.05       0
  4319.9   0.013       0  4436.1    0.04       0  4901.5    0.05       0
  4950.6    0.12       0  4966.3    0.05       0  4973.2    0.12       0
  5137.4    0.04       0
Bank Sta=4966.3,4973.2
Exp/Cntr=0.3,0.1

Type RM Length L Ch R = 1,4479,612,612,612
BEGIN DESCRIPTION:
Mapping XS 4f45d63b
END DESCRIPTION:
XS GIS Cut Line= 5
      2445008.09     13564201.99      2444704.27     13563247.11
      2444074.93     13562730.62      2443549.75     13562730.62
      2443393.51     13563095.18
#Sta/Elev= 30
  3083.9  325.67  3091.2  324.89  3166.2  323.04  3205.5  321.57  3312.7  320.03
  3372.8  317.32  3416.6  317.25  3427.0  316.21  3463.8  316.71  3479.5  316.40
  3500.5  317.53  3667.2  316.76  3678.9  317.73  3701.1  317.34  3774.4  315.52
  4056.7  314.61  4321.1  312.34  4695.7  313.11  4783.6  313.53  4935.5  312.85
  4950.0  312.59  4970.0  313.47  5006.6  308.71  5007.1  308.21  5013.5  308.71
  5040.0  312.67  5070.0  314.94  5090.9  315.06  5500.8  317.92  5821.9  321.15
#Mann=10,-1,0
  3083.9    0.12       0  3166.2    0.04       0  3372.8    0.12       0
  3463.8   0.013       0  3701.1    0.04       0  4695.7    0.05       0
  4935.5    0.12       0  5006.6    0.05       0  5013.5    0.12       0
  5090.9    0.04       0
Bank Sta=5006.6,5013.5
Exp/Cntr=0.3,0.1

Type RM Length L Ch R = 1,3867,772,772,772
BEGIN DESCRIPTION:
Mapping XS 394a9d57
END DESCRIPTION:
XS GIS Cut Line= 4
      2445178.24     13564001.48      2444553.23     13562527.50
      2443995.93     13562220.20      2443422.98     13562662.94
#Sta/Elev= 30
  3289.6  320.10  3351.0  318.49  3580.4  317.14  3708.3  317.44  4524.0  312.79
  4640.4  311.56  4664.1  309.45  4687.0  307.16  4730.6  307.15  4828.2  307.18
  4839.0  308.06  4860.7  313.56  4869.7  313.78  4927.7  309.87  4971.3  308.06
  4987.6  308.65  5033.6  306.31  5034.1  305.81  5040.5  306.31  5052.6  307.69
  5068.7  306.77  5074.4  309.34  5090.5  308.42  5096.2  309.90  5112.3  309.97
  5134.0  312.29  5162.9  311.94  5240.5  312.10  5670.7  315.12  6251.1  318.18
#Mann=11,-1,0
  3289.6    0.12       0  3580.4   0.013       0  3708.3    0.04       0
  4664.1    0.12       0  4730.6    0.05       0  4987.6    0.12       0
  5033.6    0.05       0  5040.5    0.12       0  5162.9    0.04       0
  5240.5    0.05       0  5670.7    0.04       0
Bank Sta=5033.6,5040.5
Exp/Cntr=0.3,0.1

Type RM Length L Ch R = 1,3095,675,675,675
BEGIN DESCRIPTION:
Mapping XS 367833bd
END DESCRIPTION:
XS GIS Cut Line= 4
      2446339.68     13561652.50      2444475.10     13562121.25
      2443975.10     13562121.25      2443506.34     13562465.01
#Sta/Elev= 30
  3076.8  337.81  3223.2  334.67  3390.8  330.51  3452.8  329.57  3493.0  326.80
  3504.4  325.72  3518.8  327.88  3535.3  328.01  3566.2  325.28  3595.1  326.37
  3772.5  321.82  3924.9  315.21  4089.5  311.88  4300.3  310.93  4349.9  311.22
  4360.2  312.64  4377.4  309.73  4401.5  310.79  4820.8  309.48  4923.0  307.78
  5001.9  306.68  5003.3  305.34  5003.8  304.84  5015.6  305.34  5031.6  306.94
  5059.5  310.28  5079.5  310.93  5220.9  311.80  5636.5  314.39  6080.7  317.00
#Mann=12,-1,0
  3076.8    0.05       0  3223.2    0.04       0  3390.8    0.05       0
  3493.0   0.013       0  3595.1    0.04       0  4820.8    0.12       0
  4923.0    0.04       0  5003.3    0.04       0  5015.6    0.04       0
  5031.6    0.12       0  5220.9    0.05       0  5636.5    0.04       0
Bank Sta=5003.3,5015.6
Exp/Cntr=0.3,0.1

Type RM Length L Ch R = 1,2420,864,864,864
BEGIN DESCRIPTION:
Mapping XS 6b424ff1
END DESCRIPTION:
XS GIS Cut Line= 3
      2446214.70     13561491.04      2444740.73     13561558.75
      2443615.76     13562058.73
#Sta/Elev= 30
  3507.3  335.06  3877.6  322.90  3976.2  321.88  4077.6  317.35  4267.8  312.75
  4408.0  309.70  4598.2  309.58  4658.2  305.94  4768.3  308.01  4798.4  310.72
  4808.4  308.21  4838.4  307.48  4948.5  308.03  4968.5  305.76  4984.0  301.59
  4984.5  301.09  4996.4  301.59  5008.0  304.01  5013.5  302.61  5031.3  305.08
  5068.9  307.60  5286.9  308.15  5432.9  309.68  5613.9  312.00  5864.5  315.39
  5871.2  312.72  5886.4  312.61  5894.4  314.80  5984.9  315.98  6213.9  315.39
#Mann=10,-1,0
  3507.3    0.04       0  3877.6   0.013       0  3976.2    0.04       0
  4984.0    0.04       0  4996.4    0.04       0  5031.3    0.03       0
  5068.9    0.12       0  5286.9    0.04       0  5432.9    0.12       0
  5613.9    0.04       0
Bank Sta=4984,4996.4
Exp/Cntr=0.3,0.1