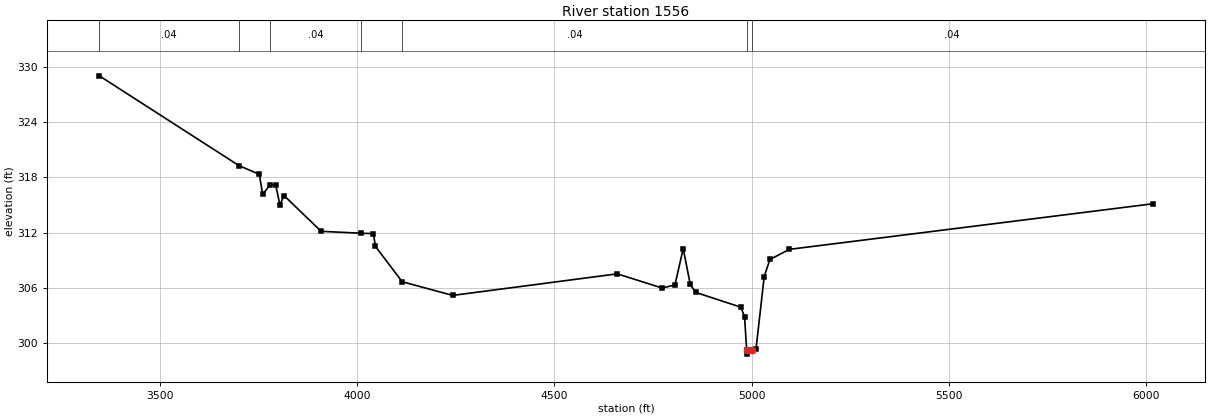
HEC-RAS study TRIB 8 TO YORKTOWN CREEK.prj: TRIB 8 TO YORKTOWN CREEK Base Level Engineering

--- TRIB 8 TO YORKTOWN CREEK.g01 (geometry) --- (continued)

Type RM Length L Ch R = 1,1556,0,0,0
BEGIN DESCRIPTION:
TRIB 8 TO YORKTOWN CREEK 1.0
END DESCRIPTION:
XS GIS Cut Line= 3
      2445813.63     13560600.42      2444225.00     13561075.00
      2443584.80     13561860.43
#Sta/Elev= 30
  3346.1  329.02  3700.1  319.27  3751.7  318.32  3760.4  316.14  3779.6  317.21
  3793.4  317.15  3804.0  314.99  3814.3  316.02  3908.5  312.13  4010.7  311.92
  4041.0  311.88  4046.3  310.49  4114.2  306.65  4242.2  305.17  4659.7  307.51
  4773.2  305.97  4805.8  306.31  4826.7  310.25  4844.6  306.37  4858.0  305.50
  4972.8  303.89  4982.3  302.87  4987.5  299.29  4988.0  298.79  4999.9  299.29
  5011.3  299.33  5032.1  307.21  5046.5  309.07  5096.0  310.17  6017.4  315.12
#Mann=7,-1,0
  3346.1    0.04       0  3700.1   0.013       0  3779.6    0.04       0
  4010.7    0.12       0  4114.2    0.04       0  4987.5    0.04       0
  4999.9    0.04       0
Bank Sta=4987.5,4999.9
Exp/Cntr=0.3,0.1

Chan Stop Cuts=-1