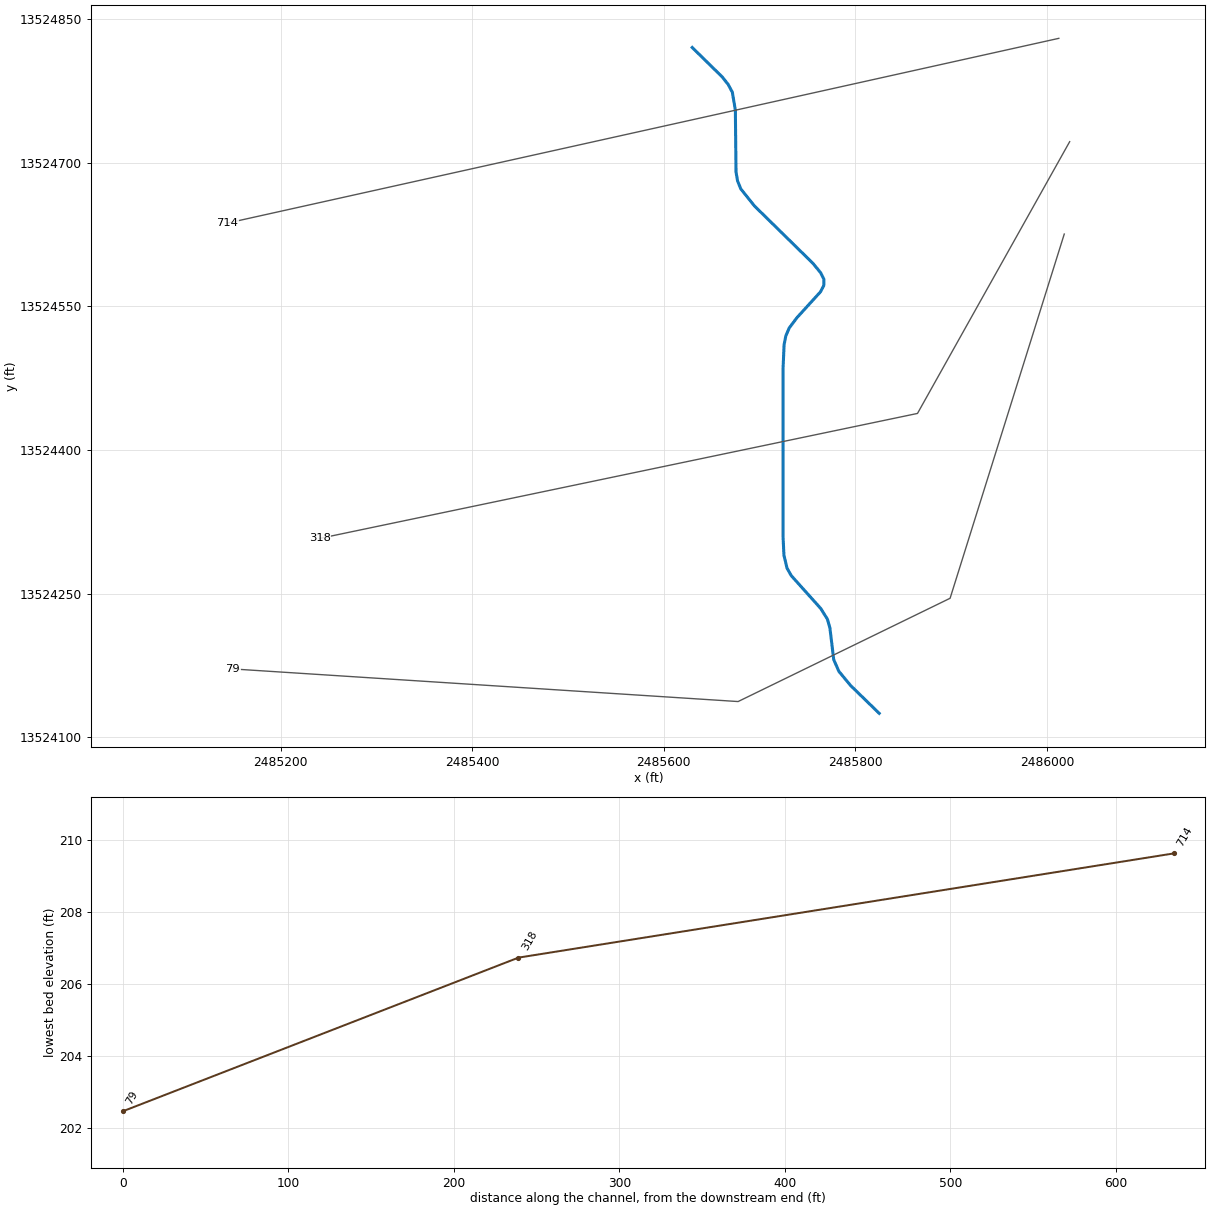
--- TRIB 8_1 TO FIFTEENMILE CREEK.prj (project) ---

Proj Title=TRIB 8_1 TO FIFTEENMILE CREEK Base Level Engineering
Current Plan=p01
Default Exp/Contr=0.3,0.1
English Units
Geom File=g01
Flow File=f01
Plan File=p01
BEGIN DESCRIPTION:
TRIB 8_1 TO FIFTEENMILE CREEK
END DESCRIPTION:

--- TRIB 8_1 TO FIFTEENMILE CREEK.p01 (plan) ---

Plan Title=Multiple Run
Short Identifier=Multiple
Geom File=g01
Flow File=f01
Subcritical Flow
K Sum by GR= 0
Std Step Tol= 0.01
Critical Tol= 0.01
Num of Std Step Trials= 20
Max Error Tol= 0.3
Flow Tol Ratio= 0.001
Split Flow NTrial= 30
Split Flow Tol= 0.02
Split Flow Ratio= 0.02
Log Output Level= 0
Friction Slope Method= 1
Unsteady Friction Slope Method= 2
Unsteady Bridges Friction Slope Method= 1
Parabolic Critical Depth
Global Vel Dist=  1 , 1 , 1
Global Log Level= 0
CheckData=True
Encroach Param= -1, 0, 0, 0
BEGIN DESCRIPTION:
Multiple Run
END DESCRIPTION:

--- TRIB 8_1 TO FIFTEENMILE CREEK.f01 (steady flow) ---

Flow Title=Multiple
Number of Profiles=7
Profile Names=10-year,25-year,50-year,1pct_min,100-year,1pct_plu,500-year
River Rch & RM= TRIB 8_1 TO FIFT,Reach-1,714
     515     818    1086     699    1395    2784    2275
Boundary for River Rch & Prof#=TRIB 8_1 TO FIFT,Reach-1,1
Up Type=0
Dn Type=3
Dn Slope=0.005
Boundary for River Rch & Prof#=TRIB 8_1 TO FIFT,Reach-1,2
Up Type=0
Dn Type=3
Dn Slope=0.005
Boundary for River Rch & Prof#=TRIB 8_1 TO FIFT,Reach-1,3
Up Type=0
Dn Type=3
Dn Slope=0.005
Boundary for River Rch & Prof#=TRIB 8_1 TO FIFT,Reach-1,4
Up Type=0
Dn Type=3
Dn Slope=0.005
Boundary for River Rch & Prof#=TRIB 8_1 TO FIFT,Reach-1,5
Up Type=0
Dn Type=3
Dn Slope=0.005
Boundary for River Rch & Prof#=TRIB 8_1 TO FIFT,Reach-1,6
Up Type=0
Dn Type=3
Dn Slope=0.005
Boundary for River Rch & Prof#=TRIB 8_1 TO FIFT,Reach-1,7
Up Type=0
Dn Type=3
Dn Slope=0.005

--- TRIB 8_1 TO FIFTEENMILE CREEK.g01 (geometry) ---

Geom Title=Existing Conditions

River Reach=TRIB 8_1 TO FIFT,Reach-1
Reach XY= 30
      2485629.72     13524820.28      2485661.11     13524789.52
      2485667.30     13524781.66      2485671.62     13524773.60
      2485674.78     13524754.91      2485675.47     13524690.19
      2485677.12     13524680.87      2485680.52     13524672.56
      2485694.71     13524654.84      2485755.67     13524595.02
      2485763.88     13524585.05      2485767.19     13524578.41
      2485767.12     13524571.78      2485763.66     13524565.15
      2485739.22     13524538.32      2485731.03     13524527.45
      2485727.47     13524519.15      2485725.66     13524509.84
      2485724.60     13524485.21      2485724.56     13524309.82
      2485725.50     13524290.21      2485728.74     13524276.55
      2485733.08     13524268.92      2485763.90     13524234.54
      2485770.92     13524223.31      2485773.48     13524214.37
      2485777.51     13524181.04      2485782.91     13524168.85
      2485795.14     13524154.08      2485825.00     13524125.00

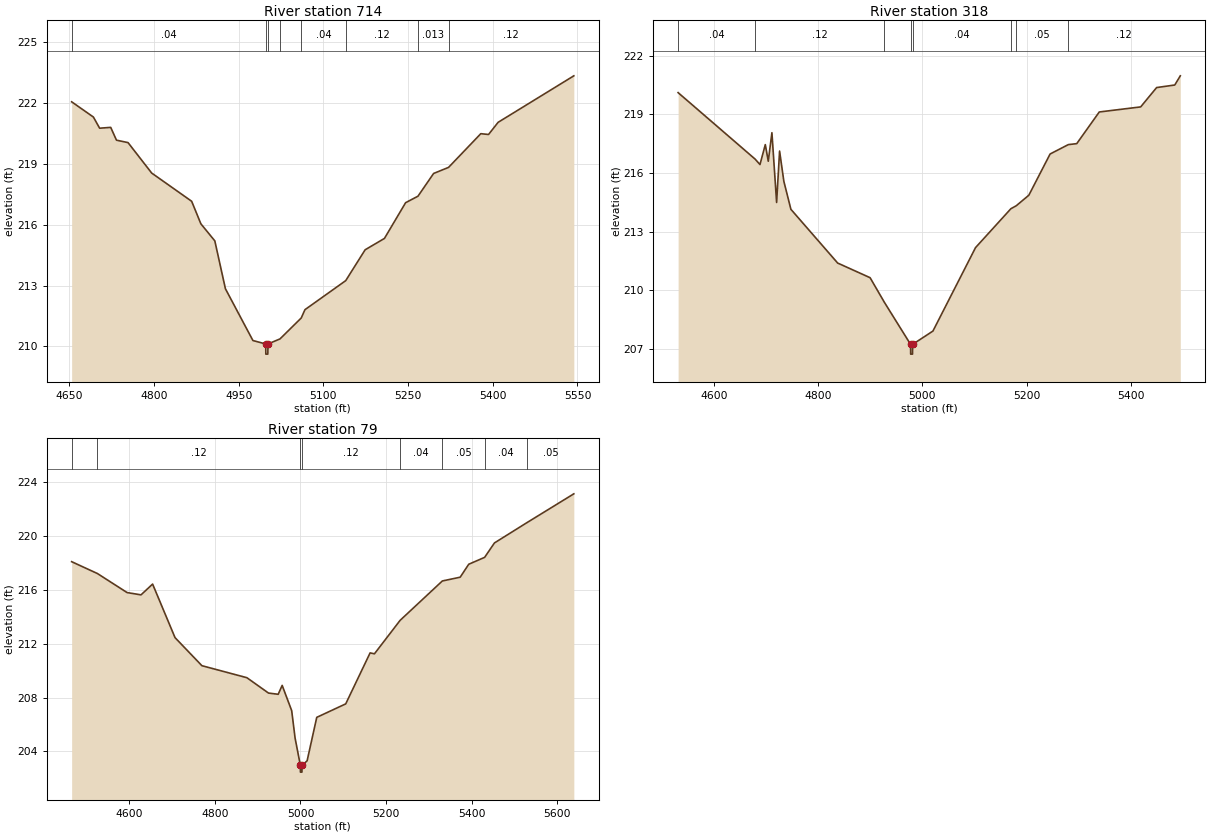
Type RM Length L Ch R = 1,714,396,396,396
BEGIN DESCRIPTION:
LGII4695
END DESCRIPTION:
XS GIS Cut Line= 2
      2486012.54     13524829.85      2485144.13     13524636.86
#Sta/Elev= 30
  4654.0  222.05  4692.5  221.30  4703.6  220.75  4723.2  220.79  4733.4  220.16
  4753.9  220.04  4795.8  218.54  4866.6  217.15  4882.9  216.04  4907.6  215.20
  4926.4  212.84  4975.1  210.29  4997.8  210.12  4998.0  209.62  5001.5  209.62
  5001.8  210.12  5023.1  210.37  5060.7  211.40  5067.3  211.81  5139.5  213.24
  5173.9  214.76  5208.1  215.32  5245.6  217.08  5267.5  217.40  5295.2  218.52
  5321.7  218.82  5378.8  220.48  5392.5  220.44  5409.5  221.04  5543.6  223.33
#Mann=8,-1,0
  4654.0    0.04       0  4997.8    0.04       0  5001.8    0.04       0
  5023.1    0.12       0  5060.7    0.04       0  5139.5    0.12       0
  5267.5   0.013       0  5321.7    0.12       0
Bank Sta=4997.8,5001.8
Exp/Cntr=0.3,0.1

Type RM Length L Ch R = 1,318,239,239,239
BEGIN DESCRIPTION:
LGII4694
END DESCRIPTION:
XS GIS Cut Line= 3
      2486023.87     13524721.97      2485864.96     13524438.19
      2485240.61     13524307.64
#Sta/Elev= 30
  4531.7  220.11  4679.3  216.71  4688.7  216.43  4698.9  217.45  4704.6  216.60
  4711.6  218.06  4720.6  214.49  4726.3  217.12  4734.5  215.57  4748.0  214.14
  4837.7  211.39  4899.9  210.64  4927.3  209.38  4977.5  207.23  4977.7  206.73
  4981.2  206.73  4981.5  207.23  5020.4  207.91  5102.1  212.18  5169.9  214.17
  5180.1  214.32  5204.3  214.86  5245.1  216.97  5280.0  217.45  5296.2  217.50
  5339.4  219.12  5418.8  219.38  5449.4  220.37  5484.2  220.50  5494.8  220.97
#Mann=8,-1,0
  4531.7    0.04       0  4679.3    0.12       0  4927.3    0.04       0
  4977.5    0.04       0  4981.5    0.04       0  5169.9    0.12       0
  5180.1    0.05       0  5280.0    0.12       0
Bank Sta=4977.5,4981.5
Exp/Cntr=0.3,0.1

Type RM Length L Ch R = 1,79,0,0,0
BEGIN DESCRIPTION:
LGII4693
END DESCRIPTION:
XS GIS Cut Line= 4
      2486018.21     13524625.50      2485899.01     13524245.20
      2485677.64     13524137.35      2485149.93     13524171.40
#Sta/Elev= 30
  4465.3  218.07  4525.6  217.19  4594.9  215.78  4627.4  215.61  4654.5  216.41
  4706.9  212.44  4769.7  210.36  4874.8  209.47  4925.4  208.33  4948.0  208.24
  4957.3  208.90  4979.5  207.03  4987.5  204.99  4999.8  202.97  5000.0  202.47
  5003.5  202.47  5003.8  202.97  5015.6  203.31  5038.1  206.53  5105.8  207.53
  5162.8  211.31  5172.9  211.24  5232.9  213.72  5331.6  216.64  5373.3  216.92
  5393.3  217.88  5430.4  218.39  5453.4  219.46  5529.1  220.96  5638.9  223.10
#Mann=8,-1,0
  4465.3    0.04       0  4525.6    0.12       0  4999.8    0.05       0
  5003.8    0.12       0  5232.9    0.04       0  5331.6    0.05       0
  5430.4    0.04       0  5529.1    0.05       0
Bank Sta=4999.8,5003.8
Exp/Cntr=0.3,0.1

Chan Stop Cuts=-1