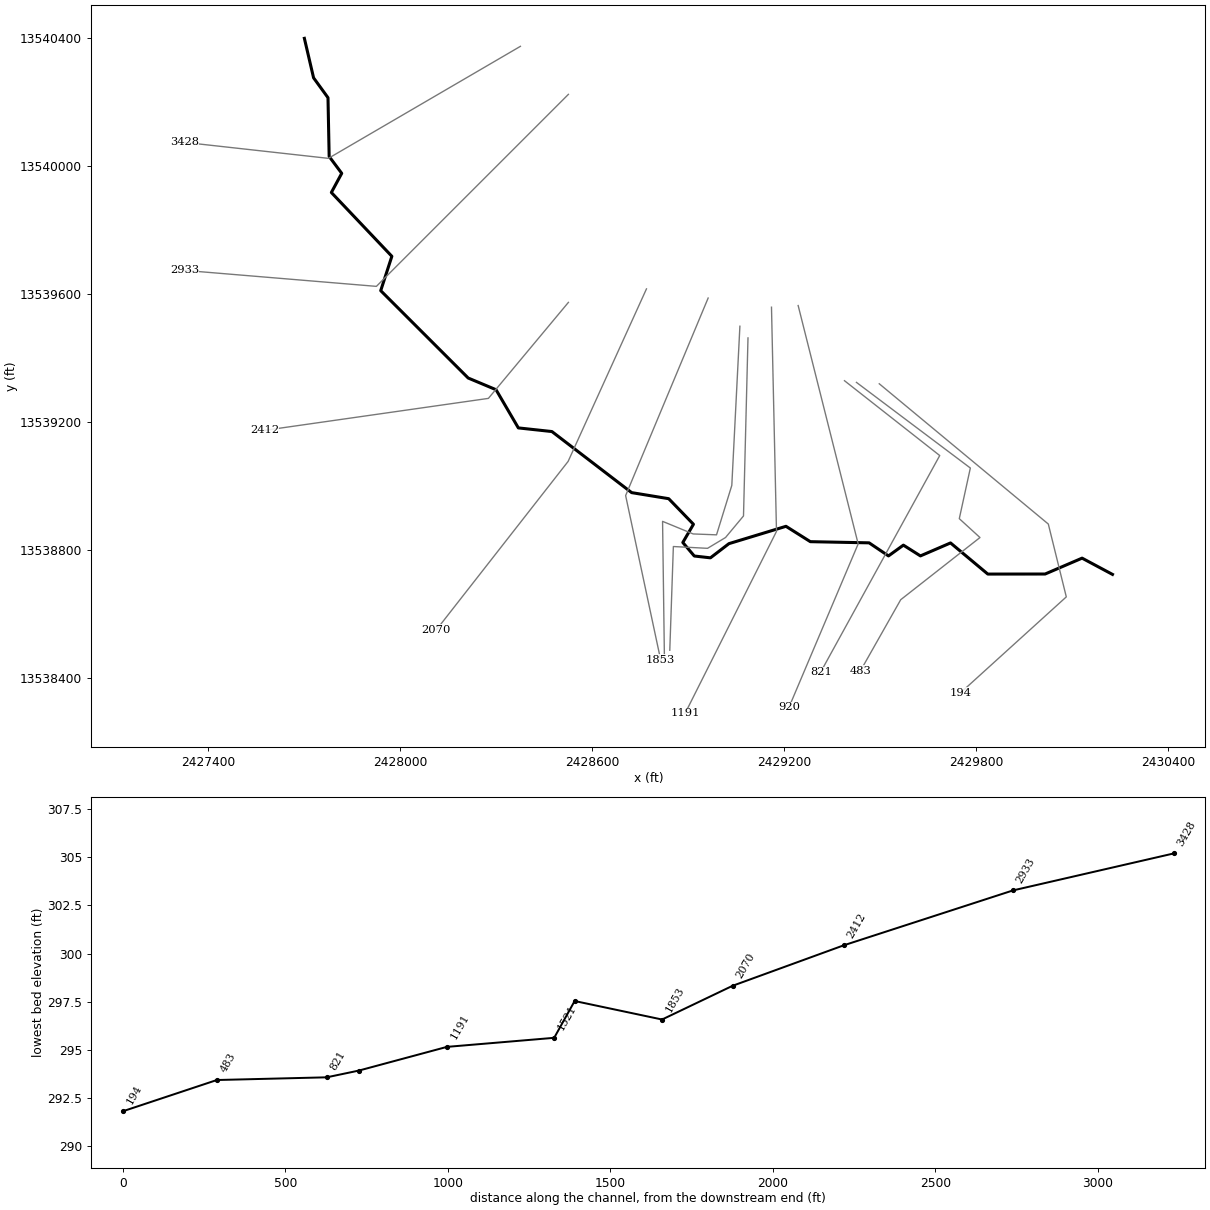
--- TRIB 8_1 TO SMITH CREEK.prj (project) ---

Proj Title=TRIB 8_1 TO SMITH CREEK Base Level Engineering
Current Plan=p01
Default Exp/Contr=0.3,0.1
English Units
Geom File=g01
Flow File=f01
Plan File=p01
BEGIN DESCRIPTION:
TRIB 8_1 TO SMITH CREEK
END DESCRIPTION:

--- TRIB 8_1 TO SMITH CREEK.p01 (plan) ---

Plan Title=Multiple Run
Short Identifier=Multiple
Geom File=g01
Flow File=f01
Subcritical Flow
K Sum by GR= 0
Std Step Tol= 0.01
Critical Tol= 0.01
Num of Std Step Trials= 20
Max Error Tol= 0.3
Flow Tol Ratio= 0.001
Split Flow NTrial= 30
Split Flow Tol= 0.02
Split Flow Ratio= 0.02
Log Output Level= 0
Friction Slope Method= 1
Unsteady Friction Slope Method= 2
Unsteady Bridges Friction Slope Method= 1
Parabolic Critical Depth
Global Vel Dist=  1 , 1 , 1
Global Log Level= 0
CheckData=True
Encroach Param= -1, 0, 0, 0
BEGIN DESCRIPTION:
Multiple Run
END DESCRIPTION:

--- TRIB 8_1 TO SMITH CREEK.f01 (steady flow) ---

Flow Title=Multiple
Number of Profiles=7
Profile Names=10-year,25-year,50-year,1pct_min,100-year,1pct_plu,500-year
River Rch & RM= TRIB 8_1 TO SMIT,Reach-1,3428
     680    1101    1482     966    1927    3844    3223
Boundary for River Rch & Prof#=TRIB 8_1 TO SMIT,Reach-1,1
Up Type=0
Dn Type=3
Dn Slope=0.005
Boundary for River Rch & Prof#=TRIB 8_1 TO SMIT,Reach-1,2
Up Type=0
Dn Type=3
Dn Slope=0.005
Boundary for River Rch & Prof#=TRIB 8_1 TO SMIT,Reach-1,3
Up Type=0
Dn Type=3
Dn Slope=0.005
Boundary for River Rch & Prof#=TRIB 8_1 TO SMIT,Reach-1,4
Up Type=0
Dn Type=3
Dn Slope=0.005
Boundary for River Rch & Prof#=TRIB 8_1 TO SMIT,Reach-1,5
Up Type=0
Dn Type=3
Dn Slope=0.005
Boundary for River Rch & Prof#=TRIB 8_1 TO SMIT,Reach-1,6
Up Type=0
Dn Type=3
Dn Slope=0.005
Boundary for River Rch & Prof#=TRIB 8_1 TO SMIT,Reach-1,7
Up Type=0
Dn Type=3
Dn Slope=0.005

--- TRIB 8_1 TO SMITH CREEK.g01 (geometry) ---

Geom Title=Existing Conditions

River Reach=TRIB 8_1 TO SMIT,Reach-1
Reach XY= 30
      2427700.00     13540400.00      2427728.77     13540276.56
      2427773.79     13540214.50      2427777.45     13540030.85
      2427816.71     13539978.21      2427784.30     13539918.33
      2427973.34     13539718.95      2427938.54     13539611.62
      2428211.80     13539338.64      2428298.83     13539302.13
      2428368.55     13539182.75      2428473.50     13539171.37
      2428722.58     13538980.54      2428838.36     13538961.60
      2428915.70     13538881.68      2428882.47     13538824.72
      2428918.32     13538782.48      2428968.79     13538776.78
      2429026.58     13538821.11      2429204.82     13538875.28
      2429280.93     13538827.29      2429464.57     13538823.62
      2429525.10     13538782.78      2429571.67     13538816.45
      2429624.91     13538782.81      2429718.95     13538823.34
      2429835.44     13538726.05      2430014.50     13538726.22
      2430129.99     13538775.81      2430225.00     13538725.00

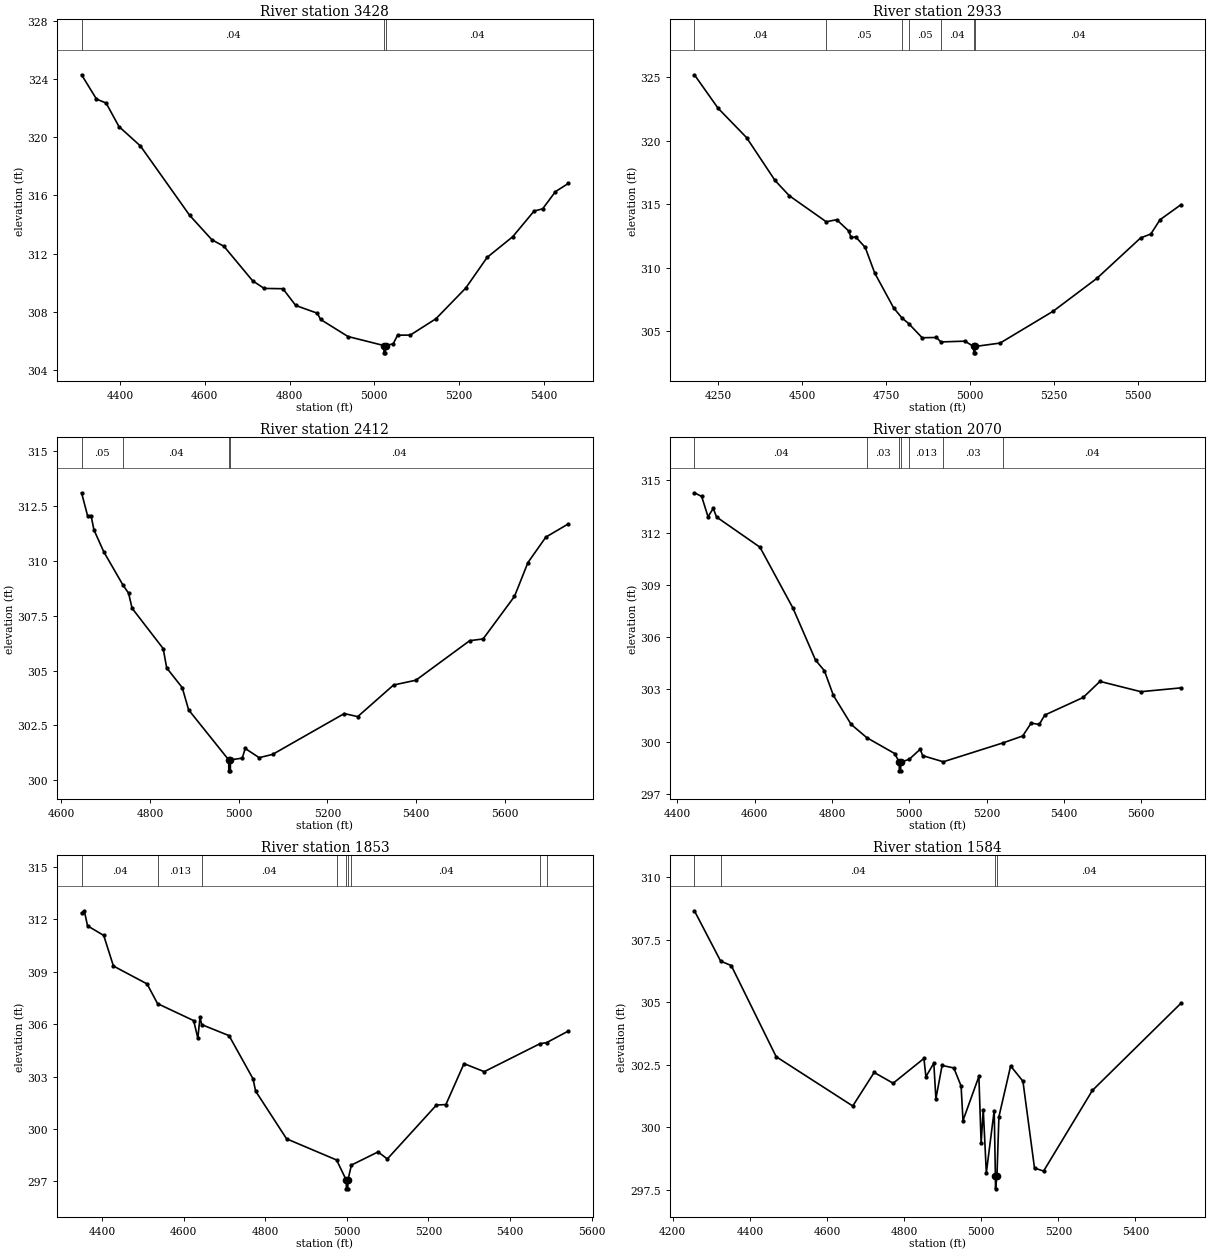
Type RM Length L Ch R = 1,3428,495,495,495
BEGIN DESCRIPTION:
TRIB 8_1 TO SMITH CREEK 7.0
END DESCRIPTION:
XS GIS Cut Line= 3
      2428375.01     13540375.01      2427775.00     13540025.00
      2427325.01     13540075.00
#Sta/Elev= 30
  4309.7  324.28  4344.9  322.61  4367.6  322.34  4397.8  320.73  4448.6  319.39
  4564.4  314.64  4616.9  312.96  4645.4  312.51  4712.8  310.15  4740.1  309.62
  4784.4  309.60  4814.6  308.45  4865.4  307.92  4873.3  307.49  4937.8  306.32
  5022.5  305.70  5022.7  305.20  5026.2  305.20  5026.5  305.70  5044.6  305.82
  5054.6  306.41  5084.8  306.42  5145.2  307.54  5215.6  309.65  5265.9  311.75
  5326.3  313.17  5376.6  314.93  5396.7  315.08  5426.9  316.26  5457.1  316.82
#Mann=3,-1,0
  4309.7    0.04       0  5022.5    0.04       0  5026.5    0.04       0
Bank Sta=5022.5,5026.5
Exp/Cntr=0.3,0.1

Type RM Length L Ch R = 1,2933,521,521,521
BEGIN DESCRIPTION:
TRIB 8_1 TO SMITH CREEK 6.0
END DESCRIPTION:
XS GIS Cut Line= 3
      2428524.97     13540224.97      2427925.00     13539625.00
      2427324.97     13539675.00
#Sta/Elev= 30
  4179.0  325.19  4249.7  322.55  4334.5  320.24  4419.4  316.86  4461.8  315.66
  4571.9  313.61  4603.2  313.77  4638.6  312.89  4645.7  312.38  4659.8  312.41
  4688.1  311.59  4716.4  309.57  4772.9  306.82  4797.2  306.04  4817.5  305.59
  4857.8  304.47  4900.2  304.49  4913.6  304.14  4985.1  304.20  5011.3  303.78
  5011.6  303.28  5015.1  303.28  5015.3  303.78  5090.2  304.05  5248.3  306.56
  5378.7  309.15  5509.2  312.34  5539.3  312.64  5566.9  313.77  5629.6  314.96
#Mann=7,-1,0
  4179.0    0.04       0  4571.9    0.05       0  4797.2    0.04       0
  4817.5    0.05       0  4913.6    0.04       0  5011.3    0.04       0
  5015.3    0.04       0
Bank Sta=5011.3,5015.3
Exp/Cntr=0.3,0.1

Type RM Length L Ch R = 1,2412,342,342,342
BEGIN DESCRIPTION:
TRIB 8_1 TO SMITH CREEK 5.0
END DESCRIPTION:
XS GIS Cut Line= 3
      2428524.97     13539574.97      2428275.00     13539275.00
      2427574.98     13539175.00
#Sta/Elev= 30
  4645.7  313.10  4659.3  312.05  4667.1  312.06  4673.6  311.41  4695.8  310.41
  4739.5  308.88  4751.7  308.53  4759.6  307.84  4829.8  306.00  4837.7  305.12
  4872.8  304.22  4887.1  303.21  4977.5  300.93  4977.8  300.43  4981.3  300.43
  4981.5  300.93  5008.2  301.01  5014.7  301.45  5046.3  301.03  5076.6  301.18
  5238.2  303.04  5268.5  302.90  5349.3  304.34  5399.8  304.56  5521.0  306.36
  5551.3  306.44  5622.1  308.38  5652.4  309.92  5692.8  311.08  5743.3  311.68
#Mann=4,-1,0
  4645.7    0.05       0  4739.5    0.04       0  4977.5    0.04       0
  4981.5    0.04       0
Bank Sta=4977.5,4981.5
Exp/Cntr=0.3,0.1

Type RM Length L Ch R = 1,2070,217,217,217
BEGIN DESCRIPTION:
Mapping XS b97e4123
END DESCRIPTION:
XS GIS Cut Line= 3
      2428768.90     13539617.16      2428524.12     13539078.11
      2428112.64     13538552.05
#Sta/Elev= 30
  4443.8  314.28  4462.6  314.07  4479.1  312.90  4492.6  313.39  4501.1  312.89
  4613.4  311.16  4698.8  307.67  4757.4  304.68  4780.4  304.07  4803.5  302.66
  4849.7  300.99  4890.3  300.23  4962.4  299.32  4974.0  298.83  4974.3  298.33
  4977.8  298.33  4978.0  298.83  4999.9  298.99  5028.3  299.57  5034.8  299.20
  5088.2  298.85  5242.2  299.93  5293.7  300.33  5315.6  301.07  5336.4  300.99
  5350.9  301.53  5450.3  302.54  5493.7  303.46  5599.6  302.87  5703.7  303.09
#Mann=7,-1,0
  4443.8    0.04       0  4890.3    0.03       0  4974.0    0.03       0
  4978.0    0.03       0  4999.9   0.013       0  5088.2    0.03       0
  5242.2    0.04       0
Bank Sta=4974,4978
Exp/Cntr=0.3,0.1

Type RM Length L Ch R = 1,1853,269,269,269
BEGIN DESCRIPTION:
Mapping XS 259c0e5a
END DESCRIPTION:
XS GIS Cut Line= 3
      2428961.61     13539588.52      2428703.80     13538971.33
      2428813.01     13538459.11
#Sta/Elev= 30
  4350.2  312.36  4356.9  312.48  4364.8  311.62  4404.5  311.07  4428.3  309.32
  4510.6  308.30  4536.5  307.17  4624.9  306.20  4635.1  305.20  4640.5  306.39
  4644.6  305.97  4711.6  305.34  4770.4  302.87  4776.7  302.17  4852.6  299.44
  4975.1  298.23  4998.9  297.08  4999.2  296.58  5002.7  296.58  5002.9  297.08
  5011.5  297.94  5076.7  298.69  5099.5  298.29  5219.8  301.37  5243.0  301.40
  5287.4  303.74  5337.0  303.28  5473.6  304.88  5489.8  304.94  5542.8  305.60
#Mann=9,-1,0
  4350.2    0.04       0  4536.5   0.013       0  4644.6    0.04       0
  4975.1    0.03       0  4998.9    0.03       0  5002.9    0.03       0
  5011.5    0.04       0  5473.6   0.013       0  5489.8    0.04       0
Bank Sta=4998.9,5002.9
Exp/Cntr=0.3,0.1

Type RM Length L Ch R = 1,1584,63,63,63
BEGIN DESCRIPTION:
4899
END DESCRIPTION:
XS GIS Cut Line= 6
      2429060.83     13539500.46      2429035.55     13539003.16
      2428987.79     13538848.64      2428914.74     13538851.45
      2428819.21     13538890.78      2428824.83     13538474.93
#Sta/Elev= 30
  4256.3  308.65  4324.3  306.64  4351.9  306.46  4468.3  302.82  4666.9  300.85
  4722.4  302.19  4771.7  301.76  4851.5  302.75  4856.6  302.02  4877.1  302.56
  4882.5  301.14  4898.6  302.47  4929.0  302.37  4947.8  301.65  4952.8  300.27
  4994.0  302.03  4999.8  299.36  5005.3  300.71  5013.3  298.18  5033.7  300.67
  5036.8  298.04  5037.1  297.54  5040.8  298.04  5045.9  300.42  5076.3  302.45
  5108.2  301.84  5138.2  298.37  5161.8  298.25  5288.2  301.47  5518.3  304.96
#Mann=4,-1,0
  4256.3   0.013       0  4324.3    0.04       0  5036.8    0.04       0
  5040.8    0.04       0
Bank Sta=5036.8,5040.8
Exp/Cntr=0.3,0.1

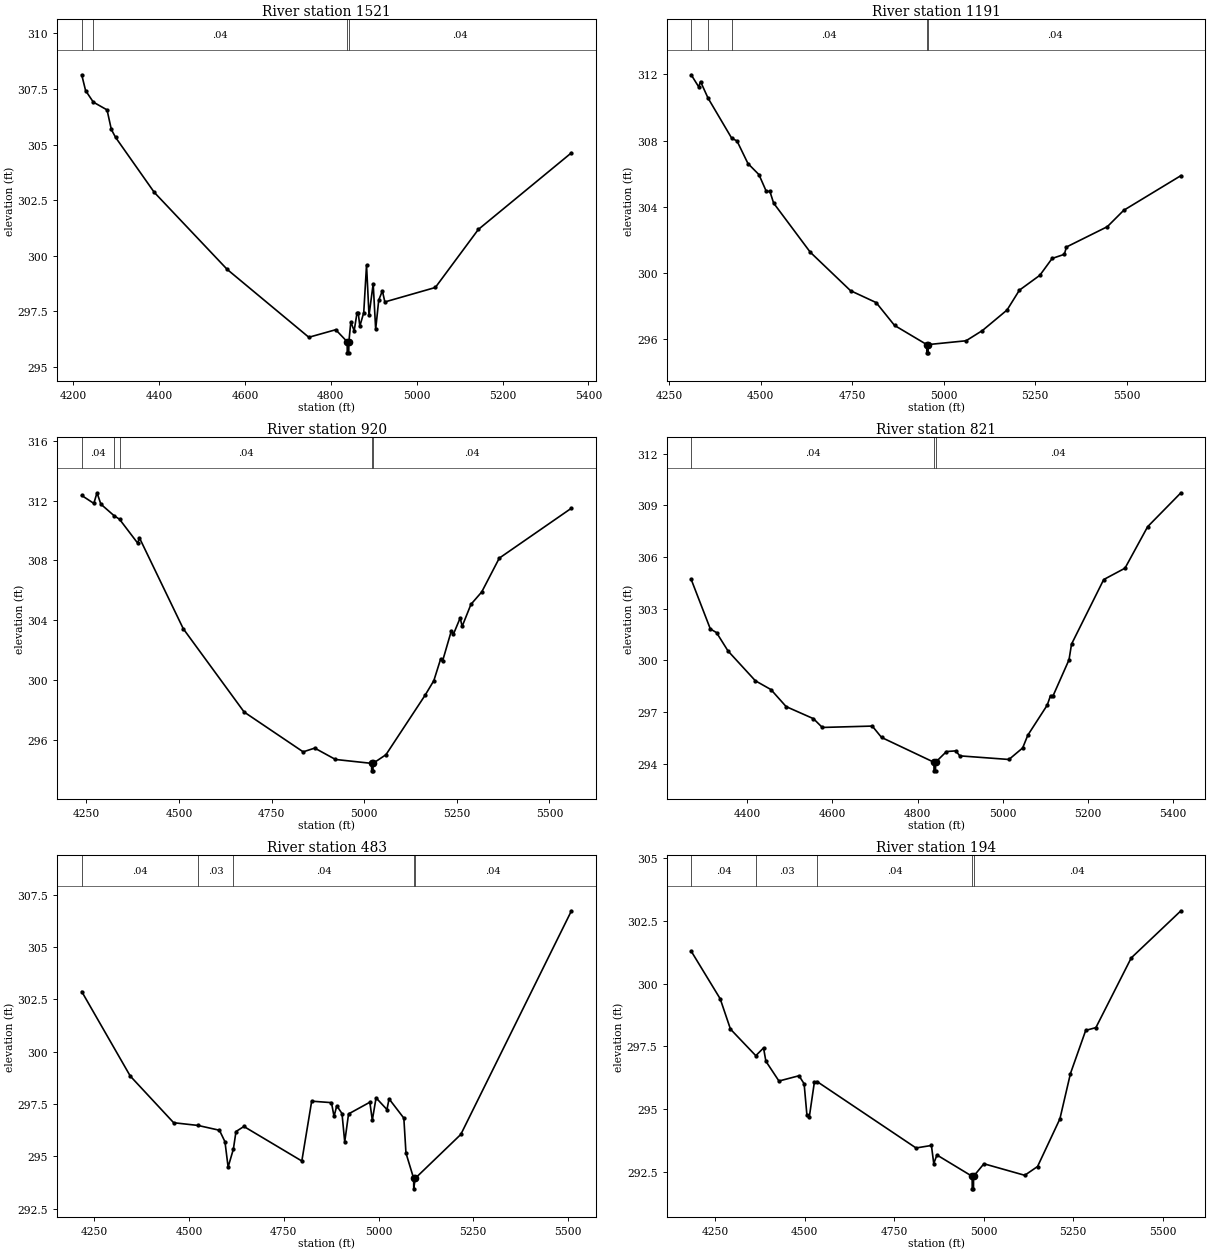
Type RM Length L Ch R = 1,1521,330,330,330
BEGIN DESCRIPTION:
4900
END DESCRIPTION:
XS GIS Cut Line= 6
      2429086.12     13539463.96      2429072.07     13538907.64
      2429015.88     13538840.21      2428959.69     13538806.49
      2428852.93     13538812.11      2428841.76     13538488.12
#Sta/Elev= 30
  4219.7  308.14  4228.7  307.43  4246.7  306.91  4278.7  306.56  4288.7  305.68
  4298.7  305.32  4388.7  302.85  4558.8  299.38  4748.8  296.33  4811.4  296.67
  4838.1  296.13  4838.3  295.63  4841.8  295.63  4842.1  296.13  4846.6  297.02
  4854.4  296.62  4860.8  297.40  4864.0  297.40  4867.6  296.83  4876.7  297.44
  4883.2  299.58  4889.0  297.31  4898.7  298.74  4904.5  296.69  4911.6  298.00
  4920.1  298.42  4925.9  297.92  5043.5  298.57  5143.6  301.18  5360.6  304.63
#Mann=4,-1,0
  4219.7   0.013       0  4246.7    0.04       0  4838.1    0.04       0
  4842.1    0.04       0
Bank Sta=4838.1,4842.1
Exp/Cntr=0.3,0.1

Type RM Length L Ch R = 1,1191,271,271,271
BEGIN DESCRIPTION:
Mapping XS 0a58c4bd
END DESCRIPTION:
XS GIS Cut Line= 3
      2429159.53     13539559.92      2429175.16     13538859.36
      2428889.58     13538290.79
#Sta/Elev= 30
  4310.6  311.98  4331.1  311.25  4336.1  311.57  4356.6  310.57  4421.3  308.14
  4435.6  307.98  4465.6  306.61  4495.6  305.94  4515.6  304.93  4525.6  304.92
  4535.6  304.22  4635.6  301.25  4745.6  298.92  4815.6  298.20  4865.7  296.82
  4953.7  295.66  4953.9  295.16  4957.4  295.16  4957.7  295.66  5061.0  295.89
  5105.7  296.51  5172.9  297.75  5206.6  298.95  5262.4  299.85  5296.0  300.87
  5329.4  301.12  5334.9  301.56  5446.6  302.79  5491.3  303.78  5647.6  305.88
#Mann=5,-1,0
  4310.6    0.04       0  4356.6   0.013       0  4421.3    0.04       0
  4953.7    0.04       0  4957.7    0.04       0
Bank Sta=4953.7,4957.7
Exp/Cntr=0.3,0.1

Type RM Length L Ch R = 1,920,99,99,99
BEGIN DESCRIPTION:
Mapping XS 82e1ccd0
END DESCRIPTION:
XS GIS Cut Line= 3
      2429242.86     13539565.09      2429430.37     13538820.29
      2429214.23     13538309.91
#Sta/Elev= 30
  4237.2  312.34  4269.9  311.81  4278.5  312.52  4288.9  311.76  4324.5  310.99
  4339.3  310.75  4388.1  309.16  4393.2  309.50  4511.4  303.43  4675.8  297.86
  4835.1  295.20  4866.3  295.45  4922.4  294.69  5019.8  294.43  5020.1  293.93
  5023.6  293.93  5023.8  294.43  5058.7  295.01  5164.2  298.98  5187.9  299.96
  5206.2  301.40  5211.6  301.28  5235.3  303.30  5240.7  303.06  5259.0  304.15
  5264.4  303.59  5288.1  305.06  5317.2  305.89  5364.6  308.15  5559.5  311.49
#Mann=5,-1,0
  4237.2    0.04       0  4324.5   0.013       0  4339.3    0.04       0
  5019.8    0.04       0  5023.8    0.04       0
Bank Sta=5019.8,5023.8
Exp/Cntr=0.3,0.1

Type RM Length L Ch R = 1,821,338,338,338
BEGIN DESCRIPTION:
4908
END DESCRIPTION:
XS GIS Cut Line= 3
      2429387.64     13539330.19      2429685.22     13539096.38
      2429313.28     13538419.82
#Sta/Elev= 30
  4268.2  304.70  4313.2  301.82  4327.7  301.61  4354.8  300.54  4419.0  298.81
  4455.6  298.30  4491.3  297.31  4555.4  296.61  4576.2  296.10  4693.6  296.18
  4715.4  295.52  4838.4  294.08  4838.7  293.58  4842.2  293.58  4842.4  294.08
  4867.9  294.70  4889.7  294.74  4899.3  294.45  5014.7  294.24  5046.9  294.91
  5059.0  295.65  5104.7  297.40  5112.3  297.95  5118.0  297.92  5155.8  300.03
  5161.7  300.94  5237.3  304.69  5287.3  305.35  5340.5  307.76  5418.7  309.73
#Mann=3,-1,0
  4268.2    0.04       0  4838.4    0.04       0  4842.4    0.04       0
Bank Sta=4838.4,4842.4
Exp/Cntr=0.3,0.1

Type RM Length L Ch R = 1,483,289,289,289
BEGIN DESCRIPTION:
TRIB 8_1 TO SMITH CREEK 1.0
END DESCRIPTION:
XS GIS Cut Line= 6
      2429425.00     13539325.00      2429780.87     13539057.41
      2429746.35     13538899.21      2429810.97     13538840.21
      2429563.29     13538645.92      2429437.22     13538423.26
#Sta/Elev= 30
  4216.8  302.87  4344.9  298.83  4459.4  296.60  4523.7  296.47  4580.2  296.24
  4594.8  295.69  4603.1  294.48  4617.0  295.34  4623.9  296.18  4644.8  296.42
  4797.6  294.77  4823.6  297.63  4875.8  297.56  4882.6  296.90  4889.8  297.41
  4903.6  297.04  4910.8  295.68  4920.9  297.02  4977.1  297.58  4983.6  296.72
  4993.5  297.79  5022.2  297.23  5027.8  297.74  5066.8  296.82  5072.4  295.15
  5092.7  293.94  5092.9  293.44  5096.7  293.94  5217.1  296.04  5509.1  306.73
#Mann=5,-1,0
  4216.8    0.04       0  4523.7    0.03       0  4617.0    0.04       0
  5092.7    0.04       0  5096.7    0.04       0
Bank Sta=5092.7,5096.7
Exp/Cntr=0.3,0.1

Type RM Length L Ch R = 1,194,0,0,0
BEGIN DESCRIPTION:
4901
END DESCRIPTION:
XS GIS Cut Line= 4
      2429496.32     13539320.62      2430024.50     13538882.35
      2430080.69     13538654.78      2429749.58     13538354.54
#Sta/Elev= 30
  4183.1  301.30  4264.1  299.40  4292.8  298.19  4363.6  297.13  4385.2  297.44
  4391.7  296.91  4428.2  296.12  4484.2  296.33  4498.5  296.01  4506.2  294.78
  4512.8  294.67  4527.2  296.08  4534.5  296.10  4811.0  293.45  4854.0  293.55
  4860.5  292.83  4869.4  293.17  4967.7  292.32  4968.0  291.82  4971.5  291.82
  4971.7  292.32  5000.6  292.82  5114.6  292.36  5150.4  292.71  5212.8  294.61
  5242.3  296.42  5284.9  298.14  5313.3  298.25  5412.0  301.03  5550.8  302.91
#Mann=5,-1,0
  4183.1    0.04       0  4363.6    0.03       0  4534.5    0.04       0
  4967.7    0.04       0  4971.7    0.04       0
Bank Sta=4967.7,4971.7
Exp/Cntr=0.3,0.1

Chan Stop Cuts=-1