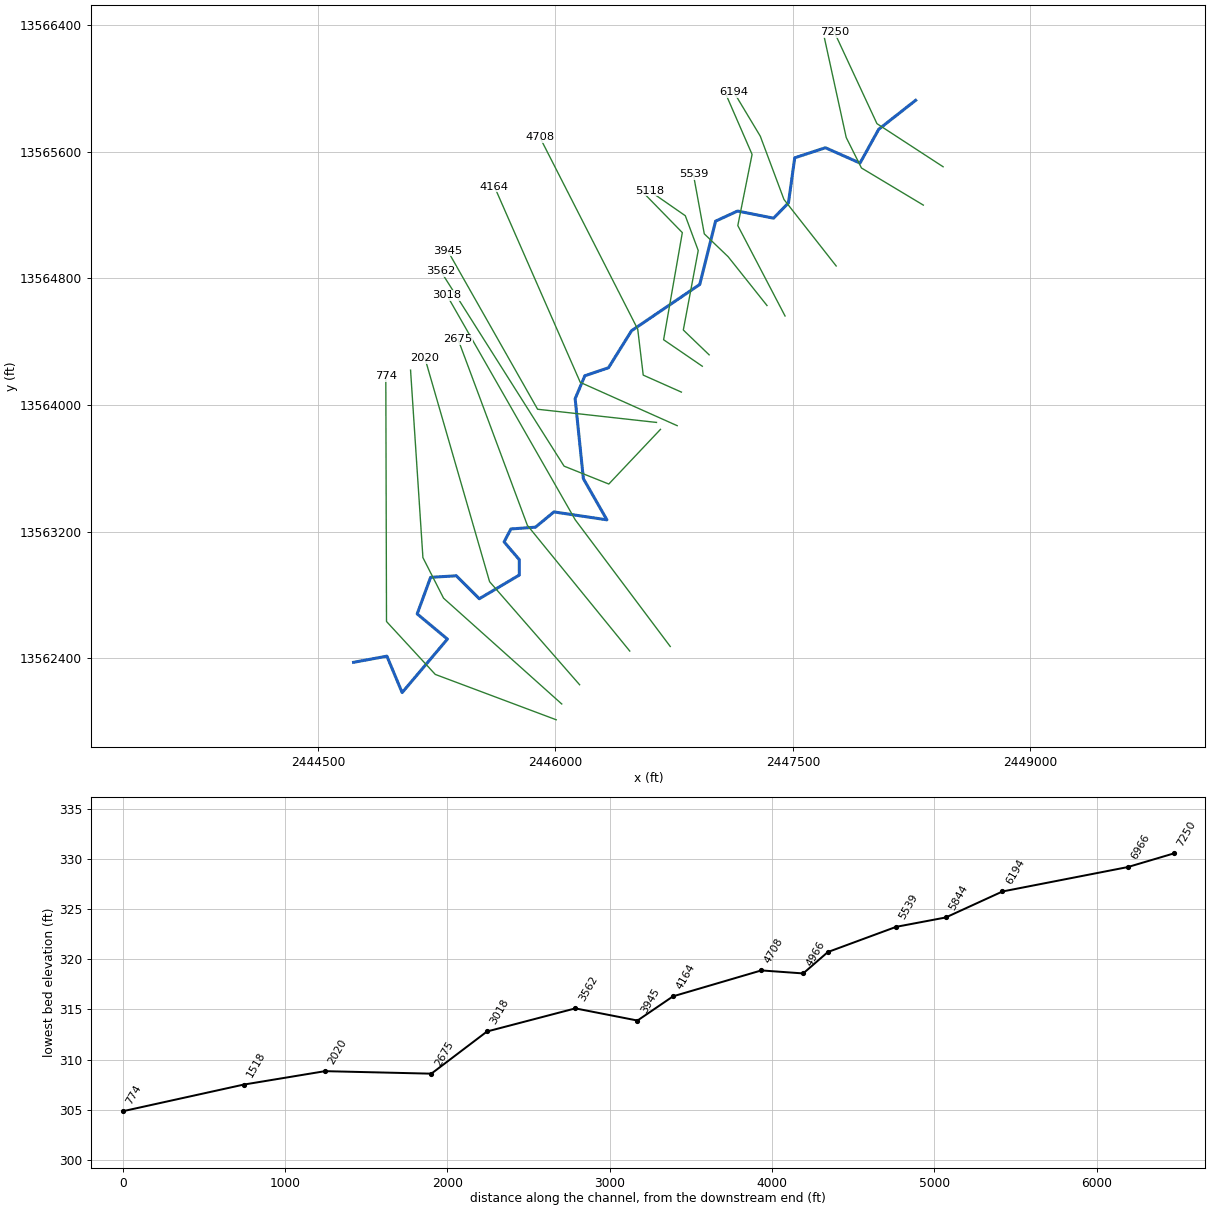
--- TRIB 8_1 TO YORKTOWN CREEK.prj (project) ---

Proj Title=TRIB 8_1 TO YORKTOWN CREEK Base Level Engineering
Current Plan=p01
Default Exp/Contr=0.3,0.1
English Units
Geom File=g01
Flow File=f01
Plan File=p01
BEGIN DESCRIPTION:
TRIB 8_1 TO YORKTOWN CREEK
END DESCRIPTION:

--- TRIB 8_1 TO YORKTOWN CREEK.p01 (plan) ---

Plan Title=Multiple Run
Short Identifier=Multiple
Geom File=g01
Flow File=f01
Subcritical Flow
K Sum by GR= 0
Std Step Tol= 0.01
Critical Tol= 0.01
Num of Std Step Trials= 20
Max Error Tol= 0.3
Flow Tol Ratio= 0.001
Split Flow NTrial= 30
Split Flow Tol= 0.02
Split Flow Ratio= 0.02
Log Output Level= 0
Friction Slope Method= 1
Unsteady Friction Slope Method= 2
Unsteady Bridges Friction Slope Method= 1
Parabolic Critical Depth
Global Vel Dist=  1 , 1 , 1
Global Log Level= 0
CheckData=True
Encroach Param= -1, 0, 0, 0
BEGIN DESCRIPTION:
Multiple Run
END DESCRIPTION:

--- TRIB 8_1 TO YORKTOWN CREEK.f01 (steady flow) ---

Flow Title=Multiple
Number of Profiles=7
Profile Names=10-year,25-year,50-year,1pct_min,100-year,1pct_plu,500-year
River Rch & RM= TRIB 8_1 TO YORK,Reach-1,7250
     618     998    1340     871    1739    3469    2902
River Rch & RM= TRIB 8_1 TO YORK,Reach-1,3018
    1164    1942    2668    1771    3534    7051    6149
Boundary for River Rch & Prof#=TRIB 8_1 TO YORK,Reach-1,1
Up Type=0
Dn Type=3
Dn Slope=0.005
Boundary for River Rch & Prof#=TRIB 8_1 TO YORK,Reach-1,2
Up Type=0
Dn Type=3
Dn Slope=0.005
Boundary for River Rch & Prof#=TRIB 8_1 TO YORK,Reach-1,3
Up Type=0
Dn Type=3
Dn Slope=0.005
Boundary for River Rch & Prof#=TRIB 8_1 TO YORK,Reach-1,4
Up Type=0
Dn Type=3
Dn Slope=0.005
Boundary for River Rch & Prof#=TRIB 8_1 TO YORK,Reach-1,5
Up Type=0
Dn Type=3
Dn Slope=0.005
Boundary for River Rch & Prof#=TRIB 8_1 TO YORK,Reach-1,6
Up Type=0
Dn Type=3
Dn Slope=0.005
Boundary for River Rch & Prof#=TRIB 8_1 TO YORK,Reach-1,7
Up Type=0
Dn Type=3
Dn Slope=0.005

--- TRIB 8_1 TO YORKTOWN CREEK.g01 (geometry) ---

Geom Title=Existing Conditions

River Reach=TRIB 8_1 TO YORK,Reach-1
Reach XY= 30
      2448275.00     13565925.00      2448041.63     13565741.71
      2447923.72     13565528.37      2447704.95     13565625.21
      2447511.36     13565561.56      2447471.47     13565276.45
      2447377.44     13565180.39      2447150.00     13565225.41
      2447011.37     13565161.55      2446911.39     13564761.76
      2446480.59     13564469.39      2446334.81     13564235.51
      2446185.61     13564185.06      2446124.28     13564040.06
      2446176.20     13563535.50      2446325.00     13563275.00
      2445990.34     13563325.04      2445873.53     13563228.56
      2445718.43     13563217.30      2445675.53     13563135.69
      2445771.53     13563023.50      2445771.64     13562926.25
      2445518.91     13562776.57      2445373.75     13562921.56
      2445211.27     13562911.81      2445126.54     13562680.85
      2445317.42     13562521.68      2445031.49     13562183.88
      2444935.38     13562413.92      2444725.00     13562375.00

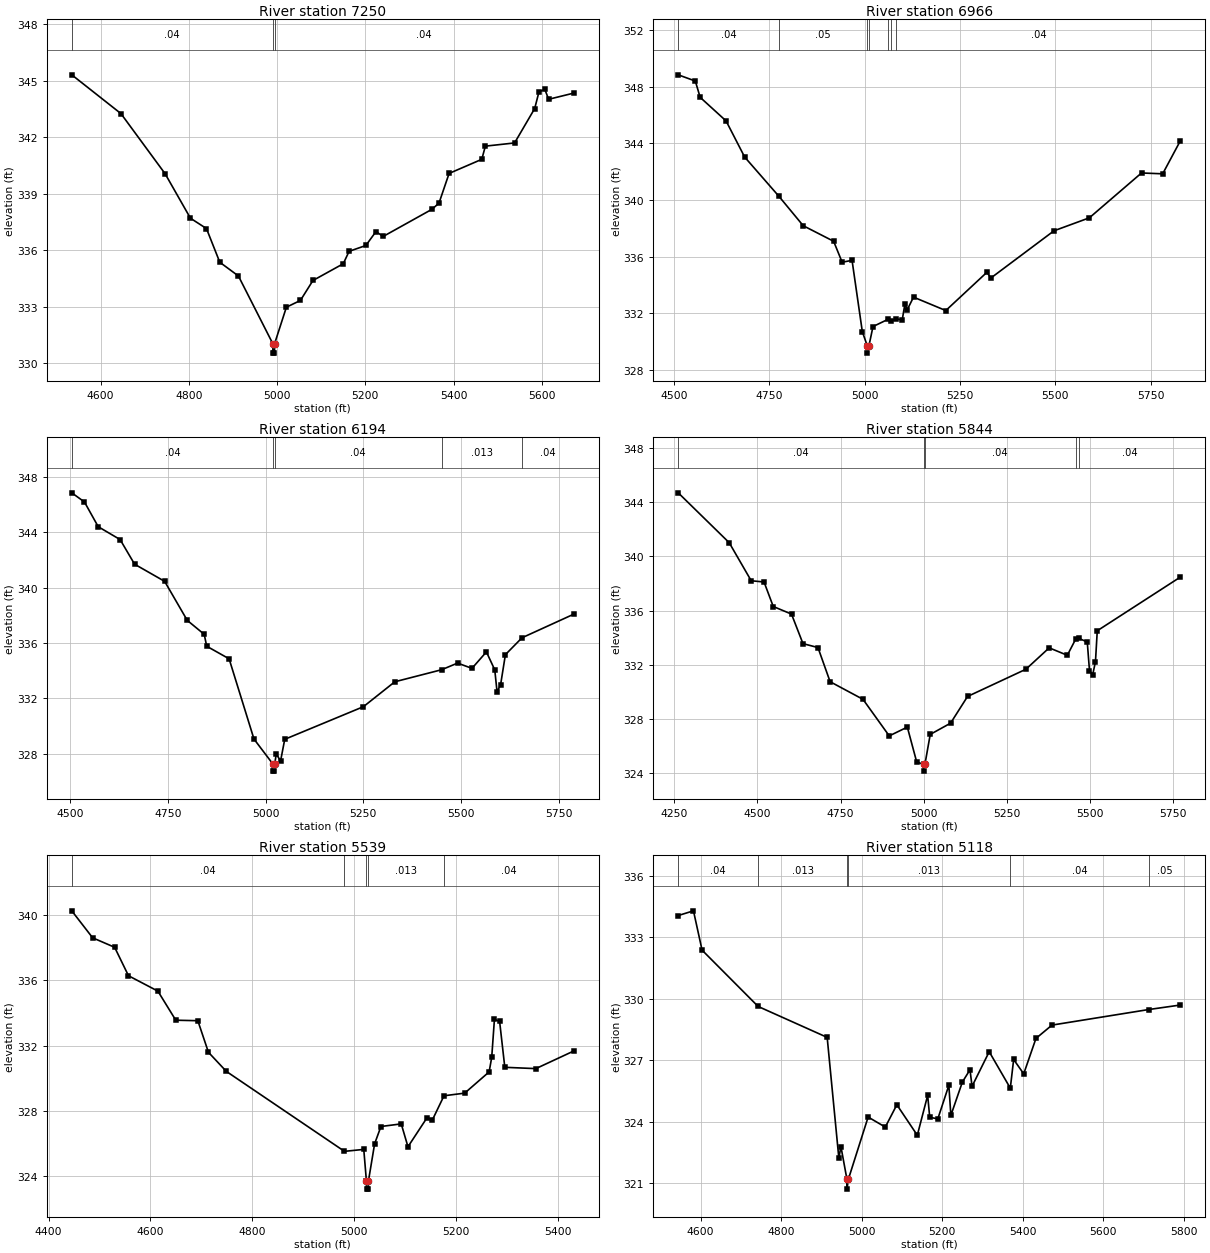
Type RM Length L Ch R = 1,7250,284,284,284
BEGIN DESCRIPTION:
TRIB 8_1 TO YORKTOWN CREEK 9.0
END DESCRIPTION:
XS GIS Cut Line= 3
      2448448.38     13565505.17      2448030.54     13565777.41
      2447760.89     13566356.73
#Sta/Elev= 30
  4534.7  345.32  4646.1  343.26  4746.3  340.06  4803.6  337.70  4839.9  337.15
  4870.1  335.36  4912.3  334.63  4990.3  331.03  4990.5  330.53  4994.0  330.53
  4994.3  331.03  5021.0  332.97  5052.8  333.33  5081.2  334.39  5149.9  335.28
  5163.1  335.94  5201.1  336.25  5224.0  336.99  5240.3  336.73  5350.6  338.17
  5366.8  338.50  5389.7  340.08  5463.8  340.83  5471.9  341.53  5538.1  341.70
  5583.7  343.53  5593.3  344.41  5606.6  344.55  5615.3  344.02  5672.4  344.35
#Mann=3,-1,0
  4534.7    0.04       0  4990.3    0.04       0  4994.3    0.04       0
Bank Sta=4990.3,4994.3
Exp/Cntr=0.3,0.1

Type RM Length L Ch R = 1,6966,772,772,772
BEGIN DESCRIPTION:
Mapping XS aae9c209
END DESCRIPTION:
XS GIS Cut Line= 4
      2448323.41     13565262.96      2447932.77     13565497.35
      2447836.42     13565690.06      2447698.43     13566320.11
#Sta/Elev= 30
  4511.7  348.85  4556.5  348.41  4569.1  347.26  4637.1  345.59  4685.7  343.04
  4775.9  340.25  4839.3  338.18  4919.0  337.08  4941.3  335.60  4967.3  335.73
  4994.2  330.69  5007.4  329.67  5007.6  329.17  5011.4  329.67  5022.2  331.05
  5062.4  331.57  5068.1  331.44  5083.4  331.59  5098.8  331.52  5106.0  332.67
  5111.6  332.22  5128.4  333.13  5213.0  332.18  5320.9  334.89  5331.1  334.48
  5496.6  337.82  5589.4  338.74  5726.0  341.91  5781.5  341.85  5827.7  344.18
#Mann=7,-1,0
  4511.7    0.04       0  4775.9    0.05       0  5007.4    0.05       0
  5011.4    0.05       0  5062.4    0.04       0  5068.1    0.05       0
  5083.4    0.04       0
Bank Sta=5007.4,5011.4
Exp/Cntr=0.3,0.1

Type RM Length L Ch R = 1,6194,350,350,350
BEGIN DESCRIPTION:
Mapping XS 383c59e4
END DESCRIPTION:
XS GIS Cut Line= 4
      2447773.06     13564878.40      2447443.19     13565298.56
      2447293.88     13565697.87      2447127.23     13565975.62
#Sta/Elev= 30
  4504.2  346.86  4536.6  346.20  4571.9  344.41  4627.9  343.48  4664.9  341.70
  4741.8  340.46  4799.6  337.64  4843.0  336.63  4849.4  335.77  4906.7  334.86
  4970.3  329.06  5019.1  327.24  5019.3  326.74  5022.8  326.74  5023.1  327.24
  5027.4  327.97  5038.4  327.48  5049.0  329.04  5250.4  331.40  5330.6  333.20
  5450.3  334.07  5491.1  334.55  5528.0  334.17  5564.9  335.36  5586.3  334.06
  5592.2  332.46  5601.3  333.00  5613.5  335.16  5655.9  336.38  5788.6  338.09
#Mann=5,-1,0
  4504.2    0.04       0  5019.1    0.04       0  5023.1    0.04       0
  5450.3   0.013       0  5655.9    0.04       0
Bank Sta=5019.1,5023.1
Exp/Cntr=0.3,0.1

Type RM Length L Ch R = 1,5844,305,305,305
BEGIN DESCRIPTION:
Mapping XS c720be4a
END DESCRIPTION:
XS GIS Cut Line= 4
      2447450.12     13564562.47      2447151.73     13565133.56
      2447241.80     13565583.29      2447079.31     13565956.66
#Sta/Elev= 30
  4261.6  344.69  4414.9  341.01  4481.1  338.20  4519.7  338.11  4547.4  336.30
  4602.3  335.74  4636.8  333.56  4681.9  333.27  4718.4  330.75  4817.3  329.45
  4896.3  326.75  4950.7  327.40  4978.8  324.83  4999.6  324.65  4999.9  324.15
  5003.6  324.65  5019.6  326.86  5080.8  327.69  5131.8  329.66  5307.4  331.67
  5377.4  333.25  5431.9  332.70  5456.6  333.87  5467.4  333.94  5491.9  333.68
  5498.6  331.57  5508.2  331.26  5516.6  332.23  5522.0  334.51  5771.8  338.47
#Mann=5,-1,0
  4261.6    0.04       0  4999.6    0.04       0  5003.6    0.04       0
  5456.6   0.013       0  5467.4    0.04       0
Bank Sta=4999.6,5003.6
Exp/Cntr=0.3,0.1

Type RM Length L Ch R = 1,5539,421,421,421
BEGIN DESCRIPTION:
4909
END DESCRIPTION:
XS GIS Cut Line= 4
      2447336.06     13564628.63      2447090.88     13564936.67
      2446940.02     13565081.25      2446870.87     13565458.40
#Sta/Elev= 30
  4445.5  340.24  4486.5  338.59  4529.7  338.01  4556.9  336.27  4614.6  335.33
  4649.8  333.55  4693.1  333.52  4713.9  331.59  4749.1  330.42  4981.1  325.53
  5019.0  325.65  5024.2  323.72  5024.4  323.22  5027.9  323.22  5028.2  323.72
  5040.3  325.99  5052.7  327.05  5092.6  327.21  5105.8  325.81  5143.5  327.60
  5153.6  327.44  5176.6  328.93  5217.2  329.09  5265.2  330.39  5270.3  331.28
  5275.6  333.60  5285.8  333.48  5296.0  330.67  5357.0  330.59  5431.6  331.67
#Mann=5,-1,0
  4445.5    0.04       0  4981.1   0.013       0  5024.2    0.03       0
  5028.2   0.013       0  5176.6    0.04       0
Bank Sta=5024.2,5028.2
Exp/Cntr=0.3,0.1

Type RM Length L Ch R = 1,5118,152,152,152
BEGIN DESCRIPTION:
4905
END DESCRIPTION:
XS GIS Cut Line= 5
      2446970.70     13564317.13      2446807.54     13564474.01
      2446901.69     13564976.12      2446820.10     13565195.79
      2446594.18     13565352.68
#Sta/Elev= 30
  4544.5  334.07  4582.3  334.30  4603.7  332.38  4742.9  329.63  4914.3  328.12
  4943.3  322.22  4948.4  322.79  4963.2  321.21  4963.4  320.71  4967.2  321.21
  5016.0  324.23  5058.6  323.74  5087.3  324.83  5138.1  323.34  5163.8  325.29
  5168.9  324.22  5189.0  324.14  5216.4  325.78  5221.4  324.31  5250.0  325.94
  5268.9  326.54  5274.0  325.73  5316.6  327.42  5369.0  325.64  5377.3  327.04
  5402.3  326.34  5432.7  328.07  5472.5  328.72  5712.7  329.48  5791.1  329.70
#Mann=6,-1,0
  4544.5    0.04       0  4742.9   0.013       0  4963.2    0.03       0
  4967.2   0.013       0  5369.0    0.04       0  5712.7    0.05       0
Bank Sta=4963.2,4967.2
Exp/Cntr=0.3,0.1

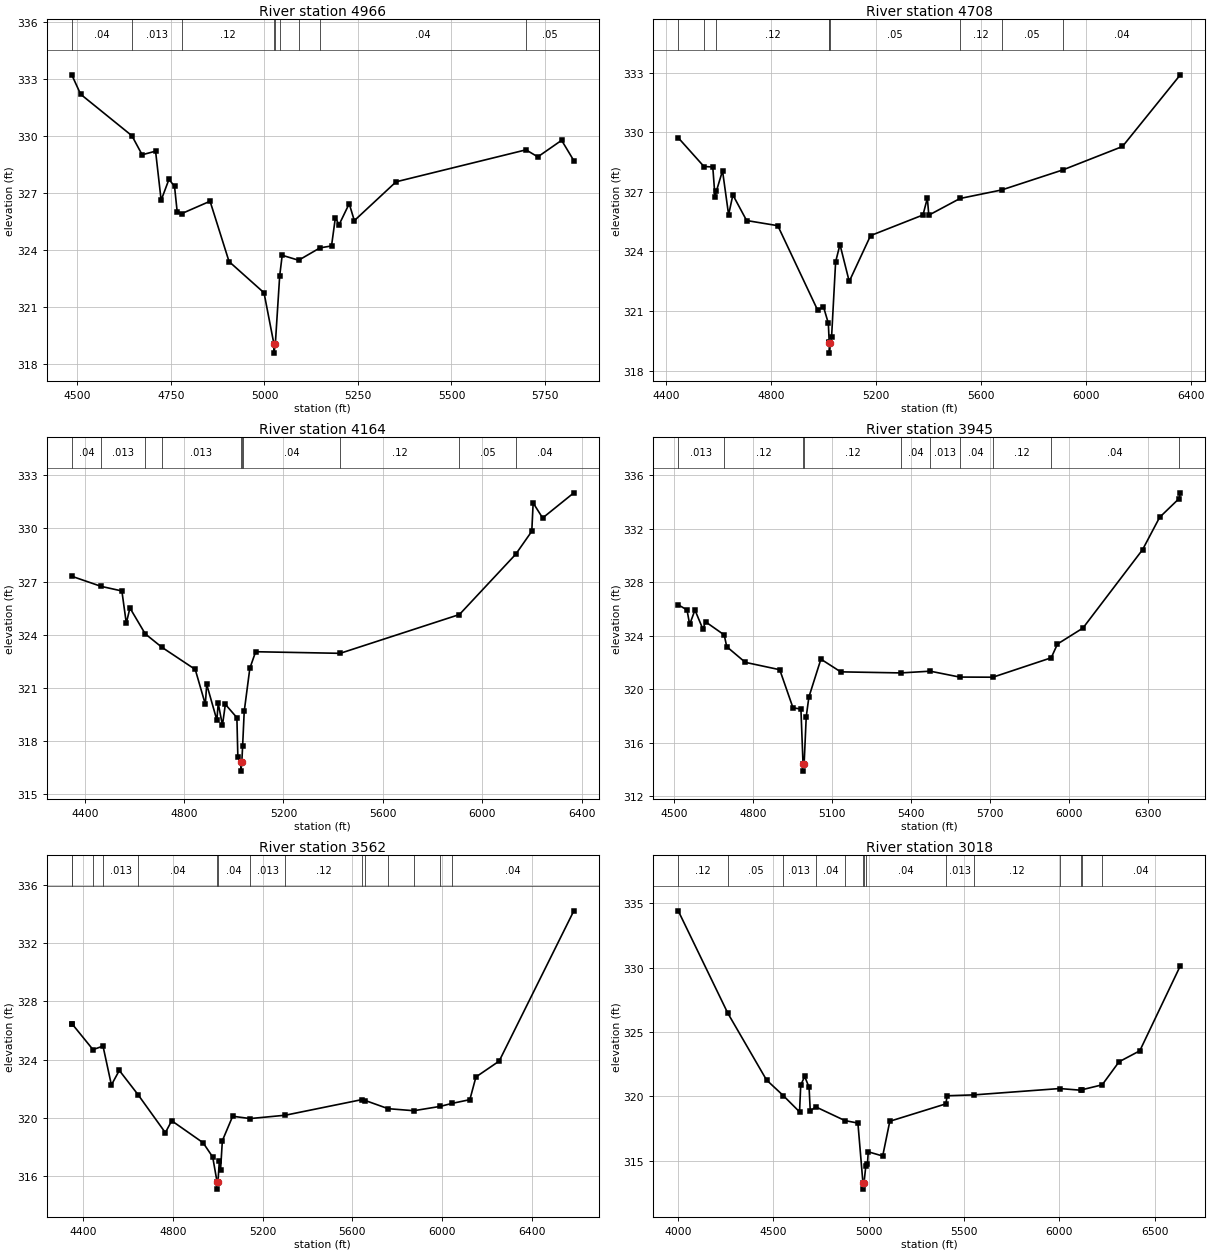
Type RM Length L Ch R = 1,4966,258,258,258
BEGIN DESCRIPTION:
4904
END DESCRIPTION:
XS GIS Cut Line= 4
      2446927.47     13564245.19      2446683.00     13564412.61
      2446801.27     13565089.09      2446550.19     13565346.45
#Sta/Elev= 30
  4484.7  333.20  4508.4  332.18  4645.5  330.00  4672.9  329.00  4708.8  329.19
  4723.7  326.61  4744.6  327.71  4759.5  327.34  4766.5  326.02  4778.7  325.91
  4854.5  326.56  4905.3  323.39  4998.8  321.75  5025.1  319.08  5025.3  318.58
  5029.1  319.08  5040.7  322.64  5047.4  323.72  5091.3  323.46  5148.5  324.11
  5179.3  324.21  5189.5  325.68  5199.6  325.33  5226.6  326.43  5240.3  325.54
  5351.9  327.58  5699.4  329.26  5730.9  328.89  5794.6  329.76  5827.3  328.69
#Mann=9,-1,0
  4484.7    0.04       0  4645.5   0.013       0  4778.7    0.12       0
  5025.1    0.05       0  5029.1    0.12       0  5040.7    0.05       0
  5091.3   0.013       0  5148.5    0.04       0  5699.4    0.05       0
Bank Sta=5025.1,5029.1
Exp/Cntr=0.3,0.1

Type RM Length L Ch R = 1,4708,544,544,544
BEGIN DESCRIPTION:
Mapping XS cfaf7f4d
END DESCRIPTION:
XS GIS Cut Line= 4
      2446795.45     13564081.77      2446554.28     13564189.11
      2446519.58     13564479.12      2445901.74     13565690.50
#Sta/Elev= 30
  4445.0  329.73  4543.2  328.28  4576.8  328.26  4585.3  326.76  4591.0  327.06
  4614.0  328.07  4637.2  325.85  4653.5  326.85  4705.9  325.56  4824.9  325.30
  4976.8  321.05  4999.3  321.21  5017.7  320.39  5021.0  319.46  5021.3  319.38
  5021.6  318.88  5025.3  319.38  5030.1  319.68  5045.6  323.48  5062.2  324.35
  5097.5  322.49  5178.9  324.80  5379.0  325.84  5395.6  326.69  5401.2  325.83
  5520.1  326.67  5679.2  327.10  5912.7  328.11  6140.2  329.29  6360.9  332.90
#Mann=9,-1,0
  4445.0    0.04       0  4543.2   0.013       0  4591.0    0.12       0
  5021.0    0.05       0  5021.3    0.05       0  5025.3    0.05       0
  5520.1    0.12       0  5679.2    0.05       0  5912.7    0.04       0
Bank Sta=5021.3,5025.3
Exp/Cntr=0.3,0.1

Type RM Length L Ch R = 1,4164,219,219,219
BEGIN DESCRIPTION:
Mapping XS d1df2f39
END DESCRIPTION:
XS GIS Cut Line= 3
      2446768.73     13563869.74      2446156.73     13564143.18
      2445614.25     13565380.04
#Sta/Elev= 30
  4347.8  327.30  4465.8  326.73  4549.5  326.47  4567.3  324.65  4581.9  325.51
  4643.4  324.05  4710.7  323.29  4844.8  322.04  4885.4  320.07  4890.9  321.20
  4931.8  319.18  4937.3  320.13  4954.3  318.89  4966.0  320.07  5012.4  319.32
  5016.3  317.12  5028.2  316.80  5028.5  316.30  5032.2  316.80  5035.5  317.72
  5041.9  319.67  5064.5  322.10  5087.9  323.04  5428.1  322.95  5908.1  325.14
  6134.6  328.54  6199.4  329.84  6204.9  331.44  6243.1  330.59  6368.7  332.01
#Mann=10,-1,0
  4347.8    0.04       0  4465.8   0.013       0  4643.4    0.12       0
  4710.7   0.013       0  5028.2    0.03       0  5032.2   0.013       0
  5035.5    0.04       0  5428.1    0.12       0  5908.1    0.05       0
  6134.6    0.04       0
Bank Sta=5028.2,5032.2
Exp/Cntr=0.3,0.1

Type RM Length L Ch R = 1,3945,383,383,383
BEGIN DESCRIPTION:
4903
END DESCRIPTION:
XS GIS Cut Line= 3
      2446638.11     13563890.29      2445887.08     13563973.49
      2445319.26     13564974.77
#Sta/Elev= 30
  4515.0  326.32  4548.3  325.94  4558.4  324.85  4578.5  325.93  4608.7  324.50
  4618.7  325.05  4689.6  324.07  4699.2  323.19  4769.7  322.02  4900.5  321.47
  4950.8  318.62  4980.9  318.53  4989.0  314.39  4989.3  313.89  4993.0  314.39
  5001.1  317.96  5011.1  319.42  5056.8  322.26  5131.9  321.31  5360.6  321.23
  5472.0  321.36  5583.5  320.92  5709.9  320.91  5931.4  322.36  5955.2  323.39
  6051.8  324.58  6278.3  330.44  6343.2  332.86  6417.0  334.26  6421.7  334.69
#Mann=10,-1,0
  4515.0   0.013       0  4689.6    0.12       0  4989.0    0.05       0
  4993.0    0.12       0  5360.6    0.04       0  5472.0   0.013       0
  5583.5    0.04       0  5709.9    0.12       0  5931.4    0.04       0
  6417.0    0.05       0
Bank Sta=4989,4993
Exp/Cntr=0.3,0.1

Type RM Length L Ch R = 1,3562,544,544,544
BEGIN DESCRIPTION:
4902
END DESCRIPTION:
XS GIS Cut Line= 4
      2446663.18     13563846.35      2446336.81     13563501.16
      2446054.37     13563614.14      2445275.10     13564845.88
#Sta/Elev= 30
  4350.2  326.48  4350.4  326.48  4444.7  324.69  4489.4  324.93  4526.8  322.26
  4562.0  323.26  4645.6  321.59  4767.1  318.98  4795.4  319.80  4935.1  318.29
  4978.0  317.31  4997.5  315.60  4997.8  315.10  5001.5  315.60  5007.8  317.05
  5013.1  316.44  5021.1  318.43  5067.0  320.11  5144.9  319.95  5301.4  320.18
  5645.1  321.26  5658.1  321.19  5759.6  320.63  5874.2  320.49  5992.5  320.79
  6043.4  320.99  6123.7  321.25  6150.8  322.81  6254.3  323.90  6587.0  334.23
#Mann=15,-1,0
  4350.2    0.04       0  4350.4   0.013       0  4444.7    0.05       0
  4489.4   0.013       0  4645.6    0.04       0  4997.5    0.04       0
  5001.5    0.04       0  5144.9   0.013       0  5301.4    0.12       0
  5645.1    0.04       0  5658.1    0.12       0  5759.6   0.013       0
  5874.2    0.04       0  5992.5    0.12       0  6043.4    0.04       0
Bank Sta=4997.5,5001.5
Exp/Cntr=0.3,0.1

Type RM Length L Ch R = 1,3018,343,343,343
BEGIN DESCRIPTION:
TRIB 8_1 TO YORKTOWN CREEK 3.0
END DESCRIPTION:
XS GIS Cut Line= 3
      2446725.00     13562475.00      2446125.00     13563275.00
      2445314.16     13564693.98
#Sta/Elev= 30
  4000.5  334.41  4261.0  326.45  4464.0  321.27  4551.2  320.07  4637.0  318.80
  4643.2  320.88  4664.0  321.55  4687.0  320.70  4693.2  318.86  4721.6  319.19
  4875.4  318.12  4943.2  317.93  4969.5  313.30  4969.9  312.80  4975.3  313.30
  4984.5  314.57  4993.2  314.72  4997.4  315.70  5073.2  315.37  5110.6  318.07
  5404.6  319.42  5411.5  320.05  5554.8  320.12  6001.5  320.61  6113.2  320.48
  6119.7  320.52  6224.9  320.90  6313.5  322.69  6422.2  323.54  6634.8  330.14
#Mann=14,-1,0
  4000.5    0.12       0  4261.0    0.05       0  4551.2   0.013       0
  4721.6    0.04       0  4875.4    0.05       0  4969.5    0.04       0
  4975.3    0.05       0  4984.5    0.04       0  5404.6   0.013       0
  5554.8    0.12       0  6001.5   0.013       0  6113.2    0.04       0
  6119.7   0.013       0  6224.9    0.04       0
Bank Sta=4969.5,4975.3
Exp/Cntr=0.3,0.1

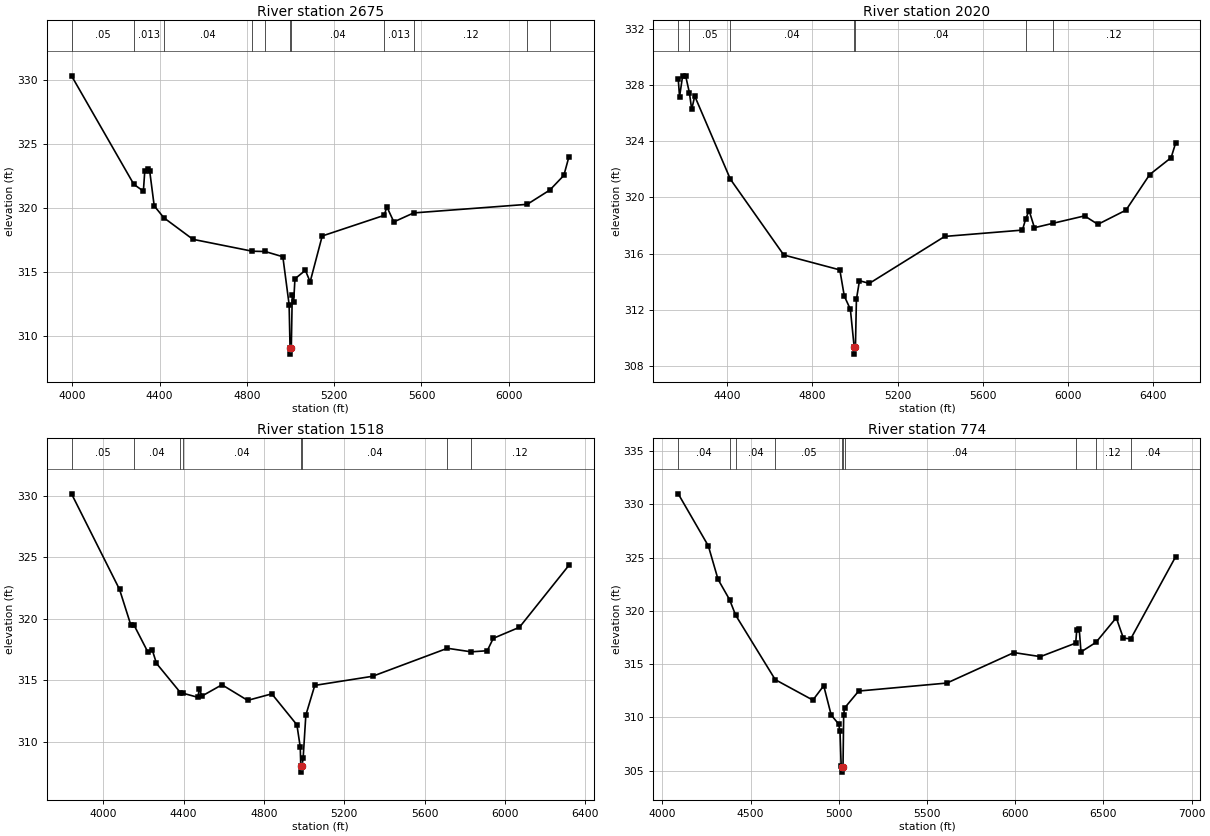
Type RM Length L Ch R = 1,2675,655,655,655
BEGIN DESCRIPTION:
Mapping XS ae1a9542
END DESCRIPTION:
XS GIS Cut Line= 3
      2446469.21     13562446.16      2445822.53     13563240.40
      2445384.15     13564416.65
#Sta/Elev= 30
  3996.2  330.32  4281.8  321.85  4325.5  321.32  4332.0  322.92  4346.4  323.07
  4354.3  322.91  4375.1  320.17  4419.5  319.24  4552.5  317.56  4825.1  316.63
  4883.3  316.61  4964.7  316.20  4993.4  312.47  4997.7  309.10  4998.1  308.60
  5003.5  309.10  5007.8  313.25  5014.2  312.68  5020.2  314.48  5068.0  315.14
  5089.8  314.24  5145.1  317.82  5429.0  319.43  5441.5  320.09  5473.5  318.92
  5564.3  319.62  6084.6  320.29  6188.7  321.41  6252.6  322.55  6275.7  323.99
#Mann=11,-1,0
  3996.2    0.05       0  4281.8   0.013       0  4419.5    0.04       0
  4825.1    0.05       0  4883.3    0.04       0  4997.7    0.04       0
  5003.5    0.04       0  5429.0   0.013       0  5564.3    0.12       0
  6084.6   0.013       0  6188.7    0.04       0
Bank Sta=4997.7,5003.5
Exp/Cntr=0.3,0.1

Type RM Length L Ch R = 1,2020,502,502,502
BEGIN DESCRIPTION:
Mapping XS 1b0e92be
END DESCRIPTION:
XS GIS Cut Line= 3
      2446152.41     13562233.43      2445583.81     13562884.50
      2445175.83     13564295.08
#Sta/Elev= 30
  4171.3  328.42  4177.5  327.15  4191.7  328.61  4206.0  328.64  4223.7  327.44
  4234.5  326.25  4248.7  327.20  4415.9  321.29  4666.4  315.90  4929.3  314.84
  4950.2  312.98  4978.7  312.04  4996.6  309.35  4997.1  308.85  5002.5  309.35
  5007.1  312.75  5021.4  314.07  5067.5  313.88  5421.4  317.22  5785.7  317.67
  5801.2  318.47  5817.0  319.06  5842.1  317.84  5927.9  318.15  6077.2  318.68
  6139.7  318.08  6271.5  319.09  6382.7  321.62  6483.2  322.82  6504.1  323.85
#Mann=7,-1,0
  4171.3   0.013       0  4223.7    0.05       0  4415.9    0.04       0
  4996.6    0.04       0  5002.5    0.04       0  5801.2   0.013       0
  5927.9    0.12       0
Bank Sta=4996.6,5002.5
Exp/Cntr=0.3,0.1

Type RM Length L Ch R = 1,1518,744,744,744
BEGIN DESCRIPTION:
Mapping XS f3c6b1a4
END DESCRIPTION:
XS GIS Cut Line= 4
      2446039.55     13562111.92      2445293.01     13562780.34
      2445162.80     13563036.41      2445084.72     13564220.61
#Sta/Elev= 30
  3841.7  330.16  4080.7  322.38  4137.5  319.45  4152.0  319.50  4222.8  317.25
  4243.7  317.45  4264.6  316.36  4383.4  313.99  4399.0  313.92  4470.2  313.60
  4477.7  314.25  4491.9  313.71  4590.6  314.62  4718.4  313.35  4838.8  313.88
  4963.7  311.36  4980.4  309.55  4983.0  308.01  4983.5  307.51  4989.0  308.01
  4994.8  308.65  5008.2  312.15  5052.7  314.57  5340.1  315.31  5713.0  317.59
  5831.4  317.30  5911.3  317.39  5941.4  318.40  6071.7  319.30  6317.8  324.34
#Mann=8,-1,0
  3841.7    0.05       0  4152.0    0.04       0  4383.4    0.05       0
  4399.0    0.04       0  4983.0    0.04       0  4989.0    0.04       0
  5713.0   0.013       0  5831.4    0.12       0
Bank Sta=4983,4989
Exp/Cntr=0.3,0.1

Type RM Length L Ch R = 1,774,0,0,0
BEGIN DESCRIPTION:
Mapping XS ef0b6ec2
END DESCRIPTION:
XS GIS Cut Line= 4
      2446004.84     13562012.10      2445240.93     13562298.56
      2444932.77     13562632.77      2444928.43     13564181.11
#Sta/Elev= 30
  4090.2  330.98  4260.9  326.09  4315.9  322.95  4381.2  321.05  4415.6  319.59
  4640.0  313.54  4853.4  311.62  4914.8  312.97  4957.1  310.22  4999.6  309.37
  5007.0  308.68  5013.8  305.39  5018.1  305.36  5018.6  304.86  5024.1  305.36
  5027.9  310.25  5032.6  310.87  5113.0  312.47  5612.9  313.22  5992.9  316.08
  6142.9  315.70  6342.9  316.97  6348.7  318.17  6362.9  318.30  6372.9  316.14
  6457.8  317.04  6572.9  319.35  6612.9  317.44  6654.9  317.37  6909.0  325.07
#Mann=10,-1,0
  4090.2    0.04       0  4381.2    0.05       0  4415.6    0.04       0
  4640.0    0.05       0  5018.1    0.05       0  5024.1    0.05       0
  5032.6    0.04       0  6342.9   0.013       0  6457.8    0.12       0
  6654.9    0.04       0
Bank Sta=5018.1,5024.1
Exp/Cntr=0.3,0.1

Chan Stop Cuts=-1