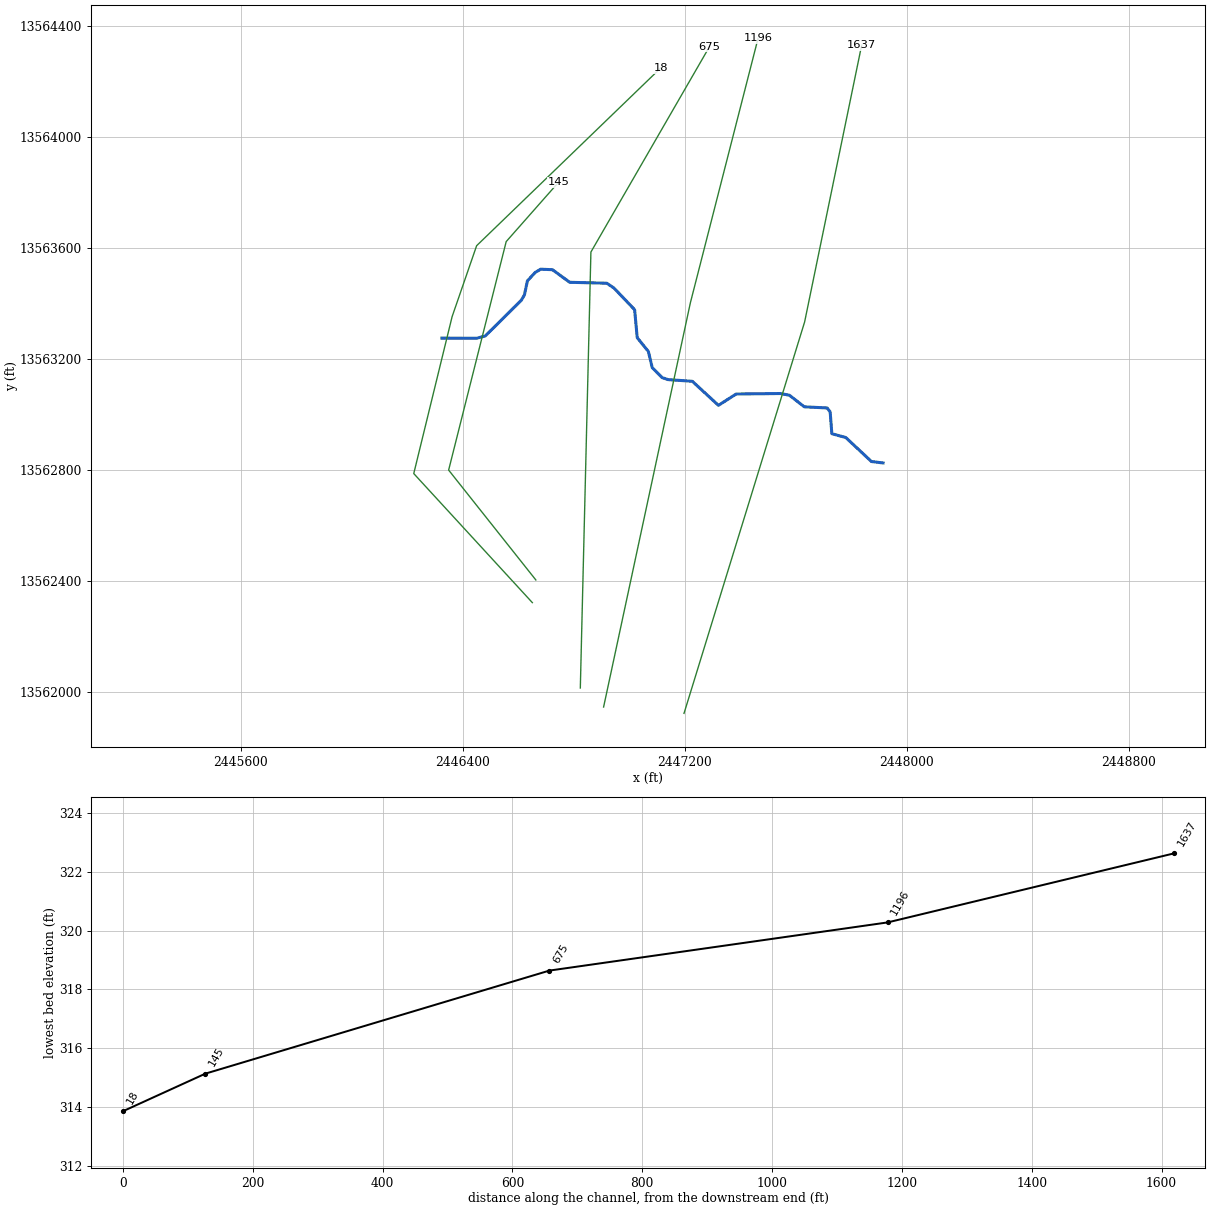
--- TRIB 8_1_1 TO YORKTOWN CREEK.prj (project) ---

Proj Title=TRIB 8_1_1 TO YORKTOWN CREEK Base Level Engineering
Current Plan=p01
Default Exp/Contr=0.3,0.1
English Units
Geom File=g01
Flow File=f01
Plan File=p01
BEGIN DESCRIPTION:
TRIB 8_1_1 TO YORKTOWN CREEK
END DESCRIPTION:

--- TRIB 8_1_1 TO YORKTOWN CREEK.p01 (plan) ---

Plan Title=Multiple Run
Short Identifier=Multiple
Geom File=g01
Flow File=f01
Subcritical Flow
K Sum by GR= 0
Std Step Tol= 0.01
Critical Tol= 0.01
Num of Std Step Trials= 20
Max Error Tol= 0.3
Flow Tol Ratio= 0.001
Split Flow NTrial= 30
Split Flow Tol= 0.02
Split Flow Ratio= 0.02
Log Output Level= 0
Friction Slope Method= 1
Unsteady Friction Slope Method= 2
Unsteady Bridges Friction Slope Method= 1
Parabolic Critical Depth
Global Vel Dist=  1 , 1 , 1
Global Log Level= 0
CheckData=True
Encroach Param= -1, 0, 0, 0
BEGIN DESCRIPTION:
Multiple Run
END DESCRIPTION:

--- TRIB 8_1_1 TO YORKTOWN CREEK.f01 (steady flow) ---

Flow Title=Multiple
Number of Profiles=7
Profile Names=10-year,25-year,50-year,1pct_min,100-year,1pct_plu,500-year
River Rch & RM= TRIB 8_1_1 TO YO,Reach-1,1637
     633    1027    1386     906    1807    3606    3047
River Rch & RM= TRIB 8_1_1 TO YO,Reach-1,18
    1164    1942    2668    1771    3534    7051    6149
Boundary for River Rch & Prof#=TRIB 8_1_1 TO YO,Reach-1,1
Up Type=0
Dn Type=3
Dn Slope=0.005
Boundary for River Rch & Prof#=TRIB 8_1_1 TO YO,Reach-1,2
Up Type=0
Dn Type=3
Dn Slope=0.005
Boundary for River Rch & Prof#=TRIB 8_1_1 TO YO,Reach-1,3
Up Type=0
Dn Type=3
Dn Slope=0.005
Boundary for River Rch & Prof#=TRIB 8_1_1 TO YO,Reach-1,4
Up Type=0
Dn Type=3
Dn Slope=0.005
Boundary for River Rch & Prof#=TRIB 8_1_1 TO YO,Reach-1,5
Up Type=0
Dn Type=3
Dn Slope=0.005
Boundary for River Rch & Prof#=TRIB 8_1_1 TO YO,Reach-1,6
Up Type=0
Dn Type=3
Dn Slope=0.005
Boundary for River Rch & Prof#=TRIB 8_1_1 TO YO,Reach-1,7
Up Type=0
Dn Type=3
Dn Slope=0.005

--- TRIB 8_1_1 TO YORKTOWN CREEK.g01 (geometry) ---

Geom Title=Existing Conditions

River Reach=TRIB 8_1_1 TO YO,Reach-1
Reach XY= 30
      2447914.97     13562825.00      2447872.98     13562830.29
      2447780.70     13562916.70      2447730.29     13562930.55
      2447724.25     13563009.23      2447713.40     13563023.34
      2447631.07     13563027.40      2447577.34     13563069.26
      2447545.15     13563075.36      2447385.43     13563073.61
      2447321.59     13563032.81      2447227.42     13563119.44
      2447140.09     13563125.47      2447118.54     13563132.74
      2447083.00     13563168.62      2447068.85     13563227.15
      2447028.83     13563276.58      2447019.48     13563377.44
      2446945.21     13563455.41      2446919.15     13563472.94
      2446785.50     13563476.25      2446723.22     13563521.67
      2446680.85     13563523.46      2446661.43     13563512.02
      2446633.04     13563481.43      2446622.45     13563431.09
      2446611.36     13563411.80      2446481.20     13563282.79
      2446450.16     13563274.62      2446325.00     13563275.00

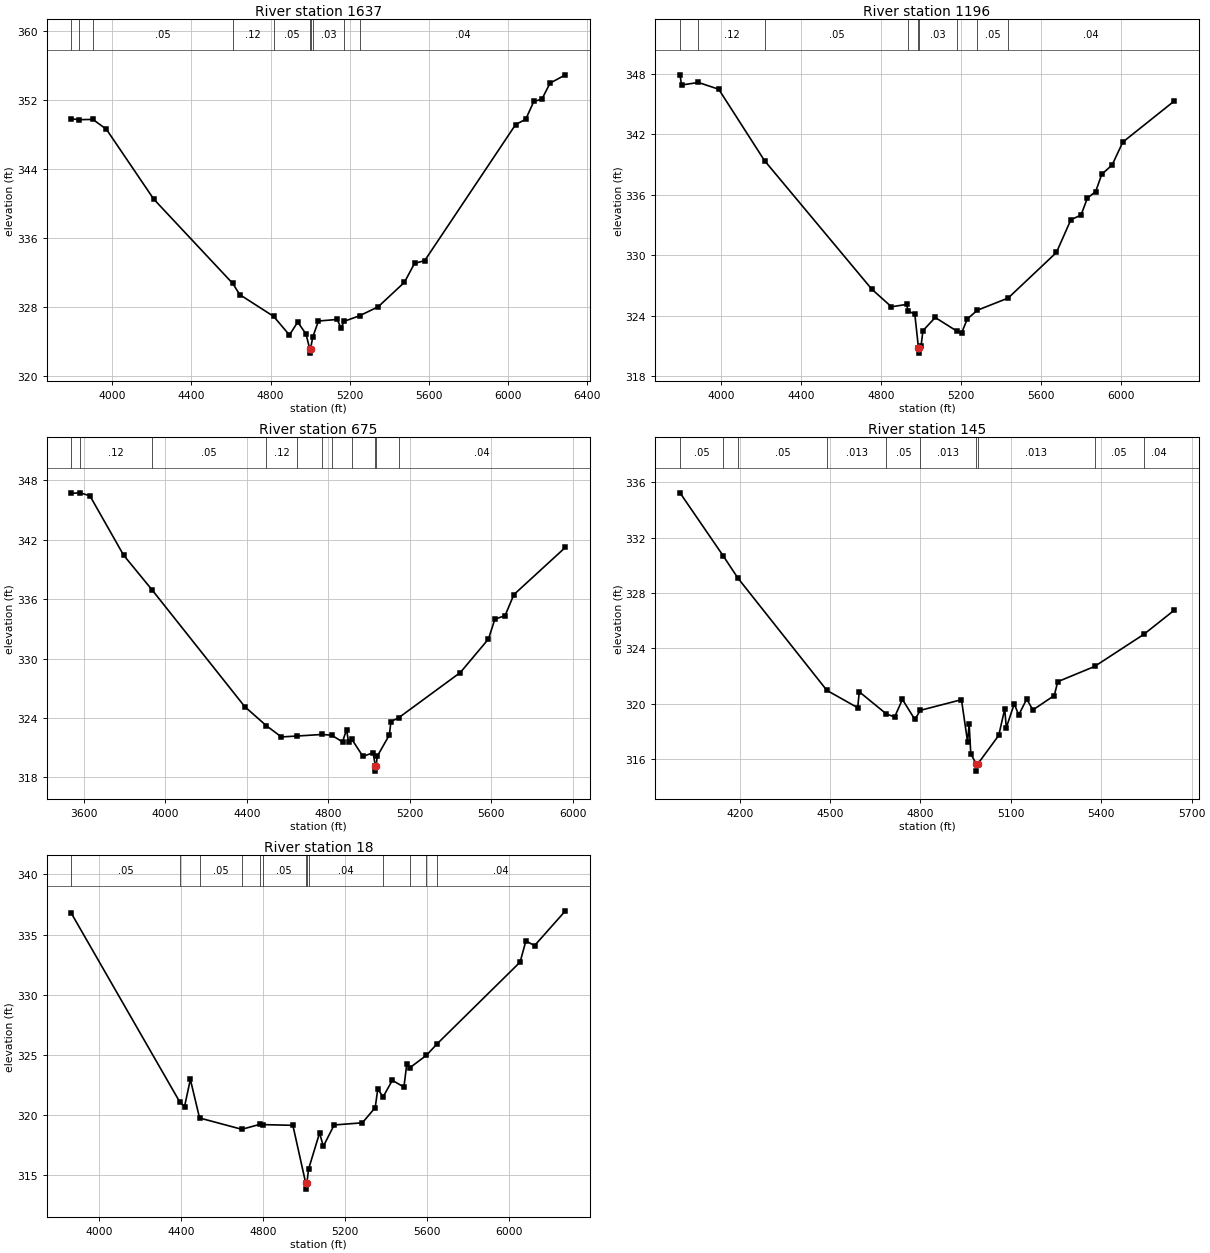
Type RM Length L Ch R = 1,1637,441,441,441
BEGIN DESCRIPTION:
LGII4617
END DESCRIPTION:
XS GIS Cut Line= 3
      2447197.50     13561922.53      2447632.25     13563333.54
      2447837.91     13564331.40
#Sta/Elev= 30
  3794.0  349.85  3832.2  349.75  3902.6  349.78  3970.8  348.64  4210.0  340.52
  4609.1  330.72  4644.2  329.43  4816.0  326.89  4895.3  324.73  4937.2  326.24
  4979.0  324.85  4997.9  323.13  4998.2  322.63  5001.9  323.13  5013.3  324.50
  5041.8  326.36  5136.0  326.54  5156.3  325.56  5171.2  326.32  5250.4  326.98
  5343.4  328.01  5476.2  330.86  5527.2  333.06  5578.3  333.37  6037.7  349.18
  6088.8  349.80  6129.6  351.87  6170.5  352.13  6211.3  353.99  6289.3  354.96
#Mann=10,-1,0
  3794.0    0.04       0  3832.2    0.12       0  3902.6    0.05       0
  4609.1    0.12       0  4816.0    0.05       0  4997.9    0.05       0
  5001.9    0.05       0  5013.3    0.03       0  5171.2   0.013       0
  5250.4    0.04       0
Bank Sta=4997.9,5001.9
Exp/Cntr=0.3,0.1

Type RM Length L Ch R = 1,1196,521,521,521
BEGIN DESCRIPTION:
LGII4616
END DESCRIPTION:
XS GIS Cut Line= 3
      2446907.66     13561945.38      2447220.38     13563402.19
      2447464.44     13564355.55
#Sta/Elev= 30
  3793.7  347.92  3801.6  346.91  3885.6  347.16  3987.6  346.49  4216.9  339.40
  4753.7  326.64  4852.5  324.88  4928.6  325.12  4936.2  324.45  4969.5  324.16
  4988.0  320.78  4988.2  320.28  4992.0  320.78  5000.7  320.97  5010.4  322.51
  5071.8  323.82  5181.4  322.45  5204.8  322.32  5232.3  323.67  5282.8  324.54
  5437.0  325.75  5678.9  330.28  5751.1  333.53  5802.0  333.99  5833.7  335.68
  5875.0  336.31  5905.9  338.05  5957.6  338.96  6011.2  341.24  6267.8  345.30
#Mann=9,-1,0
  3793.7    0.04       0  3885.6    0.12       0  4216.9    0.05       0
  4936.2    0.03       0  4988.0    0.03       0  4992.0    0.03       0
  5181.4   0.013       0  5282.8    0.05       0  5437.0    0.04       0
Bank Sta=4988,4992
Exp/Cntr=0.3,0.1

Type RM Length L Ch R = 1,675,530,530,530
BEGIN DESCRIPTION:
LGII4615
END DESCRIPTION:
XS GIS Cut Line= 3
      2446823.76     13562014.07      2446861.90     13563585.24
      2447289.01     13564325.06
#Sta/Elev= 30
  3538.5  346.67  3581.7  346.72  3629.5  346.42  3795.0  340.43  3934.6  336.93
  4389.7  325.15  4494.9  323.24  4569.7  322.09  4645.7  322.18  4770.1  322.34
  4817.1  322.26  4869.8  321.59  4889.8  322.84  4899.8  321.53  4915.7  321.85
  4969.9  320.13  5019.9  320.49  5031.4  319.14  5031.6  318.64  5035.4  319.14
  5039.9  320.12  5099.9  322.29  5107.5  323.64  5145.3  324.02  5448.4  328.59
  5586.4  331.97  5617.9  333.97  5668.1  334.33  5711.2  336.45  5964.4  341.22
#Mann=11,-1,0
  3538.5    0.04       0  3581.7    0.12       0  3934.6    0.05       0
  4494.9    0.12       0  4645.7    0.05       0  4770.1    0.12       0
  4817.1   0.013       0  4915.7    0.05       0  5031.4    0.05       0
  5035.4    0.05       0  5145.3    0.04       0
Bank Sta=5031.4,5035.4
Exp/Cntr=0.3,0.1

Type RM Length L Ch R = 1,145,127,127,127
BEGIN DESCRIPTION:
4910
END DESCRIPTION:
XS GIS Cut Line= 4
      2446663.44     13562403.40      2446349.14     13562799.43
      2446556.57     13563622.89      2446745.14     13563836.61
#Sta/Elev= 30
  4001.8  335.23  4144.5  330.70  4194.4  329.06  4489.4  320.96  4591.6  319.71
  4596.8  320.86  4686.7  319.26  4714.2  319.04  4740.0  320.31  4781.3  318.86
  4799.5  319.52  4936.0  320.29  4956.3  317.25  4961.5  318.53  4966.9  316.39
  4985.5  315.63  4985.8  315.13  4989.5  315.63  5059.7  317.71  5079.6  319.62
  5084.8  318.27  5111.3  319.99  5125.9  319.18  5152.5  320.33  5173.1  319.55
  5244.0  320.59  5255.6  321.59  5377.8  322.69  5541.3  325.01  5641.6  326.74
#Mann=10,-1,0
  4001.8    0.05       0  4144.5    0.12       0  4194.4    0.05       0
  4489.4   0.013       0  4686.7    0.05       0  4799.5   0.013       0
  4985.5    0.03       0  4989.5   0.013       0  5377.8    0.05       0
  5541.3    0.04       0
Bank Sta=4985.5,4989.5
Exp/Cntr=0.3,0.1

Type RM Length L Ch R = 1,18,0,0,0
BEGIN DESCRIPTION:
LGII4614
END DESCRIPTION:
XS GIS Cut Line= 5
      2446650.86     13562321.69      2446223.42     13562786.85
      2446361.71     13563352.60      2446450.03     13563608.12
      2447113.61     13564248.83
#Sta/Elev= 30
  3865.8  336.76  4394.6  321.07  4417.1  320.71  4445.5  322.96  4490.3  319.76
  4696.2  318.82  4786.0  319.24  4798.4  319.21  4944.9  319.15  5007.4  314.35
  5007.9  313.85  5013.2  314.35  5021.3  315.51  5075.0  318.52  5093.1  317.40
  5146.0  319.18  5283.5  319.36  5345.9  320.62  5358.6  322.17  5384.5  321.51
  5429.3  322.89  5485.9  322.33  5500.1  324.28  5514.6  323.93  5595.6  324.97
  5647.6  325.92  6051.9  332.71  6080.0  334.47  6122.3  334.08  6272.7  336.97
#Mann=13,-1,0
  3865.8    0.05       0  4394.6   0.013       0  4490.3    0.05       0
  4696.2    0.04       0  4786.0   0.013       0  4798.4    0.05       0
  5007.4    0.05       0  5013.2    0.05       0  5021.3    0.04       0
  5384.5   0.013       0  5514.6    0.05       0  5595.6   0.013       0
  5647.6    0.04       0
Bank Sta=5007.4,5013.2
Exp/Cntr=0.3,0.1

Chan Stop Cuts=-1