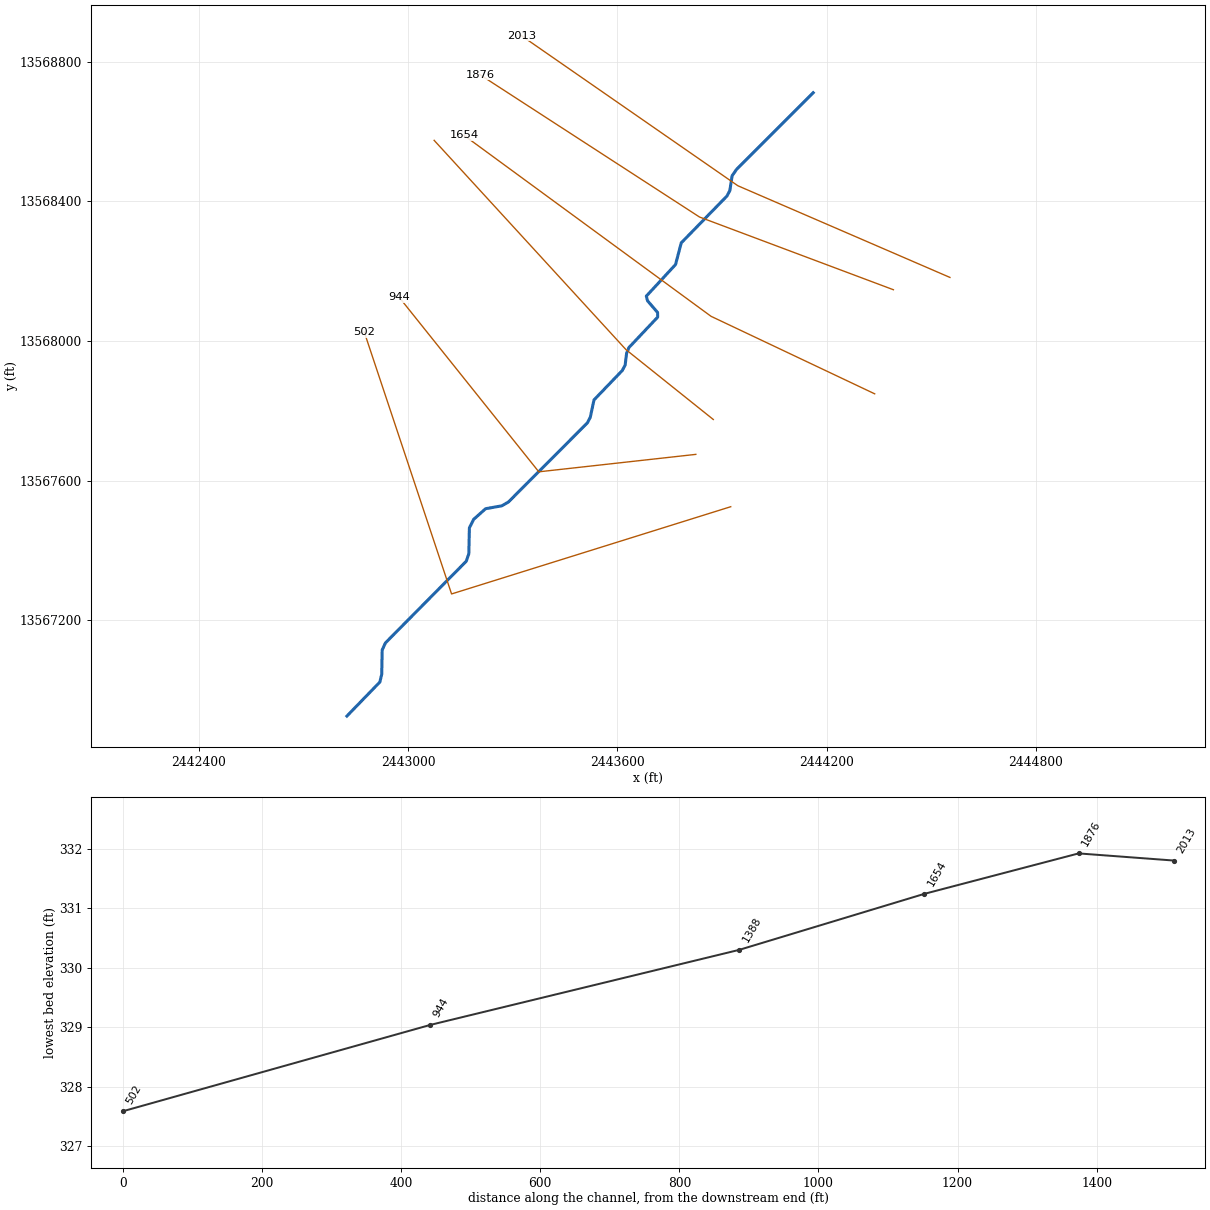
--- TRIB 8_2 TO YORKTOWN CREEK.prj (project) ---

Proj Title=TRIB 8_2 TO YORKTOWN CREEK Base Level Engineering
Current Plan=p01
Default Exp/Contr=0.3,0.1
English Units
Geom File=g01
Flow File=f01
Plan File=p01
BEGIN DESCRIPTION:
TRIB 8_2 TO YORKTOWN CREEK
END DESCRIPTION:

--- TRIB 8_2 TO YORKTOWN CREEK.p01 (plan) ---

Plan Title=Multiple Run
Short Identifier=Multiple
Geom File=g01
Flow File=f01
Subcritical Flow
K Sum by GR= 0
Std Step Tol= 0.01
Critical Tol= 0.01
Num of Std Step Trials= 20
Max Error Tol= 0.3
Flow Tol Ratio= 0.001
Split Flow NTrial= 30
Split Flow Tol= 0.02
Split Flow Ratio= 0.02
Log Output Level= 0
Friction Slope Method= 1
Unsteady Friction Slope Method= 2
Unsteady Bridges Friction Slope Method= 1
Parabolic Critical Depth
Global Vel Dist=  1 , 1 , 1
Global Log Level= 0
CheckData=True
Encroach Param= -1, 0, 0, 0
BEGIN DESCRIPTION:
Multiple Run
END DESCRIPTION:

--- TRIB 8_2 TO YORKTOWN CREEK.f01 (steady flow) ---

Flow Title=Multiple
Number of Profiles=7
Profile Names=10-year,25-year,50-year,1pct_min,100-year,1pct_plu,500-year
River Rch & RM= TRIB 8_2 TO YORK,Reach-1,2013
     450     711     940     603    1204    2402    1952
Boundary for River Rch & Prof#=TRIB 8_2 TO YORK,Reach-1,1
Up Type=0
Dn Type=3
Dn Slope=0.005
Boundary for River Rch & Prof#=TRIB 8_2 TO YORK,Reach-1,2
Up Type=0
Dn Type=3
Dn Slope=0.005
Boundary for River Rch & Prof#=TRIB 8_2 TO YORK,Reach-1,3
Up Type=0
Dn Type=3
Dn Slope=0.005
Boundary for River Rch & Prof#=TRIB 8_2 TO YORK,Reach-1,4
Up Type=0
Dn Type=3
Dn Slope=0.005
Boundary for River Rch & Prof#=TRIB 8_2 TO YORK,Reach-1,5
Up Type=0
Dn Type=3
Dn Slope=0.005
Boundary for River Rch & Prof#=TRIB 8_2 TO YORK,Reach-1,6
Up Type=0
Dn Type=3
Dn Slope=0.005
Boundary for River Rch & Prof#=TRIB 8_2 TO YORK,Reach-1,7
Up Type=0
Dn Type=3
Dn Slope=0.005

--- TRIB 8_2 TO YORKTOWN CREEK.g01 (geometry) ---

Geom Title=Existing Conditions

River Reach=TRIB 8_2 TO YORK,Reach-1
Reach XY= 30
      2444161.38     13568711.38      2443941.65     13568491.67
      2443928.98     13568473.35      2443922.46     13568431.05
      2443914.22     13568415.32      2443783.16     13568281.05
      2443766.80     13568218.95      2443683.02     13568128.33
      2443686.71     13568115.00      2443715.38     13568081.67
      2443715.68     13568068.34      2443633.20     13567981.05
      2443626.56     13567964.36      2443622.46     13567931.05
      2443614.20     13567915.33      2443533.18     13567831.04
      2443522.47     13567781.05      2443514.22     13567765.32
      2443288.20     13567538.64      2443268.91     13567527.55
      2443222.43     13567519.26      2443188.26     13567488.65
      2443176.10     13567464.67      2443174.47     13567390.22
      2443167.14     13567368.83      2442935.52     13567134.79
      2442926.16     13567114.52      2442924.87     13567045.05
      2442919.54     13567022.55      2442825.00     13566925.00

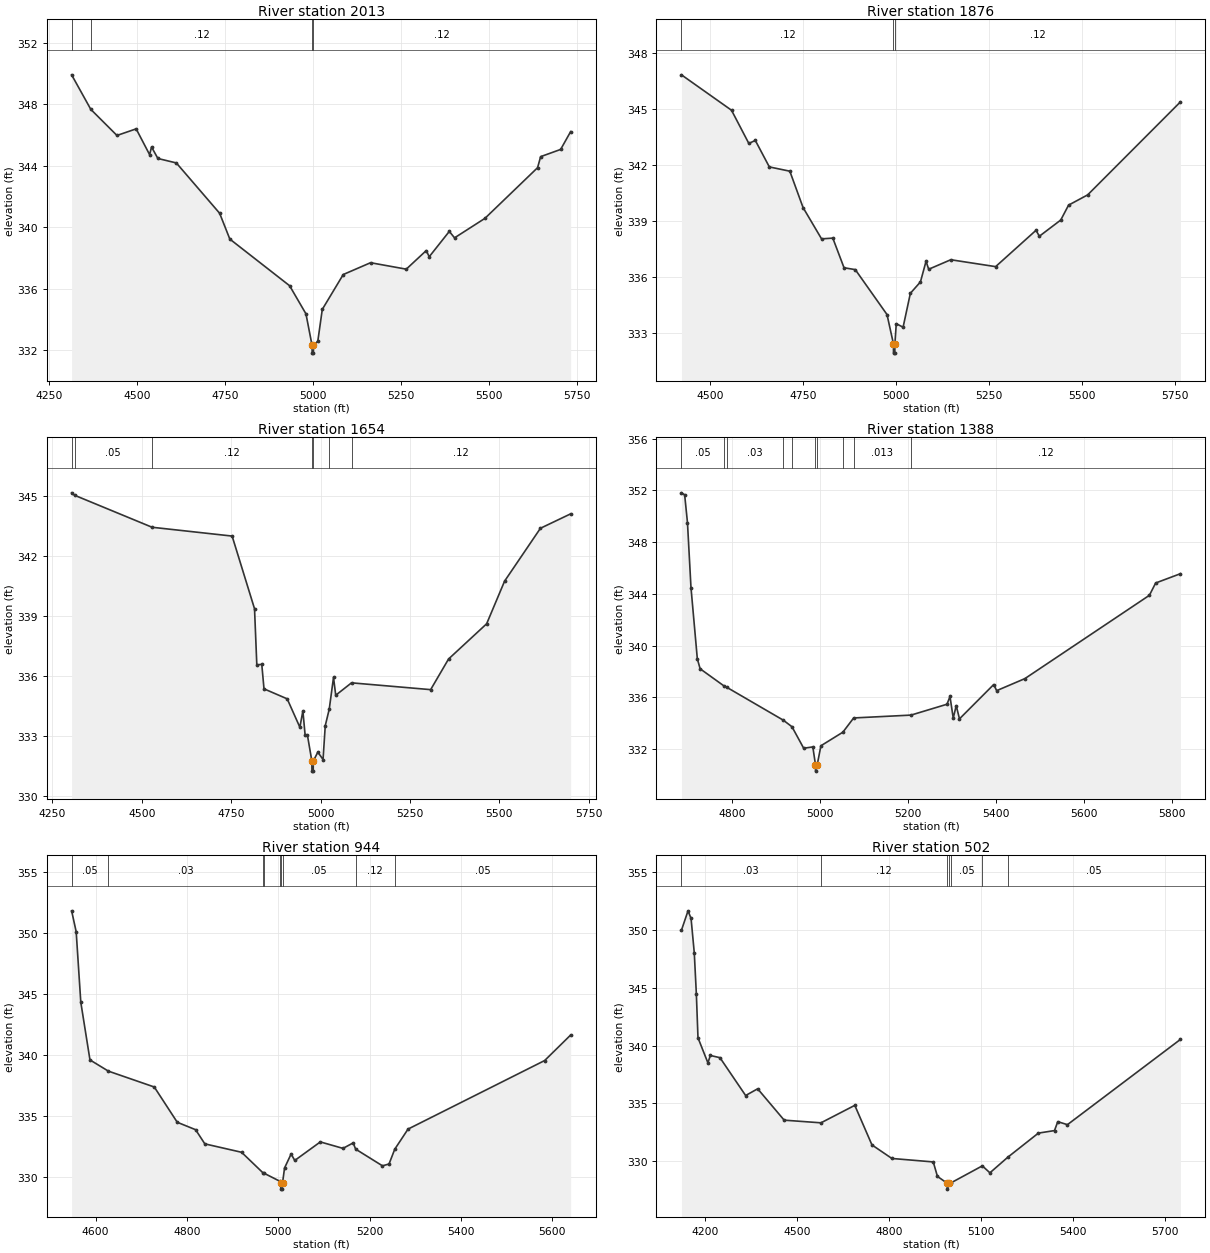
Type RM Length L Ch R = 1,2013,137,137,137
BEGIN DESCRIPTION:
TRIB 8_2 TO YORKTOWN CREEK 4.0
END DESCRIPTION:
XS GIS Cut Line= 3
      2444553.24     13568182.07      2443945.39     13568444.84
      2443324.96     13568875.03
#Sta/Elev= 30
  4313.9  349.93  4368.4  347.68  4442.7  345.98  4497.2  346.41  4535.4  344.73
  4540.9  345.23  4558.9  344.48  4611.3  344.19  4734.3  340.91  4763.2  339.23
  4933.0  336.19  4979.4  334.36  4996.8  332.30  4997.0  331.80  5000.5  331.80
  5000.8  332.30  5013.1  332.58  5025.8  334.65  5085.3  336.92  5162.9  337.69
  5264.3  337.27  5321.0  338.48  5329.5  338.08  5386.5  339.73  5401.4  339.31
  5487.7  340.58  5637.2  343.88  5645.9  344.60  5702.7  345.07  5731.1  346.23
#Mann=4,-1,0
  4313.9   0.013       0  4368.4    0.12       0  4996.8    0.05       0
  5000.8    0.12       0
Bank Sta=4996.8,5000.8
Exp/Cntr=0.3,0.1

Type RM Length L Ch R = 1,1876,222,222,222
BEGIN DESCRIPTION:
Mapping XS 40c2ef57
END DESCRIPTION:
XS GIS Cut Line= 3
      2444391.20     13568146.81      2443835.64     13568355.14
      2443206.26     13568763.16
#Sta/Elev= 30
  4421.8  346.85  4556.6  344.95  4603.2  343.17  4620.7  343.33  4658.4  341.91
  4713.6  341.68  4749.2  339.73  4799.0  338.05  4829.3  338.09  4859.5  336.50
  4889.8  336.40  4975.2  333.99  4992.5  332.42  4992.7  331.92  4996.2  331.92
  4996.5  332.42  5000.1  333.50  5018.5  333.31  5038.1  335.13  5065.2  335.74
  5080.3  336.85  5087.4  336.42  5146.9  336.93  5267.6  336.56  5376.4  338.51
  5385.3  338.19  5442.9  339.06  5464.0  339.86  5515.4  340.41  5765.2  345.40
#Mann=3,-1,0
  4421.8    0.12       0  4992.5    0.05       0  4996.5    0.12       0
Bank Sta=4992.5,4996.5
Exp/Cntr=0.3,0.1

Type RM Length L Ch R = 1,1654,266,266,266
BEGIN DESCRIPTION:
4911
END DESCRIPTION:
XS GIS Cut Line= 3
      2444337.55     13567848.53      2443868.52     13568070.70
      2443160.79     13568589.15
#Sta/Elev= 30
  4303.6  345.14  4311.7  345.02  4528.8  343.42  4752.7  342.98  4815.4  339.35
  4821.8  336.55  4835.7  336.57  4841.9  335.35  4906.8  334.85  4942.3  333.43
  4950.7  334.25  4956.9  333.05  4963.3  333.05  4975.8  331.74  4976.1  331.24
  4979.6  331.24  4979.8  331.74  4992.5  332.19  5007.1  331.82  5013.3  333.51
  5024.4  334.33  5036.4  335.92  5042.6  335.03  5086.8  335.65  5308.2  335.31
  5358.3  336.84  5464.9  338.60  5515.1  340.73  5615.4  343.37  5699.9  344.09
#Mann=7,-1,0
  4303.6   0.013       0  4311.7    0.05       0  4528.8    0.12       0
  4975.8    0.05       0  4979.8    0.12       0  5024.4    0.05       0
  5086.8    0.12       0
Bank Sta=4975.8,4979.8
Exp/Cntr=0.3,0.1

Type RM Length L Ch R = 1,1388,444,444,444
BEGIN DESCRIPTION:
TRIB 8_2 TO YORKTOWN CREEK 3.0
END DESCRIPTION:
XS GIS Cut Line= 3
      2443875.04     13567774.97      2443625.00     13567975.00
      2443075.03     13568574.97
#Sta/Elev= 30
  4684.4  351.81  4691.7  351.66  4698.1  349.51  4706.1  344.48  4720.5  338.98
  4726.9  338.21  4781.7  336.87  4786.9  336.79  4915.8  334.24  4935.6  333.73
  4962.2  332.07  4983.0  332.17  4989.0  330.80  4989.2  330.30  4993.0  330.80
  5001.4  332.26  5051.3  333.31  5075.8  334.41  5206.1  334.63  5287.9  335.47
  5294.7  336.07  5302.1  334.40  5308.9  335.36  5316.3  334.34  5394.0  336.99
  5400.8  336.52  5464.9  337.45  5747.9  343.89  5762.1  344.84  5818.5  345.56
#Mann=10,-1,0
  4684.4    0.05       0  4781.7   0.013       0  4786.9    0.03       0
  4915.8    0.05       0  4935.6   0.013       0  4989.0    0.03       0
  4993.0   0.013       0  5051.3    0.05       0  5075.8   0.013       0
  5206.1    0.12       0
Bank Sta=4989,4993
Exp/Cntr=0.3,0.1

Type RM Length L Ch R = 1,944,442,442,442
BEGIN DESCRIPTION:
TRIB 8_2 TO YORKTOWN CREEK 2.0
END DESCRIPTION:
XS GIS Cut Line= 3
      2443824.98     13567675.00      2443375.00     13567625.00
      2442974.98     13568125.03
#Sta/Elev= 30
  4547.3  351.85  4557.3  350.14  4567.4  344.36  4587.5  339.63  4627.9  338.71
  4728.4  337.41  4778.7  334.52  4818.9  333.91  4839.1  332.75  4919.6  332.06
  4967.2  330.35  4969.5  330.33  5003.2  329.69  5005.3  329.54  5005.5  329.04
  5009.0  329.04  5009.3  329.54  5013.7  330.77  5028.1  331.92  5036.1  331.39
  5092.1  332.91  5141.7  332.38  5164.1  332.83  5169.4  332.32  5228.2  330.95
  5242.6  331.10  5255.1  332.31  5284.2  333.96  5583.5  339.58  5640.4  341.67
#Mann=9,-1,0
  4547.3    0.05       0  4627.9    0.03       0  4967.2    0.05       0
  4969.5    0.12       0  5003.2    0.05       0  5005.3    0.05       0
  5009.3    0.05       0  5169.4    0.12       0  5255.1    0.05       0
Bank Sta=5005.3,5009.3
Exp/Cntr=0.3,0.1

Type RM Length L Ch R = 1,502,0,0,0
BEGIN DESCRIPTION:
TRIB 8_2 TO YORKTOWN CREEK 1.0
END DESCRIPTION:
XS GIS Cut Line= 3
      2443925.00     13567525.00      2443125.00     13567275.00
      2442875.01     13568024.98
#Sta/Elev= 30
  4122.5  349.96  4144.0  351.64  4153.9  350.98  4164.4  348.01  4171.2  344.44
  4176.5  340.67  4208.9  338.50  4216.8  339.14  4248.2  338.95  4332.0  335.68
  4371.3  336.26  4457.8  333.55  4577.9  333.32  4688.3  334.83  4744.3  331.41
  4809.3  330.24  4944.4  329.94  4958.0  328.69  4990.3  328.09  4990.5  327.59
  4994.3  328.09  5002.8  328.14  5104.5  329.60  5129.3  329.00  5187.8  330.35
  5287.4  332.43  5340.1  332.65  5350.7  333.42  5382.3  333.16  5751.2  340.53
#Mann=7,-1,0
  4122.5    0.03       0  4577.9    0.12       0  4990.3    0.05       0
  4994.3    0.12       0  5002.8    0.05       0  5104.5    0.12       0
  5187.8    0.05       0
Bank Sta=4990.3,4994.3
Exp/Cntr=0.3,0.1

Chan Stop Cuts=-1