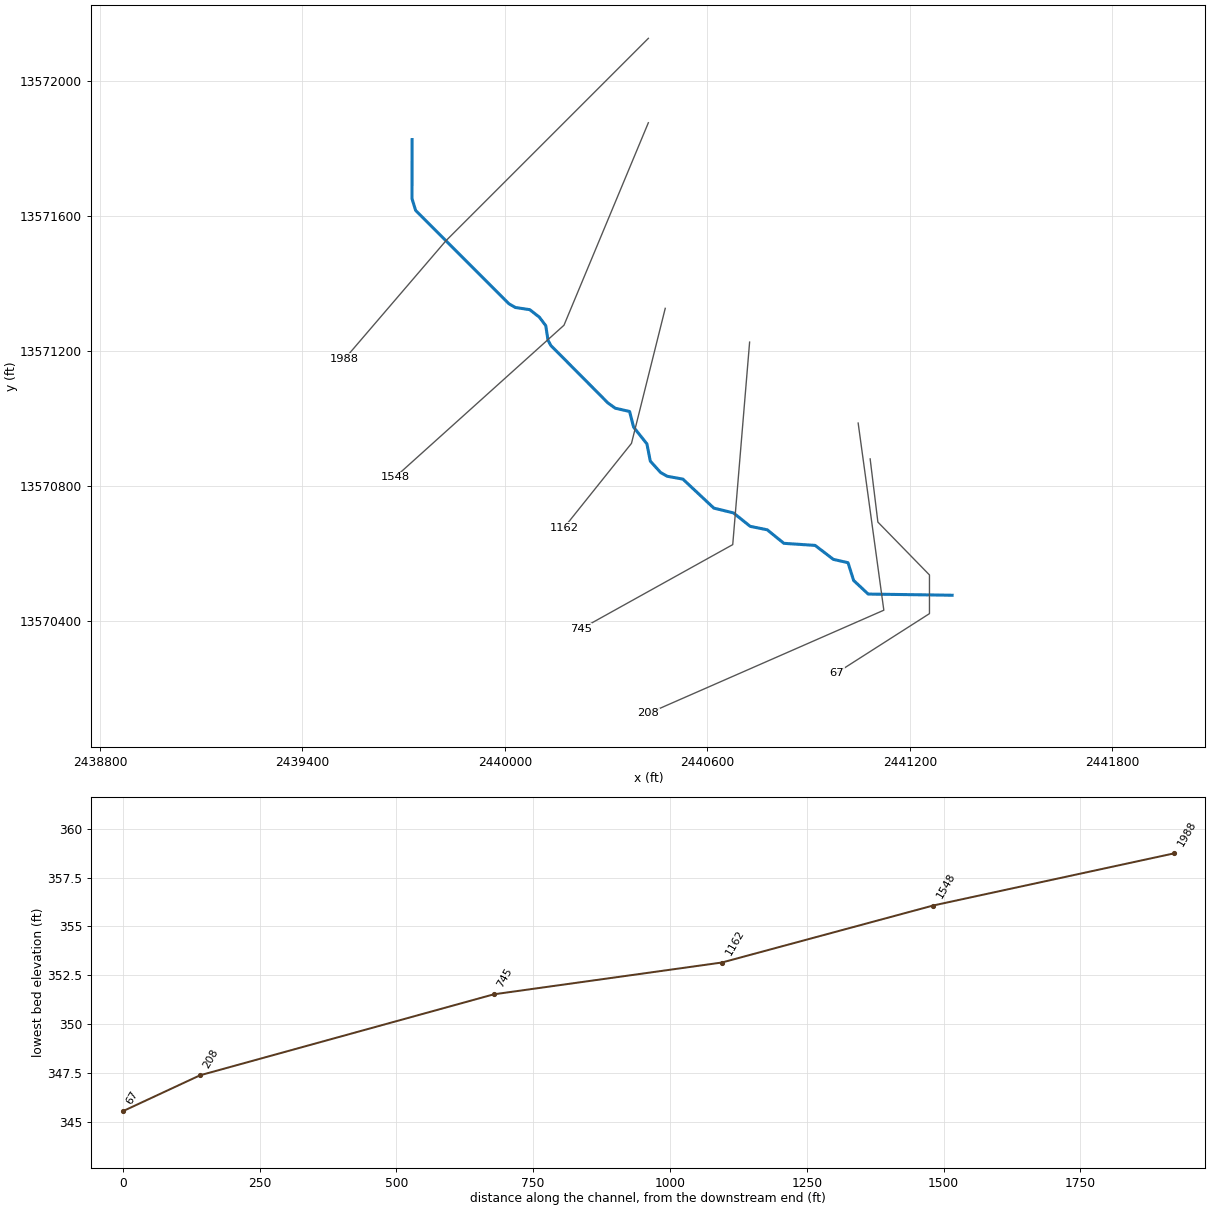
--- TRIB 8_3 TO YORKTOWN CREEK.prj (project) ---

Proj Title=TRIB 8_3 TO YORKTOWN CREEK Base Level Engineering
Current Plan=p01
Default Exp/Contr=0.3,0.1
English Units
Geom File=g01
Flow File=f01
Plan File=p01
BEGIN DESCRIPTION:
TRIB 8_3 TO YORKTOWN CREEK
END DESCRIPTION:

--- TRIB 8_3 TO YORKTOWN CREEK.p01 (plan) ---

Plan Title=Multiple Run
Short Identifier=Multiple
Geom File=g01
Flow File=f01
Subcritical Flow
K Sum by GR= 0
Std Step Tol= 0.01
Critical Tol= 0.01
Num of Std Step Trials= 20
Max Error Tol= 0.3
Flow Tol Ratio= 0.001
Split Flow NTrial= 30
Split Flow Tol= 0.02
Split Flow Ratio= 0.02
Log Output Level= 0
Friction Slope Method= 1
Unsteady Friction Slope Method= 2
Unsteady Bridges Friction Slope Method= 1
Parabolic Critical Depth
Global Vel Dist=  1 , 1 , 1
Global Log Level= 0
CheckData=True
Encroach Param= -1, 0, 0, 0
BEGIN DESCRIPTION:
Multiple Run
END DESCRIPTION:

--- TRIB 8_3 TO YORKTOWN CREEK.f01 (steady flow) ---

Flow Title=Multiple
Number of Profiles=7
Profile Names=10-year,25-year,50-year,1pct_min,100-year,1pct_plu,500-year
River Rch & RM= TRIB 8_3 TO YORK,Reach-1,1988
     300     464     604     383     764    1525    1207
Boundary for River Rch & Prof#=TRIB 8_3 TO YORK,Reach-1,1
Up Type=0
Dn Type=3
Dn Slope=0.005
Boundary for River Rch & Prof#=TRIB 8_3 TO YORK,Reach-1,2
Up Type=0
Dn Type=3
Dn Slope=0.005
Boundary for River Rch & Prof#=TRIB 8_3 TO YORK,Reach-1,3
Up Type=0
Dn Type=3
Dn Slope=0.005
Boundary for River Rch & Prof#=TRIB 8_3 TO YORK,Reach-1,4
Up Type=0
Dn Type=3
Dn Slope=0.005
Boundary for River Rch & Prof#=TRIB 8_3 TO YORK,Reach-1,5
Up Type=0
Dn Type=3
Dn Slope=0.005
Boundary for River Rch & Prof#=TRIB 8_3 TO YORK,Reach-1,6
Up Type=0
Dn Type=3
Dn Slope=0.005
Boundary for River Rch & Prof#=TRIB 8_3 TO YORK,Reach-1,7
Up Type=0
Dn Type=3
Dn Slope=0.005

--- TRIB 8_3 TO YORKTOWN CREEK.g01 (geometry) ---

Geom Title=Existing Conditions

River Reach=TRIB 8_3 TO YORK,Reach-1
Reach XY= 30
      2439725.00     13571825.00      2439724.69     13571649.87
      2439735.47     13571615.20      2440011.80     13571338.64
      2440031.09     13571327.55      2440073.57     13571321.11
      2440102.14     13571298.84      2440121.11     13571273.57
      2440127.55     13571231.09      2440135.79     13571215.34
      2440305.08     13571044.86      2440327.01     13571029.13
      2440369.41     13571019.39      2440381.24     13570973.14
      2440420.81     13570923.26      2440430.73     13570872.46
      2440461.44     13570838.49      2440480.87     13570827.46
      2440527.26     13570819.12      2440618.95     13570733.16
      2440677.19     13570718.90      2440726.72     13570679.16
      2440777.18     13570668.88      2440826.59     13570628.83
      2440919.06     13570622.68      2440973.16     13570581.27
      2441016.51     13570571.46      2441033.15     13570518.92
      2441076.26     13570478.48      2441325.00     13570475.00

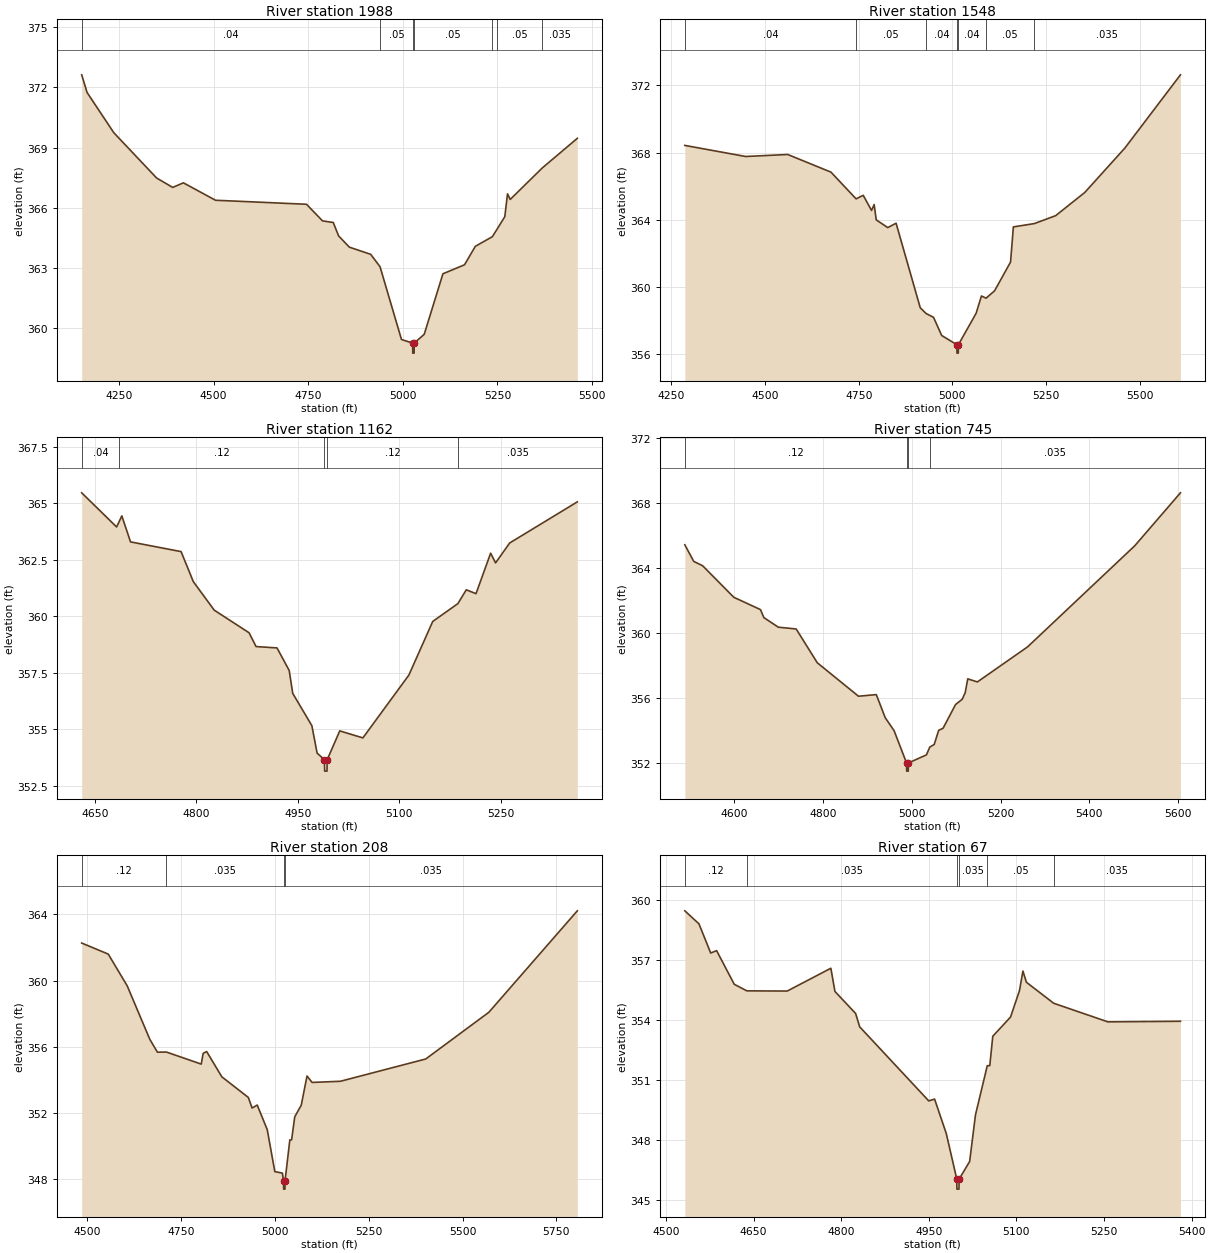
Type RM Length L Ch R = 1,1988,440,440,440
BEGIN DESCRIPTION:
TRIB 8_3 TO YORKTOWN CREEK 5.0
END DESCRIPTION:
XS GIS Cut Line= 3
      2440425.03     13572125.03      2439825.00     13571525.00
      2439524.97     13571174.97
#Sta/Elev= 30
  4151.4  372.63  4165.6  371.75  4236.3  369.74  4349.4  367.48  4391.9  367.01
  4420.1  367.24  4505.0  366.37  4745.4  366.17  4787.8  365.34  4816.1  365.26
  4830.3  364.59  4858.6  364.03  4915.1  363.67  4939.8  363.05  4996.4  359.42
  5026.0  359.24  5026.2  358.74  5029.7  358.74  5030.0  359.24  5056.5  359.68
  5105.9  362.70  5163.0  363.15  5191.5  364.07  5236.4  364.55  5247.8  364.89
  5269.4  365.55  5276.6  366.69  5283.7  366.41  5368.3  367.98  5461.0  369.46
#Mann=7,-1,0
  4151.4    0.04       0  4939.8    0.05       0  5026.0    0.05       0
  5030.0    0.05       0  5236.4    0.12       0  5247.8    0.05       0
  5368.3   0.035       0
Bank Sta=5026,5030
Exp/Cntr=0.3,0.1

Type RM Length L Ch R = 1,1548,386,386,386
BEGIN DESCRIPTION:
TRIB 8_3 TO YORKTOWN CREEK 4.0
END DESCRIPTION:
XS GIS Cut Line= 3
      2440424.99     13571874.97      2440175.00     13571275.00
      2439674.96     13570824.97
#Sta/Elev= 30
  4285.9  368.43  4448.4  367.77  4560.5  367.89  4675.9  366.84  4743.0  365.25
  4762.0  365.46  4784.2  364.56  4791.2  364.91  4796.7  364.00  4827.5  363.54
  4849.7  363.80  4914.2  358.77  4929.6  358.43  4949.7  358.20  4971.4  357.12
  5012.0  356.57  5012.2  356.07  5015.7  356.07  5016.0  356.57  5063.3  358.44
  5077.5  359.47  5089.9  359.34  5112.6  359.78  5155.2  361.49  5162.7  363.58
  5218.9  363.78  5275.6  364.25  5353.3  365.63  5460.2  368.27  5608.6  372.63
#Mann=7,-1,0
  4285.9    0.04       0  4743.0    0.05       0  4929.6    0.04       0
  5012.0    0.04       0  5016.0    0.04       0  5089.9    0.05       0
  5218.9   0.035       0
Bank Sta=5012,5016
Exp/Cntr=0.3,0.1

Type RM Length L Ch R = 1,1162,417,417,417
BEGIN DESCRIPTION:
TRIB 8_3 TO YORKTOWN CREEK 3.0
END DESCRIPTION:
XS GIS Cut Line= 3
      2440475.01     13571325.04      2440375.00     13570925.00
      2440175.01     13570675.01
#Sta/Elev= 30
  4630.7  365.46  4682.3  363.95  4686.4  364.21  4690.0  364.44  4702.9  363.29
  4777.6  362.86  4795.7  361.53  4826.6  360.27  4878.1  359.27  4888.4  358.66
  4919.4  358.60  4937.4  357.60  4942.6  356.59  4970.9  355.16  4978.6  353.95
  4989.5  353.65  4989.8  353.15  4993.3  353.15  4993.5  353.65  5012.1  354.93
  5046.3  354.62  5114.3  357.40  5149.5  359.77  5186.7  360.56  5199.1  361.17
  5213.5  361.00  5235.1  362.79  5242.4  362.36  5263.2  363.24  5363.2  365.06
#Mann=5,-1,0
  4630.7    0.04       0  4686.4    0.12       0  4989.5    0.05       0
  4993.5    0.12       0  5186.7   0.035       0
Bank Sta=4989.5,4993.5
Exp/Cntr=0.3,0.1

Type RM Length L Ch R = 1,745,537,537,537
BEGIN DESCRIPTION:
TRIB 8_3 TO YORKTOWN CREEK 2.0
END DESCRIPTION:
XS GIS Cut Line= 3
      2440725.00     13571225.01      2440675.00     13570625.00
      2440224.98     13570374.99
#Sta/Elev= 30
  4488.6  365.45  4508.7  364.43  4528.8  364.16  4599.0  362.22  4659.2  361.46
  4666.7  360.97  4699.3  360.38  4739.5  360.27  4787.1  358.19  4880.0  356.13
  4920.1  356.23  4940.2  354.81  4960.2  354.01  4988.3  352.02  4988.6  351.52
  4992.1  351.52  4992.3  352.02  5033.0  352.52  5040.6  353.00  5050.6  353.16
  5060.6  354.03  5070.6  354.16  5098.7  355.62  5113.6  355.94  5120.4  356.34
  5126.2  357.20  5147.9  357.01  5261.1  359.17  5502.5  365.39  5605.5  368.65
#Mann=4,-1,0
  4488.6    0.12       0  4988.3    0.05       0  4992.3    0.12       0
  5040.6   0.035       0
Bank Sta=4988.3,4992.3
Exp/Cntr=0.3,0.1

Type RM Length L Ch R = 1,208,141,141,141
BEGIN DESCRIPTION:
TRIB 8_3 TO YORKTOWN CREEK 1.0
END DESCRIPTION:
XS GIS Cut Line= 3
      2441046.61     13570985.13      2441122.65     13570430.71
      2440425.01     13570125.00
#Sta/Elev= 30
  4484.6  362.27  4555.4  361.60  4605.9  359.68  4666.4  356.43  4686.6  355.66
  4710.4  355.67  4803.3  354.94  4808.4  355.59  4817.8  355.70  4858.2  354.17
  4928.9  352.92  4938.9  352.28  4952.6  352.46  4979.3  350.97  4999.5  348.43
  5019.7  348.34  5022.7  347.87  5023.0  347.37  5026.5  347.37  5026.7  347.87
  5039.5  350.35  5044.2  350.35  5052.6  351.75  5069.9  352.45  5085.3  354.22
  5098.8  353.83  5174.3  353.90  5401.9  355.25  5570.2  358.08  5805.9  364.22
#Mann=4,-1,0
  4484.6    0.12       0  4710.4   0.035       0  5022.7   0.035       0
  5026.7   0.035       0
Bank Sta=5022.7,5026.7
Exp/Cntr=0.3,0.1

Type RM Length L Ch R = 1,67,0,0,0
BEGIN DESCRIPTION:
4912
END DESCRIPTION:
XS GIS Cut Line= 5
      2441082.12     13570878.98      2441105.04     13570691.79
      2441257.86     13570535.14      2441257.86     13570420.52
      2440982.77     13570244.77
#Sta/Elev= 30
  4532.4  359.44  4556.6  358.79  4576.7  357.33  4586.8  357.45  4617.0  355.77
  4638.5  355.44  4707.7  355.43  4782.4  356.57  4789.4  355.41  4824.8  354.31
  4831.8  353.64  4950.0  349.94  4960.0  350.03  4980.0  348.31  4998.0  346.03
  4998.2  345.53  5001.7  345.53  5002.0  346.03  5020.0  346.91  5030.0  349.24
  5050.2  351.70  5054.5  351.70  5059.6  353.17  5090.0  354.13  5105.3  355.45
  5111.2  356.43  5117.2  355.87  5163.9  354.82  5256.7  353.89  5380.9  353.92
#Mann=6,-1,0
  4532.4    0.12       0  4638.5   0.035       0  4998.0   0.035       0
  5002.0   0.035       0  5050.2    0.05       0  5163.9   0.035       0
Bank Sta=4998,5002
Exp/Cntr=0.3,0.1

Chan Stop Cuts=-1