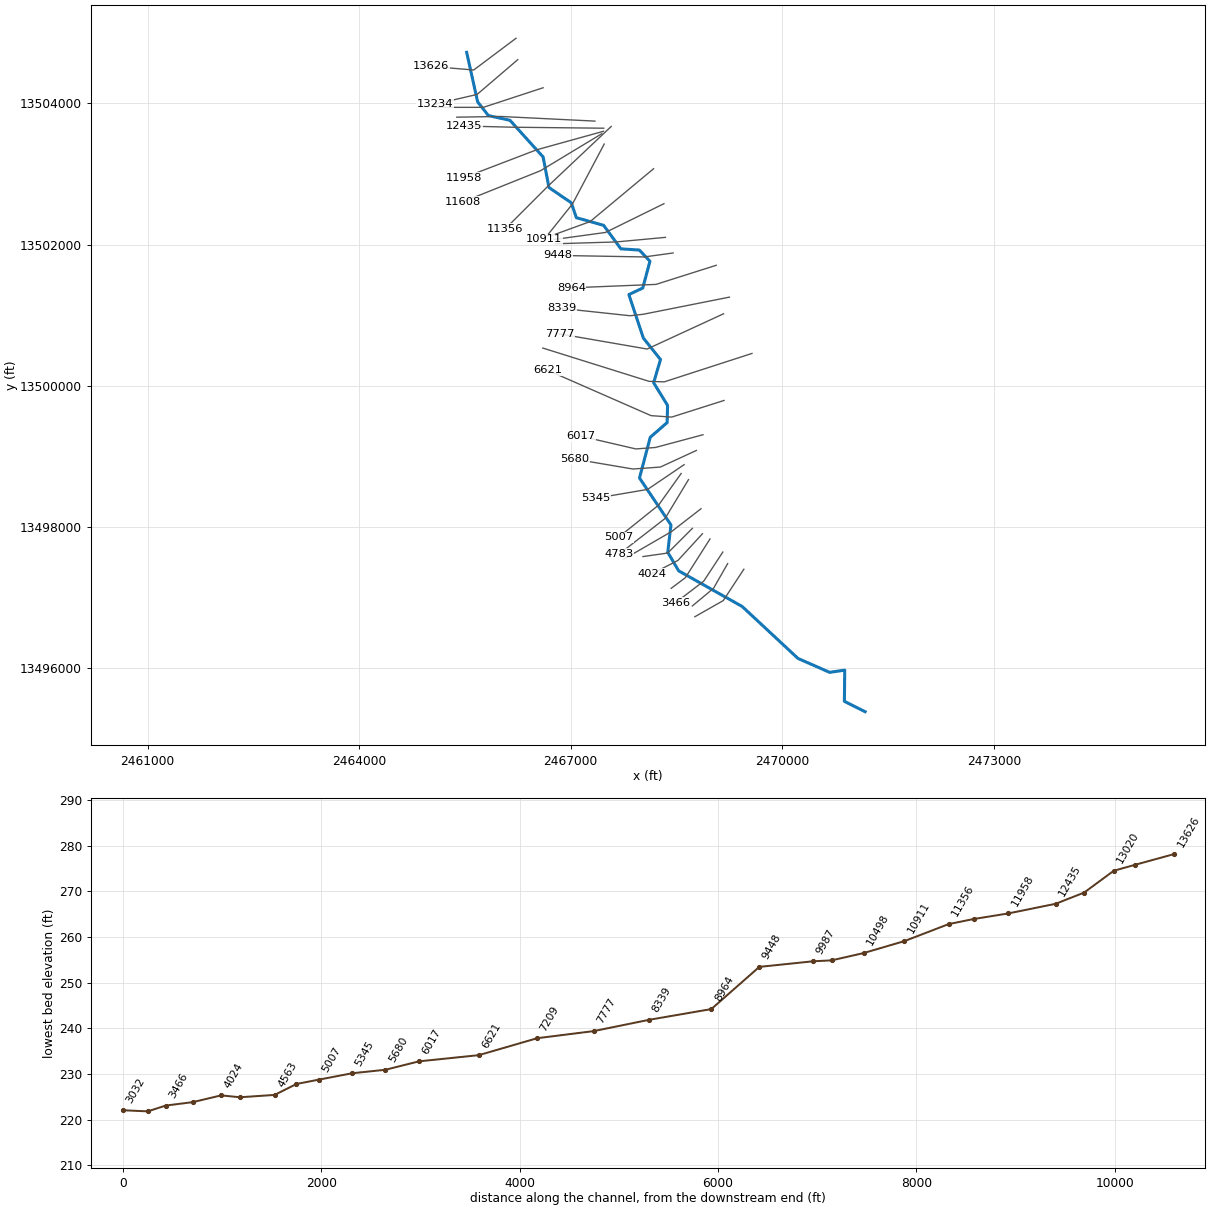
--- TRIB 9 TO EIGHTEENMILE CREEK.prj (project) ---

Proj Title=TRIB 9 TO EIGHTEENMILE CREEK Base Level Engineering
Current Plan=p01
Default Exp/Contr=0.3,0.1
English Units
Geom File=g01
Flow File=f01
Plan File=p01
Y Axis Title=Elevation
X Axis Title(PF)=Main Channel Distance
X Axis Title(XS)=Station
BEGIN DESCRIPTION:
TRIB 9 TO EIGHTEENMILE CREEK
END DESCRIPTION:
DSS Export Rating Curves= 0
DSS Export Rating Curve Sorted= 0
DSS Export Volume Flow Curves= 0
DXF OffsetX= 0
DXF OffsetY= 0
DXF ScaleX= 1
DXF ScaleY= 10

--- TRIB 9 TO EIGHTEENMILE CREEK.p01 (plan) ---

Plan Title=Multiple Run
Program Version=4.10
Short Identifier=Multiple
Geom File=g01
Flow File=f01
Subcritical Flow
K Sum by GR= 0
Std Step Tol= 0.01
Critical Tol= 0.01
Num of Std Step Trials= 20
Max Error Tol= 0.3
Flow Tol Ratio= 0.001
Split Flow NTrial= 30
Split Flow Tol= 0.02
Split Flow Ratio= 0.02
Log Output Level= 0
Friction Slope Method= 1
Unsteady Friction Slope Method= 2
Unsteady Bridges Friction Slope Method= 1
Parabolic Critical Depth
Global Vel Dist= 1 , 1 , 1
Global Log Level= 0
CheckData=True
Persistent XS Scale= 4000 , 6000 , 265 , 230 , 500 , 5
Encroach Param=-1 ,0,0, 0
BEGIN DESCRIPTION:
Multiple Run
END DESCRIPTION:
Computation Interval=1HOUR
Output Interval=1HOUR
Run HTab= 0
Run UNet= 0
Run PostProcess= 0
Run WQNet= 0
UNET Theta= 1
UNET Theta Warmup= 1
UNET ZTol= 0.02
UNET ZSATol= 0.05
UNET MxIter= 20
UNET MaxInSteps= 0
UNET DtIC= 0
UNET DtMin= 0
UNET MaxCRTS= 20
UNET WFStab= 2
UNET SFStab= 1
UNET WFX= 1
UNET SFX= 1
UNET DSS MLevel= 4
UNET DZMax Abort= 100
UNET Convert EG Bridges= 0
UNET Use Existing IB Tables=-1
UNET Froude Reduction=False
UNET Froude Limit= 1
UNET Froude Power= 10
UNET Time Slicing=0,0, 5
UNET Junction Losses=0
Instantaneous Interval=1HOUR
Write IC File= 0
Write IC File at Sim End=0
Echo Input=False
Echo Parameters=False
Echo Output=False
Write Detailed= 0
WQ AD Non Conservative
WQ ULTIMATE=-1
WQ Max Comp Step=1HOUR
WQ Output Interval=15MIN
WQ Output Selected Increments= 0
WQ Output face flow=0
WQ Output face velocity=0
WQ Output face area=0
WQ Output face dispersion=0
WQ Output cell volume=0
WQ Output cell surface area=0
WQ Output cell continuity=0
WQ Output cumulative cell continuity=0
WQ Output face conc=0
WQ Output face dconc_dx=0
WQ Output face courant=0
WQ Output face peclet=0
WQ Output face adv mass=0
WQ Output face disp mass=0
WQ Output cell mass=0
WQ Output cell source sink temp=0
WQ Output cell source sink nsm=0
WQ Output MaxMinRange=-1
WQ Daily Max Min Mean=-1
WQ Daily Range=0
WQ Daily Time=0
WQ Create Restart=0
WQ Fixed Restart=0
WQ System Summary=0
WQ Use Fixed Temperature=0
Sorting and Armoring Iterations= 10
XS Update Threshold= 0.02
Hydraulics Update Threshold= 0.02
Energy Slope Method= 1
Volume Change Method= 0
XS Weighting Method= 0
Number of US Weighted Cross Sections= 1
Number of DS Weighted Cross Sections= 1
Upstream XS Weight=0.25
Main XS Weight=0.5
Downstream XS Weight=0.25
Number of DS XS's Weighted with US Boundary= 1
Upstream Boundary Weight= 1
Weight of XSs Associated with US Boundary= 0
Number of US XS's Weighted with DS Boundary= 1
Downstream Boundary Weight= 0.5
Weight of XSs Associated with DS Boundary= 0.5
Sediment Output Level= 4
Mass or Volume Output= 0
Output Increment Type= 1
Profile and TS Output Increment= 10
XS Output Flag= 0
XS Output Increment= 10
Disregard all LS=0
Disregard all Conn=0
Disregard all Breaches=0
Disregard all Pumps=0

--- TRIB 9 TO EIGHTEENMILE CREEK.f01 (steady flow) ---

Flow Title=Multiple
Number of Profiles=7
Profile Names=10-year,25-year,50-year,1pct_min,100-year,1pct_plu,500-year
River Rch & RM= TRIB 9 TO EIGHTE,Reach-1,13626
     513     815    1084     698    1393    2780    2276
River Rch & RM= TRIB 9 TO EIGHTE,Reach-1,9448
     710    1152    1552    1012    2019    4029    3383
River Rch & RM= TRIB 9 TO EIGHTE,Reach-1,7209
     836    1366    1850    1211    2416    4821    4082
River Rch & RM= TRIB 9 TO EIGHTE,Reach-1,3738
    1072    1775    2424    1600    3192    6369    5481
Boundary for River Rch & Prof#=TRIB 9 TO EIGHTE,Reach-1,1
Up Type=0
Dn Type=3
Dn Slope=0.005
Boundary for River Rch & Prof#=TRIB 9 TO EIGHTE,Reach-1,2
Up Type=0
Dn Type=3
Dn Slope=0.005
Boundary for River Rch & Prof#=TRIB 9 TO EIGHTE,Reach-1,3
Up Type=0
Dn Type=3
Dn Slope=0.005
Boundary for River Rch & Prof#=TRIB 9 TO EIGHTE,Reach-1,4
Up Type=0
Dn Type=3
Dn Slope=0.005
Boundary for River Rch & Prof#=TRIB 9 TO EIGHTE,Reach-1,5
Up Type=0
Dn Type=3
Dn Slope=0.005
Boundary for River Rch & Prof#=TRIB 9 TO EIGHTE,Reach-1,6
Up Type=0
Dn Type=3
Dn Slope=0.005
Boundary for River Rch & Prof#=TRIB 9 TO EIGHTE,Reach-1,7
Up Type=0
Dn Type=3
Dn Slope=0.005

--- TRIB 9 TO EIGHTEENMILE CREEK.g01 (geometry) ---

Geom Title=Existing Conditions
Program Version=4.10

River Reach=TRIB 9 TO EIGHTE,Reach-1
Reach XY= 30
        2465525.       13504725.      2465680.52     13504022.57
       2465833.3     13503828.08      2466138.65     13503761.74
      2466608.71     13503241.71      2466691.63     13502808.29
      2467008.37     13502591.71      2467080.25     13502380.44
       2467466.7     13502271.92      2467711.64     13501938.63
      2467973.75     13501921.54      2468123.36     13501763.17
      2468021.65      13501383.1      2467824.87     13501290.43
      2468030.52     13500672.57       2468273.2     13500368.89
      2468175.38     13500040.27      2468373.38     13499718.97
      2468367.47     13499474.99      2468127.94     13499267.02
      2467975.38     13498690.16      2468421.38      13498023.5
      2468375.97     13497635.29      2468530.47     13497372.55
      2469431.19     13496867.15       2470222.3     13496130.36
       2470671.7     13495933.08      2470885.18     13495964.68
      2470880.29     13495522.32        2471175.       13495375.

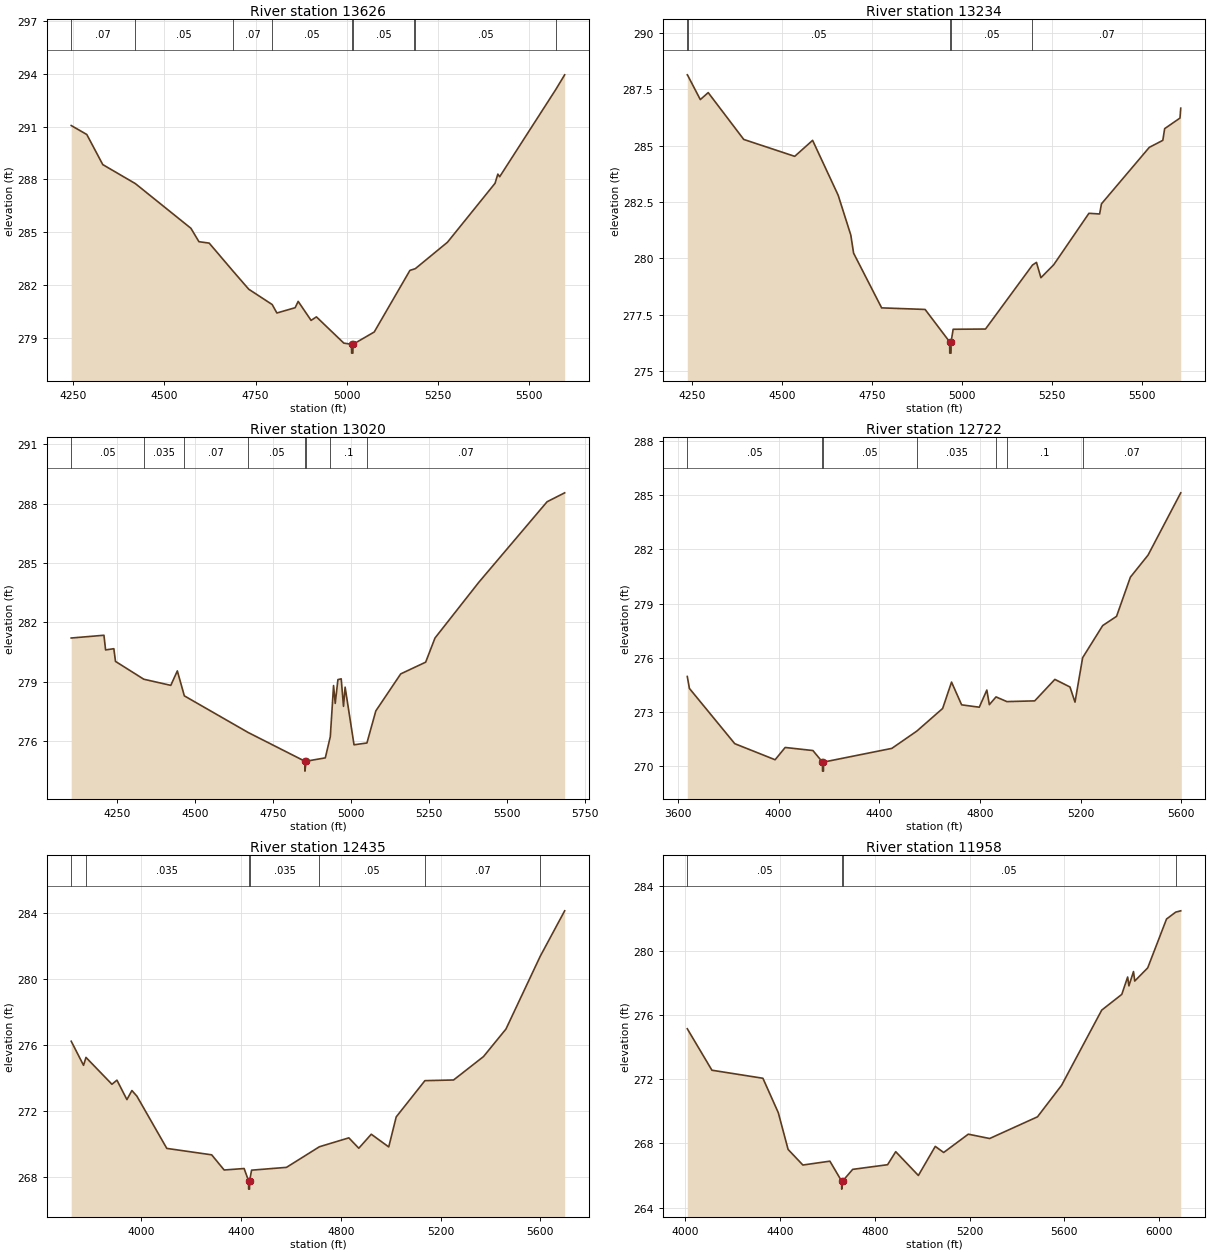
Type RM Length L Ch R = 1 ,13626   ,392,392,392
BEGIN DESCRIPTION:
TRIB 9 TO EIGHTEENMILE CREEK 29.0
END DESCRIPTION:
XS GIS Cut Line= 3
      2466225.01     13504925.01        2465625.       13504475.
      2465024.99       13504525.
#Sta/Elev= 30
    4245  291.06  4287.7  290.55  4331.5  288.84  4420.8  287.76  4573.1  285.22
    4595  284.46  4623.1  284.38  4688.8  282.78  4731.5  281.76  4795.7  280.89
  4808.6  280.41  4858.6  280.71  4866.9  281.07  4902.3  279.99  4916.9  280.19
  4991.9   278.7  5013.1  278.63  5013.3  278.13  5016.8  278.13  5017.1  278.63
  5075.3  279.33  5173.1  282.83  5185.2  282.91    5188  282.93    5276  284.43
  5406.4  287.78    5414   288.3    5419  288.15  5572.9  293.11  5597.1  293.94
#Mann= 9 ,-1 , 0
    4245     .07       0  4420.8     .05       0  4688.8     .07       0
  4795.7     .05       0  5013.1     .05       0  5017.1     .05       0
  5185.2     .12       0    5188     .05       0  5572.9     .07       0
Bank Sta=5013.1,5017.1
XS Rating Curve= 0 ,0
Exp/Cntr=0.3,0.1

Type RM Length L Ch R = 1 ,13234   ,214,214,214
BEGIN DESCRIPTION:
Mapping XS 1c0252af
END DESCRIPTION:
XS GIS Cut Line= 3
      2466249.63     13504621.67      2465673.25     13504128.62
      2465076.57     13503989.86
#Sta/Elev= 30
  4237.1  288.15  4237.8  288.14  4273.3  287.05  4295.2  287.36    4394  285.28
  4535.6  284.53  4585.3  285.24  4656.4   282.8  4691.5  281.03  4699.2  280.23
  4777.1   277.8  4897.9  277.73  4966.1  276.29  4966.4  275.79  4969.9  275.79
  4970.1  276.29  4975.8  276.85  5065.7  276.86  5196.2   279.7  5207.3  279.82
  5219.7  279.14    5255  279.71  5353.1     282  5382.8  281.97  5387.9  282.42
  5520.9  284.93  5558.4  285.24  5563.5  285.76  5606.1  286.23  5608.2  286.67
#Mann= 5 ,-1 , 0
  4237.1    .035       0  4237.8     .05       0  4966.1     .05       0
  4970.1     .05       0  5196.2     .07       0
Bank Sta=4966.1,4970.1
XS Rating Curve= 0 ,0
Exp/Cntr=0.3,0.1

Type RM Length L Ch R = 1 ,13020   ,298,298,298
BEGIN DESCRIPTION:
Mapping XS d2e6ddfd
END DESCRIPTION:
XS GIS Cut Line= 3
      2466608.84     13504223.08      2465761.62      13503945.3
      2465068.61      13503945.3
#Sta/Elev= 30
  4101.5  281.21  4206.6  281.35  4211.9  280.61  4238.4  280.67  4243.7  280.03
  4334.5  279.13  4421.3  278.82  4442.3  279.55  4464.8  278.29  4669.8  276.44
  4851.8  274.99  4852.1  274.49  4855.8  274.99  4917.5  275.16  4933.5  276.23
    4944  278.81  4949.3  277.91    4958  279.11  4968.5  279.15  4975.9  277.76
  4981.1  278.73  5009.7  275.82  5051.1  275.91  5079.7  277.53  5159.7   279.4
  5239.7  279.99  5269.7  281.21  5409.7  284.01  5629.7  288.09  5686.1  288.54
#Mann= 8 ,-1 , 0
  4101.5     .05       0  4334.5    .035       0  4464.8     .07       0
  4669.8     .05       0  4851.8     .05       0  4855.8     .05       0
  4933.5      .1       0  5051.1     .07       0
Bank Sta=4851.8,4855.8
XS Rating Curve= 0 ,0
Exp/Cntr=0.3,0.1

Type RM Length L Ch R = 1 ,12722   ,287,287,287
BEGIN DESCRIPTION:
Mapping XS d9e6dfb5
END DESCRIPTION:
XS GIS Cut Line= 3
      2467343.36     13503750.15      2466003.11     13503816.12
      2465385.08      13503805.7
#Sta/Elev= 30
  3637.5  274.96  3645.9   274.3  3826.1  271.24  3986.3  270.35  4026.3  271.03
  4136.5  270.86  4174.5  270.22  4174.8  269.72  4178.3  269.72  4178.5  270.22
    4450  270.98  4549.5  271.94  4651.8  273.19  4687.1  274.65  4727.2  273.39
  4797.3  273.26  4827.3  274.21  4837.3   273.4  4863.8  273.83  4906.9  273.57
  5017.5  273.61  5097.5   274.8  5157.5  274.38  5177.5  273.54  5207.8     276
  5287.5  277.78  5342.5  278.29  5397.5  280.46  5467.6  281.68  5597.5  285.13
#Mann= 7 ,-1 , 0
  3637.5     .05       0  4174.5     .05       0  4178.5     .05       0
  4549.5    .035       0  4863.8     .05       0  4906.9      .1       0
  5207.8     .07       0
Bank Sta=4174.5,4178.5
XS Rating Curve= 0 ,0
Exp/Cntr=0.3,0.1

Type RM Length L Ch R = 1 ,12435   ,477,477,477
BEGIN DESCRIPTION:
Mapping XS efab9de1
END DESCRIPTION:
XS GIS Cut Line= 3
      2467468.35     13503649.45      2466183.67     13503663.34
      2465489.64     13503680.69
#Sta/Elev= 30
  3718.6  276.23  3768.1  274.77  3777.8  275.25    3882  273.62    3902  273.87
    3942  272.69    3962  273.24    3982   272.9    4102  269.73    4282  269.34
    4332  268.42    4412  268.51    4430  267.76  4430.2  267.26  4433.7  267.26
    4434  267.76    4442  268.41    4582  268.58  4713.9  269.83    4832  270.37
    4872  269.74    4922  270.59    4992  269.82    5022  271.64  5137.2  273.84
  5252.1  273.88  5372.1   275.3  5462.2  276.97  5599.5  281.38  5697.6  284.14
#Mann= 7 ,-1 , 0
  3718.6     .05       0  3777.8    .035       0    4430     .05       0
    4434    .035       0  4713.9     .05       0  5137.2     .07       0
  5599.5    .035       0
Bank Sta=4430,4434
XS Rating Curve= 0 ,0
Exp/Cntr=0.3,0.1

Type RM Length L Ch R = 1 ,11958   ,350,350,350
BEGIN DESCRIPTION:
Mapping XS 5d1eeb76
END DESCRIPTION:
XS GIS Cut Line= 3
      2467465.24     13503606.03      2466513.85     13503342.14
       2465490.1     13502949.99
#Sta/Elev= 30
  4008.1  275.13  4112.1  272.55  4327.4  272.05  4392.3  269.91  4433.8  267.62
  4496.1  266.65  4610.2  266.89  4659.8  265.65  4660.1  265.15  4663.8  265.65
  4706.5  266.38  4853.9  266.67  4888.2  267.48  4983.8     266  5055.2  267.81
  5090.6  267.43  5194.7  268.57  5284.8   268.3  5486.8  269.65  5588.5  271.61
    5758  276.29  5842.8  277.27  5867.5  278.35  5872.8   277.8  5892.2  278.69
  5897.5   278.1  5952.2  278.92  6031.7  281.96  6070.5  282.39  6091.7  282.47
#Mann= 4 ,-1 , 0
  4008.1     .05       0  4659.8     .05       0  4663.8     .05       0
  6070.5    .035       0
Bank Sta=4659.8,4663.8
XS Rating Curve= 0 ,0
Exp/Cntr=0.3,0.1

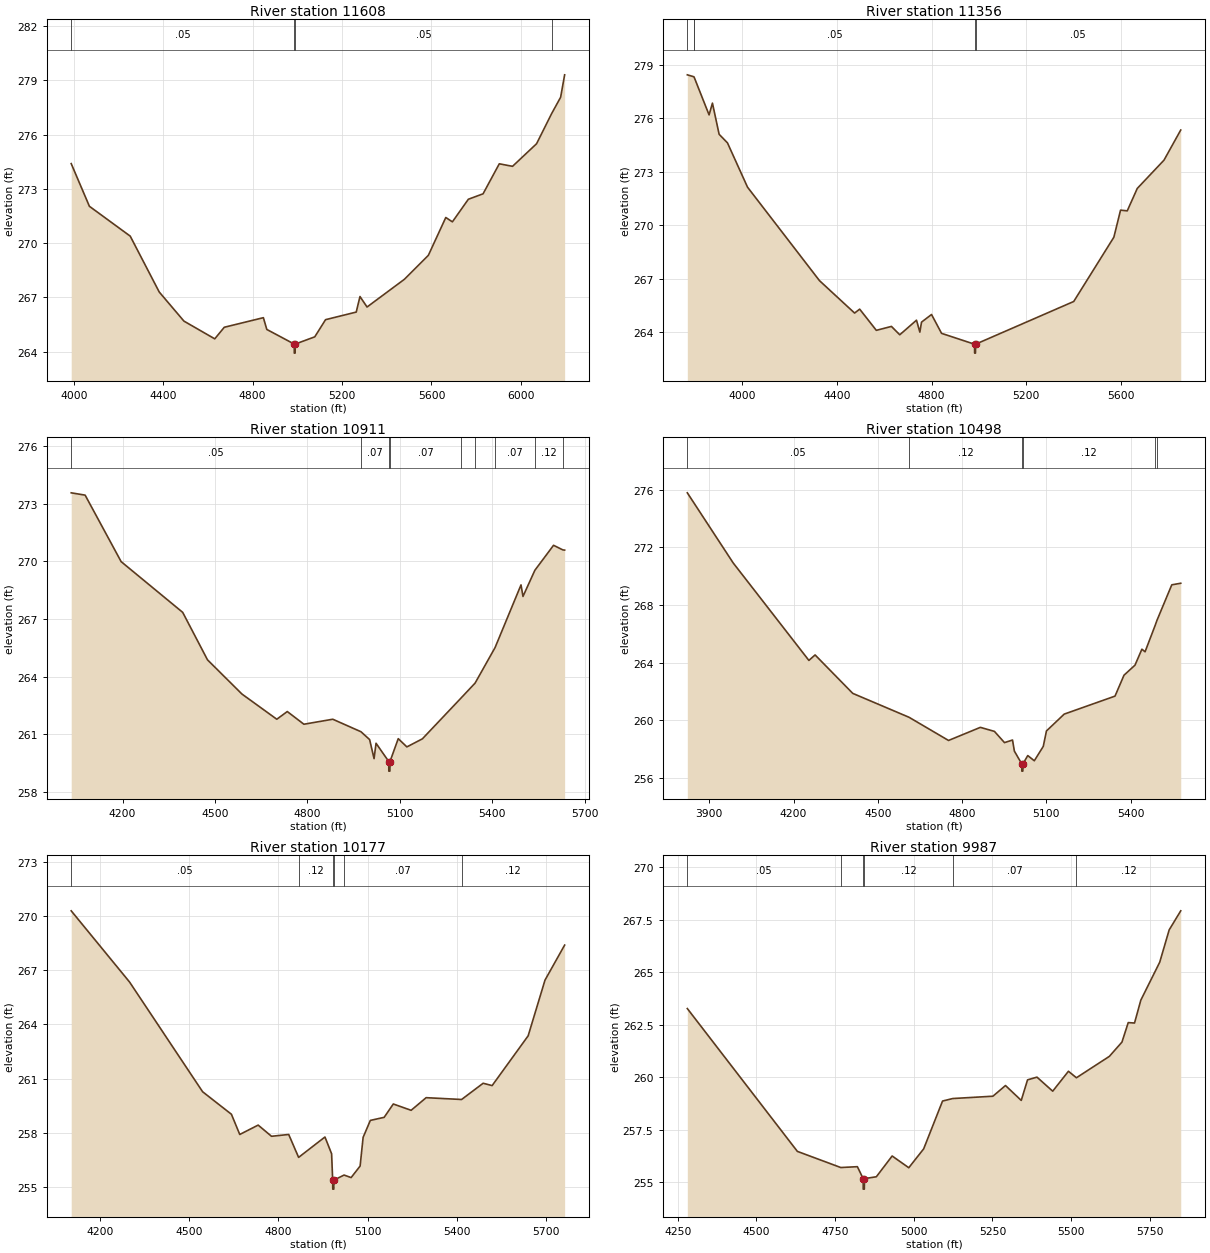
Type RM Length L Ch R = 1 ,11608   ,252,252,252
BEGIN DESCRIPTION:
Mapping XS 641005b4
END DESCRIPTION:
XS GIS Cut Line= 3
      2467440.94     13503571.31      2466572.88       13503047.
      2465465.24     13502602.56
#Sta/Elev= 30
  3988.2   274.4  4069.6  272.04  4252.2  270.39    4382   267.3  4492.6  265.69
  4630.4  264.71  4673.1  265.35    4848  265.88  4863.3  265.23  4986.2  264.42
  4986.4  263.92  4989.9  263.92  4990.2  264.42  5077.8  264.82  5126.2  265.77
  5263.4  266.19  5280.2  267.05  5311.8  266.47  5478.6     268  5586.2  269.33
  5664.1  271.42  5693.7  271.18  5765.1  272.43  5830.9  272.73  5903.5  274.39
  5962.7  274.25  6070.3   275.5  6137.4  277.16  6177.9  278.07  6195.8  279.31
#Mann= 4 ,-1 , 0
  3988.2     .05       0  4986.2     .05       0  4990.2     .05       0
  6137.4    .035       0
Bank Sta=4986.2,4990.2
XS Rating Curve= 0 ,0
Exp/Cntr=0.3,0.1

Type RM Length L Ch R = 1 ,11356   ,445,445,445
BEGIN DESCRIPTION:
TRIB 9 TO EIGHTEENMILE CREEK 24.0
END DESCRIPTION:
XS GIS Cut Line= 3
      2467574.97     13503674.97        2466675.       13502825.
      2466075.02     13502225.02
#Sta/Elev= 30
  3766.8  278.44  3794.8  278.33  3797.1  278.26  3858.8  276.19    3873  276.85
  3901.3   275.1  3936.5  274.62  4021.4  272.13  4325.7  266.88  4474.1  265.06
  4495.6  265.28    4566  264.09  4629.9  264.31  4665.1  263.84  4735.9  264.66
    4750  263.99  4757.1  264.55  4799.4  264.98  4841.9  263.92  4981.5  263.31
  4981.7  262.81  4985.2  262.81  4985.5  263.31  5400.7  265.71  5570.4  269.32
  5598.7  270.84    5627   270.8  5669.4  272.06  5782.5  273.65  5853.2  275.34
#Mann= 5 ,-1 , 0
  3766.8     .05       0  3794.8    .035       0  3797.1     .05       0
  4981.5     .05       0  4985.5     .05       0
Bank Sta=4981.5,4985.5
XS Rating Curve= 0 ,0
Exp/Cntr=0.3,0.1

Type RM Length L Ch R = 1 ,10911   ,413,413,413
BEGIN DESCRIPTION:
TRIB 9 TO EIGHTEENMILE CREEK 23.0
END DESCRIPTION:
XS GIS Cut Line= 3
      2467474.98     13503424.96        2467025.       13502575.
      2466625.02     13502075.03
#Sta/Elev= 30
  4033.2  273.57  4078.4  273.45  4195.3  269.99  4395.2  267.35  4475.7  264.88
  4587.6   263.1  4700.7  261.79  4734.7  262.19  4788.7  261.53  4882.4  261.79
    4974  261.14  5002.1  260.73  5016.5  259.74  5022.9  260.54  5064.2  259.59
  5064.4  259.09  5067.9  259.09  5068.2  259.59    5095  260.78    5123  260.35
  5173.4  260.77  5298.7  262.89  5344.5  263.67  5409.4  265.52  5493.6  268.78
    5500  268.18  5538.6  269.54  5599.2  270.84  5629.5   270.6  5635.2  270.59
#Mann= 9 ,-1 , 0
  4033.2     .05       0    4974     .07       0  5064.2     .05       0
  5068.2     .07       0  5298.7     .12       0  5344.5     .05       0
  5409.4     .07       0  5538.6     .12       0  5629.5     .07       0
Bank Sta=5064.2,5068.2
XS Rating Curve= 0 ,0
Exp/Cntr=0.3,0.1

Type RM Length L Ch R = 1 ,10498   ,321,321,321
BEGIN DESCRIPTION:
TRIB 9 TO EIGHTEENMILE CREEK 22.0
END DESCRIPTION:
XS GIS Cut Line= 3
      2468174.98     13503074.98        2467275.       13502325.
      2466725.04     13502125.02
#Sta/Elev= 30
  3821.8  275.79  3985.1  270.92  4254.6  264.15  4276.7  264.53  4410.8  261.86
  4611.2   260.2  4751.8  258.59  4865.1   259.5  4915.2  259.22    4951  258.44
  4979.6  258.62  4986.2  257.85  5012.6  256.96  5012.8  256.46  5016.3  256.46
  5016.6  256.96  5033.9  257.54  5057.2  257.18  5089.1  258.18  5100.4  259.25
  5163.6  260.42  5344.5  261.67  5376.4  263.12  5415.6  263.82  5440.2  264.93
  5451.5  264.75  5487.2  266.57    5494  266.94  5546.6   269.4  5578.5  269.51
#Mann= 6 ,-1 , 0
  3821.8     .05       0  4611.2     .12       0  5012.6     .05       0
  5016.6     .12       0  5487.2     .07       0    5494     .12       0
Bank Sta=5012.6,5016.6
XS Rating Curve= 0 ,0
Exp/Cntr=0.3,0.1

Type RM Length L Ch R = 1 ,10177   ,190,190,190
BEGIN DESCRIPTION:
Mapping XS 4fea9c93
END DESCRIPTION:
XS GIS Cut Line= 3
      2468321.54     13502579.02      2467492.58     13502171.05
       2466763.4     13502071.22
#Sta/Elev= 30
    4103   270.3  4299.4  266.35    4545  260.27    4642  259.02    4670   257.9
  4731.9  258.42  4776.8   257.8  4834.7   257.9    4868  256.63  4956.6  257.76
    4979  256.83  4982.6  255.37  4982.9  254.87  4986.4  254.87  4986.6  255.37
    5021  255.65  5044.7  255.51  5074.9  256.15    5085  257.74  5109.3  258.68
  5155.7  258.85  5186.6  259.59  5246.5  259.24    5297  259.94  5416.3  259.84
  5488.8  260.74    5519  260.61  5640.2  263.37  5696.9  266.46  5762.9   268.4
#Mann= 6 ,-1 , 0
    4103     .05       0    4868     .12       0  4982.6     .05       0
  4986.6     .12       0    5021     .07       0  5416.3     .12       0
Bank Sta=4982.6,4986.6
XS Rating Curve= 0 ,0
Exp/Cntr=0.3,0.1

Type RM Length L Ch R = 1 ,9987    ,539,539,539
BEGIN DESCRIPTION:
Mapping XS 655fd347
END DESCRIPTION:
XS GIS Cut Line= 3
      2468343.27      13502101.6      2467644.49      13502036.5
      2466778.18     13502010.51
#Sta/Elev= 30
  4280.2  263.27    4630  256.46    4768  255.69  4820.8  255.73  4839.2  255.16
  4839.4  254.66  4842.9  254.66  4843.2  255.16  4881.1  255.25  4931.3  256.24
  4984.2  255.68  5031.5  256.58  5091.5  258.86    5124  258.98  5251.6  259.09
  5291.6   259.6  5341.7  258.89  5361.7  259.87  5391.7     260  5441.7  259.33
  5491.7  260.28  5517.1  259.97  5621.8  260.99  5661.8  261.67  5681.8   262.6
  5701.8  262.58  5721.8  263.67  5781.9  265.48  5811.9  267.02  5848.7  267.93
#Mann= 6 ,-1 , 0
  4280.2     .05       0    4768     .12       0  4839.2     .05       0
  4843.2     .12       0    5124     .07       0  5517.1     .12       0
Bank Sta=4839.2,4843.2
XS Rating Curve= 0 ,0
Exp/Cntr=0.3,0.1

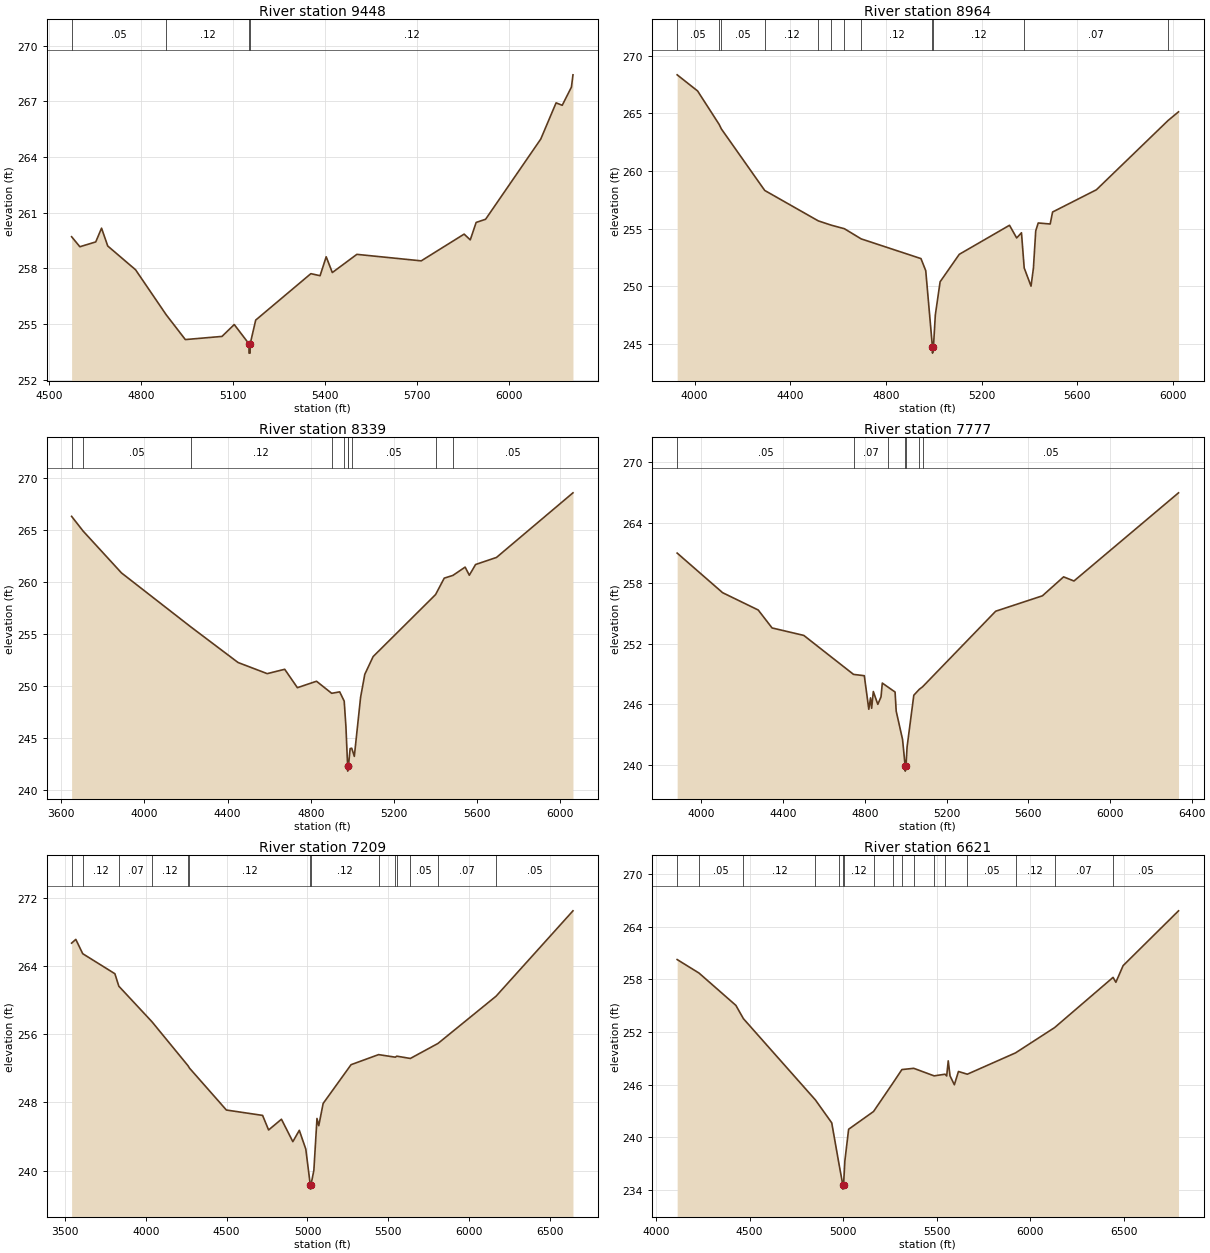
Type RM Length L Ch R = 1 ,9448    ,484,484,484
BEGIN DESCRIPTION:
Mapping XS d2f8f53b
END DESCRIPTION:
XS GIS Cut Line= 3
      2468451.78     13501880.25       2468043.8     13501823.83
      2466819.96     13501845.53
#Sta/Elev= 30
  4574.4  259.71  4601.4  259.17  4653.1  259.43  4672.1  260.17  4692.3  259.21
  4783.1  257.93  4882.9  255.51  4945.5  254.17  5065.1  254.34  5105.1  254.98
  5153.1  253.94  5153.3  253.44  5156.8  253.44  5157.1  253.94  5175.1  255.22
  5355.1  257.72  5385.1  257.61  5405.1  258.63  5425.1  257.78  5505.1  258.76
  5715.2  258.41  5855.2  259.85  5875.2  259.54  5894.4  260.48  5925.2  260.65
  6105.2  264.97  6155.2  266.92  6175.3  266.79  6205.3  267.77  6210.3  268.43
#Mann= 4 ,-1 , 0
  4574.4     .05       0  4882.9     .12       0  5153.1     .05       0
  5157.1     .12       0
Bank Sta=5153.1,5157.1
XS Rating Curve= 0 ,0
Exp/Cntr=0.3,0.1

Type RM Length L Ch R = 1 ,8964    ,625,625,625
BEGIN DESCRIPTION:
Mapping XS fc91e4af
END DESCRIPTION:
XS GIS Cut Line= 3
      2469062.81     13501705.42      2468208.67      13501434.6
       2467008.6     13501386.04
#Sta/Elev= 30
  3926.8  268.34  4012.3  266.94  4102.7  264.03  4111.3  263.66  4293.1  258.31
  4517.2  255.67  4571.3   255.3  4626.4  254.99  4696.5  254.11  4946.6   252.4
  4966.6  251.35  4994.7   244.7  4994.9   244.2  4998.7   244.7  5006.7  247.52
  5026.7  250.39  5106.8  252.77  5316.9  255.29  5346.9  254.19    5367  254.64
  5378.4  251.59    5407  250.01    5417  251.58  5426.6   254.8    5437  255.49
  5487.1   255.4  5497.1  256.44  5680.4  258.37  5980.3  264.38  6023.9  265.13
#Mann= 12 ,-1 , 0
  3926.8     .05       0  4102.7     .07       0  4111.3     .05       0
  4293.1     .12       0  4517.2      .1       0  4571.3     .12       0
  4626.4     .07       0  4696.5     .12       0  4994.7     .05       0
  4998.7     .12       0  5378.4     .07       0  5980.3     .05       0
Bank Sta=4994.7,4998.7
XS Rating Curve= 0 ,0
Exp/Cntr=0.3,0.1

Type RM Length L Ch R = 1 ,8339    ,562,562,562
BEGIN DESCRIPTION:
Mapping XS 7a48f2e3
END DESCRIPTION:
XS GIS Cut Line= 4
      2469250.36     13501254.05      2468028.12     13501010.99
      2467840.62     13500990.15      2466869.21     13501094.23
#Sta/Elev= 30
  3649.8  266.35  3704.9  264.94  3889.8  260.91  4223.5  255.72  4450.5   252.3
  4590.8  251.23  4674.9  251.65    4736  249.88  4827.8   250.5    4901  249.34
  4939.4  249.48  4961.1  248.59  4969.5  246.12  4977.6  242.36  4977.9  241.86
  4981.6  242.36  4989.7  244.03  4997.4  244.06  5009.8  243.28    5040  248.96
  5060.1  251.16  5100.3  252.87  5400.7  258.83  5442.3  260.41  5483.8  260.67
  5542.9  261.47    5563  260.69  5593.1  261.72  5693.7   262.4  6061.6  268.61
#Mann= 10 ,-1 , 0
  3649.8     .07       0  3704.9     .05       0  4223.5     .12       0
    4901     .05       0  4961.1      .1       0  4977.6     .05       0
  4981.6      .1       0  4997.4     .05       0  5400.7     .07       0
  5483.8     .05       0
Bank Sta=4977.6,4981.6
XS Rating Curve= 0 ,0
Exp/Cntr=0.3,0.1

Type RM Length L Ch R = 1 ,7777    ,568,568,568
BEGIN DESCRIPTION:
Mapping XS 0fcef5d4
END DESCRIPTION:
XS GIS Cut Line= 3
      2469166.97     13501017.92      2468083.67     13500517.93
      2466840.59     13500733.21
#Sta/Elev= 30
  3881.1  261.01  4103.5  257.08    4278  255.36  4345.8  253.58  4501.1  252.84
  4744.6  248.97  4797.4  248.84  4819.4  245.51  4827.8  246.64  4833.3  245.61
  4841.5  247.27  4863.5     246  4879.2  246.74  4885.5  248.11  4914.1   247.7
    4948  247.22  4953.5  245.32  4984.6  242.52  4997.4  239.87  4997.7  239.37
  5001.4  239.87  5006.7  241.75  5039.7   246.9  5066.7  247.49  5082.7  247.74
  5440.6  255.24  5669.5  256.77  5773.1  258.65  5823.9  258.24  6335.8  266.99
#Mann= 7 ,-1 , 0
  3881.1     .05       0  4744.6     .07       0  4914.1     .05       0
  4997.4     .05       0  5001.4     .05       0  5066.7     .12       0
  5082.7     .05       0
Bank Sta=4997.4,5001.4
XS Rating Curve= 0 ,0
Exp/Cntr=0.3,0.1

Type RM Length L Ch R = 1 ,7209    ,588,588,588
BEGIN DESCRIPTION:
Mapping XS 2ce2e82c
END DESCRIPTION:
XS GIS Cut Line= 4
      2469569.76     13500455.42      2468326.73     13500052.65
      2468111.45      13500059.6      2466604.55     13500531.81
#Sta/Elev= 30
  3540.9  266.68  3566.9  267.12  3609.7  265.44  3808.7  263.09  3832.9  261.63
  4037.8  257.46  4261.3  252.29  4269.9  252.02  4498.3   247.1  4722.2  246.47
  4759.4  244.76  4838.9  246.02  4909.3  243.39  4949.3  244.72  4989.4  242.52
  5017.3  238.32  5017.6  237.82  5021.4  238.32  5039.4  240.03  5058.7  246.11
  5069.7  245.26  5096.8  247.87  5269.5  252.42  5439.6   253.6  5543.5   253.3
  5552.2  253.42  5636.2  253.15    5807  254.91  6166.2  260.45  6642.1  270.47
#Mann= 14 ,-1 , 0
  3540.9     .07       0  3609.7     .12       0  3832.9     .07       0
  4037.8     .12       0  4261.3     .07       0  4269.9     .12       0
  5017.3     .05       0  5021.4     .12       0  5439.6     .07       0
  5543.5     .05       0  5552.2     .07       0  5636.2     .05       0
    5807     .07       0  6166.2     .05       0
Bank Sta=5017.3,5021.4
XS Rating Curve= 0 ,0
Exp/Cntr=0.3,0.1

Type RM Length L Ch R = 1 ,6621    ,604,604,604
BEGIN DESCRIPTION:
Mapping XS fc58989c
END DESCRIPTION:
XS GIS Cut Line= 4
      2469173.96     13499788.77      2468430.89     13499552.65
      2468139.23     13499573.49      2466668.51     13500218.66
#Sta/Elev= 30
  4113.5  260.26  4230.3  258.72  4427.2  255.04  4467.3  253.53  4852.3  244.26
  4939.2  241.66  4977.9  236.98  4998.2  234.61  4998.5  234.11  5002.4  234.61
  5009.4  237.34  5029.4  240.93  5162.4  242.95  5268.7  246.28    5314  247.73
  5377.4  247.87  5486.2  247.01  5544.5   247.2  5553.2     247  5561.5  248.72
  5571.1  247.01  5594.2     246  5616.1  247.51  5663.4   247.2    5921  249.63
  6129.7  252.51    6442  258.23  6456.9  257.67  6495.7  259.57  6791.6  265.81
#Mann= 17 ,-1 , 0
  4113.5     .12       0  4230.3     .05       0  4467.3     .12       0
  4852.3     .05       0  4977.9     .12       0  4998.2     .05       0
  5002.4     .12       0  5162.4     .05       0  5268.7     .07       0
    5314     .05       0  5377.4     .07       0  5486.2     .12       0
  5544.5     .07       0  5663.4     .05       0    5921     .12       0
  6129.7     .07       0    6442     .05       0
Bank Sta=4998.2,5002.4
XS Rating Curve= 0 ,0
Exp/Cntr=0.3,0.1

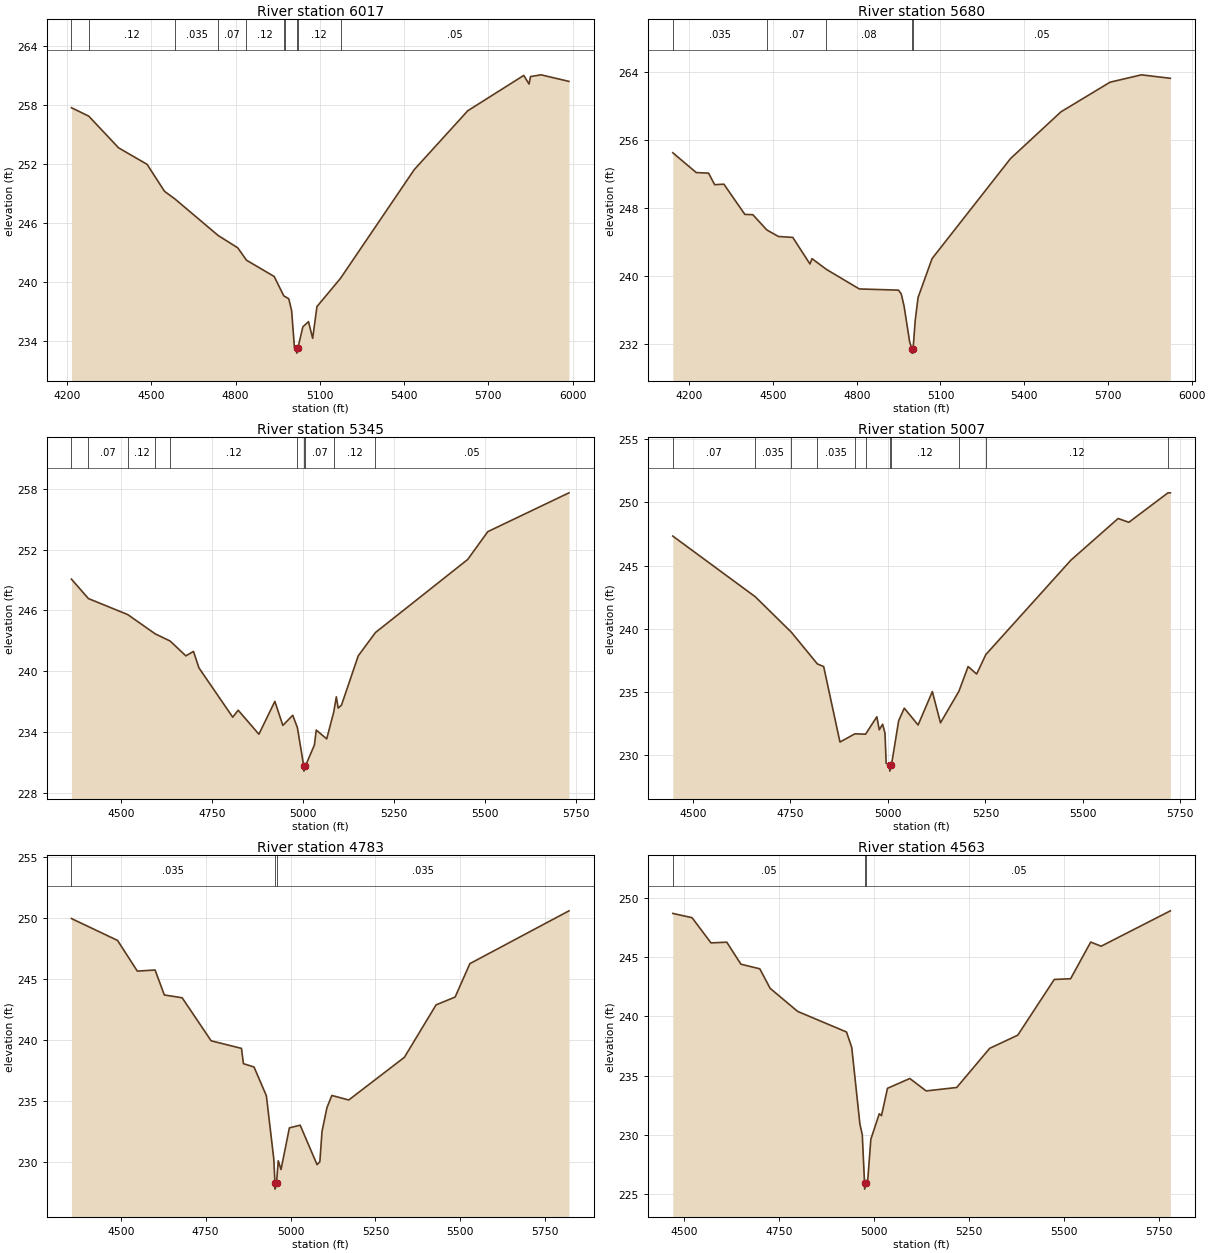
Type RM Length L Ch R = 1 ,6017    ,337,337,337
BEGIN DESCRIPTION:
Mapping XS e0be6fca
END DESCRIPTION:
XS GIS Cut Line= 4
      2468875.33     13499302.65      2468201.73      13499122.1
      2467923.95     13499101.26      2467148.12     13499281.37
#Sta/Elev= 30
    4215  257.76  4276.8   256.9    4383  253.67  4484.5  251.99  4546.6  249.24
  4583.4  248.47  4737.6  244.74  4807.6  243.48  4838.6  242.22  4937.3  240.56
  4971.6  238.58  4976.1  238.51  4989.3  238.29  4999.4  237.08  5009.4  233.33
  5017.3  233.25  5017.6  232.75  5021.5  233.25  5039.5  235.43  5059.5  235.96
  5074.4  234.26  5089.6  237.49  5173.7  240.38  5436.2  251.45  5626.9  257.45
  5826.3  261.05  5845.2  260.17  5850.3  260.93  5887.9  261.11  5987.4  260.44
#Mann= 10 ,-1 , 0
    4215     .05       0  4276.8     .12       0  4583.4    .035       0
  4737.6     .07       0  4838.6     .12       0  4971.6     .07       0
  4976.1     .12       0  5017.3     .05       0  5021.5     .12       0
  5173.7     .05       0
Bank Sta=5017.3,5021.5
XS Rating Curve= 0 ,0
Exp/Cntr=0.3,0.1

Type RM Length L Ch R = 1 ,5680    ,335,335,335
BEGIN DESCRIPTION:
Mapping XS a6e3a491
END DESCRIPTION:
XS GIS Cut Line= 4
      2468781.32     13499079.56      2468271.17     13498844.32
      2467882.28     13498816.54      2467062.82     13498955.43
#Sta/Elev= 30
  4140.9  254.51  4224.9  252.18    4269  252.11    4291  250.75    4324  250.81
  4399.1  247.25  4427.5  247.22  4477.8  245.42  4519.4  244.65  4570.8  244.54
  4632.4  241.41  4639.6  242.04  4691.5  240.77  4809.1  238.47  4949.5  238.33
  4959.5  237.88  4969.5  236.46  4989.6  232.24  4997.3  231.41  4997.6  230.91
  5001.5  230.91  5001.8  231.41  5009.6  234.79  5019.7  237.46  5069.8  242.04
  5350.5  253.81  5531.6  259.33  5707.5  262.82  5820.1  263.69  5923.7  263.28
#Mann= 5 ,-1 , 0
  4140.9    .035       0  4477.8     .07       0  4691.5     .08       0
  4997.3     .05       0  5001.8     .05       0
Bank Sta=4997.3,5001.8
XS Rating Curve= 0 ,0
Exp/Cntr=0.3,0.1

Type RM Length L Ch R = 1 ,5345    ,338,338,338
BEGIN DESCRIPTION:
Mapping XS 80501593
END DESCRIPTION:
XS GIS Cut Line= 3
      2468607.65     13498878.14      2468090.33     13498527.47
      2467358.87     13498402.67
#Sta/Elev= 30
    4364  249.09  4410.7  247.17  4518.8  245.59  4594.2  243.69  4635.3  242.98
  4678.4  241.52  4699.4  241.96  4714.3  240.34  4807.2  235.47  4822.1  236.16
  4879.1  233.79  4922.9  237.03  4944.9  234.66    4972  235.66  4984.8  234.45
  5002.3  230.65  5002.6  230.15  5006.8  230.65  5031.6  232.73  5036.7   234.2
  5065.4  233.33  5084.7  235.98  5091.8  237.48  5096.9  236.37    5106  236.66
    5152  241.52  5199.3  243.82  5452.8  251.03  5507.9  253.77    5731   257.6
#Mann= 10 ,-1 , 0
    4364    .035       0  4410.7     .07       0  4518.8     .12       0
  4594.2     .07       0  4635.3     .12       0  4984.8     .07       0
  5002.3     .05       0  5006.8     .07       0  5084.7     .12       0
  5199.3     .05       0
Bank Sta=5002.3,5006.8
XS Rating Curve= 0 ,0
Exp/Cntr=0.3,0.1

Type RM Length L Ch R = 1 ,5007    ,224,224,224
BEGIN DESCRIPTION:
Mapping XS 5c7534df
END DESCRIPTION:
XS GIS Cut Line= 3
      2468566.03     13498753.18      2468246.58     13498305.25
      2467680.58     13497850.37
#Sta/Elev= 30
  4448.1  247.33  4659.7  242.53  4752.4  239.72  4818.9  237.22  4835.1  237.01
  4876.9  231.04  4915.2  231.69  4942.5  231.66  4971.5  233.04  4977.7  232.01
  4986.3  232.45  4992.4  231.74  4995.4  229.36  5004.4  229.24  5004.7  228.74
    5009  229.24  5027.5  232.73  5041.9  233.72  5077.3  232.39  5113.9  235.03
  5134.7  232.56  5181.9  235.05  5205.6  237.01  5227.5  236.42  5251.1  237.96
  5469.1  245.42  5590.4  248.72  5617.9  248.42  5718.3  250.75  5724.4  250.75
#Mann= 11 ,-1 , 0
  4448.1     .07       0  4659.7    .035       0  4752.4     .07       0
  4818.9    .035       0  4915.2     .07       0  4942.5     .12       0
  5004.4     .05       0    5009     .12       0  5181.9     .07       0
  5251.1     .12       0  5718.3     .05       0
Bank Sta=5004.4,5009
XS Rating Curve= 0 ,0
Exp/Cntr=0.3,0.1

Type RM Length L Ch R = 1 ,4783    ,220,220,220
BEGIN DESCRIPTION:
Mapping XS 83827be0
END DESCRIPTION:
XS GIS Cut Line= 3
      2468670.18     13498666.34      2468336.85     13498114.28
      2467688.75     13497611.74
#Sta/Elev= 30
  4354.7  249.93  4490.5  248.14  4548.8  245.63  4601.1  245.72  4628.3  243.68
  4680.7  243.45  4766.1  239.93  4855.4  239.31  4861.2  238.06  4892.3  237.79
  4928.7  235.44  4950.5  230.28    4954   228.3  4954.3   227.8  4958.6   228.3
  4963.7  230.12  4971.8   229.4  4996.5  232.81  5028.2  233.03    5078   229.8
  5086.2  230.04  5092.5  232.51    5107  234.46  5121.5  235.46  5171.3  235.09
  5335.1  238.58  5428.4  242.87  5484.5  243.51  5527.9  246.24  5819.7  250.56
#Mann= 3 ,-1 , 0
  4354.7    .035       0    4954    .035       0  4958.6    .035       0
Bank Sta=4954,4958.6
XS Rating Curve= 0 ,0
Exp/Cntr=0.3,0.1

Type RM Length L Ch R = 1 ,4563    ,350,350,350
BEGIN DESCRIPTION:
Mapping XS 38aafd39
END DESCRIPTION:
XS GIS Cut Line= 3
      2468847.31      13498253.2       2468430.6     13497930.25
      2467753.56     13497537.91
#Sta/Elev= 30
  4470.1   248.7  4520.8  248.34  4570.6  246.21  4612.2  246.27  4649.4  244.41
  4699.1  244.02  4726.3  242.37  4798.7  240.42  4927.3  238.68  4941.1  237.38
  4962.6   230.9  4968.9  229.99  4974.8   225.9  4975.1   225.4  4979.4   225.9
  4983.4  226.24  4991.4  229.62  5013.6  231.77  5019.4  231.61  5035.2  233.92
    5094  234.75    5137   233.7  5217.4  233.99  5304.3   237.3  5378.1  238.41
  5474.2  243.12  5517.2  243.18  5570.1  246.28  5597.6  245.93  5779.8  248.92
#Mann= 3 ,-1 , 0
  4470.1     .05       0  4974.8     .05       0  4979.4     .05       0
Bank Sta=4974.8,4979.4
XS Rating Curve= 0 ,0
Exp/Cntr=0.3,0.1

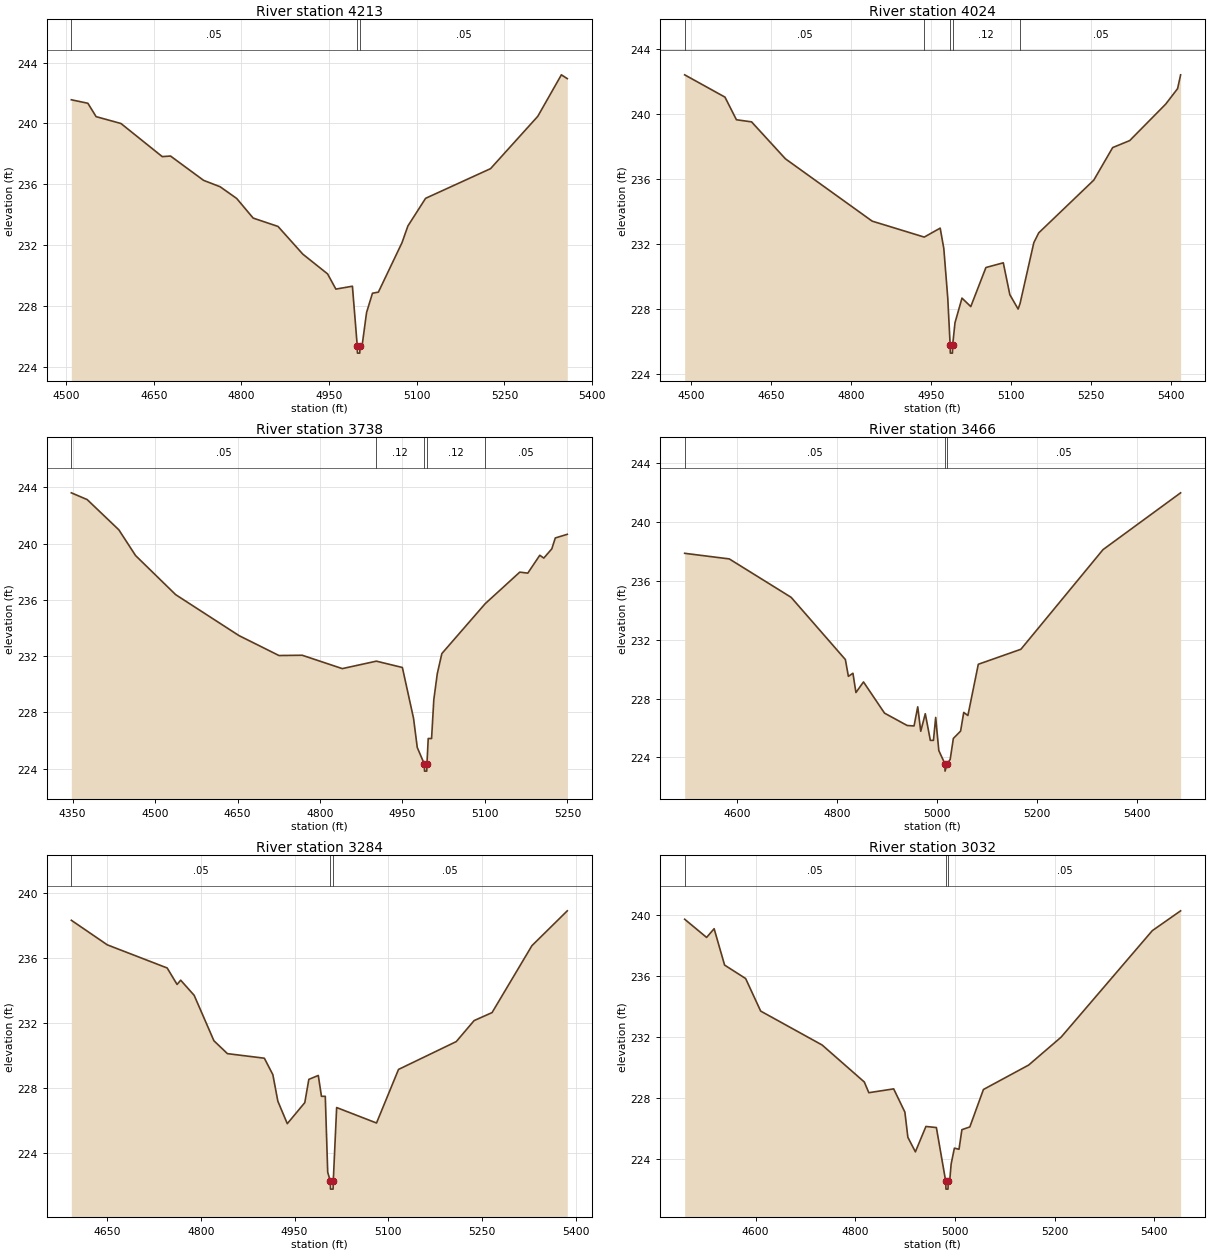
Type RM Length L Ch R = 1 ,4213    ,189,189,189
BEGIN DESCRIPTION:
TRIB 9 TO EIGHTEENMILE CREEK 8.0
END DESCRIPTION:
XS GIS Cut Line= 3
      2468725.01     13497975.01        2468375.       13497625.
      2468025.05     13497575.01
#Sta/Elev= 30
  4509.1  241.55  4537.4  241.32  4551.5  240.44    4594  239.99  4664.7  237.81
  4678.8  237.85  4735.4  236.25  4763.7  235.83    4792  235.06  4820.2  233.77
  4862.7  233.22  4905.1   231.4  4947.5   230.1  4961.7   229.1    4990  229.29
  4998.2  225.39  4998.6  224.89  5002.6  224.89  5002.9  225.39  5006.6  225.39
  5014.2  227.56  5024.3  228.83  5034.4   228.9  5074.8  232.15  5084.9  233.25
  5115.2  235.07  5226.3  237.02  5307.1  240.46  5347.5  243.19  5357.6  242.94
#Mann= 3 ,-1 , 0
  4509.1     .05       0  4998.2     .05       0  5002.9     .05       0
Bank Sta=4998.2,5002.9
XS Rating Curve= 0 ,0
Exp/Cntr=0.3,0.1

Type RM Length L Ch R = 1 ,4024    ,286,286,286
BEGIN DESCRIPTION:
Mapping XS ce20f8a9
END DESCRIPTION:
XS GIS Cut Line= 3
      2468868.08     13497898.97      2468520.88     13497520.53
      2468150.08     13497329.93
#Sta/Elev= 30
  4488.3   242.4  4563.9  241.03  4585.4  239.64  4613.8  239.51  4677.3  237.24
  4840.1  233.41  4937.8  232.43  4967.7  232.98  4974.5  231.73  4981.9   228.7
  4986.4   225.8  4986.7   225.3  4990.7   225.3  4991.1   225.8  4995.5  227.17
  5008.6  228.68  5025.1  228.16  5053.5  230.56  5086.1  230.85  5098.4  228.89
  5113.9  228.01  5117.5  228.34  5143.4  232.09  5152.6  232.69  5255.9  235.93
  5291.3  237.93  5323.3  238.36  5390.8   240.6  5413.1  241.55  5418.8   242.4
#Mann= 5 ,-1 , 0
  4488.3     .05       0  4937.8     .12       0  4986.4     .05       0
  4991.1     .12       0  5117.5     .05       0
Bank Sta=4986.4,4991.1
XS Rating Curve= 0 ,0
Exp/Cntr=0.3,0.1

Type RM Length L Ch R = 1 ,3738    ,272,272,272
BEGIN DESCRIPTION:
TRIB 9 TO EIGHTEENMILE CREEK 7.0
END DESCRIPTION:
XS GIS Cut Line= 3
        2468975.     13497825.01        2468625.       13497275.
      2468425.02     13497125.02
#Sta/Elev= 30
  4347.8  243.61  4376.6  243.13  4434.2  240.98  4464.6  239.15  4537.5  236.37
  4652.6  233.46  4725.4  232.04  4767.7  232.06  4840.6  231.11  4902.5  231.64
  4949.8  231.19  4970.1  227.58  4976.9   225.5  4989.8  224.32  4990.1  223.82
  4994.1  223.82  4994.5  224.32  4996.8  226.14  5002.9  226.14    5007  228.91
  5013.3  230.75  5021.6  232.18  5100.5  235.73  5163.3  237.97  5177.9   237.9
  5199.7  239.17    5207  238.97  5221.6  239.63  5227.9   240.4  5249.7  240.66
#Mann= 5 ,-1 , 0
  4347.8     .05       0  4902.5     .12       0  4989.8     .05       0
  4994.5     .12       0  5100.5     .05       0
Bank Sta=4989.8,4994.5
XS Rating Curve= 0 ,0
Exp/Cntr=0.3,0.1

Type RM Length L Ch R = 1 ,3466    ,182,182,182
BEGIN DESCRIPTION:
Mapping XS 11e4ab47
END DESCRIPTION:
XS GIS Cut Line= 3
      2469156.32     13497638.61      2468885.46     13497225.39
       2468489.8     13496923.44
#Sta/Elev= 30
  4495.8  237.87    4585  237.49  4708.7  234.88  4817.2  230.65  4823.2  229.51
  4832.3  229.72  4838.3  228.41  4853.4  229.13  4895.5  227.01  4940.8  226.17
  4954.5  226.14  4961.9  227.44  4967.9  225.78    4977  226.97  4987.1  225.16
  4993.3  225.16  4997.8  226.72    5004  224.47  5016.2  223.57  5016.5  223.07
  5020.9  223.57  5026.8  223.87  5033.1  225.29  5047.6  225.79  5053.9  227.06
  5062.2  226.85    5083  230.33  5168.2  231.35  5332.4  238.12  5487.6  241.98
#Mann= 3 ,-1 , 0
  4495.8     .05       0  5016.2     .05       0  5020.9     .05       0
Bank Sta=5016.2,5020.9
XS Rating Curve= 0 ,0
Exp/Cntr=0.3,0.1

Type RM Length L Ch R = 1 ,3284    ,252,252,252
BEGIN DESCRIPTION:
TRIB 9 TO EIGHTEENMILE CREEK 6.0
END DESCRIPTION:
XS GIS Cut Line= 3
      2469225.02     13497475.04        2469025.       13497125.
      2468724.98     13496874.98
#Sta/Elev= 30
  4592.8  238.31  4650.4   236.8  4746.2  235.38    4762  234.37  4767.8  234.63
  4789.4   233.7    4821  230.91  4842.6  230.12  4901.7  229.84  4915.3  228.83
  4923.3   227.2  4938.4  225.82  4966.4  227.11  4972.9  228.54    4988  228.78
  4993.1   227.5  4999.2   227.5  5003.1  222.84  5007.2   222.3  5007.6   221.8
  5011.7   221.8    5012   222.3  5017.4  226.81  5081.2  225.86  5116.4  229.15
  5208.8  230.86  5237.4  232.15  5266.1  232.64  5329.9  236.75  5386.5  238.89
#Mann= 3 ,-1 , 0
  4592.8     .05       0  5007.2     .05       0    5012     .05       0
Bank Sta=5007.2,5012
XS Rating Curve= 0 ,0
Exp/Cntr=0.3,0.1

Type RM Length L Ch R = 1 ,3032    ,196,196,196
BEGIN DESCRIPTION:
Mapping XS 9c955d17
END DESCRIPTION:
XS GIS Cut Line= 3
      2469454.92     13497395.54      2469163.24     13496951.08
      2468760.49     13496721.93
#Sta/Elev= 30
  4457.9  239.71  4501.9  238.52    4517  239.09    4538  236.71  4580.2  235.83
  4610.4   233.7  4733.7  231.48  4818.3  229.06  4827.4  228.36  4877.2  228.61
  4899.7  227.09  4905.7  225.44  4920.8  224.49  4941.9  226.15  4962.9  226.08
  4981.7  222.55  4982.1  222.05  4986.2  222.05  4986.6  222.55  4989.5  222.55
  4992.5  223.69    4999  224.73  5008.3  224.66  5014.1  225.94    5030  226.12
  5057.3  228.57  5148.1  230.17    5213  231.99    5396  238.96  5452.9  240.26
#Mann= 3 ,-1 , 0
  4457.9     .05       0  4981.7     .05       0  4986.6     .05       0
Bank Sta=4981.7,4986.6
XS Rating Curve= 0 ,0
Exp/Cntr=0.3,0.1