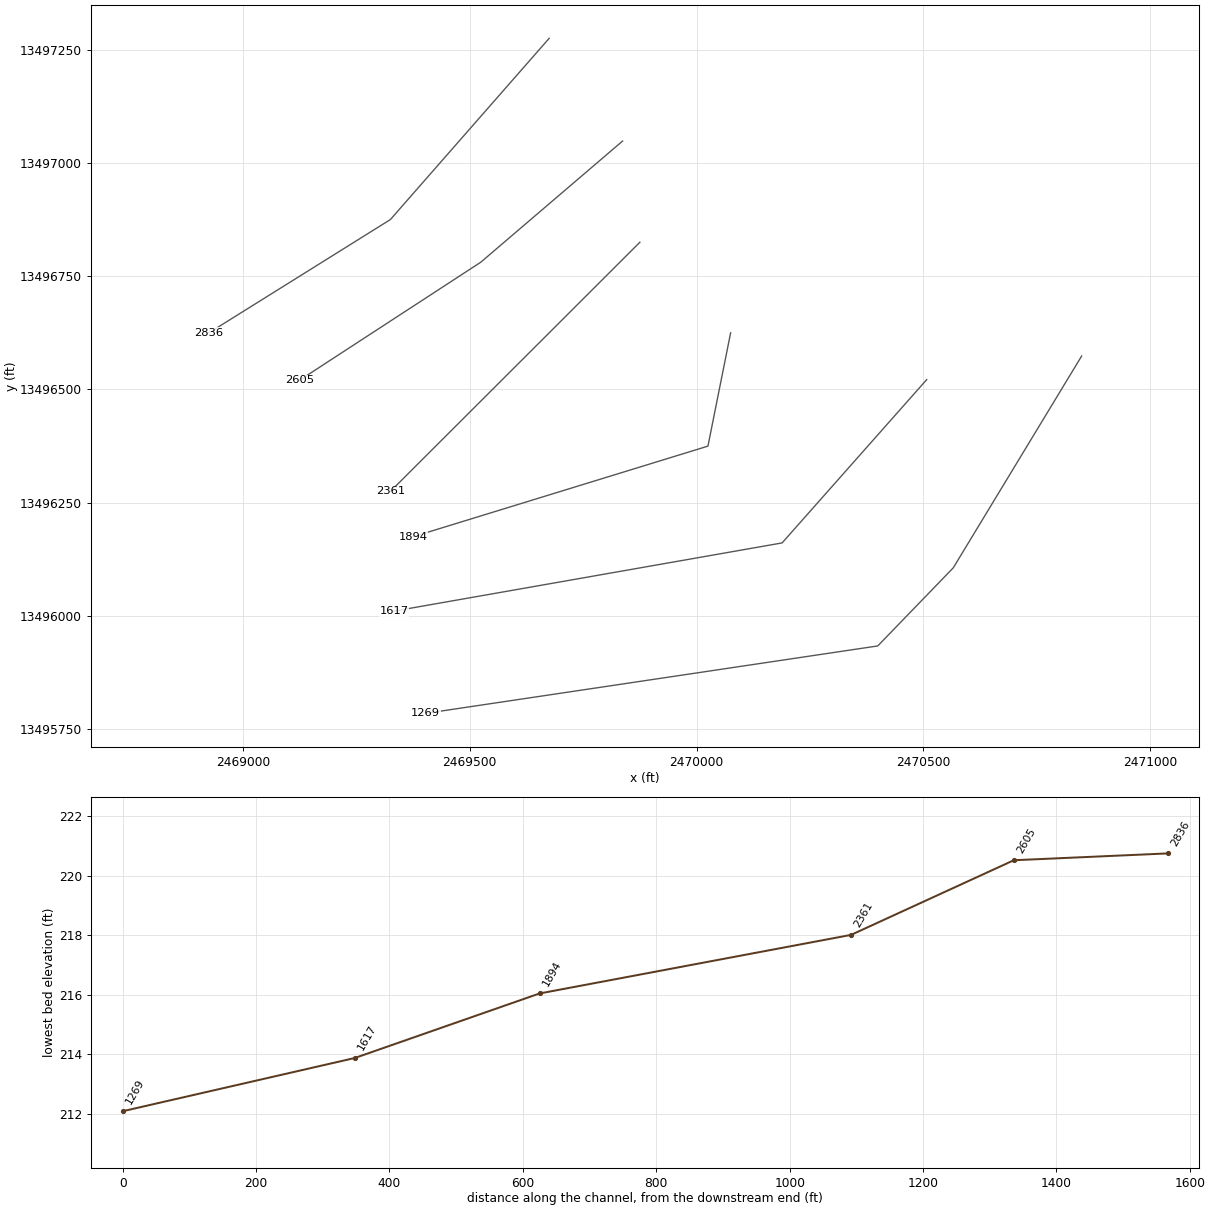
HEC-RAS study TRIB 9 TO EIGHTEENMILE CREEK.prj: TRIB 9 TO EIGHTEENMILE CREEK Base Level Engineering

--- TRIB 9 TO EIGHTEENMILE CREEK.g01 (geometry) --- (continued)

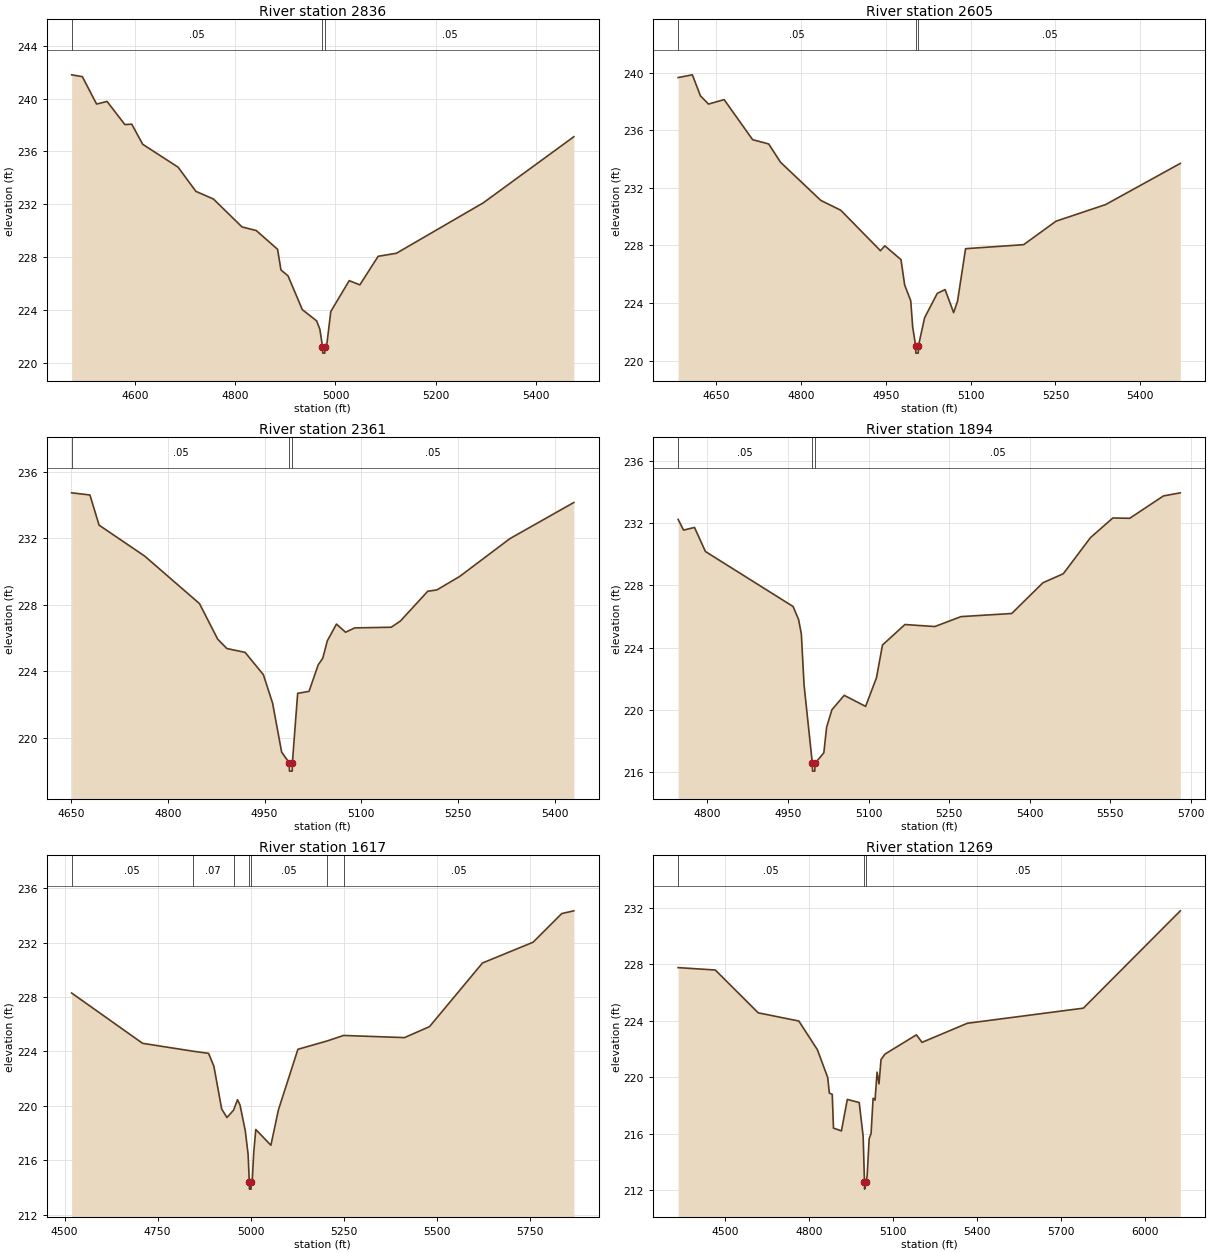
Type RM Length L Ch R = 1 ,2836    ,231,231,231
BEGIN DESCRIPTION:
TRIB 9 TO EIGHTEENMILE CREEK 5.0
END DESCRIPTION:
XS GIS Cut Line= 3
        2469675.       13497275.        2469325.       13496875.
        2468925.       13496625.
#Sta/Elev= 30
    4473  241.79  4494.4  241.65  4522.8  239.58  4543.7  239.78  4579.3  238.03
  4593.1  238.06  4614.9  236.54  4685.6  234.81  4721.2  232.98  4756.3   232.4
  4813.3  230.29  4841.7  230.02  4884.4   228.6  4891.1  227.04  4905.3  226.59
  4933.8  224.04  4962.3  223.19  4968.9  222.55  4974.1  221.25  4974.5  220.75
  4978.6  220.75    4979  221.25  4983.1  221.52  4990.7   223.9  5027.5  226.23
  5048.7  225.91  5085.3  228.07  5121.8   228.3  5295.2  232.11  5476.2  237.11
#Mann= 3 ,-1 , 0
    4473     .05       0  4974.1     .05       0    4979     .05       0
Bank Sta=4974.1,4979
XS Rating Curve= 0 ,0
Exp/Cntr=0.3,0.1

Type RM Length L Ch R = 1 ,2605    ,244,244,244
BEGIN DESCRIPTION:
Mapping XS f5c8862f
END DESCRIPTION:
XS GIS Cut Line= 3
      2469836.89     13497048.34      2469524.35     13496780.94
      2469125.07     13496520.54
#Sta/Elev= 30
  4582.7  239.65  4607.9  239.84  4622.2  238.38  4636.5  237.81  4664.1  238.12
  4714.4  235.34  4742.9  235.04  4763.8  233.77  4835.1  231.12  4870.3  230.44
  4940.5  227.63  4948.2  227.97  4976.8  227.01  4983.3  225.25    4994  224.16
  4997.5  222.33  5002.7  221.02  5003.1  220.52  5007.3  220.52  5007.6  221.02
  5018.6  222.98    5041  224.67  5054.8  224.93  5069.9  223.33  5076.8  224.13
    5091  227.77  5193.7  228.05    5251  229.68  5338.5  230.83  5470.7  233.69
#Mann= 3 ,-1 , 0
  4582.7     .05       0  5002.7     .05       0  5007.6     .05       0
Bank Sta=5002.7,5007.6
XS Rating Curve= 0 ,0
Exp/Cntr=0.3,0.1

Type RM Length L Ch R = 1 ,2361    ,467,467,467
BEGIN DESCRIPTION:
TRIB 9 TO EIGHTEENMILE CREEK 4.0
END DESCRIPTION:
XS GIS Cut Line= 3
      2469875.03     13496825.03        2469625.       13496575.
      2469324.97     13496274.97
#Sta/Elev= 30
  4651.2  234.72  4679.5  234.59  4693.7  232.78  4764.4  230.92  4849.2  228.07
  4877.5  225.93  4891.7  225.37  4919.9  225.14  4948.2   223.8  4962.4   222.1
  4976.5  219.15  4988.2  218.51  4988.6  218.01  4992.8  218.01  4993.1  218.51
  5001.3  222.68  5018.9   222.8  5033.1  224.39  5040.2  224.79  5047.2  225.83
  5061.4  226.84  5075.5  226.35  5089.7  226.61  5146.2  226.65  5160.4  227.02
  5202.8  228.81  5216.9  228.89  5252.3   229.7  5330.1  231.97  5429.1  234.14
#Mann= 3 ,-1 , 0
  4651.2     .05       0  4988.2     .05       0  4993.1     .05       0
Bank Sta=4988.2,4993.1
XS Rating Curve= 0 ,0
Exp/Cntr=0.3,0.1

Type RM Length L Ch R = 1 ,1894    ,277,277,277
BEGIN DESCRIPTION:
TRIB 9 TO EIGHTEENMILE CREEK 3.0
END DESCRIPTION:
XS GIS Cut Line= 3
      2470074.99     13496624.96        2470025.       13496375.
      2469374.98     13496174.99
#Sta/Elev= 30
  4745.4  232.25  4755.6  231.56  4775.9  231.73  4796.3  230.18  4959.5  226.64
  4969.7   225.8  4974.8  224.88  4979.9  221.59  4995.3  216.54  4995.7  216.04
  4999.9  216.04  5000.2  216.54  5016.7  217.22  5021.9  218.87  5031.7  219.99
  5054.6  220.92  5094.5  220.21  5114.7  222.05  5125.9  224.16  5167.7  225.48
  5223.3  225.35  5272.3  225.99  5366.5  226.19  5424.7  228.17  5462.6  228.75
    5513  231.07  5554.8  232.34  5586.2  232.32    5649  233.76  5680.4  233.96
#Mann= 3 ,-1 , 0
  4745.4     .05       0  4995.3     .05       0  5000.2     .05       0
Bank Sta=4995.3,5000.2
XS Rating Curve= 0 ,0
Exp/Cntr=0.3,0.1

Type RM Length L Ch R = 1 ,1617    ,348,348,348
BEGIN DESCRIPTION:
TRIB 9 TO EIGHTEENMILE CREEK 2.0
END DESCRIPTION:
XS GIS Cut Line= 3
      2470507.24     13496521.83      2470188.46     13496161.37
       2469333.1     13496010.87
#Sta/Elev= 30
  4518.8   228.3  4709.5   224.6  4844.8  224.02  4886.8  223.86  4901.1  222.91
    4922  219.77  4936.2  219.14  4953.9  219.68  4964.6  220.45  4971.3  220.06
  4985.5  218.16  4993.1  216.42  4996.3  214.37  4996.7  213.87  5000.9  213.87
  5001.3  214.37  5003.9  214.37  5008.2  216.56  5013.7  218.26  5054.3   217.1
  5074.6  219.71  5126.9  224.16  5206.1  224.78  5249.7  225.18  5413.3  225.02
  5480.7  225.83  5622.9  230.51    5759  232.04  5836.1  234.15  5868.5  234.35
#Mann= 7 ,-1 , 0
  4518.8     .05       0  4844.8     .07       0  4953.9     .05       0
  4996.3     .05       0  5001.3     .05       0  5206.1     .07       0
  5249.7     .05       0
Bank Sta=4996.3,5001.3
XS Rating Curve= 0 ,0
Exp/Cntr=0.3,0.1

Type RM Length L Ch R = 1 ,1269    ,0,0,0
BEGIN DESCRIPTION:
Mapping XS 6e1cdecf
END DESCRIPTION:
XS GIS Cut Line= 4
      2470848.72     13496573.86      2470565.71     13496106.35
      2470399.31     13495934.01      2469402.52     13495785.17
#Sta/Elev= 30
  4331.5  227.76  4464.4  227.59  4617.6  224.56  4762.7  223.98    4829  221.95
  4865.9  219.98  4871.7  218.88  4882.1  218.79  4886.5   216.4  4914.8   216.2
  4935.9  218.43  4978.4  218.21  4992.5  215.81  4997.2  212.58  4997.6  212.08
  5002.2  212.58  5006.7  213.01  5013.9  215.64  5020.8  216.02    5028  218.51
    5035  218.38  5042.2  220.36  5049.1  219.53  5056.3  221.25  5070.5  221.64
  5182.6     223  5202.8  222.47  5364.6  223.82  5779.1  224.89  6125.4  231.78
#Mann= 3 ,-1 , 0
  4331.5     .05       0  4997.2     .05       0  5002.2     .05       0
Bank Sta=4997.2,5002.2
XS Rating Curve= 0 ,0
Exp/Cntr=0.3,0.1

Chan Stop Cuts=-1
Use User Specified Reach Order=0
Composite Channel Slope=5