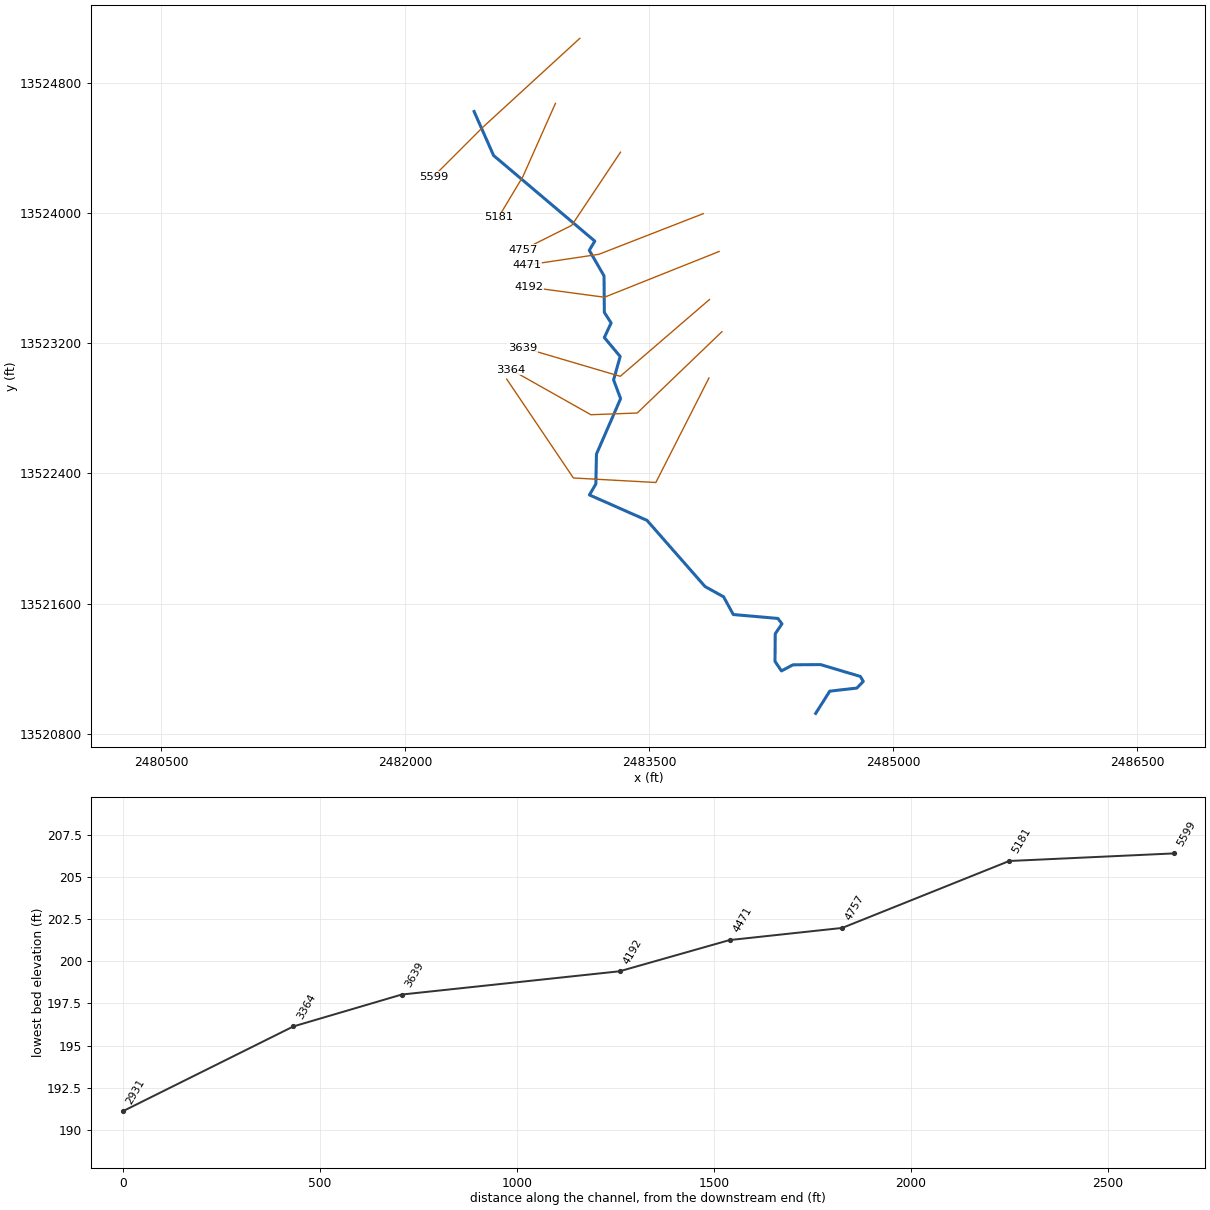
--- TRIB 9 TO FIFTEENMILE CREEK.prj (project) ---

Proj Title=TRIB 9 TO FIFTEENMILE CREEK Base Level Engineering
Current Plan=p01
Default Exp/Contr=0.3,0.1
English Units
Geom File=g01
Flow File=f01
Plan File=p01
BEGIN DESCRIPTION:
TRIB 9 TO FIFTEENMILE CREEK
END DESCRIPTION:

--- TRIB 9 TO FIFTEENMILE CREEK.p01 (plan) ---

Plan Title=Multiple Run
Short Identifier=Multiple
Geom File=g01
Flow File=f01
Subcritical Flow
K Sum by GR= 0
Std Step Tol= 0.01
Critical Tol= 0.01
Num of Std Step Trials= 20
Max Error Tol= 0.3
Flow Tol Ratio= 0.001
Split Flow NTrial= 30
Split Flow Tol= 0.02
Split Flow Ratio= 0.02
Log Output Level= 0
Friction Slope Method= 1
Unsteady Friction Slope Method= 2
Unsteady Bridges Friction Slope Method= 1
Parabolic Critical Depth
Global Vel Dist=  1 , 1 , 1
Global Log Level= 0
CheckData=True
Encroach Param= -1, 0, 0, 0
BEGIN DESCRIPTION:
Multiple Run
END DESCRIPTION:

--- TRIB 9 TO FIFTEENMILE CREEK.f01 (steady flow) ---

Flow Title=Multiple
Number of Profiles=7
Profile Names=10-year,25-year,50-year,1pct_min,100-year,1pct_plu,500-year
River Rch & RM= TRIB 9 TO FIFTEE,Reach-1,5599
     496     784    1040     668    1333    2660    2167
Boundary for River Rch & Prof#=TRIB 9 TO FIFTEE,Reach-1,1
Up Type=0
Dn Type=3
Dn Slope=0.005
Boundary for River Rch & Prof#=TRIB 9 TO FIFTEE,Reach-1,2
Up Type=0
Dn Type=3
Dn Slope=0.005
Boundary for River Rch & Prof#=TRIB 9 TO FIFTEE,Reach-1,3
Up Type=0
Dn Type=3
Dn Slope=0.005
Boundary for River Rch & Prof#=TRIB 9 TO FIFTEE,Reach-1,4
Up Type=0
Dn Type=3
Dn Slope=0.005
Boundary for River Rch & Prof#=TRIB 9 TO FIFTEE,Reach-1,5
Up Type=0
Dn Type=3
Dn Slope=0.005
Boundary for River Rch & Prof#=TRIB 9 TO FIFTEE,Reach-1,6
Up Type=0
Dn Type=3
Dn Slope=0.005
Boundary for River Rch & Prof#=TRIB 9 TO FIFTEE,Reach-1,7
Up Type=0
Dn Type=3
Dn Slope=0.005

--- TRIB 9 TO FIFTEENMILE CREEK.g01 (geometry) ---

Geom Title=Existing Conditions

River Reach=TRIB 9 TO FIFTEE,Reach-1
Reach XY= 30
      2482425.00     13524625.00      2482544.77     13524354.87
      2483167.01     13523828.35      2483133.25     13523771.77
      2483223.80     13523614.50      2483225.66     13523390.16
      2483267.41     13523324.99      2483225.65     13523235.64
      2483323.02     13523119.10      2483282.57     13522975.00
      2483325.69     13522859.94      2483177.24     13522519.07
      2483173.61     13522335.43      2483134.01     13522267.98
      2483488.22     13522111.38      2483844.84     13521704.62
      2483958.50     13521642.04      2484018.52     13521532.69
      2484292.66     13521508.59      2484317.79     13521475.35
      2484276.39     13521414.57      2484274.95     13521244.76
      2484314.56     13521185.94      2484385.43     13521223.61
      2484554.97     13521224.93      2484799.55     13521152.09
      2484817.62     13521121.59      2484778.03     13521080.48
      2484611.66     13521061.65      2484525.00     13520925.00

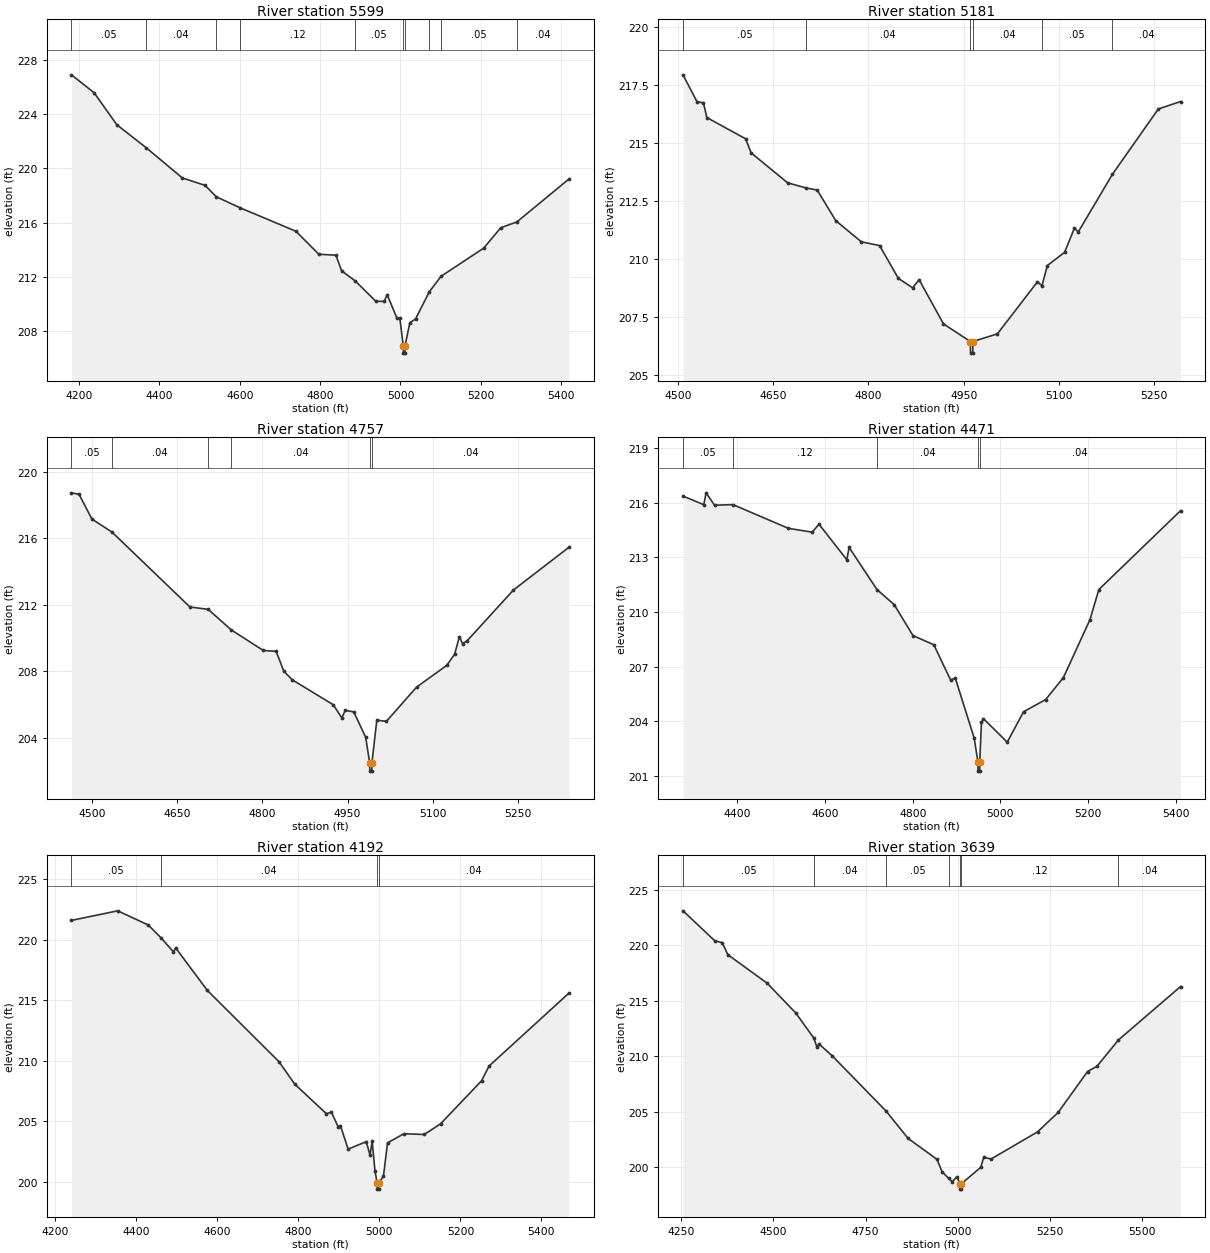
Type RM Length L Ch R = 1,5599,418,418,418
BEGIN DESCRIPTION:
TRIB 9 TO FIFTEENMILE CREEK 9.0
END DESCRIPTION:
XS GIS Cut Line= 3
      2483075.04     13525075.03      2482475.00     13524525.00
      2482174.97     13524224.97
#Sta/Elev= 30
  4181.1  226.89  4237.6  225.57  4294.3  223.21  4366.9  221.53  4457.1  219.30
  4513.8  218.75  4541.7  217.91  4601.0  217.10  4740.1  215.37  4796.8  213.68
  4839.4  213.61  4853.6  212.46  4887.3  211.72  4938.7  210.22  4959.6  210.21
  4967.0  210.70  4991.7  208.95  4998.6  208.95  5007.2  206.90  5007.5  206.40
  5011.0  206.40  5011.2  206.90  5023.4  208.64  5037.5  208.91  5072.1  210.93
  5101.2  212.06  5207.2  214.13  5249.6  215.63  5289.8  216.06  5419.4  219.22
#Mann=10,-1,0
  4181.1    0.05       0  4366.9    0.04       0  4541.7    0.05       0
  4601.0    0.12       0  4887.3    0.05       0  5007.2    0.05       0
  5011.2    0.05       0  5072.1    0.04       0  5101.2    0.05       0
  5289.8    0.04       0
Bank Sta=5007.2,5011.2
Exp/Cntr=0.3,0.1

Type RM Length L Ch R = 1,5181,424,424,424
BEGIN DESCRIPTION:
TRIB 9 TO FIFTEENMILE CREEK 8.0
END DESCRIPTION:
XS GIS Cut Line= 3
      2482925.01     13524675.02      2482725.00     13524225.00
      2482575.01     13523975.01
#Sta/Elev= 30
  4507.8  217.93  4529.7  216.78  4540.0  216.72  4545.4  216.09  4606.3  215.18
  4615.2  214.57  4672.7  213.28  4701.7  213.06  4719.2  212.97  4748.6  211.65
  4788.9  210.74  4817.6  210.58  4847.1  209.17  4869.6  208.76  4879.9  209.11
  4918.2  207.21  4960.6  206.45  4960.9  205.95  4964.4  205.95  4964.6  206.45
  5003.2  206.78  5066.3  209.02  5073.5  208.85  5081.9  209.72  5109.1  210.29
  5124.7  211.34  5130.5  211.16  5184.5  213.65  5256.8  216.46  5291.8  216.78
#Mann=6,-1,0
  4507.8    0.05       0  4701.7    0.04       0  4960.6    0.04       0
  4964.6    0.04       0  5073.5    0.05       0  5184.5    0.04       0
Bank Sta=4960.6,4964.6
Exp/Cntr=0.3,0.1

Type RM Length L Ch R = 1,4757,286,286,286
BEGIN DESCRIPTION:
TRIB 9 TO FIFTEENMILE CREEK 7.0
END DESCRIPTION:
XS GIS Cut Line= 3
      2483325.01     13524375.02      2483025.00     13523925.00
      2482724.97     13523774.98
#Sta/Elev= 30
  4463.6  218.75  4477.1  218.66  4499.7  217.17  4535.2  216.38  4672.4  211.87
  4704.5  211.73  4745.1  210.49  4801.6  209.25  4824.2  209.20  4837.7  208.00
  4852.7  207.48  4924.8  205.98  4939.9  205.19  4945.9  205.64  4960.9  205.55
  4981.9  204.02  4988.9  202.48  4989.2  201.98  4992.7  201.98  4992.9  202.48
  5001.5  205.05  5018.4  204.98  5071.5  207.04  5124.6  208.35  5138.6  209.03
  5147.0  210.09  5152.6  209.66  5161.0  209.85  5242.0  212.89  5339.9  215.47
#Mann=6,-1,0
  4463.6    0.05       0  4535.2    0.04       0  4704.5    0.05       0
  4745.1    0.04       0  4988.9    0.04       0  4992.9    0.04       0
Bank Sta=4988.9,4992.9
Exp/Cntr=0.3,0.1

Type RM Length L Ch R = 1,4471,279,279,279
BEGIN DESCRIPTION:
Mapping XS 8576cbcf
END DESCRIPTION:
XS GIS Cut Line= 3
      2483834.05     13523997.21      2483191.66     13523747.19
      2482750.70     13523681.22
#Sta/Elev= 30
  4275.8  216.36  4323.2  215.89  4328.5  216.54  4347.7  215.86  4390.1  215.89
  4516.2  214.59  4570.6  214.38  4586.0  214.82  4649.5  212.87  4654.9  213.54
  4718.4  211.23  4757.7  210.40  4800.6  208.70  4848.0  208.20  4886.4  206.26
  4897.0  206.37  4940.1  203.08  4948.8  201.76  4949.1  201.26  4952.6  201.26
  4952.8  201.76  4956.8  203.94  4961.3  204.14  5015.6  202.85  5052.8  204.52
  5103.3  205.19  5143.8  206.40  5204.4  209.58  5224.6  211.23  5411.0  215.56
#Mann=5,-1,0
  4275.8    0.05       0  4390.1    0.12       0  4718.4    0.04       0
  4948.8    0.04       0  4952.8    0.04       0
Bank Sta=4948.8,4952.8
Exp/Cntr=0.3,0.1

Type RM Length L Ch R = 1,4192,553,553,553
BEGIN DESCRIPTION:
Mapping XS 68558717
END DESCRIPTION:
XS GIS Cut Line= 3
      2483931.20     13523764.54      2483226.38     13523483.30
      2482761.12     13523545.80
#Sta/Elev= 30
  4239.7  221.59  4354.0  222.38  4429.4  221.21  4461.0  220.15  4491.7  218.99
  4497.1  219.32  4575.3  215.81  4752.4  209.92  4790.9  208.08  4869.0  205.64
  4881.6  205.76  4898.7  204.52  4904.0  204.63  4922.9  202.71  4967.7  203.33
  4976.8  202.22  4982.2  203.36  4989.3  200.87  4994.6  199.91  4994.9  199.41
  4998.4  199.41  4998.6  199.91  5010.0  200.48  5020.1  203.23  5060.5  203.98
  5110.9  203.92  5151.3  204.81  5252.2  208.35  5270.8  209.57  5468.0  215.59
#Mann=4,-1,0
  4239.7    0.05       0  4461.0    0.04       0  4994.6    0.04       0
  4998.6    0.04       0
Bank Sta=4994.6,4998.6
Exp/Cntr=0.3,0.1

Type RM Length L Ch R = 1,3639,275,275,275
BEGIN DESCRIPTION:
Mapping XS 7975620e
END DESCRIPTION:
XS GIS Cut Line= 3
      2483872.20     13523469.41      2483323.60     13522997.19
      2482722.90     13523174.28
#Sta/Elev= 30
  4254.6  223.09  4341.2  220.38  4361.0  220.23  4376.3  219.14  4482.7  216.58
  4560.6  213.89  4609.6  211.63  4617.7  210.85  4624.3  211.08  4659.9  210.02
  4806.2  205.04  4865.6  202.59  4943.5  200.72  4957.8  199.58  4975.2  199.01
  4985.3  198.70  4997.8  199.14  5006.3  198.53  5006.5  198.03  5010.0  198.03
  5010.3  198.53  5062.4  199.99  5070.8  200.90  5090.5  200.74  5216.8  203.19
  5272.7  204.94  5352.3  208.62  5377.9  209.09  5436.1  211.46  5604.7  216.27
#Mann=7,-1,0
  4254.6    0.05       0  4609.6    0.04       0  4806.2    0.05       0
  4975.2    0.12       0  5006.3    0.05       0  5010.3    0.12       0
  5436.1    0.04       0
Bank Sta=5006.3,5010.3
Exp/Cntr=0.3,0.1

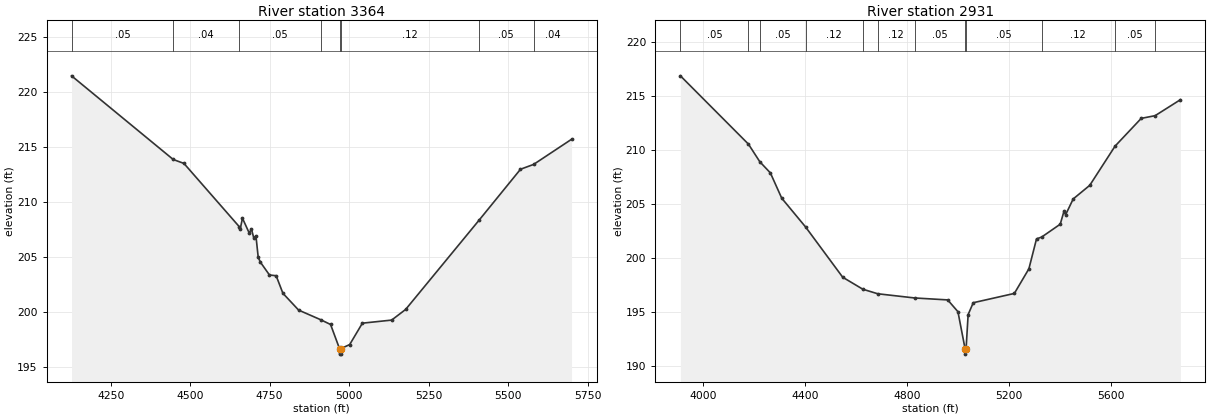
Type RM Length L Ch R = 1,3364,433,433,433
BEGIN DESCRIPTION:
Mapping XS eedc96b5
END DESCRIPTION:
XS GIS Cut Line= 4
      2483948.61     13523271.51      2483427.77     13522771.50
      2483143.05     13522761.08      2482650.02     13523038.84
#Sta/Elev= 30
  4126.8  221.49  4446.6  213.87  4480.4  213.51  4654.3  207.75  4657.4  207.53
  4664.4  208.52  4685.7  207.17  4692.7  207.54  4699.9  206.73  4706.8  206.92
  4714.0  204.95  4721.0  204.51  4749.3  203.35  4770.4  203.28  4791.7  201.68
  4841.1  200.15  4910.0  199.28  4941.6  198.84  4969.7  196.64  4969.9  196.14
  4973.4  196.14  4973.7  196.64  5001.7  197.01  5041.7  198.96  5133.7  199.24
  5177.7  200.21  5408.4  208.33  5539.0  212.98  5580.2  213.42  5699.6  215.71
#Mann=8,-1,0
  4126.8    0.05       0  4446.6    0.04       0  4654.3    0.05       0
  4910.0    0.12       0  4969.7    0.05       0  4973.7    0.12       0
  5408.4    0.05       0  5580.2    0.04       0
Bank Sta=4969.7,4973.7
Exp/Cntr=0.3,0.1

Type RM Length L Ch R = 1,2931,0,0,0
BEGIN DESCRIPTION:
TRIB 9 TO FIFTEENMILE CREEK 3.0
END DESCRIPTION:
XS GIS Cut Line= 4
      2483868.76     13522986.81      2483542.35     13522344.41
      2483035.41     13522372.19      2482625.71     13522979.80
#Sta/Elev= 30
  3911.9  216.88  4178.6  210.56  4223.5  208.92  4264.8  207.89  4309.3  205.55
  4403.0  202.88  4548.5  198.23  4627.4  197.12  4685.7  196.70  4830.8  196.31
  4960.3  196.13  5000.4  195.04  5028.4  191.61  5028.7  191.11  5032.4  191.61
  5040.4  194.77  5060.5  195.87  5221.7  196.73  5278.7  199.01  5308.6  201.78
  5328.8  201.95  5401.6  203.14  5416.5  204.35  5422.6  204.01  5452.5  205.48
  5517.4  206.74  5616.7  210.37  5719.3  212.94  5773.8  213.19  5873.0  214.67
#Mann=12,-1,0
  3911.9    0.05       0  4178.6    0.04       0  4223.5    0.05       0
  4403.0    0.12       0  4627.4    0.05       0  4685.7    0.12       0
  4830.8    0.05       0  5028.4    0.05       0  5032.4    0.05       0
  5328.8    0.12       0  5616.7    0.05       0  5773.8    0.04       0
Bank Sta=5028.4,5032.4
Exp/Cntr=0.3,0.1

Chan Stop Cuts=-1