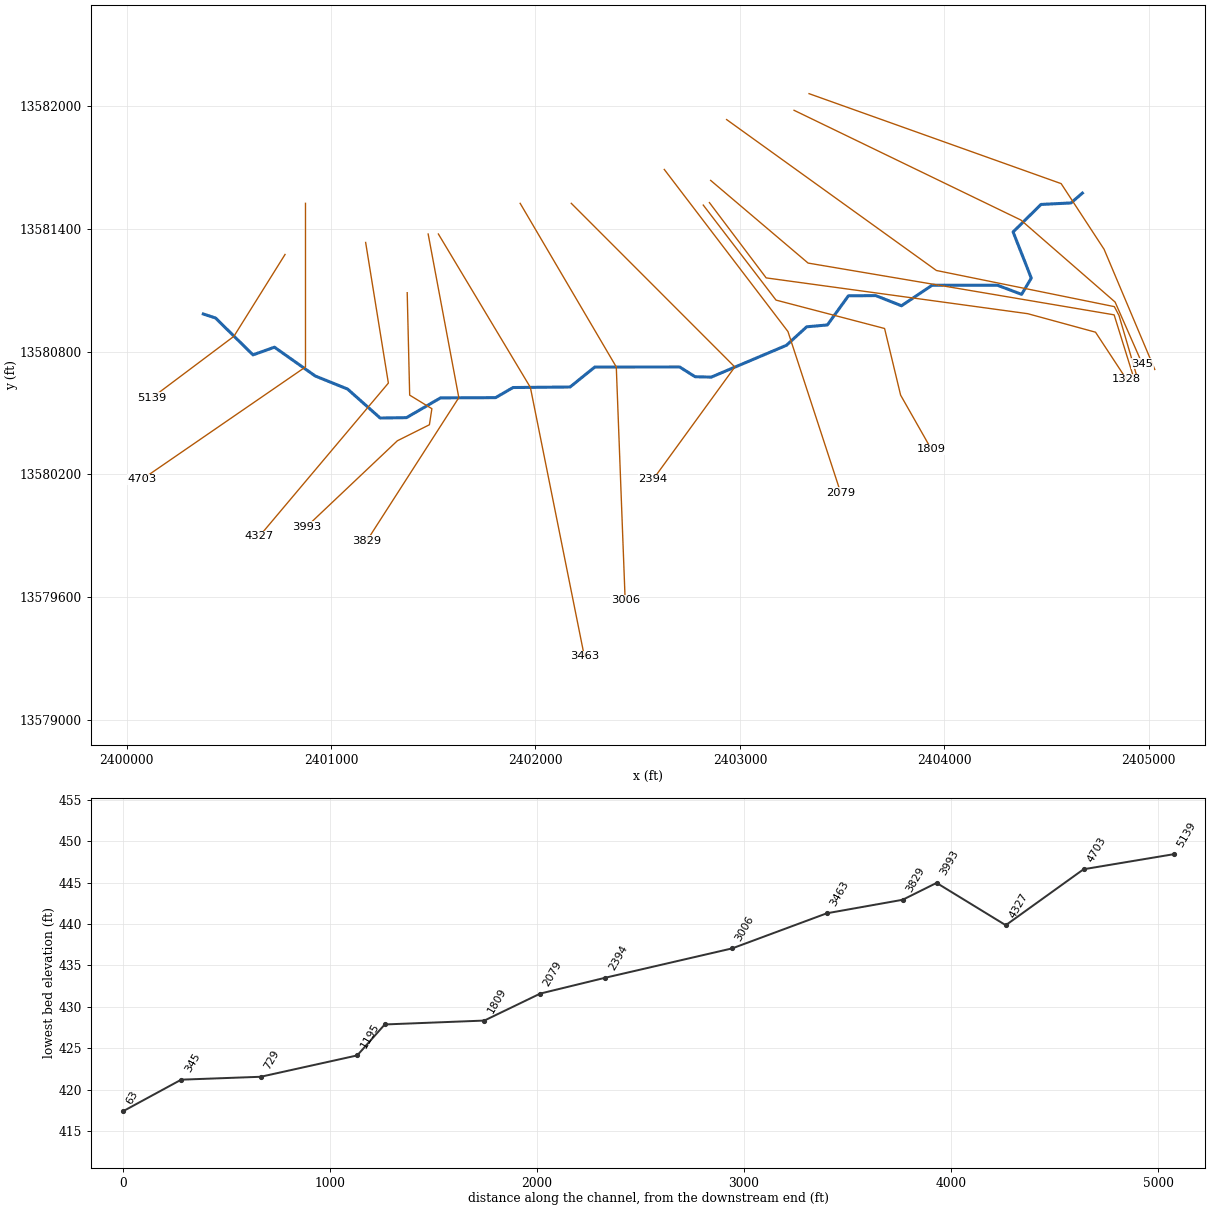
--- TRIB 9 TO SALT CREEK.prj (project) ---

Proj Title=TRIB 9 TO SALT CREEK Base Level Engineering
Current Plan=p01
Default Exp/Contr=0.3,0.1
English Units
Geom File=g01
Flow File=f01
Plan File=p01
BEGIN DESCRIPTION:
TRIB 9 TO SALT CREEK
END DESCRIPTION:

--- TRIB 9 TO SALT CREEK.p01 (plan) ---

Plan Title=Multiple Run
Short Identifier=Multiple
Geom File=g01
Flow File=f01
Subcritical Flow
K Sum by GR= 0
Std Step Tol= 0.01
Critical Tol= 0.01
Num of Std Step Trials= 20
Max Error Tol= 0.3
Flow Tol Ratio= 0.001
Split Flow NTrial= 30
Split Flow Tol= 0.02
Split Flow Ratio= 0.02
Log Output Level= 0
Friction Slope Method= 1
Unsteady Friction Slope Method= 2
Unsteady Bridges Friction Slope Method= 1
Parabolic Critical Depth
Global Vel Dist=  1 , 1 , 1
Global Log Level= 0
CheckData=True
Encroach Param= -1, 0, 0, 0
BEGIN DESCRIPTION:
Multiple Run
END DESCRIPTION:

--- TRIB 9 TO SALT CREEK.f01 (steady flow) ---

Flow Title=Multiple
Number of Profiles=7
Profile Names=10-year,25-year,50-year,1pct_min,100-year,1pct_plu,500-year
River Rch & RM= TRIB 9 TO SALT C,Reach-1,5139
     975    1643    2272    1522    3037    6060    5380
River Rch & RM= TRIB 9 TO SALT C,Reach-1,3463
    1283    2188    3051    2058    4106    8193    7377
Boundary for River Rch & Prof#=TRIB 9 TO SALT C,Reach-1,1
Up Type=0
Dn Type=3
Dn Slope=0.005
Boundary for River Rch & Prof#=TRIB 9 TO SALT C,Reach-1,2
Up Type=0
Dn Type=3
Dn Slope=0.005
Boundary for River Rch & Prof#=TRIB 9 TO SALT C,Reach-1,3
Up Type=0
Dn Type=3
Dn Slope=0.005
Boundary for River Rch & Prof#=TRIB 9 TO SALT C,Reach-1,4
Up Type=0
Dn Type=3
Dn Slope=0.005
Boundary for River Rch & Prof#=TRIB 9 TO SALT C,Reach-1,5
Up Type=0
Dn Type=3
Dn Slope=0.005
Boundary for River Rch & Prof#=TRIB 9 TO SALT C,Reach-1,6
Up Type=0
Dn Type=3
Dn Slope=0.005
Boundary for River Rch & Prof#=TRIB 9 TO SALT C,Reach-1,7
Up Type=0
Dn Type=3
Dn Slope=0.005

--- TRIB 9 TO SALT CREEK.g01 (geometry) ---

Geom Title=Existing Conditions

River Reach=TRIB 9 TO SALT C,Reach-1
Reach XY= 30
      2400375.00     13580984.00      2400434.78     13580964.50
      2400618.27     13580784.15      2400723.26     13580821.63
      2400922.71     13580680.85      2401081.06     13580616.86
      2401240.16     13580475.37      2401369.07     13580477.23
      2401535.48     13580573.85      2401805.00     13580575.01
      2401890.22     13580624.48      2402169.14     13580627.07
      2402290.16     13580724.61      2402704.97     13580724.93
      2402780.98     13580677.17      2402859.73     13580675.38
      2403227.29     13580830.85      2403326.50     13580921.37
      2403427.67     13580930.42      2403530.68     13581073.03
      2403664.49     13581073.79      2403790.09     13581024.23
      2403940.16     13581124.61      2404259.79     13581124.46
      2404377.62     13581079.99      2404424.99     13581159.51
      2404336.10     13581385.06      2404472.55     13581519.54
      2404619.21     13581526.91      2404675.00     13581575.00

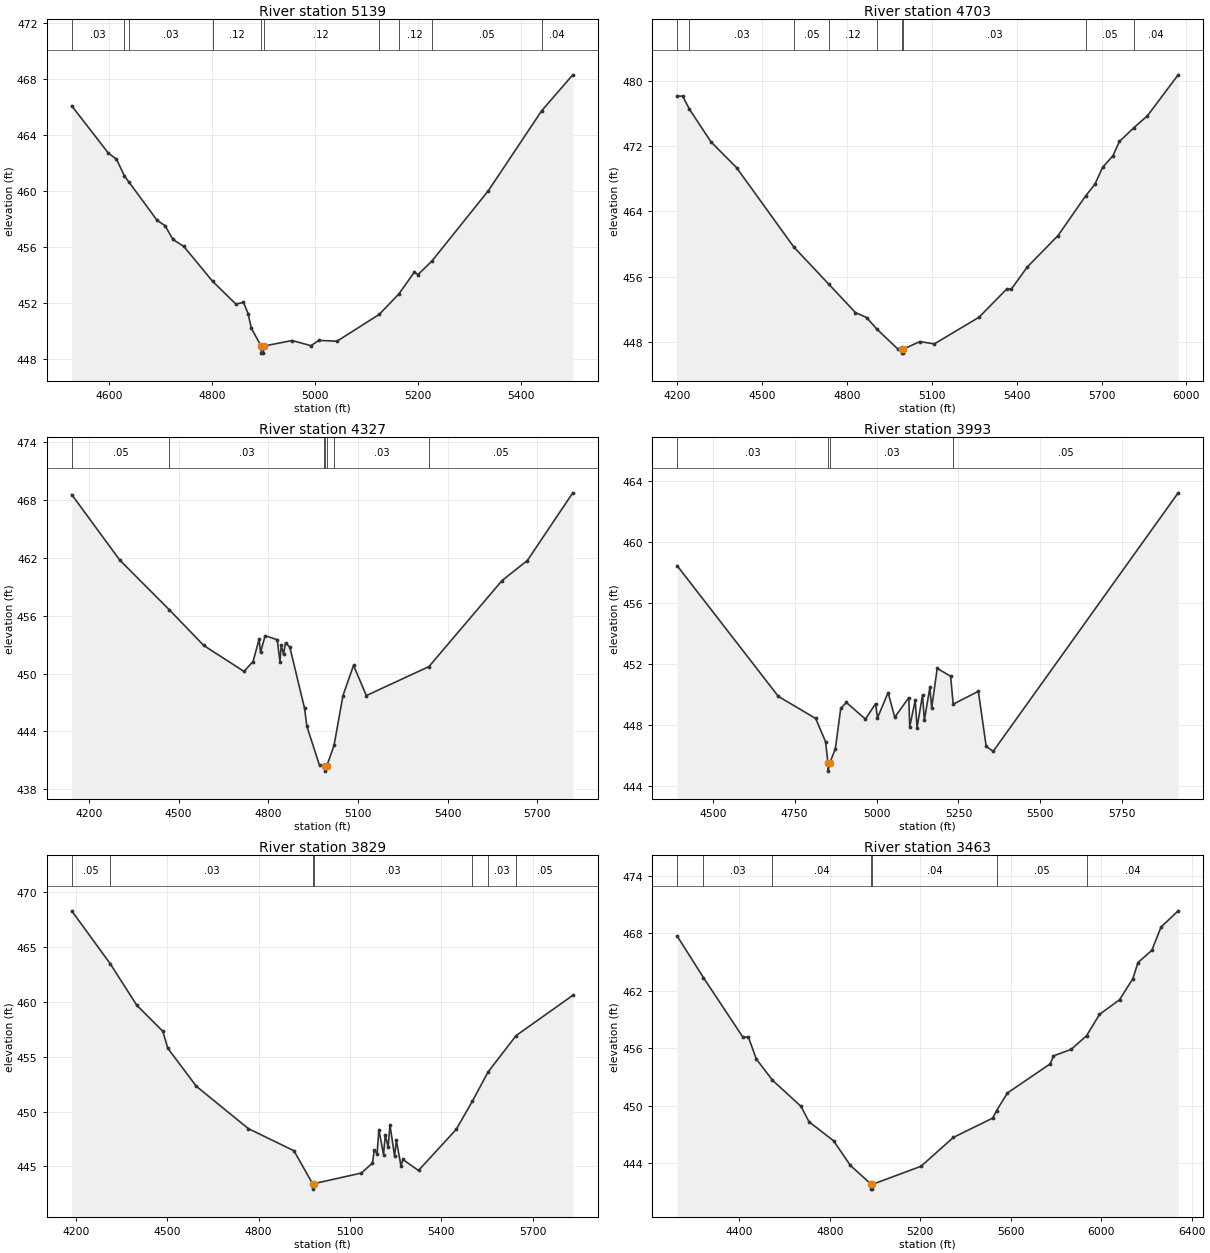
Type RM Length L Ch R = 1,5139,436,436,436
BEGIN DESCRIPTION:
TRIB 9 TO SALT CREEK 11.0
END DESCRIPTION:
XS GIS Cut Line= 3
      2400774.99     13581274.98      2400525.00     13580875.00
      2400124.98     13580574.98
#Sta/Elev= 30
  4528.3  466.09  4599.6  462.70  4615.0  462.29  4630.6  461.08  4639.1  460.66
  4694.0  457.91  4709.3  457.54  4724.6  456.55  4745.8  456.05  4801.6  453.56
  4846.7  451.94  4861.4  452.06  4870.3  451.26  4876.7  450.21  4895.7  448.94
  4896.0  448.44  4899.9  448.44  4900.2  448.94  4955.8  449.34  4992.3  448.97
  5007.3  449.35  5042.7  449.29  5124.5  451.20  5162.4  452.65  5192.7  454.22
  5200.0  454.05  5226.5  455.00  5336.4  460.04  5439.5  465.73  5500.0  468.30
#Mann=10,-1,0
  4528.3    0.03       0  4630.6    0.05       0  4639.1    0.03       0
  4801.6    0.12       0  4895.7    0.05       0  4900.2    0.12       0
  5124.5    0.05       0  5162.4    0.12       0  5226.5    0.05       0
  5439.5    0.04       0
Bank Sta=4895.7,4900.2
Exp/Cntr=0.3,0.1

Type RM Length L Ch R = 1,4703,376,376,376
BEGIN DESCRIPTION:
TRIB 9 TO SALT CREEK 10.0
END DESCRIPTION:
XS GIS Cut Line= 3
      2400875.00     13581525.00      2400875.00     13580725.00
      2400075.02     13580175.01
#Sta/Elev= 30
  4200.0  478.14  4220.0  478.12  4243.7  476.52  4320.0  472.51  4410.0  469.37
  4612.5  459.63  4736.5  455.06  4830.0  451.60  4870.0  450.98  4905.2  449.59
  4980.0  447.13  4995.2  447.12  4995.6  446.62  4999.5  446.62  4999.8  447.12
  5058.2  448.04  5108.9  447.75  5267.0  451.02  5366.0  454.52  5380.9  454.46
  5437.7  457.19  5546.1  461.03  5643.9  465.90  5676.5  467.33  5703.8  469.40
  5740.3  470.82  5763.1  472.57  5815.0  474.28  5861.9  475.71  5970.8  480.74
#Mann=9,-1,0
  4200.0   0.013       0  4243.7    0.03       0  4612.5    0.05       0
  4736.5    0.12       0  4905.2    0.03       0  4995.2    0.03       0
  4999.8    0.03       0  5643.9    0.05       0  5815.0    0.04       0
Bank Sta=4995.2,4999.8
Exp/Cntr=0.3,0.1

Type RM Length L Ch R = 1,4327,334,334,334
BEGIN DESCRIPTION:
Mapping XS 47541778
END DESCRIPTION:
XS GIS Cut Line= 3
      2401169.25     13581333.71      2401280.37     13580646.17
      2400649.20     13579897.09
#Sta/Elev= 30
  4142.5  468.59  4303.3  461.78  4469.3  456.61  4583.9  452.92  4718.6  450.22
  4749.0  451.24  4769.1  453.56  4774.1  452.20  4789.5  453.93  4830.0  453.51
  4839.0  451.21  4843.3  452.93  4851.0  452.02  4857.6  453.18  4871.9  452.75
  4921.3  446.38  4929.1  444.51  4971.3  440.45  4985.2  440.48  4990.4  440.36
  4990.8  439.86  4995.1  440.36  5020.0  442.54  5049.7  447.70  5085.1  450.85
  5128.0  447.71  5337.3  450.72  5581.9  459.66  5666.5  461.74  5818.5  468.77
#Mann=7,-1,0
  4142.5    0.05       0  4469.3    0.03       0  4985.2    0.05       0
  4990.4    0.05       0  4995.1    0.05       0  5020.0    0.03       0
  5337.3    0.05       0
Bank Sta=4990.4,4995.1
Exp/Cntr=0.3,0.1

Type RM Length L Ch R = 1,3993,164,164,164
BEGIN DESCRIPTION:
4916
END DESCRIPTION:
XS GIS Cut Line= 6
      2401372.53     13581088.07      2401384.60     13580587.31
      2401493.20     13580520.94      2401481.13     13580442.51
      2401324.26     13580364.08      2400878.91     13579942.80
#Sta/Elev= 30
  4391.0  458.44  4700.1  449.87  4814.2  448.42  4844.2  446.90  4851.9  445.47
  4852.2  444.97  4856.6  445.47  4874.2  446.44  4890.6  449.08  4907.9  449.47
  4966.0  448.38  4996.9  449.39  5002.8  448.46  5035.2  450.12  5055.5  448.50
  5098.5  449.79  5101.2  447.87  5118.0  449.62  5123.6  447.82  5140.3  449.96
  5145.9  448.30  5162.7  450.46  5168.3  449.11  5185.1  451.70  5226.1  451.19
  5233.9  449.36  5310.7  450.20  5334.7  446.59  5356.1  446.27  5920.8  463.21
#Mann=4,-1,0
  4391.0    0.03       0  4851.9    0.03       0  4856.6    0.03       0
  5233.9    0.05       0
Bank Sta=4851.9,4856.6
Exp/Cntr=0.3,0.1

Type RM Length L Ch R = 1,3829,366,366,366
BEGIN DESCRIPTION:
TRIB 9 TO SALT CREEK 8.0
END DESCRIPTION:
XS GIS Cut Line= 3
      2401475.00     13581374.99      2401625.00     13580575.00
      2401175.00     13579874.99
#Sta/Elev= 30
  4186.2  468.32  4312.3  463.51  4399.8  459.71  4485.5  457.33  4501.6  455.79
  4595.7  452.31  4766.1  448.46  4916.2  446.43  4977.4  443.43  4977.8  442.93
  4982.1  443.43  5137.8  444.40  5174.2  445.31  5180.1  446.51  5189.3  446.16
  5195.3  448.36  5210.5  446.08  5216.4  447.89  5225.7  446.74  5231.6  448.80
  5246.8  445.95  5252.7  447.38  5267.9  445.03  5273.9  445.64  5325.4  444.63
  5449.6  448.39  5502.3  450.95  5554.2  453.63  5646.1  456.94  5832.3  460.61
#Mann=7,-1,0
  4186.2    0.05       0  4312.3    0.03       0  4977.4    0.03       0
  4982.1    0.03       0  5502.3    0.05       0  5554.2    0.03       0
  5646.1    0.05       0
Bank Sta=4977.4,4982.1
Exp/Cntr=0.3,0.1

Type RM Length L Ch R = 1,3463,457,457,457
BEGIN DESCRIPTION:
TRIB 9 TO SALT CREEK 7.0
END DESCRIPTION:
XS GIS Cut Line= 3
      2401524.98     13581375.03      2401974.97     13580625.08
      2402238.93     13579310.82
#Sta/Elev= 30
  4125.4  467.72  4242.0  463.37  4417.0  457.13  4440.3  457.19  4475.3  454.89
  4546.9  452.67  4673.5  449.93  4708.5  448.33  4817.4  446.34  4891.2  443.78
  4983.8  441.80  4984.2  441.30  4988.7  441.30  4989.1  441.80  5204.1  443.69
  5346.9  446.70  5520.3  448.71  5537.9  449.50  5585.4  451.33  5775.3  454.38
  5788.9  455.20  5867.1  455.88  5935.7  457.31  5992.5  459.53  6081.2  461.06
  6140.1  463.26  6162.8  464.94  6224.0  466.22  6264.8  468.65  6340.5  470.34
#Mann=7,-1,0
  4125.4    0.05       0  4242.0    0.03       0  4546.9    0.04       0
  4983.8    0.04       0  4989.1    0.04       0  5537.9    0.05       0
  5935.7    0.04       0
Bank Sta=4983.8,4989.1
Exp/Cntr=0.3,0.1

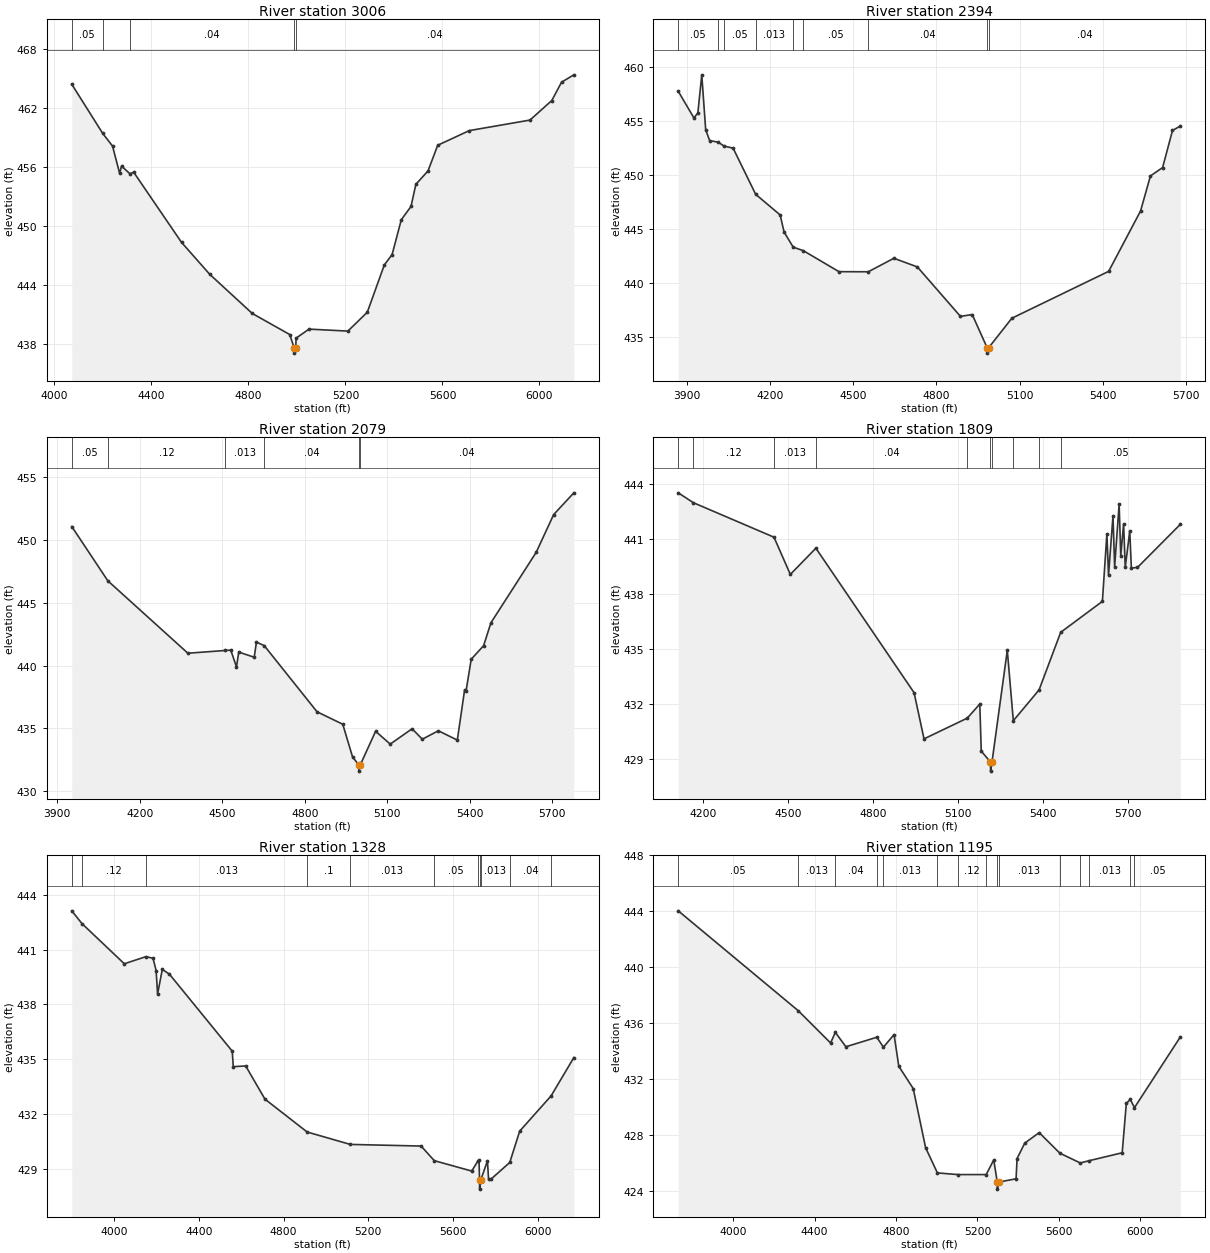
Type RM Length L Ch R = 1,3006,612,612,612
BEGIN DESCRIPTION:
TRIB 9 TO SALT CREEK 6.0
END DESCRIPTION:
XS GIS Cut Line= 3
      2401924.99     13581525.01      2402395.19     13580725.07
      2402438.58     13579584.29
#Sta/Elev= 30
  4072.1  464.39  4199.8  459.39  4240.1  458.11  4269.3  455.34  4277.2  456.07
  4312.1  455.29  4327.3  455.45  4524.5  448.32  4640.5  445.08  4816.2  441.09
  4970.5  438.95  4989.3  437.56  4989.8  437.06  4994.7  437.56  4997.1  438.59
  5050.1  439.50  5210.2  439.30  5290.3  441.22  5360.3  446.02  5392.5  447.08
  5430.4  450.62  5470.4  451.97  5490.4  454.22  5540.5  455.58  5580.5  458.19
  5710.6  459.68  5960.8  460.75  6050.8  462.74  6090.9  464.60  6141.6  465.35
#Mann=5,-1,0
  4072.1    0.05       0  4199.8   0.013       0  4312.1    0.04       0
  4989.3    0.04       0  4994.7    0.04       0
Bank Sta=4989.3,4994.7
Exp/Cntr=0.3,0.1

Type RM Length L Ch R = 1,2394,315,315,315
BEGIN DESCRIPTION:
TRIB 9 TO SALT CREEK 5.0
END DESCRIPTION:
XS GIS Cut Line= 3
      2402174.97     13581525.03      2402975.00     13580725.00
      2402574.99     13580174.99
#Sta/Elev= 30
  3868.6  457.76  3925.2  455.29  3939.4  455.75  3953.5  459.28  3967.6  454.21
  3981.8  453.19  4012.5  453.05  4033.7  452.69  4066.6  452.49  4148.0  448.22
  4236.3  446.31  4250.5  444.73  4283.4  443.33  4320.2  443.00  4448.5  441.06
  4554.3  441.05  4646.5  442.30  4731.3  441.50  4886.9  436.92  4929.3  437.09
  4983.1  434.02  4983.6  433.52  4988.6  434.02  5072.3  436.75  5421.6  441.09
  5536.7  446.68  5572.3  449.92  5616.3  450.70  5651.9  454.13  5680.1  454.54
#Mann=9,-1,0
  3868.6    0.05       0  4012.5   0.013       0  4033.7    0.05       0
  4148.0   0.013       0  4283.4    0.04       0  4320.2    0.05       0
  4554.3    0.04       0  4983.1    0.04       0  4988.6    0.04       0
Bank Sta=4983.1,4988.6
Exp/Cntr=0.3,0.1

Type RM Length L Ch R = 1,2079,270,270,270
BEGIN DESCRIPTION:
Mapping XS 4d772c0e
END DESCRIPTION:
XS GIS Cut Line= 3
      2402629.91     13581690.66      2403234.88     13580898.11
      2403492.82     13580110.22
#Sta/Elev= 30
  3952.5  451.06  4083.7  446.74  4374.8  440.98  4511.6  441.20  4530.8  441.23
  4551.6  439.89  4559.8  441.07  4616.0  440.66  4624.2  441.86  4652.3  441.59
  4844.6  436.32  4938.1  435.33  4973.9  432.72  4996.4  432.10  4996.9  431.60
  5001.9  432.10  5057.6  434.77  5110.7  433.75  5190.3  434.97  5227.4  434.14
  5285.9  434.81  5354.8  434.07  5381.4  438.08  5386.7  437.99  5405.3  440.50
  5450.4  441.58  5477.0  443.40  5641.5  449.00  5705.2  452.01  5778.6  453.74
#Mann=6,-1,0
  3952.5    0.05       0  4083.7    0.12       0  4511.6   0.013       0
  4652.3    0.04       0  4996.4    0.04       0  5001.9    0.04       0
Bank Sta=4996.4,5001.9
Exp/Cntr=0.3,0.1

Type RM Length L Ch R = 1,1809,481,481,481
BEGIN DESCRIPTION:
4915
END DESCRIPTION:
XS GIS Cut Line= 5
      2402820.54     13581516.46      2403176.52     13581051.88
      2403707.46     13580913.12      2403785.89     13580587.31
      2403936.73     13580321.84
#Sta/Elev= 30
  4110.9  443.52  4164.6  442.98  4449.3  441.10  4507.1  439.07  4597.4  440.50
  4944.4  432.62  4979.6  430.10  5132.4  431.23  5176.7  432.00  5181.9  429.43
  5214.4  428.84  5214.9  428.34  5219.9  428.84  5273.9  434.93  5295.2  431.09
  5386.2  432.77  5462.6  435.91  5610.0  437.60  5625.9  441.28  5631.7  439.03
  5647.5  442.27  5653.3  439.49  5669.2  442.89  5674.9  440.10  5685.0  441.82
  5690.8  439.46  5706.7  441.43  5712.4  439.42  5734.0  439.45  5885.4  441.80
#Mann=10,-1,0
  4110.9    0.05       0  4164.6    0.12       0  4449.3   0.013       0
  4597.4    0.04       0  5132.4     0.1       0  5214.4    0.04       0
  5219.9     0.1       0  5295.2    0.05       0  5386.2     0.1       0
  5462.6    0.05       0
Bank Sta=5214.4,5219.9
Exp/Cntr=0.3,0.1

Type RM Length L Ch R = 1,1328,133,133,133
BEGIN DESCRIPTION:
4914
END DESCRIPTION:
XS GIS Cut Line= 5
      2402850.69     13581528.56      2403128.25     13581160.49
      2404407.34     13580985.52      2404739.17     13580895.02
      2404890.02     13580665.73
#Sta/Elev= 30
  3799.7  443.12  3847.9  442.42  4047.7  440.22  4150.0  440.61  4183.4  440.52
  4197.9  439.85  4204.9  438.56  4227.1  439.91  4260.7  439.65  4557.3  435.43
  4562.3  434.58  4620.8  434.62  4711.8  432.80  4911.0  431.00  5114.7  430.32
  5449.1  430.23  5511.2  429.43  5687.9  428.86  5717.7  429.42  5722.5  429.45
  5724.8  428.37  5725.3  427.87  5730.6  428.37  5762.2  429.42  5767.4  428.42
  5777.3  428.40  5867.5  429.33  5914.5  431.05  6062.8  432.98  6170.1  435.08
#Mann=11,-1,0
  3799.7    0.05       0  3847.9    0.12       0  4150.0   0.013       0
  4911.0     0.1       0  5114.7   0.013       0  5511.2    0.05       0
  5717.7   0.013       0  5724.8    0.05       0  5730.6   0.013       0
  5867.5    0.04       0  6062.8    0.05       0
Bank Sta=5724.8,5730.6
Exp/Cntr=0.3,0.1

Type RM Length L Ch R = 1,1195,466,466,466
BEGIN DESCRIPTION:
4913
END DESCRIPTION:
XS GIS Cut Line= 4
      2402856.74     13581637.13      2403333.39     13581232.89
      2404830.25     13580979.81      2404926.20     13580671.81
#Sta/Elev= 30
  3730.7  444.03  4320.0  436.89  4479.0  434.58  4502.2  435.34  4554.0  434.31
  4705.9  434.99  4738.3  434.28  4790.6  435.18  4813.7  432.92  4884.7  431.32
  4945.6  427.09  5003.4  425.29  5103.7  425.17  5243.1  425.17  5280.2  426.22
  5297.5  424.63  5298.0  424.13  5303.6  424.63  5389.8  424.87  5394.8  426.32
  5432.4  427.42  5503.4  428.17  5604.9  426.70  5705.1  426.00  5747.9  426.16
  5911.0  426.73  5931.2  430.26  5950.6  430.54  5971.4  429.96  6196.4  435.01
#Mann=15,-1,0
  3730.7    0.05       0  4320.0   0.013       0  4502.2    0.04       0
  4705.9    0.05       0  4738.3   0.013       0  5003.4     0.1       0
  5103.7    0.12       0  5243.1   0.013       0  5297.5    0.03       0
  5303.6   0.013       0  5604.9    0.05       0  5705.1    0.12       0
  5747.9   0.013       0  5950.6    0.04       0  5971.4    0.05       0
Bank Sta=5297.5,5303.6
Exp/Cntr=0.3,0.1

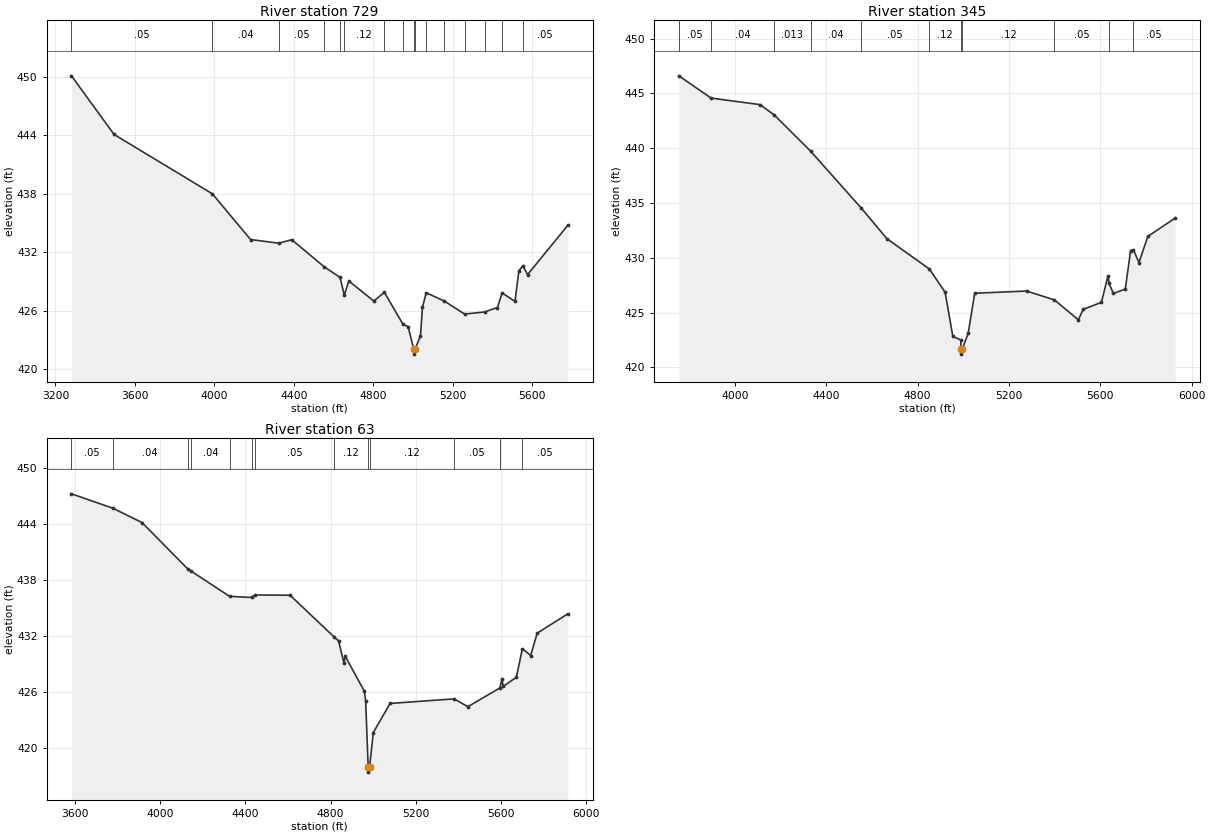
Type RM Length L Ch R = 1,729,384,384,384
BEGIN DESCRIPTION:
Mapping XS 3dcbc004
END DESCRIPTION:
XS GIS Cut Line= 5
      2402934.76     13581934.49      2403960.86     13581196.69
      2404831.34     13581019.96      2404854.12     13580976.56
      2404938.26     13580689.92
#Sta/Elev= 30
  3280.6  450.08  3495.1  444.07  3990.5  437.98  4182.6  433.30  4324.7  432.92
  4390.1  433.28  4553.8  430.50  4633.9  429.41  4654.7  427.57  4677.4  429.05
  4803.7  426.99  4856.7  427.89  4950.9  424.59  4976.1  424.38  5004.8  422.05
  5005.3  421.55  5010.9  422.05  5038.4  423.41  5048.6  426.37  5067.5  427.84
  5159.5  426.98  5260.5  425.66  5361.5  425.87  5426.2  426.33  5449.9  427.82
  5514.6  426.96  5534.1  430.08  5554.0  430.62  5577.9  429.70  5780.4  434.75
#Mann=16,-1,0
  3280.6    0.05       0  3990.5    0.04       0  4324.7    0.05       0
  4553.8    0.12       0  4633.9     0.1       0  4654.7    0.12       0
  4856.7    0.05       0  4950.9    0.12       0  5004.8    0.05       0
  5010.9    0.12       0  5067.5   0.013       0  5159.5    0.05       0
  5260.5    0.12       0  5361.5    0.05       0  5449.9   0.013       0
  5554.0    0.05       0
Bank Sta=5004.8,5010.9
Exp/Cntr=0.3,0.1

Type RM Length L Ch R = 1,345,282,282,282
BEGIN DESCRIPTION:
Mapping XS a211d20d
END DESCRIPTION:
XS GIS Cut Line= 4
      2403264.70     13581979.82      2404374.09     13581443.36
      2404835.03     13581042.31      2404967.86     13580740.19
#Sta/Elev= 30
  3754.3  446.61  3895.4  444.58  4110.1  443.98  4171.8  443.04  4331.0  439.74
  4551.8  434.57  4665.5  431.74  4851.7  428.97  4920.4  426.85  4954.3  422.81
  4989.1  422.50  4990.0  421.70  4990.5  421.20  4996.2  421.70  5021.6  423.12
  5050.0  426.76  5277.0  426.96  5399.3  426.15  5503.9  424.33  5524.8  425.28
  5605.0  425.93  5633.8  428.37  5638.3  427.65  5657.2  426.74  5709.3  427.14
  5732.7  430.64  5744.6  430.74  5769.4  429.56  5808.2  431.95  5927.6  433.62
#Mann=11,-1,0
  3754.3    0.05       0  3895.4    0.04       0  4171.8   0.013       0
  4331.0    0.04       0  4551.8    0.05       0  4851.7    0.12       0
  4990.0    0.05       0  4996.2    0.12       0  5399.3    0.05       0
  5638.3   0.013       0  5744.6    0.05       0
Bank Sta=4990,4996.2
Exp/Cntr=0.3,0.1

Type RM Length L Ch R = 1,63,0,0,0
BEGIN DESCRIPTION:
TRIB 9 TO SALT CREEK 1.0
END DESCRIPTION:
XS GIS Cut Line= 4
      2403338.00     13582061.14      2404571.14     13581621.31
      2404781.21     13581300.13      2405029.03     13580712.77
#Sta/Elev= 30
  3583.5  447.23  3776.3  445.70  3914.5  444.15  4129.2  439.18  4146.9  438.91
  4325.8  436.23  4429.7  436.11  4445.0  436.38  4610.2  436.35  4816.3  431.88
  4837.8  431.45  4863.3  429.04  4868.6  429.82  4958.9  426.05  4964.9  425.02
  4976.9  417.87  4977.4  417.37  4983.1  417.87  5001.0  421.62  5079.5  424.74
  5380.3  425.23  5444.9  424.39  5595.1  426.40  5605.0  427.39  5610.5  426.56
  5672.8  427.55  5700.8  430.61  5739.9  429.88  5770.5  432.28  5914.0  434.35
#Mann=13,-1,0
  3583.5    0.05       0  3776.3    0.04       0  4129.2   0.013       0
  4146.9    0.04       0  4325.8    0.05       0  4429.7    0.04       0
  4445.0    0.05       0  4816.3    0.12       0  4976.9    0.05       0
  4983.1    0.12       0  5380.3    0.05       0  5595.1   0.013       0
  5700.8    0.05       0
Bank Sta=4976.9,4983.1
Exp/Cntr=0.3,0.1

Chan Stop Cuts=-1