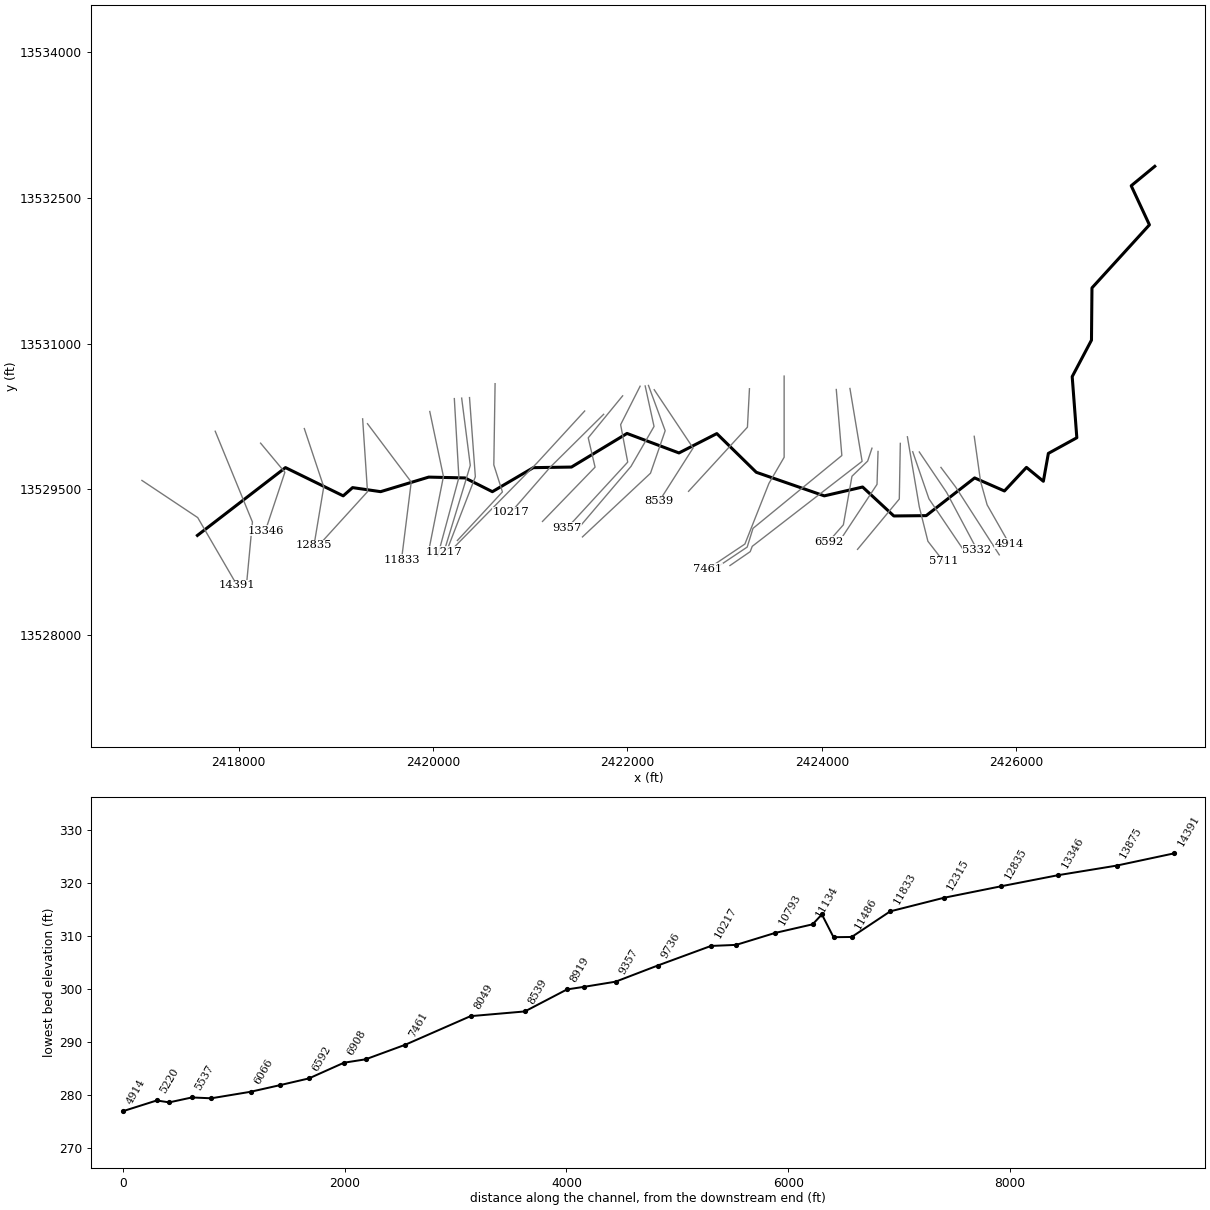
--- TRIB 9 TO SMITH CREEK.prj (project) ---

Proj Title=TRIB 9 TO SMITH CREEK Base Level Engineering
Current Plan=p01
Default Exp/Contr=0.3,0.1
English Units
Geom File=g01
Flow File=f01
Plan File=p01
BEGIN DESCRIPTION:
TRIB 9 TO SMITH CREEK
END DESCRIPTION:

--- TRIB 9 TO SMITH CREEK.p01 (plan) ---

Plan Title=Multiple Run
Short Identifier=Multiple
Geom File=g01
Flow File=f01
Subcritical Flow
K Sum by GR= 0
Std Step Tol= 0.01
Critical Tol= 0.01
Num of Std Step Trials= 20
Max Error Tol= 0.3
Flow Tol Ratio= 0.001
Split Flow NTrial= 30
Split Flow Tol= 0.02
Split Flow Ratio= 0.02
Log Output Level= 0
Friction Slope Method= 1
Unsteady Friction Slope Method= 2
Unsteady Bridges Friction Slope Method= 1
Parabolic Critical Depth
Global Vel Dist=  1 , 1 , 1
Global Log Level= 0
CheckData=True
Encroach Param= -1, 0, 0, 0
BEGIN DESCRIPTION:
Multiple Run
END DESCRIPTION:

--- TRIB 9 TO SMITH CREEK.f01 (steady flow) ---

Flow Title=Multiple
Number of Profiles=7
Profile Names=10-year,25-year,50-year,1pct_min,100-year,1pct_plu,500-year
River Rch & RM= TRIB 9 TO SMITH ,Reach-1,14391
     641    1037    1394     907    1809    3610    3017
River Rch & RM= TRIB 9 TO SMITH ,Reach-1,13346
     728    1185    1599    1045    2084    4159    3505
River Rch & RM= TRIB 9 TO SMITH ,Reach-1,11833
    1124    1875    2573    1705    3403    6789    5897
River Rch & RM= TRIB 9 TO SMITH ,Reach-1,7461
    1824    3126    4369    2945    5876   11724   10540
River Rch & RM= TRIB 9 TO SMITH ,Reach-1,5711
    2202    3800    5335    3611    7205   14376   13028
River Rch & RM= TRIB 9 TO SMITH ,Reach-1,1399
    2254    3893    5470    3704    7391   14748   13380
Boundary for River Rch & Prof#=TRIB 9 TO SMITH ,Reach-1,1
Up Type=0
Dn Type=3
Dn Slope=0.005
Boundary for River Rch & Prof#=TRIB 9 TO SMITH ,Reach-1,2
Up Type=0
Dn Type=3
Dn Slope=0.005
Boundary for River Rch & Prof#=TRIB 9 TO SMITH ,Reach-1,3
Up Type=0
Dn Type=3
Dn Slope=0.005
Boundary for River Rch & Prof#=TRIB 9 TO SMITH ,Reach-1,4
Up Type=0
Dn Type=3
Dn Slope=0.005
Boundary for River Rch & Prof#=TRIB 9 TO SMITH ,Reach-1,5
Up Type=0
Dn Type=3
Dn Slope=0.005
Boundary for River Rch & Prof#=TRIB 9 TO SMITH ,Reach-1,6
Up Type=0
Dn Type=3
Dn Slope=0.005
Boundary for River Rch & Prof#=TRIB 9 TO SMITH ,Reach-1,7
Up Type=0
Dn Type=3
Dn Slope=0.005

--- TRIB 9 TO SMITH CREEK.g01 (geometry) ---

Geom Title=Existing Conditions

River Reach=TRIB 9 TO SMITH ,Reach-1
Reach XY= 30
      2417575.00     13529025.00      2418481.13     13529723.22
      2419075.10     13529432.34      2419171.58     13529517.18
      2419459.78     13529475.52      2419954.85     13529625.36
      2420328.31     13529616.93      2420609.78     13529475.24
      2421030.94     13529722.74      2421423.45     13529728.75
      2421995.03     13530074.94      2422529.58     13529874.13
      2422918.97     13530073.39      2423325.00     13529675.00
      2424024.90     13529432.33      2424418.97     13529523.38
      2424740.15     13529225.37      2425073.46     13529228.72
      2425571.70     13529616.92      2425878.34     13529482.60
      2426104.77     13529725.50      2426278.66     13529582.48
      2426330.25     13529869.53      2426623.03     13530030.65
      2426575.39     13530659.84      2426773.78     13531035.50
      2426778.82     13531573.41      2427369.91     13532222.70
      2427182.50     13532625.00      2427425.00     13532825.00

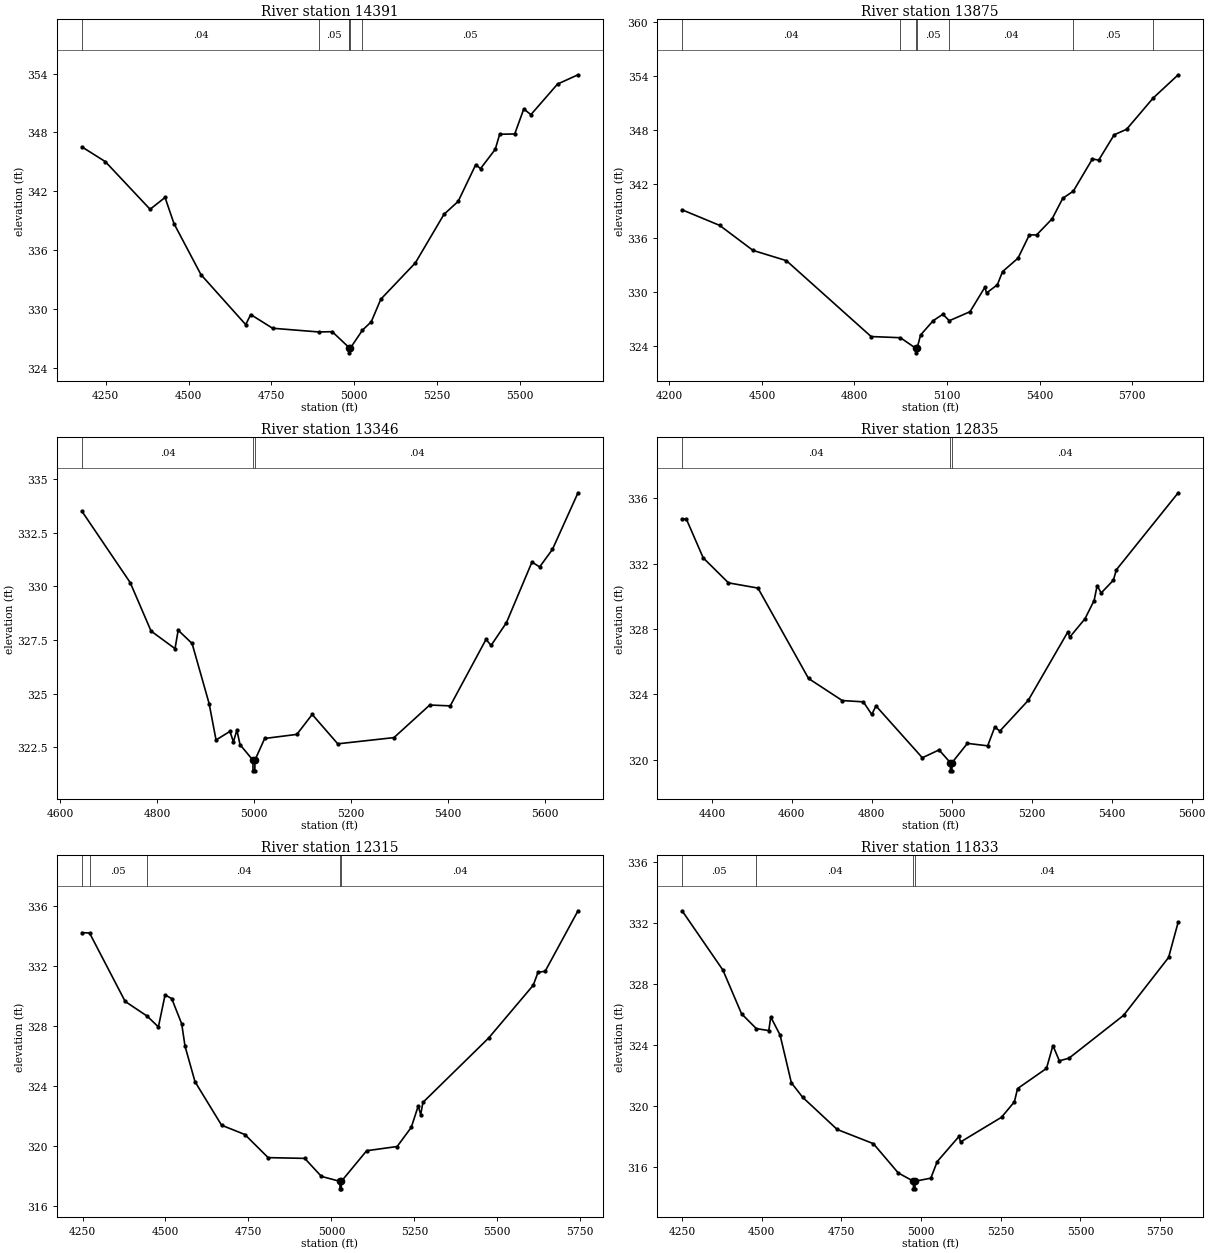
Type RM Length L Ch R = 1,14391,516,516,516
BEGIN DESCRIPTION:
LGII4644
END DESCRIPTION:
XS GIS Cut Line= 3
      2417004.26     13529591.08      2417578.22     13529208.44
      2417983.38     13528510.65
#Sta/Elev= 30
  4178.4  346.53  4248.9  345.03  4384.1  340.16  4429.2  341.37  4456.2  338.70
  4537.4  333.50  4672.6  328.39  4687.6  329.42  4753.7  328.02  4893.6  327.64
  4933.6  327.67  4982.8  326.10  4984.6  326.01  4984.9  325.51  4988.6  326.01
  5024.9  327.83  5051.2  328.67  5080.3  330.99  5184.4  334.69  5270.6  339.64
  5313.6  340.97  5366.6  344.72  5381.0  344.31  5425.4  346.28  5438.8  347.82
  5484.2  347.85  5511.5  350.40  5533.0  349.82  5613.3  352.94  5675.1  353.89
#Mann=6,-1,0
  4178.4    0.04       0  4893.6    0.05       0  4982.8     0.1       0
  4984.6    0.05       0  4988.6     0.1       0  5024.9    0.05       0
Bank Sta=4984.6,4988.6
Exp/Cntr=0.3,0.1

Type RM Length L Ch R = 1,13875,529,529,529
BEGIN DESCRIPTION:
LGII4643
END DESCRIPTION:
XS GIS Cut Line= 3
      2417758.29     13530097.56      2418140.96     13529163.42
      2418084.83     13528568.44
#Sta/Elev= 30
  4241.6  339.10  4363.2  337.37  4471.3  334.59  4579.4  333.45  4853.9  325.02
  4948.8  324.89  4998.8  323.71  4999.1  323.21  5002.8  323.71  5014.1  325.19
  5054.9  326.78  5086.1  327.49  5107.4  326.78  5174.3  327.78  5222.3  330.49
  5227.8  329.86  5262.9  330.77  5279.6  332.23  5329.8  333.73  5366.4  336.31
  5390.1  336.31  5440.3  338.10  5474.8  340.38  5508.9  341.17  5570.9  344.76
  5591.0  344.61  5641.2  347.43  5681.4  348.04  5767.4  351.51  5848.7  354.10
#Mann=7,-1,0
  4241.6    0.04       0  4948.8    0.05       0  4998.8    0.05       0
  5002.8    0.05       0  5107.4    0.04       0  5508.9    0.05       0
  5767.4    0.03       0
Bank Sta=4998.8,5002.8
Exp/Cntr=0.3,0.1

Type RM Length L Ch R = 1,13346,511,511,511
BEGIN DESCRIPTION:
TRIB 9 TO SMITH CREEK 28.0
END DESCRIPTION:
XS GIS Cut Line= 3
      2418224.98     13529975.02      2418475.00     13529675.00
      2418275.00     13529075.00
#Sta/Elev= 30
  4645.0  333.51  4744.6  330.18  4787.6  327.92  4837.0  327.10  4843.5  327.96
  4872.2  327.34  4907.3  324.54  4921.6  322.84  4950.3  323.24  4957.4  322.75
  4964.6  323.30  4971.1  322.62  4997.6  321.90  4997.9  321.40  5001.6  321.40
  5001.8  321.90  5021.9  322.91  5088.2  323.10  5119.9  324.03  5172.6  322.66
  5288.5  322.95  5362.3  324.47  5404.5  324.43  5478.3  327.53  5488.8  327.25
  5520.4  328.31  5573.1  331.14  5588.9  330.91  5615.3  331.73  5668.0  334.37
#Mann=3,-1,0
  4645.0    0.04       0  4997.6    0.04       0  5001.8    0.04       0
Bank Sta=4997.6,5001.8
Exp/Cntr=0.3,0.1

Type RM Length L Ch R = 1,12835,520,520,520
BEGIN DESCRIPTION:
TRIB 9 TO SMITH CREEK 27.0
END DESCRIPTION:
XS GIS Cut Line= 3
      2418675.01     13530124.98      2418875.00     13529525.00
      2418775.00     13528925.01
#Sta/Elev= 30
  4325.7  334.71  4336.2  334.73  4378.4  332.35  4441.6  330.82  4515.4  330.50
  4641.9  324.97  4726.2  323.62  4778.9  323.54  4800.0  322.77  4810.6  323.29
  4926.5  320.12  4968.3  320.60  4996.5  319.82  4996.8  319.32  5000.5  319.32
  5000.8  319.82  5039.2  321.00  5089.9  320.85  5107.7  322.00  5120.3  321.75
  5191.3  323.63  5290.2  327.81  5295.2  327.50  5333.2  328.62  5356.1  329.74
  5363.7  330.65  5373.8  330.20  5404.2  330.98  5411.8  331.62  5566.4  336.33
#Mann=3,-1,0
  4325.7    0.04       0  4996.5    0.04       0  5000.8    0.04       0
Bank Sta=4996.5,5000.8
Exp/Cntr=0.3,0.1

Type RM Length L Ch R = 1,12315,482,482,482
BEGIN DESCRIPTION:
TRIB 9 TO SMITH CREEK 26.0
END DESCRIPTION:
XS GIS Cut Line= 3
      2419275.00     13530225.00      2419325.00     13529475.00
      2418824.98     13528924.98
#Sta/Elev= 30
  4248.2  334.20  4271.2  334.18  4378.5  329.62  4444.8  328.64  4478.7  327.92
  4498.8  330.05  4518.8  329.81  4548.9  328.13  4558.9  326.64  4589.0  324.27
  4669.1  321.37  4739.3  320.75  4809.4  319.21  4919.7  319.16  4969.8  317.96
  5025.7  317.63  5026.0  317.13  5029.8  317.13  5030.1  317.63  5106.3  319.67
  5198.2  319.95  5240.8  321.23  5261.7  322.65  5269.1  322.08  5275.9  322.89
  5473.9  327.18  5608.4  330.70  5622.6  331.56  5644.2  331.63  5743.2  335.66
#Mann=5,-1,0
  4248.2    0.04       0  4271.2    0.05       0  4444.8    0.04       0
  5025.7    0.04       0  5030.1    0.04       0
Bank Sta=5025.7,5030.1
Exp/Cntr=0.3,0.1

Type RM Length L Ch R = 1,11833,347,347,347
BEGIN DESCRIPTION:
TRIB 9 TO SMITH CREEK 25.0
END DESCRIPTION:
XS GIS Cut Line= 3
      2419325.00     13530175.00      2419775.00     13529575.00
      2419675.00     13528775.02
#Sta/Elev= 30
  4250.4  332.80  4378.5  328.91  4436.9  326.05  4483.1  325.08  4522.3  324.95
  4528.5  325.84  4557.7  324.66  4593.1  321.53  4628.5  320.58  4736.9  318.47
  4850.4  317.54  4928.5  315.62  4975.8  315.08  4976.2  314.58  4980.8  314.58
  4981.3  315.08  5030.6  315.28  5050.8  316.37  5118.8  318.01  5123.8  317.65
  5252.3  319.27  5292.7  320.28  5302.7  321.15  5393.4  322.47  5413.6  323.97
  5433.7  322.97  5464.0  323.14  5635.3  325.95  5776.4  329.74  5806.6  332.06
#Mann=4,-1,0
  4250.4    0.05       0  4483.1    0.04       0  4975.8    0.04       0
  4981.3    0.04       0
Bank Sta=4975.8,4981.3
Exp/Cntr=0.3,0.1

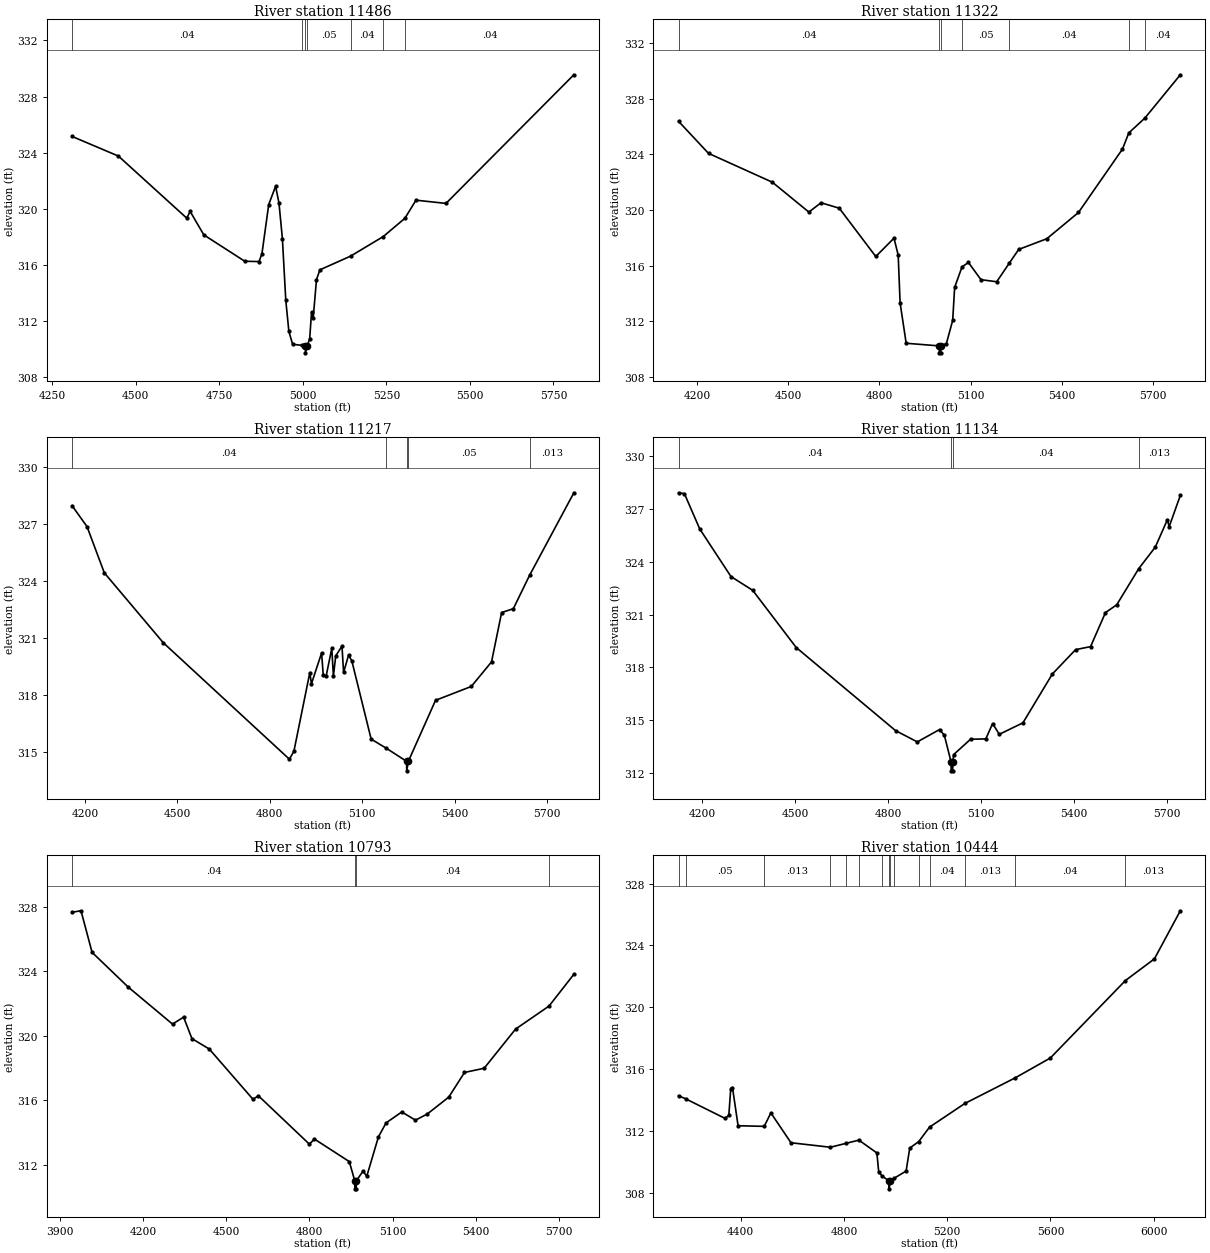
Type RM Length L Ch R = 1,11486,164,164,164
BEGIN DESCRIPTION:
Mapping XS cdbf140d
END DESCRIPTION:
XS GIS Cut Line= 3
      2419965.80     13530300.73      2420106.42     13529631.47
      2419947.63     13528829.71
#Sta/Elev= 30
  4309.8  325.16  4448.5  323.76  4652.9  319.34  4663.1  319.82  4703.9  318.15
  4826.6  316.27  4868.9  316.25  4877.7  316.78  4898.1  320.31  4918.7  321.61
  4928.8  320.42  4939.0  317.89  4949.2  313.48  4958.4  311.28  4969.6  310.36
  4998.8  310.28  5007.7  310.25  5008.1  309.75  5013.3  310.25  5020.7  310.75
  5026.2  312.65  5031.3  312.25  5041.0  314.96  5051.2  315.66  5143.3  316.64
  5240.8  318.03  5305.5  319.33  5338.7  320.62  5428.4  320.39  5811.0  329.55
#Mann=7,-1,0
  4309.8    0.04       0  4998.8    0.05       0  5007.7    0.05       0
  5013.3    0.05       0  5143.3    0.04       0  5240.8    0.05       0
  5305.5    0.04       0
Bank Sta=5007.7,5013.3
Exp/Cntr=0.3,0.1

Type RM Length L Ch R = 1,11322,105,105,105
BEGIN DESCRIPTION:
Mapping XS 1d4a8f91
END DESCRIPTION:
XS GIS Cut Line= 3
      2420218.40     13530433.56      2420265.28     13529621.06
      2420046.52     13528811.13
#Sta/Elev= 30
  4138.2  326.39  4236.9  324.08  4447.3  322.00  4567.5  319.85  4607.5  320.52
  4667.6  320.13  4787.8  316.65  4847.9  317.97  4861.7  316.75  4868.0  313.31
  4888.0  310.40  4997.0  310.21  4997.4  309.71  5002.1  309.71  5002.6  310.21
  5020.5  310.38  5041.2  312.05  5047.7  314.43  5071.9  315.90  5093.0  316.22
  5134.4  314.98  5186.2  314.83  5227.6  316.17  5258.7  317.16  5351.3  317.93
  5455.5  319.82  5600.5  324.39  5621.2  325.55  5674.2  326.62  5791.0  329.74
#Mann=7,-1,0
  4138.2    0.04       0  4997.0    0.04       0  5002.6    0.04       0
  5071.9    0.05       0  5227.6    0.04       0  5621.2   0.013       0
  5674.2    0.04       0
Bank Sta=4997,5002.6
Exp/Cntr=0.3,0.1

Type RM Length L Ch R = 1,11217,83,83,83
BEGIN DESCRIPTION:
Mapping XS 557215bd
END DESCRIPTION:
XS GIS Cut Line= 4
      2420293.92     13530438.80      2420382.47     13529746.06
      2420327.78     13529563.77      2420111.63     13528855.41
#Sta/Elev= 30
  4158.1  327.96  4206.7  326.86  4262.7  324.43  4454.3  320.75  4863.9  314.62
  4878.5  315.05  4930.1  319.18  4935.3  318.59  4968.3  320.21  4973.6  319.06
  4982.9  318.98  5001.4  320.46  5006.6  318.99  5014.2  320.06  5034.5  320.57
  5039.7  319.19  5056.0  320.10  5066.4  319.80  5129.2  315.68  5178.3  315.20
  5244.3  314.51  5244.7  314.01  5249.9  314.51  5338.3  317.72  5454.4  318.45
  5520.0  319.74  5552.9  322.34  5590.9  322.54  5643.4  324.29  5787.4  328.64
#Mann=5,-1,0
  4158.1    0.04       0  5178.3    0.05       0  5244.3    0.04       0
  5249.9    0.05       0  5643.4   0.013       0
Bank Sta=5244.3,5249.9
Exp/Cntr=0.3,0.1

Type RM Length L Ch R = 1,11134,341,341,341
BEGIN DESCRIPTION:
Mapping XS 350800cc
END DESCRIPTION:
XS GIS Cut Line= 3
      2420374.66     13530443.95      2420434.55     13529628.87
      2420145.72     13528879.48
#Sta/Elev= 30
  4123.6  327.90  4142.6  327.85  4192.1  325.85  4293.0  323.15  4363.2  322.37
  4503.6  319.13  4824.4  314.42  4894.6  313.78  4966.5  314.48  4981.9  314.16
  5003.8  312.64  5004.2  312.14  5008.9  312.14  5009.4  312.64  5011.9  313.06
  5066.5  313.93  5115.8  313.95  5137.9  314.82  5159.4  314.21  5235.7  314.86
  5330.8  317.63  5405.9  319.01  5454.1  319.18  5502.3  321.11  5538.6  321.55
  5609.7  323.60  5663.1  324.82  5702.4  326.38  5707.8  325.97  5744.0  327.75
#Mann=4,-1,0
  4123.6    0.04       0  5003.8    0.04       0  5009.4    0.04       0
  5609.7   0.013       0
Bank Sta=5003.8,5009.4
Exp/Cntr=0.3,0.1

Type RM Length L Ch R = 1,10793,349,349,349
BEGIN DESCRIPTION:
Mapping XS 2fbb39be
END DESCRIPTION:
XS GIS Cut Line= 4
      2420637.68     13530587.23      2420624.65     13529751.27
      2420713.20     13529472.62      2420249.83     13528972.81
#Sta/Elev= 30
  3943.6  327.66  3975.8  327.75  4015.8  325.17  4145.9  323.02  4305.9  320.72
  4345.9  321.15  4375.9  319.82  4438.7  319.17  4595.9  316.06  4615.9  316.27
  4799.7  313.27  4817.7  313.59  4943.6  312.19  4963.3  311.00  4963.7  310.50
  4968.5  310.50  4969.0  311.00  4993.2  311.60  5006.6  311.28  5048.6  313.72
  5076.2  314.59  5132.9  315.27  5182.2  314.76  5224.7  315.14  5302.4  316.19
  5359.1  317.72  5430.0  317.98  5543.3  320.41  5664.1  321.84  5753.6  323.81
#Mann=4,-1,0
  3943.6    0.04       0  4963.3    0.04       0  4969.0    0.04       0
  5664.1   0.013       0
Bank Sta=4963.3,4969
Exp/Cntr=0.3,0.1

Type RM Length L Ch R = 1,10444,227,227,227
BEGIN DESCRIPTION:
Mapping XS 0d26a145
END DESCRIPTION:
XS GIS Cut Line= 3
      2421559.55     13530305.95      2421069.97     13529772.10
      2420215.82     13528902.33
#Sta/Elev= 30
  4159.6  314.28  4187.3  314.08  4340.3  312.81  4354.4  313.02  4361.8  314.74
  4368.6  314.81  4390.2  312.34  4491.4  312.30  4517.2  313.17  4595.1  311.24
  4747.8  310.95  4807.9  311.20  4858.1  311.41  4927.8  310.58  4935.0  309.33
  4947.4  309.11  4974.5  308.76  4975.0  308.26  4980.2  308.76  4995.3  308.95
  5041.0  309.41  5055.1  310.90  5089.6  311.31  5131.7  312.25  5268.4  313.78
  5463.9  315.44  5599.6  316.72  5890.4  321.73  6002.6  323.13  6103.0  326.24
#Mann=15,-1,0
  4159.6   0.013       0  4187.3    0.05       0  4491.4   0.013       0
  4747.8    0.04       0  4807.9   0.013       0  4858.1    0.04       0
  4947.4   0.013       0  4974.5    0.04       0  4980.2   0.013       0
  4995.3    0.04       0  5089.6   0.013       0  5131.7    0.04       0
  5268.4   0.013       0  5463.9    0.04       0  5890.4   0.013       0
Bank Sta=4974.5,4980.2
Exp/Cntr=0.3,0.1

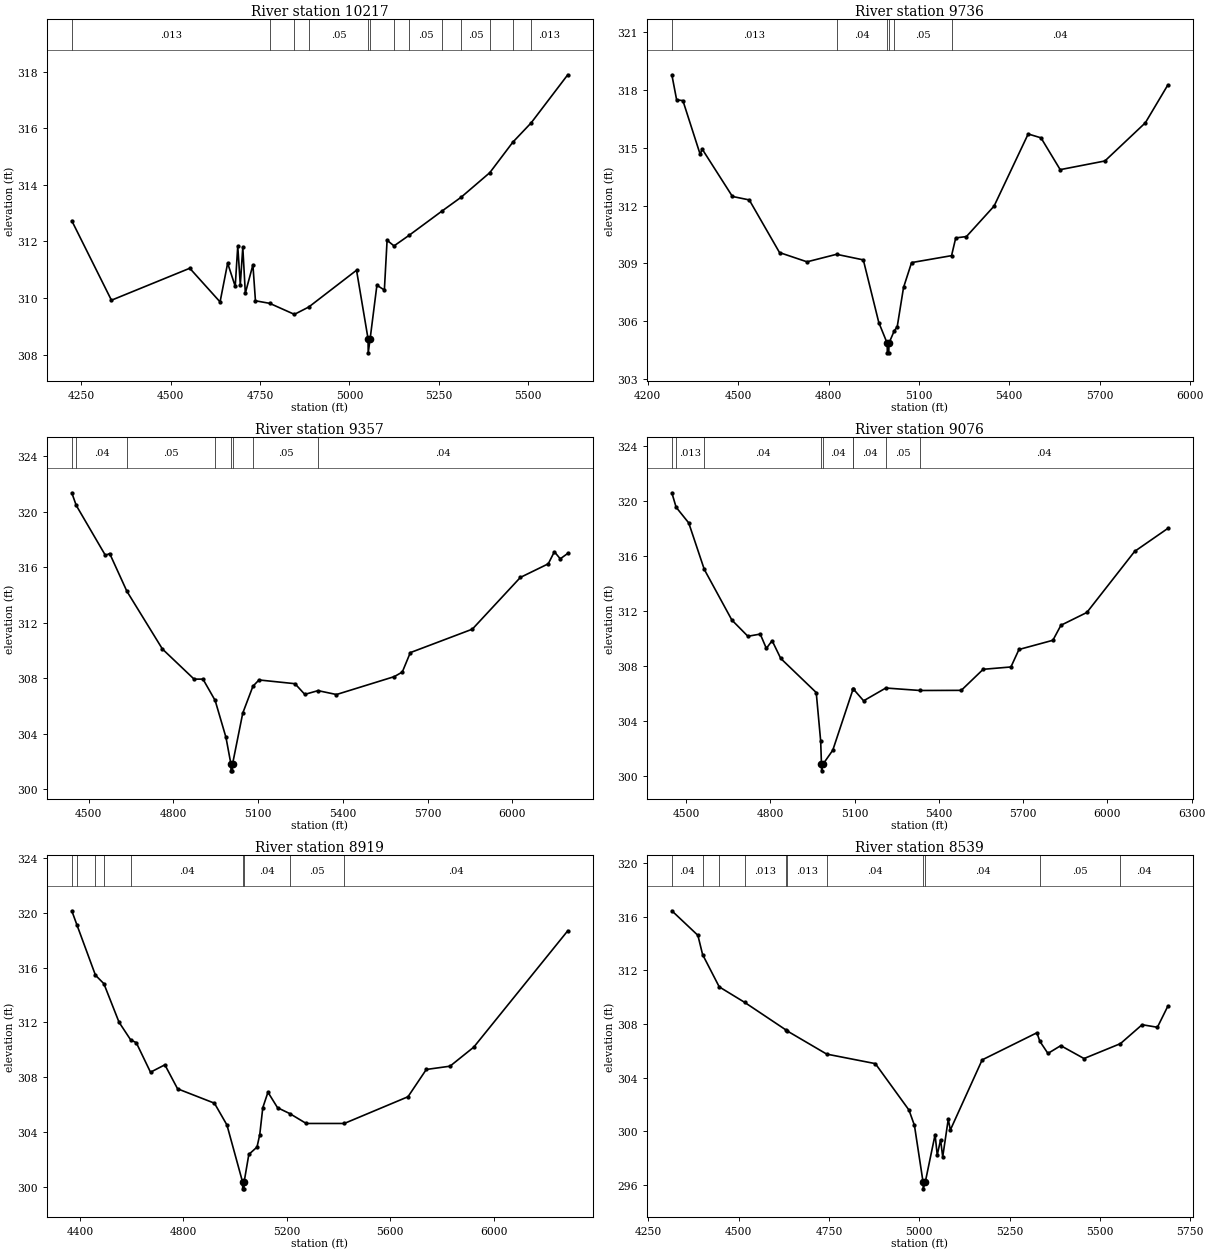
Type RM Length L Ch R = 1,10217,481,481,481
BEGIN DESCRIPTION:
Mapping XS 45e066a6
END DESCRIPTION:
XS GIS Cut Line= 3
      2421754.84     13530272.07      2421205.38     13529727.83
      2420801.75     13529264.31
#Sta/Elev= 30
  4222.9  312.73  4333.9  309.92  4553.1  311.05  4637.9  309.86  4659.1  311.23
  4680.3  310.41  4687.4  311.83  4694.5  310.47  4701.5  311.79  4708.6  310.17
  4729.8  311.17  4736.9  309.90  4776.7  309.81  4845.9  309.42  4886.1  309.68
  5019.8  310.98  5052.0  308.56  5052.5  308.06  5057.9  308.56  5076.8  310.45
  5097.7  310.28  5105.3  312.04  5124.7  311.84  5167.5  312.22  5258.7  313.07
  5312.4  313.56  5392.8  314.43  5457.4  315.51  5508.5  316.19  5610.9  317.89
#Mann=13,-1,0
  4222.9   0.013       0  4776.7    0.05       0  4845.9   0.013       0
  4886.1    0.05       0  5052.0    0.05       0  5057.9    0.05       0
  5124.7   0.013       0  5167.5    0.05       0  5258.7   0.013       0
  5312.4    0.05       0  5392.8   0.013       0  5457.4    0.05       0
  5508.5   0.013       0
Bank Sta=5052,5057.9
Exp/Cntr=0.3,0.1

Type RM Length L Ch R = 1,9736,379,379,379
BEGIN DESCRIPTION:
Mapping XS 1d33807c
END DESCRIPTION:
XS GIS Cut Line= 4
      2421950.15     13530462.18      2421596.01     13530029.91
      2421666.32     13529727.83      2421125.63     13529168.94
#Sta/Elev= 30
  4279.9  318.78  4295.8  317.48  4316.6  317.44  4374.0  314.65  4380.5  314.93
  4481.0  312.47  4536.9  312.29  4637.4  309.56  4728.7  309.08  4826.7  309.47
  4915.6  309.18  4967.0  305.93  4994.8  304.86  4995.3  304.36  5000.2  304.36
  5000.7  304.86  5018.2  305.50  5028.1  305.71  5049.1  307.75  5075.8  309.04
  5208.5  309.40  5222.4  310.32  5257.9  310.39  5349.7  311.97  5462.9  315.71
  5505.4  315.51  5569.2  313.86  5717.6  314.31  5851.9  316.29  5926.5  318.25
#Mann=6,-1,0
  4279.9   0.013       0  4826.7    0.04       0  4994.8    0.04       0
  5000.7    0.04       0  5018.2    0.05       0  5208.5    0.04       0
Bank Sta=4994.8,5000.7
Exp/Cntr=0.3,0.1

Type RM Length L Ch R = 1,9357,281,281,281
BEGIN DESCRIPTION:
Mapping XS 02136df4
END DESCRIPTION:
XS GIS Cut Line= 4
      2422129.87     13530561.17      2421929.34     13530165.33
      2422002.26     13529779.91      2421379.91     13529102.88
#Sta/Elev= 30
  4440.0  321.36  4455.8  320.45  4559.0  316.85  4574.2  316.98  4635.1  314.26
  4760.8  310.10  4872.9  307.93  4904.4  307.93  4947.5  306.39  4985.8  303.73
  5003.2  301.82  5003.7  301.32  5008.7  301.32  5009.2  301.82  5045.2  305.48
  5081.3  307.42  5102.7  307.87  5230.1  307.60  5264.8  306.83  5311.7  307.10
  5376.9  306.82  5581.6  308.11  5609.9  308.44  5638.3  309.84  5857.8  311.53
  6027.9  315.26  6126.6  316.24  6148.2  317.11  6169.1  316.60  6195.6  316.99
#Mann=8,-1,0
  4440.0   0.013       0  4455.8    0.04       0  4635.1    0.05       0
  4947.5    0.04       0  5003.2    0.04       0  5009.2    0.04       0
  5081.3    0.05       0  5311.7    0.04       0
Bank Sta=5003.2,5009.2
Exp/Cntr=0.3,0.1

Type RM Length L Ch R = 1,9076,157,157,157
BEGIN DESCRIPTION:
Mapping XS 251da190
END DESCRIPTION:
XS GIS Cut Line= 4
      2422181.96     13530563.72      2422273.09     13530147.10
      2422036.11     13529735.64      2421476.23     13529076.80
#Sta/Elev= 30
  4449.2  320.57  4464.4  319.52  4509.3  318.38  4564.7  315.00  4662.9  311.32
  4720.0  310.14  4763.9  310.30  4785.7  309.26  4806.2  309.82  4836.9  308.53
  4963.3  306.05  4979.1  302.52  4981.9  300.86  4982.4  300.36  4987.9  300.86
  5022.2  301.86  5094.1  306.28  5095.3  306.31  5132.0  305.45  5211.0  306.38
  5332.9  306.20  5479.7  306.21  5557.7  307.74  5656.5  307.91  5685.1  309.18
  5805.9  309.85  5834.5  310.94  5926.8  311.87  6097.0  316.31  6215.1  317.98
#Mann=9,-1,0
  4449.2    0.04       0  4464.4   0.013       0  4564.7    0.04       0
  4981.9    0.04       0  4987.9    0.04       0  5094.1    0.05       0
  5095.3    0.04       0  5211.0    0.05       0  5332.9    0.04       0
Bank Sta=4981.9,4987.9
Exp/Cntr=0.3,0.1

Type RM Length L Ch R = 1,8919,380,380,380
BEGIN DESCRIPTION:
Mapping XS 8d1942a6
END DESCRIPTION:
XS GIS Cut Line= 4
      2422215.80     13530568.98      2422387.67     13530102.83
      2422236.63     13529665.33      2421536.59     13529009.53
#Sta/Elev= 30
  4368.1  320.15  4388.4  319.10  4459.7  315.45  4492.3  314.83  4550.9  312.02
  4596.3  310.72  4617.5  310.53  4672.7  308.37  4728.3  308.91  4777.4  307.16
  4920.0  306.11  4968.4  304.52  5028.9  300.36  5029.4  299.86  5034.4  299.86
  5034.9  300.36  5053.1  302.37  5084.8  302.91  5095.4  303.82  5107.1  305.78
  5127.1  306.91  5164.2  305.78  5211.6  305.35  5275.2  304.63  5422.3  304.63
  5668.9  306.58  5739.7  308.57  5831.5  308.81  5923.4  310.20  6287.0  318.69
#Mann=9,-1,0
  4368.1    0.04       0  4388.4   0.013       0  4459.7    0.04       0
  4492.3   0.013       0  4596.3    0.04       0  5028.9    0.04       0
  5034.9    0.04       0  5211.6    0.05       0  5422.3    0.04       0
Bank Sta=5028.9,5034.9
Exp/Cntr=0.3,0.1

Type RM Length L Ch R = 1,8539,490,490,490
BEGIN DESCRIPTION:
TRIB 9 TO SMITH CREEK 18.0
END DESCRIPTION:
XS GIS Cut Line= 3
      2422274.99     13530525.02      2422675.00     13529925.00
      2422324.97     13529374.96
#Sta/Elev= 30
  4315.1  316.43  4387.2  314.60  4400.2  313.17  4446.3  310.76  4516.4  309.61
  4631.5  307.54  4632.9  307.50  4743.8  305.75  4878.5  305.04  4971.6  301.58
  4986.7  300.44  5010.6  296.21  5011.1  295.71  5016.7  296.21  5043.9  299.75
  5049.8  298.23  5059.1  299.36  5065.0  298.09  5080.3  300.89  5086.2  300.10
  5174.2  305.32  5325.8  307.34  5333.8  306.71  5356.3  305.80  5391.8  306.38
  5456.2  305.42  5557.0  306.53  5617.0  307.94  5659.4  307.75  5688.2  309.32
#Mann=11,-1,0
  4315.1    0.04       0  4400.2   0.013       0  4446.3    0.04       0
  4516.4   0.013       0  4631.5    0.04       0  4632.9   0.013       0
  4743.8    0.04       0  5010.6    0.04       0  5016.7    0.04       0
  5333.8    0.05       0  5557.0    0.04       0
Bank Sta=5010.6,5016.7
Exp/Cntr=0.3,0.1

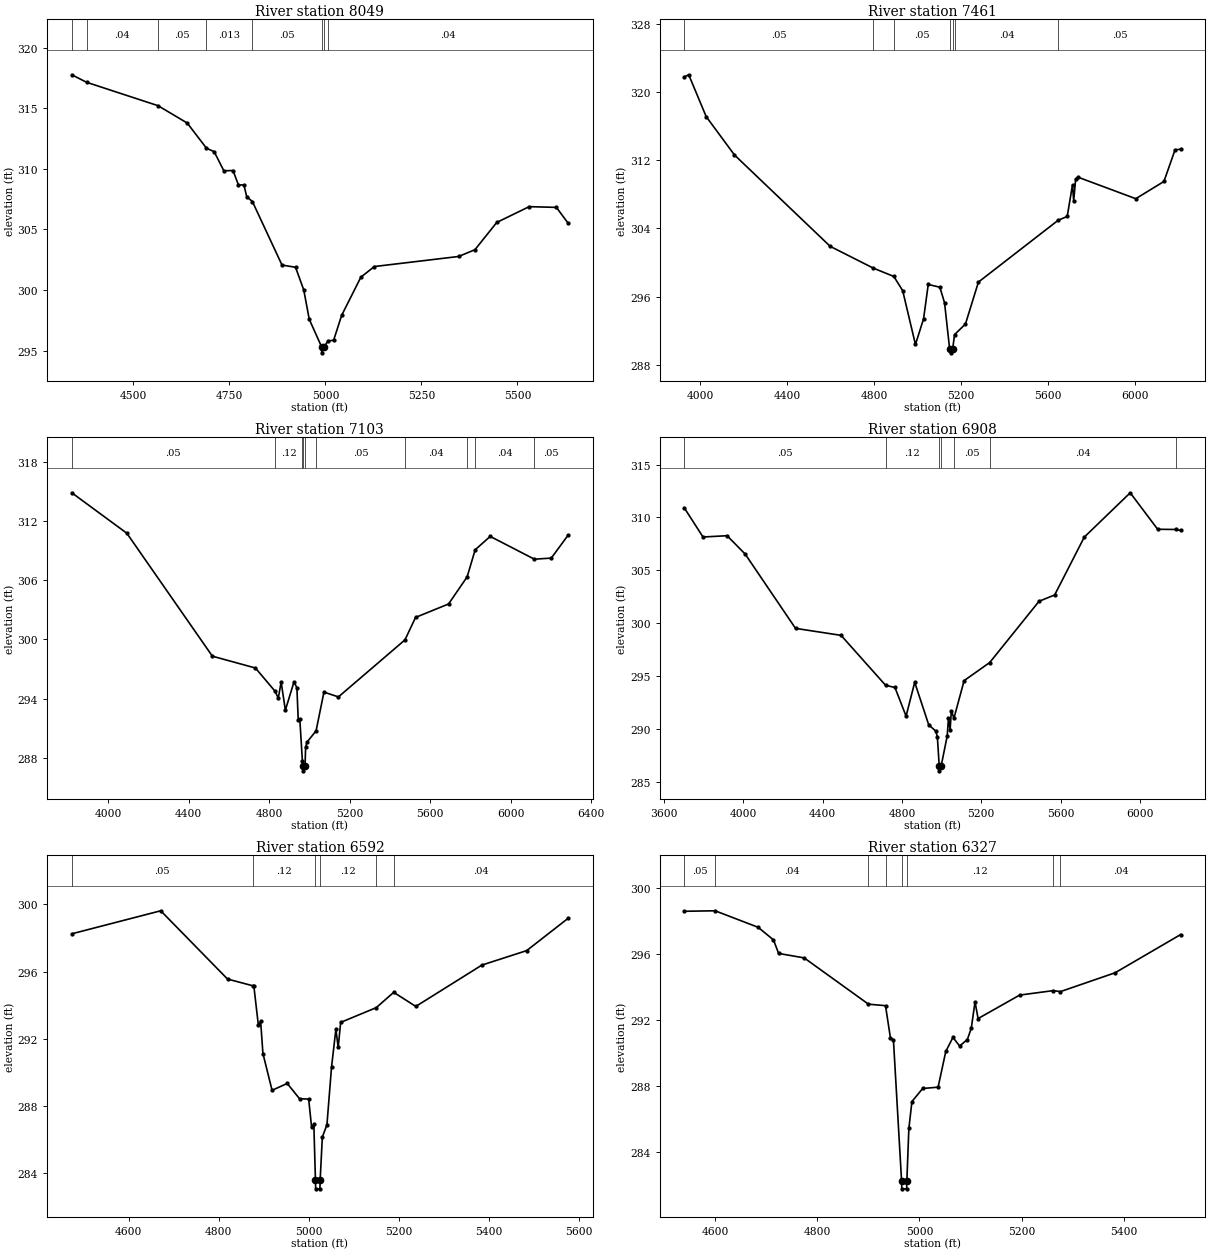
Type RM Length L Ch R = 1,8049,588,588,588
BEGIN DESCRIPTION:
Mapping XS 94e0e7c4
END DESCRIPTION:
XS GIS Cut Line= 3
      2423254.86     13530535.14      2423234.03     13530139.29
      2422628.28     13529478.94
#Sta/Elev= 30
  4339.3  317.76  4377.9  317.14  4563.9  315.21  4639.9  313.78  4690.1  311.70
  4710.0  311.42  4735.3  309.84  4759.2  309.86  4773.3  308.67  4787.5  308.67
  4794.9  307.70  4809.7  307.30  4886.8  302.06  4922.0  301.88  4943.5  300.00
  4957.7  297.59  4989.8  295.32  4990.3  294.82  4996.0  295.32  5006.9  295.80
  5021.2  295.86  5042.2  297.92  5092.1  301.06  5127.3  301.94  5346.8  302.77
  5389.3  303.33  5446.1  305.58  5530.5  306.88  5601.4  306.82  5631.8  305.52
#Mann=8,-1,0
  4339.3    0.05       0  4377.9    0.04       0  4563.9    0.05       0
  4690.1   0.013       0  4809.7    0.05       0  4989.8    0.05       0
  4996.0    0.05       0  5006.9    0.04       0
Bank Sta=4989.8,4996
Exp/Cntr=0.3,0.1

Type RM Length L Ch R = 1,7461,358,358,358
BEGIN DESCRIPTION:
Mapping XS fd4fc851
END DESCRIPTION:
XS GIS Cut Line= 5
      2423611.63     13530665.35      2423611.63     13529829.39
      2423455.38     13529561.16      2423207.99     13528936.16
      2422823.78     13528679.16
#Sta/Elev= 30
  3928.3  321.77  3948.6  322.01  4028.6  317.12  4158.6  312.62  4598.6  301.91
  4797.3  299.35  4891.2  298.38  4931.8  296.72  4990.5  290.41  5027.8  293.41
  5049.3  297.44  5102.8  297.12  5124.3  295.29  5147.4  289.94  5151.5  289.93
  5152.0  289.43  5161.7  289.93  5170.4  291.57  5220.4  292.81  5279.9  297.72
  5646.8  304.97  5688.0  305.41  5712.3  309.11  5717.7  307.22  5726.6  309.76
  5736.7  310.02  6003.1  307.49  6132.5  309.51  6183.6  313.22  6209.1  313.28
#Mann=7,-1,0
  3928.3    0.05       0  4797.3   0.013       0  4891.2    0.05       0
  5151.5    0.05       0  5161.7    0.05       0  5170.4    0.04       0
  5646.8    0.05       0
Bank Sta=5151.5,5161.7
Exp/Cntr=0.3,0.1

Type RM Length L Ch R = 1,7103,195,195,195
BEGIN DESCRIPTION:
Mapping XS eb5933a3
END DESCRIPTION:
XS GIS Cut Line= 5
      2424148.09     13530527.30      2424205.38     13529847.62
      2423291.32     13529097.62      2423231.42     13528904.91
      2422900.72     13528683.58
#Sta/Elev= 30
  3820.4  314.86  4093.7  310.76  4518.4  298.30  4732.3  297.10  4828.7  294.77
  4845.7  294.06  4860.0  295.67  4880.8  292.83  4923.9  295.71  4938.2  295.08
  4944.7  291.84  4952.6  291.92  4965.4  287.65  4968.3  287.18  4968.8  286.68
  4978.6  287.18  4981.3  289.05  4987.8  289.58  5033.3  290.73  5072.4  294.66
  5144.2  294.17  5474.6  299.95  5527.4  302.23  5691.1  303.59  5783.5  306.34
  5823.2  309.08  5898.0  310.44  6117.2  308.13  6201.2  308.24  6284.6  310.56
#Mann=10,-1,0
  3820.4    0.05       0  4828.7    0.12       0  4965.4   0.013       0
  4968.3    0.03       0  4978.6   0.013       0  5033.3    0.05       0
  5474.6    0.04       0  5783.5    0.05       0  5823.2    0.04       0
  6117.2    0.05       0
Bank Sta=4968.3,4978.6
Exp/Cntr=0.3,0.1

Type RM Length L Ch R = 1,6908,316,316,316
BEGIN DESCRIPTION:
Mapping XS 4353a7ce
END DESCRIPTION:
XS GIS Cut Line= 5
      2424288.71     13530537.77      2424413.72     13529787.72
      2423283.51     13528912.72      2423262.67     13528858.04
      2423054.32     13528714.79
#Sta/Elev= 30
  3703.5  310.90  3797.6  308.15  3919.2  308.27  4010.4  306.53  4263.9  299.51
  4493.4  298.85  4717.8  294.13  4765.0  293.92  4821.1  291.21  4864.6  294.41
  4935.2  290.39  4970.5  289.80  4978.7  289.27  4988.0  286.54  4988.5  286.04
  4998.3  286.54  5028.5  289.35  5034.8  291.04  5043.0  289.91  5049.3  291.73
  5062.3  291.01  5113.6  294.57  5242.7  296.28  5491.1  302.07  5569.9  302.67
  5719.3  308.14  5950.7  312.33  6089.0  308.88  6180.2  308.86  6204.6  308.77
#Mann=7,-1,0
  3703.5    0.05       0  4717.8    0.12       0  4988.0    0.05       0
  4998.3    0.12       0  5062.3    0.05       0  5242.7    0.04       0
  6180.2    0.05       0
Bank Sta=4988,4998.3
Exp/Cntr=0.3,0.1

Type RM Length L Ch R = 1,6592,265,265,265
BEGIN DESCRIPTION:
Mapping XS 7b3ec8d6
END DESCRIPTION:
XS GIS Cut Line= 5
      2424515.29     13529923.18      2424471.01     13529790.33
      2424309.55     13529634.08      2424221.01     13529134.08
      2424068.87     13528961.32
#Sta/Elev= 30
  4473.3  298.25  4670.9  299.62  4819.3  295.56  4875.3  295.16  4877.7  295.17
  4887.8  292.82  4892.9  293.04  4898.0  291.13  4918.3  288.94  4952.0  289.35
  4979.3  288.44  4999.6  288.42  5006.1  286.75  5011.1  286.92  5014.7  283.58
  5015.2  283.08  5024.6  283.08  5025.1  283.58  5030.0  286.16  5040.2  286.89
  5050.4  290.32  5060.1  292.57  5065.2  291.49  5070.7  292.98  5149.9  293.86
  5188.6  294.77  5237.6  293.93  5384.5  296.39  5484.0  297.25  5576.0  299.17
#Mann=6,-1,0
  4473.3    0.05       0  4875.3    0.12       0  5014.7    0.05       0
  5025.1    0.12       0  5149.9    0.05       0  5188.6    0.04       0
Bank Sta=5014.7,5025.1
Exp/Cntr=0.3,0.1

Type RM Length L Ch R = 1,6327,261,261,261
BEGIN DESCRIPTION:
Mapping XS 6ec4b947
END DESCRIPTION:
XS GIS Cut Line= 3
      2424577.78     13529889.33      2424567.36     13529550.75
      2424219.22     13529023.33
#Sta/Elev= 30
  4540.0  298.58  4600.2  298.61  4684.4  297.61  4714.4  296.85  4724.4  296.03
  4774.4  295.76  4900.2  292.96  4933.5  292.87  4943.1  290.93  4949.0  290.81
  4964.9  282.29  4965.4  281.79  4974.8  281.79  4975.3  282.29  4979.2  285.44
  4985.2  287.07  5006.2  287.86  5036.4  287.94  5051.4  290.10  5065.4  290.95
  5078.5  290.43  5093.6  290.82  5101.3  291.51  5108.6  293.10  5114.6  292.09
  5195.9  293.51  5261.5  293.78  5275.6  293.72  5382.6  294.86  5510.7  297.17
#Mann=8,-1,0
  4540.0    0.05       0  4600.2    0.04       0  4900.2    0.05       0
  4933.5    0.12       0  4964.9    0.05       0  4975.3    0.12       0
  5261.5    0.05       0  5275.6    0.04       0
Bank Sta=4964.9,4975.3
Exp/Cntr=0.3,0.1

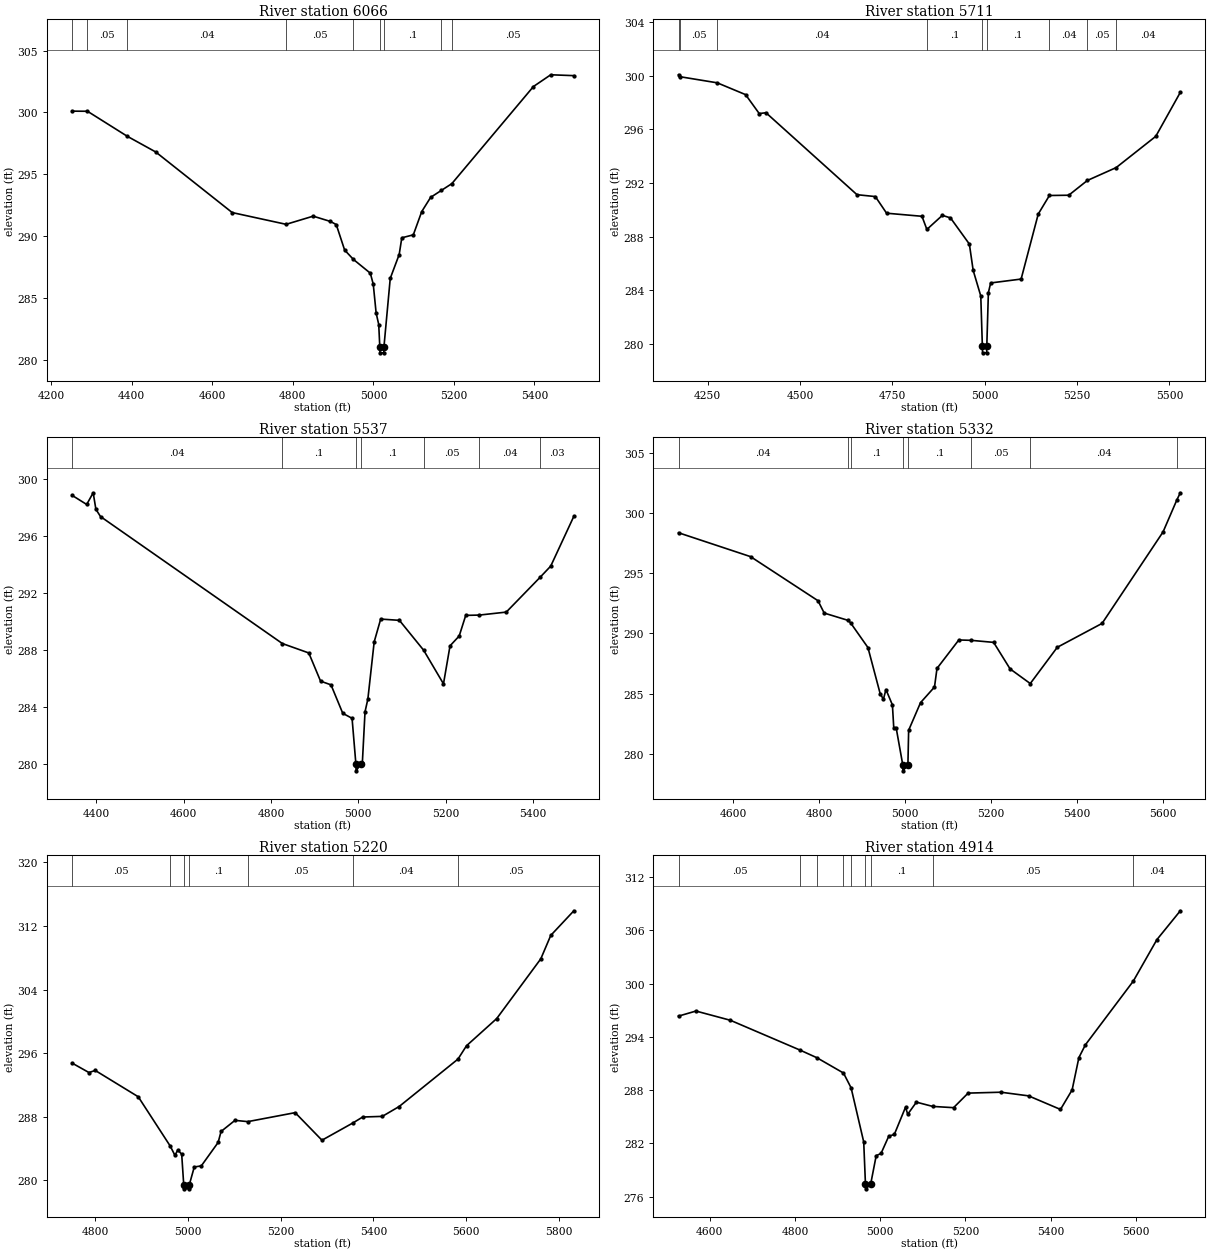
Type RM Length L Ch R = 1,6066,355,355,355
BEGIN DESCRIPTION:
Mapping XS fa6c03a7
END DESCRIPTION:
XS GIS Cut Line= 3
      2424806.95     13529972.66      2424796.53     13529399.70
      2424366.87     13528881.51
#Sta/Elev= 30
  4251.7  300.10  4290.0  300.09  4388.7  298.07  4459.4  296.80  4649.4  291.90
  4783.3  290.95  4850.5  291.61  4893.5  291.18  4907.8  290.93  4928.6  288.87
  4950.5  288.11  4992.4  287.00  4999.7  286.11  5006.8  283.79  5013.3  282.85
  5015.9  281.06  5016.4  280.56  5025.8  280.56  5026.3  281.06  5041.9  286.58
  5064.1  288.51  5070.6  289.86  5099.2  290.10  5120.1  291.98  5142.2  293.13
  5168.8  293.69  5194.9  294.24  5397.5  302.09  5440.5  303.04  5497.9  302.97
#Mann=9,-1,0
  4251.7    0.04       0  4290.0    0.05       0  4388.7    0.04       0
  4783.3    0.05       0  4950.5     0.1       0  5015.9    0.05       0
  5026.3     0.1       0  5168.8    0.12       0  5194.9    0.05       0
Bank Sta=5015.9,5026.3
Exp/Cntr=0.3,0.1

Type RM Length L Ch R = 1,5711,174,174,174
BEGIN DESCRIPTION:
Mapping XS a481ad26
END DESCRIPTION:
XS GIS Cut Line= 4
      2424879.87     13530040.29      2425002.26     13529318.97
      2425090.80     13528964.81      2425251.12     13528757.95
#Sta/Elev= 30
  4171.0  300.06  4176.3  299.91  4275.8  299.46  4352.5  298.58  4389.4  297.17
  4407.7  297.23  4654.1  291.12  4703.8  290.98  4734.2  289.74  4830.0  289.51
  4843.3  288.53  4885.2  289.58  4907.2  289.39  4958.3  287.44  4968.6  285.48
  4989.2  283.57  4993.5  279.83  4994.0  279.33  5005.0  279.33  5005.5  279.83
  5009.8  283.82  5016.0  284.54  5098.4  284.83  5144.8  289.68  5175.0  291.06
  5227.3  291.08  5277.7  292.18  5355.7  293.14  5462.9  295.47  5529.4  298.75
#Mann=9,-1,0
  4171.0    0.04       0  4176.3    0.05       0  4275.8    0.04       0
  4843.3     0.1       0  4993.5    0.05       0  5005.5     0.1       0
  5175.0    0.04       0  5277.7    0.05       0  5355.7    0.04       0
Bank Sta=4993.5,5005.5
Exp/Cntr=0.3,0.1

Type RM Length L Ch R = 1,5537,205,205,205
BEGIN DESCRIPTION:
Mapping XS 52c33ecc
END DESCRIPTION:
XS GIS Cut Line= 3
      2424934.56     13529886.65      2425101.22     13529402.31
      2425458.00     13528873.65
#Sta/Elev= 30
  4344.1  298.84  4377.6  298.20  4392.5  299.02  4398.7  297.86  4409.3  297.35
  4826.1  288.43  4886.6  287.77  4913.6  285.79  4937.5  285.53  4964.5  283.53
  4985.8  283.18  4994.5  279.99  4995.0  279.49  5006.5  279.99  5009.4  280.07
  5015.5  283.64  5022.0  284.53  5036.5  288.55  5051.4  290.15  5094.3  290.06
  5149.9  287.96  5195.3  285.60  5210.3  288.27  5231.3  288.96  5246.3  290.41
  5277.5  290.43  5339.2  290.64  5416.3  293.07  5441.1  293.87  5494.1  297.37
#Mann=7,-1,0
  4344.1    0.04       0  4826.1     0.1       0  4994.5    0.05       0
  5006.5     0.1       0  5149.9    0.05       0  5277.5    0.04       0
  5416.3    0.03       0
Bank Sta=4994.5,5006.5
Exp/Cntr=0.3,0.1

Type RM Length L Ch R = 1,5332,112,112,112
BEGIN DESCRIPTION:
Mapping XS 1bcb30f0
END DESCRIPTION:
XS GIS Cut Line= 3
      2425002.25     13529884.09      2425283.51     13529467.41
      2425595.69     13528879.47
#Sta/Elev= 30
  4472.3  298.39  4640.1  296.40  4797.0  292.73  4811.5  291.70  4867.3  291.09
  4872.8  290.89  4913.3  288.83  4941.7  285.00  4949.3  284.52  4955.3  285.33
  4970.3  284.05  4973.5  282.11  4979.2  282.11  4994.4  279.06  4994.9  278.56
  5006.4  279.06  5008.1  281.94  5035.8  284.24  5068.3  285.54  5074.1  287.09
  5124.9  289.46  5153.6  289.43  5206.0  289.26  5244.3  287.05  5291.3  285.83
  5354.2  288.85  5458.5  290.84  5600.5  298.46  5632.8  301.14  5640.7  301.72
#Mann=8,-1,0
  4472.3    0.04       0  4867.3    0.05       0  4872.8     0.1       0
  4994.4    0.05       0  5006.4     0.1       0  5153.6    0.05       0
  5291.3    0.04       0  5632.8    0.05       0
Bank Sta=4994.4,5006.4
Exp/Cntr=0.3,0.1

Type RM Length L Ch R = 1,5220,306,306,306
BEGIN DESCRIPTION:
TRIB 9 TO SMITH CREEK 11.0
END DESCRIPTION:
XS GIS Cut Line= 3
      2425225.03     13529724.97      2425375.00     13529525.00
      2425824.99     13528825.02
#Sta/Elev= 30
  4750.3  294.75  4786.7  293.56  4800.3  293.82  4893.0  290.51  4961.8  284.32
  4972.1  283.14  4978.4  283.81  4986.7  283.28  4991.1  279.42  4991.6  278.92
  5002.6  278.92  5003.1  279.42  5013.8  281.67  5029.0  281.81  5065.3  284.76
  5071.6  286.14  5101.6  287.54  5129.3  287.38  5231.4  288.51  5289.2  285.04
  5356.1  287.22  5377.0  287.96  5419.3  288.04  5455.6  289.28  5582.5  295.25
  5600.9  296.93  5666.0  300.35  5761.1  307.87  5782.6  310.82  5832.4  313.92
#Mann=7,-1,0
  4750.3    0.05       0  4961.8     0.1       0  4991.1    0.05       0
  5003.1     0.1       0  5129.3    0.05       0  5356.1    0.04       0
  5582.5    0.05       0
Bank Sta=4991.1,5003.1
Exp/Cntr=0.3,0.1

Type RM Length L Ch R = 1,4914,351,351,351
BEGIN DESCRIPTION:
Mapping XS e78410eb
END DESCRIPTION:
XS GIS Cut Line= 4
      2425567.37     13530045.50      2425632.47     13529582.00
      2425700.17     13529339.81      2425926.75     13528941.35
#Sta/Elev= 30
  4526.5  296.34  4567.4  296.91  4648.2  295.87  4812.3  292.50  4851.4  291.65
  4913.7  289.93  4931.6  288.26  4961.2  282.17  4965.3  277.39  4965.8  276.89
  4977.4  277.39  4990.5  280.63  5001.8  280.87  5020.0  282.82  5033.0  283.01
  5059.3  286.08  5064.5  285.29  5084.9  286.65  5123.2  286.17  5172.1  286.03
  5206.3  287.67  5283.2  287.77  5348.1  287.36  5423.1  285.83  5450.4  288.03
  5466.3  291.67  5481.6  293.11  5594.0  300.28  5649.4  304.95  5704.4  308.20
#Mann=9,-1,0
  4526.5    0.05       0  4812.3    0.04       0  4851.4    0.05       0
  4913.7    0.04       0  4931.6     0.1       0  4965.3    0.05       0
  4977.4     0.1       0  5123.2    0.05       0  5594.0    0.04       0
Bank Sta=4965.3,4977.4
Exp/Cntr=0.3,0.1