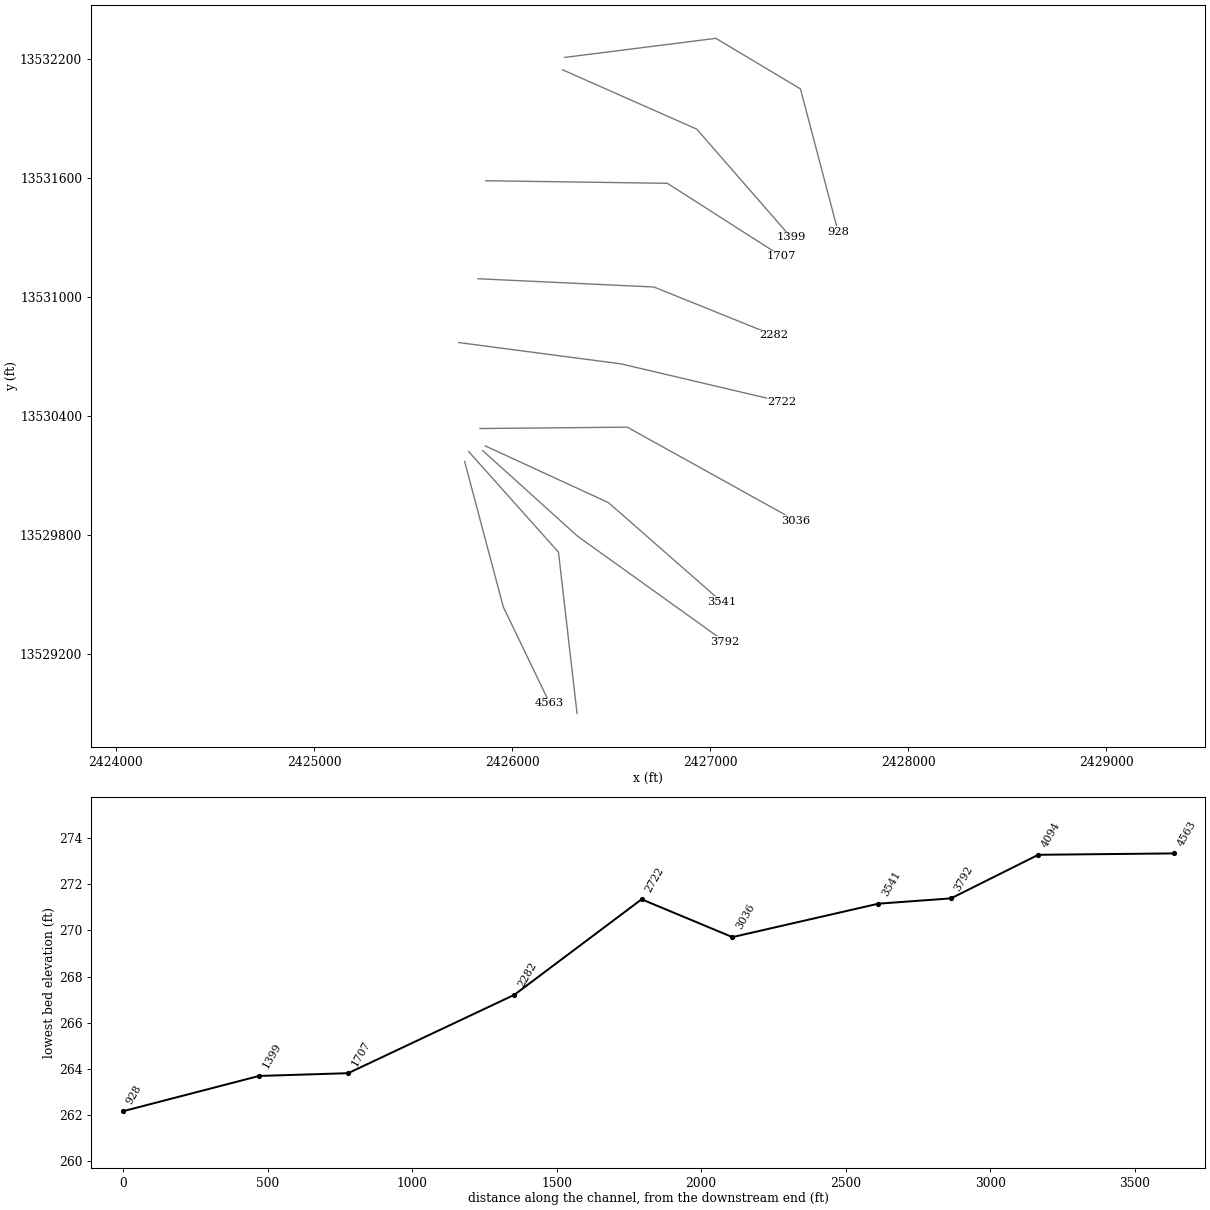
HEC-RAS study TRIB 9 TO SMITH CREEK.prj: TRIB 9 TO SMITH CREEK Base Level Engineering

--- TRIB 9 TO SMITH CREEK.g01 (geometry) --- (continued)

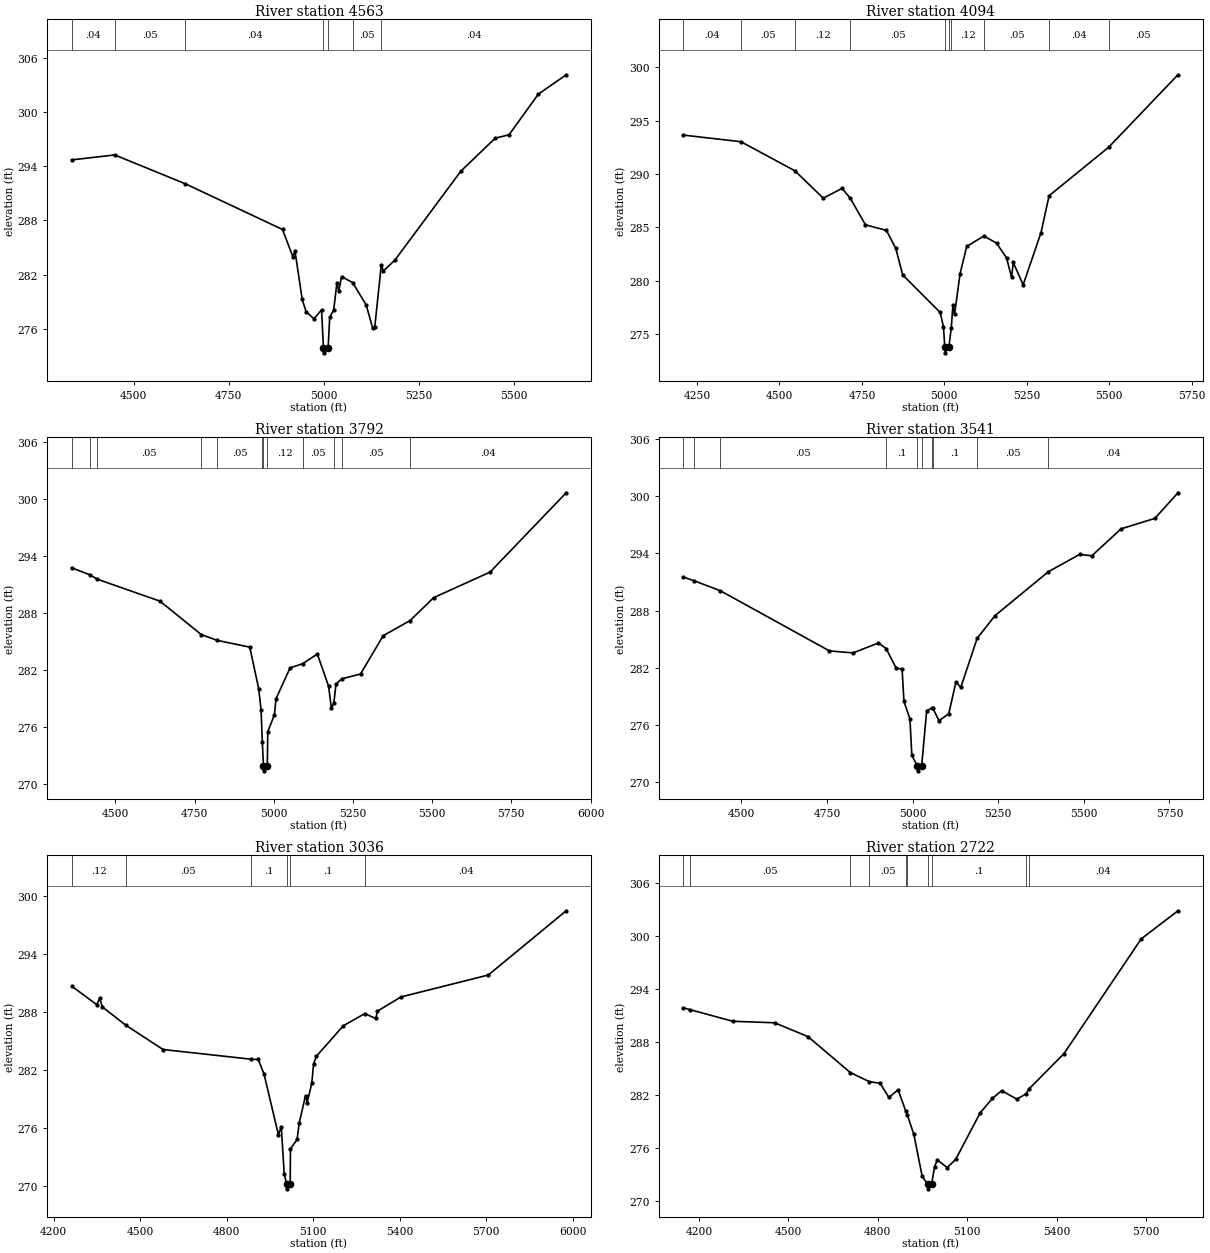
Type RM Length L Ch R = 1,4563,469,469,469
BEGIN DESCRIPTION:
Mapping XS 203bbde4
END DESCRIPTION:
XS GIS Cut Line= 3
      2425760.07     13530170.55      2425955.38     13529436.16
      2426189.56     13528949.60
#Sta/Elev= 30
  4337.2  294.69  4450.3  295.24  4636.2  292.04  4891.4  286.99  4918.9  283.94
  4924.1  284.64  4943.1  279.26  4953.5  277.88  4974.1  277.11  4994.0  278.09
  4999.1  273.84  4999.6  273.34  5011.2  273.84  5015.5  277.30  5025.9  278.05
  5034.2  281.02  5039.3  280.18  5046.6  281.77  5075.6  281.12  5111.4  278.64
  5128.5  276.07  5134.0  276.24  5151.1  283.07  5156.7  282.40  5187.2  283.62
  5360.3  293.45  5450.8  297.10  5486.8  297.47  5564.0  301.97  5637.1  304.11
#Mann=7,-1,0
  4337.2    0.04       0  4450.3    0.05       0  4636.2    0.04       0
  4999.1    0.04       0  5011.2    0.04       0  5075.6    0.05       0
  5151.1    0.04       0
Bank Sta=4999.1,5011.2
Exp/Cntr=0.3,0.1

Type RM Length L Ch R = 1,4094,302,302,302
BEGIN DESCRIPTION:
Mapping XS b2851fb5
END DESCRIPTION:
XS GIS Cut Line= 3
      2425780.91     13530220.01      2426234.03     13529712.20
      2426327.61     13528898.55
#Sta/Elev= 30
  4208.9  293.64  4383.3  293.02  4546.8  290.30  4632.9  287.74  4689.8  288.66
  4714.9  287.73  4760.8  285.25  4824.4  284.73  4852.8  283.04  4873.7  280.57
  4987.3  277.06  4997.4  275.71  5001.4  273.78  5001.9  273.28  5013.5  273.78
  5021.0  275.58  5025.9  277.71  5030.9  276.87  5047.7  280.67  5067.9  283.23
  5119.9  284.20  5158.4  283.54  5188.6  282.15  5204.0  280.34  5209.0  281.73
  5239.0  279.64  5293.1  284.51  5317.7  287.97  5498.2  292.50  5708.5  299.28
#Mann=10,-1,0
  4208.9    0.04       0  4383.3    0.05       0  4546.8    0.12       0
  4714.9    0.05       0  5001.4    0.05       0  5013.5    0.05       0
  5021.0    0.12       0  5119.9    0.05       0  5317.7    0.04       0
  5498.2    0.05       0
Bank Sta=5001.4,5013.5
Exp/Cntr=0.3,0.1

Type RM Length L Ch R = 1,3792,251,251,251
BEGIN DESCRIPTION:
Mapping XS b7bbc87c
END DESCRIPTION:
XS GIS Cut Line= 3
      2425851.23     13530225.21      2426330.38     13529792.93
      2427074.53     13529259.54
#Sta/Elev= 30
  4362.3  292.76  4420.2  292.02  4442.5  291.57  4641.1  289.25  4771.1  285.74
  4820.8  285.13  4924.4  284.41  4952.8  280.00  4960.0  277.81  4964.1  274.42
  4967.7  271.89  4968.2  271.39  4979.8  271.89  4981.2  275.51  5002.1  277.29
  5007.4  278.99  5051.7  282.23  5091.6  282.67  5137.7  283.69  5173.3  280.29
  5181.9  277.98  5189.9  278.54  5196.6  280.53  5215.1  281.08  5274.0  281.58
  5345.5  285.61  5430.5  287.21  5504.9  289.62  5683.0  292.31  5923.2  300.66
#Mann=12,-1,0
  4362.3    0.04       0  4420.2    0.12       0  4442.5    0.05       0
  4771.1    0.12       0  4820.8    0.05       0  4964.1    0.12       0
  4967.7    0.05       0  4979.8    0.12       0  5091.6    0.05       0
  5189.9    0.12       0  5215.1    0.05       0  5430.5    0.04       0
Bank Sta=4967.7,4979.8
Exp/Cntr=0.3,0.1

Type RM Length L Ch R = 1,3541,505,505,505
BEGIN DESCRIPTION:
Mapping XS 146082d6
END DESCRIPTION:
XS GIS Cut Line= 3
      2425864.22     13530248.67      2426486.63     13529962.20
      2427056.93     13529462.22
#Sta/Elev= 30
  4331.1  291.51  4362.6  291.12  4438.7  290.08  4757.1  283.76  4826.0  283.55
  4900.4  284.59  4922.7  284.01  4951.9  281.95  4969.3  281.85  4974.8  278.46
  4992.3  276.59  4997.8  272.79  5014.0  271.66  5014.5  271.16  5026.4  271.66
  5041.1  277.47  5057.8  277.79  5058.8  277.76  5077.1  276.43  5105.6  277.16
  5126.5  280.48  5140.7  279.93  5188.5  285.08  5240.2  287.45  5396.0  292.07
  5488.0  293.90  5523.2  293.75  5608.6  296.58  5707.3  297.68  5774.7  300.37
#Mann=10,-1,0
  4331.1    0.04       0  4362.6    0.12       0  4438.7    0.05       0
  4922.7     0.1       0  5014.0    0.05       0  5026.4     0.1       0
  5057.8    0.12       0  5058.8     0.1       0  5188.5    0.05       0
  5396.0    0.04       0
Bank Sta=5014,5026.4
Exp/Cntr=0.3,0.1

Type RM Length L Ch R = 1,3036,314,314,314
BEGIN DESCRIPTION:
Mapping XS c0660acf
END DESCRIPTION:
XS GIS Cut Line= 3
      2425838.17     13530336.34      2426581.25     13530343.28
      2427431.00     13529871.58
#Sta/Elev= 30
  4262.9  290.66  4349.7  288.75  4359.7  289.39  4369.7  288.50  4449.8  286.64
  4579.7  284.11  4885.0  283.11  4909.8  283.08  4929.8  281.59  4979.8  275.30
  4989.8  276.14  4999.8  271.29  5008.2  270.21  5008.7  269.71  5020.6  270.21
  5021.7  273.85  5044.6  274.81  5052.2  276.54  5073.9  279.35  5079.6  278.63
  5095.6  280.62  5101.8  282.61  5111.7  283.42  5204.7  286.56  5279.3  287.82
  5317.6  287.32  5323.3  288.08  5404.6  289.54  5707.8  291.81  5977.9  298.45
#Mann=6,-1,0
  4262.9    0.12       0  4449.8    0.05       0  4885.0     0.1       0
  5008.2    0.05       0  5020.6     0.1       0  5279.3    0.04       0
Bank Sta=5008.2,5020.6
Exp/Cntr=0.3,0.1

Type RM Length L Ch R = 1,2722,440,440,440
BEGIN DESCRIPTION:
Mapping XS c145e816
END DESCRIPTION:
XS GIS Cut Line= 3
      2425730.54     13530770.37      2426550.00     13530662.72
      2427361.30     13530472.04
#Sta/Elev= 30
  4147.7  291.88  4169.1  291.67  4313.6  290.35  4453.7  290.18  4565.7  288.61
  4707.6  284.54  4772.0  283.50  4807.8  283.32  4837.3  281.71  4868.3  282.58
  4893.8  280.16  4899.3  279.71  4921.1  277.52  4949.0  272.76  4967.8  271.85
  4968.3  271.35  4980.5  271.85  4990.4  273.84  4999.9  274.63  5032.8  273.75
  5061.5  274.69  5143.7  279.97  5184.8  281.61  5215.6  282.48  5267.0  281.52
  5298.8  282.15  5305.9  282.62  5424.7  286.67  5684.2  299.69  5807.6  302.88
#Mann=10,-1,0
  4147.7    0.04       0  4169.1    0.05       0  4707.6    0.12       0
  4772.0    0.05       0  4893.8    0.12       0  4899.3     0.1       0
  4967.8    0.05       0  4980.5     0.1       0  5298.8    0.05       0
  5305.9    0.04       0
Bank Sta=4967.8,4980.5
Exp/Cntr=0.3,0.1

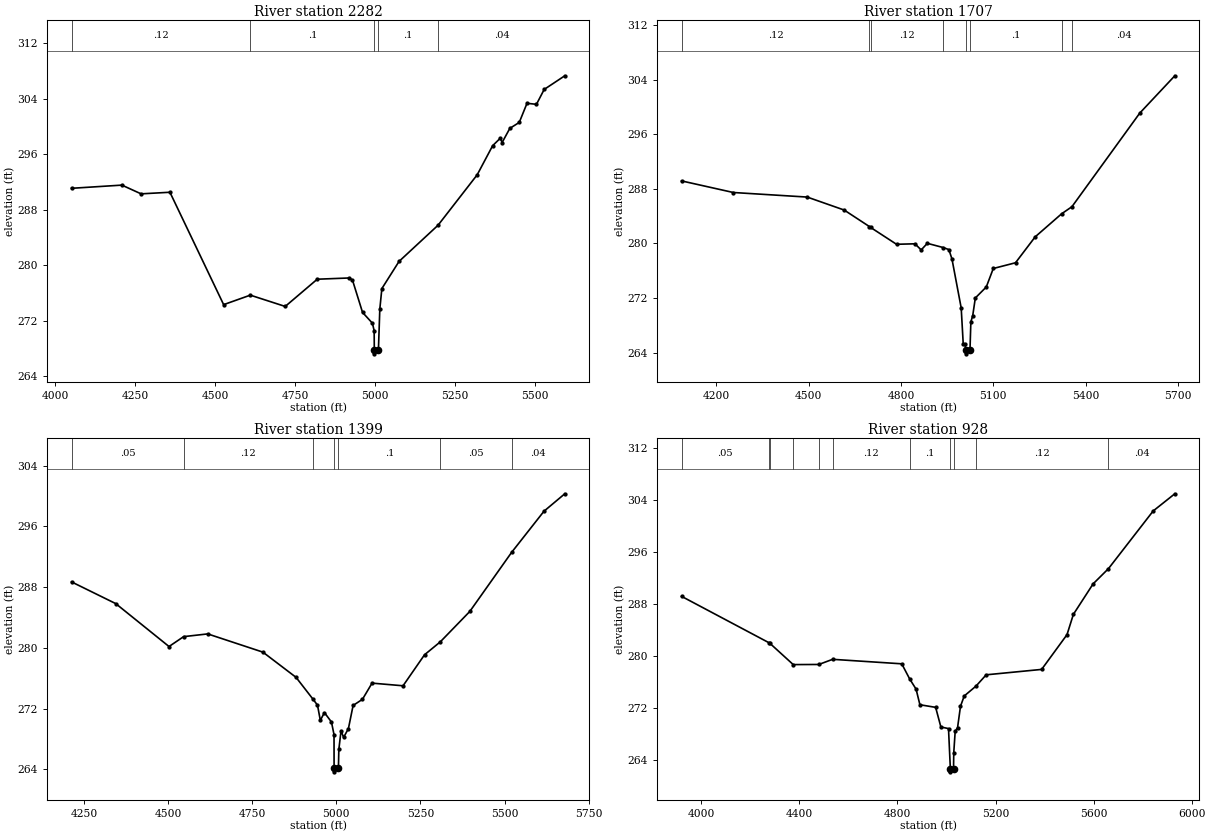
Type RM Length L Ch R = 1,2282,575,575,575
BEGIN DESCRIPTION:
Mapping XS 5f1b990e
END DESCRIPTION:
XS GIS Cut Line= 3
      2425827.74     13531092.41      2426715.80     13531050.75
      2427321.25     13530806.49
#Sta/Elev= 30
  4050.6  291.10  4208.0  291.56  4268.1  290.30  4358.2  290.53  4526.1  274.31
  4609.5  275.68  4718.6  274.05  4818.7  277.98  4918.8  278.16  4928.8  277.86
  4960.3  273.19  4991.2  271.63  4996.6  270.55  4997.1  267.71  4997.6  267.21
  5009.9  267.71  5014.3  273.68  5020.7  276.63  5074.4  280.55  5196.3  285.77
  5318.7  293.05  5367.0  297.25  5391.1  298.34  5396.5  297.70  5420.7  299.75
  5450.2  300.61  5474.4  303.37  5503.9  303.22  5528.1  305.37  5592.5  307.34
#Mann=5,-1,0
  4050.6    0.12       0  4609.5     0.1       0  4997.1    0.05       0
  5009.9     0.1       0  5196.3    0.04       0
Bank Sta=4997.1,5009.9
Exp/Cntr=0.3,0.1

Type RM Length L Ch R = 1,1707,308,308,308
BEGIN DESCRIPTION:
Mapping XS b15eeae3
END DESCRIPTION:
XS GIS Cut Line= 3
      2425866.83     13531587.20      2426783.51     13531574.18
      2427360.83     13531204.90
#Sta/Elev= 30
  4087.5  289.16  4255.7  287.46  4495.7  286.79  4615.7  284.89  4697.9  282.46
  4701.6  282.34  4785.7  279.87  4845.7  279.94  4865.8  279.04  4885.8  280.01
  4938.3  279.38  4955.8  279.09  4965.8  277.72  4995.8  270.54  5002.5  265.18
  5008.1  265.18  5011.5  264.31  5012.0  263.81  5024.3  264.31  5027.2  268.50
  5033.2  269.40  5041.7  272.00  5077.3  273.61  5100.0  276.32  5172.2  277.16
  5236.1  280.96  5322.0  284.34  5355.5  285.38  5575.8  299.10  5689.6  304.57
#Mann=8,-1,0
  4087.5    0.12       0  4697.9     0.1       0  4701.6    0.12       0
  4938.3     0.1       0  5011.5    0.05       0  5024.3     0.1       0
  5322.0    0.05       0  5355.5    0.04       0
Bank Sta=5011.5,5024.3
Exp/Cntr=0.3,0.1

Type RM Length L Ch R = 1,1399,471,471,471
BEGIN DESCRIPTION:
Mapping XS db02d057
END DESCRIPTION:
XS GIS Cut Line= 3
      2426254.86     13532147.10      2426931.95     13531847.62
      2427408.48     13531300.78
#Sta/Elev= 30
  4213.1  288.70  4344.5  285.84  4502.8  280.19  4546.2  281.49  4617.8  281.85
  4781.8  279.45  4880.3  276.13  4929.3  273.33  4944.0  272.47  4952.4  270.47
  4964.6  271.49  4985.5  270.25  4993.1  268.59  4993.3  264.19  4993.8  263.69
  5006.2  264.19  5007.4  266.64  5014.0  269.11  5021.6  268.22  5035.9  269.39
  5049.8  272.43  5077.6  273.24  5106.1  275.37  5198.2  275.02  5262.0  279.10
  5309.0  280.81  5396.6  284.81  5520.7  292.58  5616.9  298.00  5678.8  300.30
#Mann=7,-1,0
  4213.1    0.05       0  4546.2    0.12       0  4929.3     0.1       0
  4993.3    0.05       0  5006.2     0.1       0  5309.0    0.05       0
  5520.7    0.04       0
Bank Sta=4993.3,5006.2
Exp/Cntr=0.3,0.1

Type RM Length L Ch R = 1,928,0,0,0
BEGIN DESCRIPTION:
Mapping XS 9279bf04
END DESCRIPTION:
XS GIS Cut Line= 4
      2426265.27     13532209.60      2427028.30     13532305.95
      2427455.38     13532050.75      2427645.41     13531329.68
#Sta/Elev= 30
  3919.0  289.13  4276.2  281.99  4278.2  281.95  4374.7  278.64  4479.1  278.66
  4535.4  279.45  4817.4  278.76  4849.7  276.43  4875.8  274.87  4891.4  272.47
  4955.6  272.07  4977.0  269.05  5008.1  268.81  5015.6  262.66  5016.1  262.16
  5028.6  262.66  5029.5  265.08  5035.3  268.36  5045.1  268.97  5057.0  272.24
  5072.3  273.82  5120.1  275.33  5161.8  277.07  5388.0  277.90  5491.5  283.24
  5517.5  286.36  5598.1  291.05  5660.7  293.39  5843.1  302.25  5931.3  304.89
#Mann=11,-1,0
  3919.0    0.05       0  4276.2    0.12       0  4278.2    0.05       0
  4374.7    0.12       0  4479.1    0.05       0  4535.4    0.12       0
  4849.7     0.1       0  5015.6    0.05       0  5028.6     0.1       0
  5120.1    0.12       0  5660.7    0.04       0
Bank Sta=5015.6,5028.6
Exp/Cntr=0.3,0.1

Chan Stop Cuts=-1