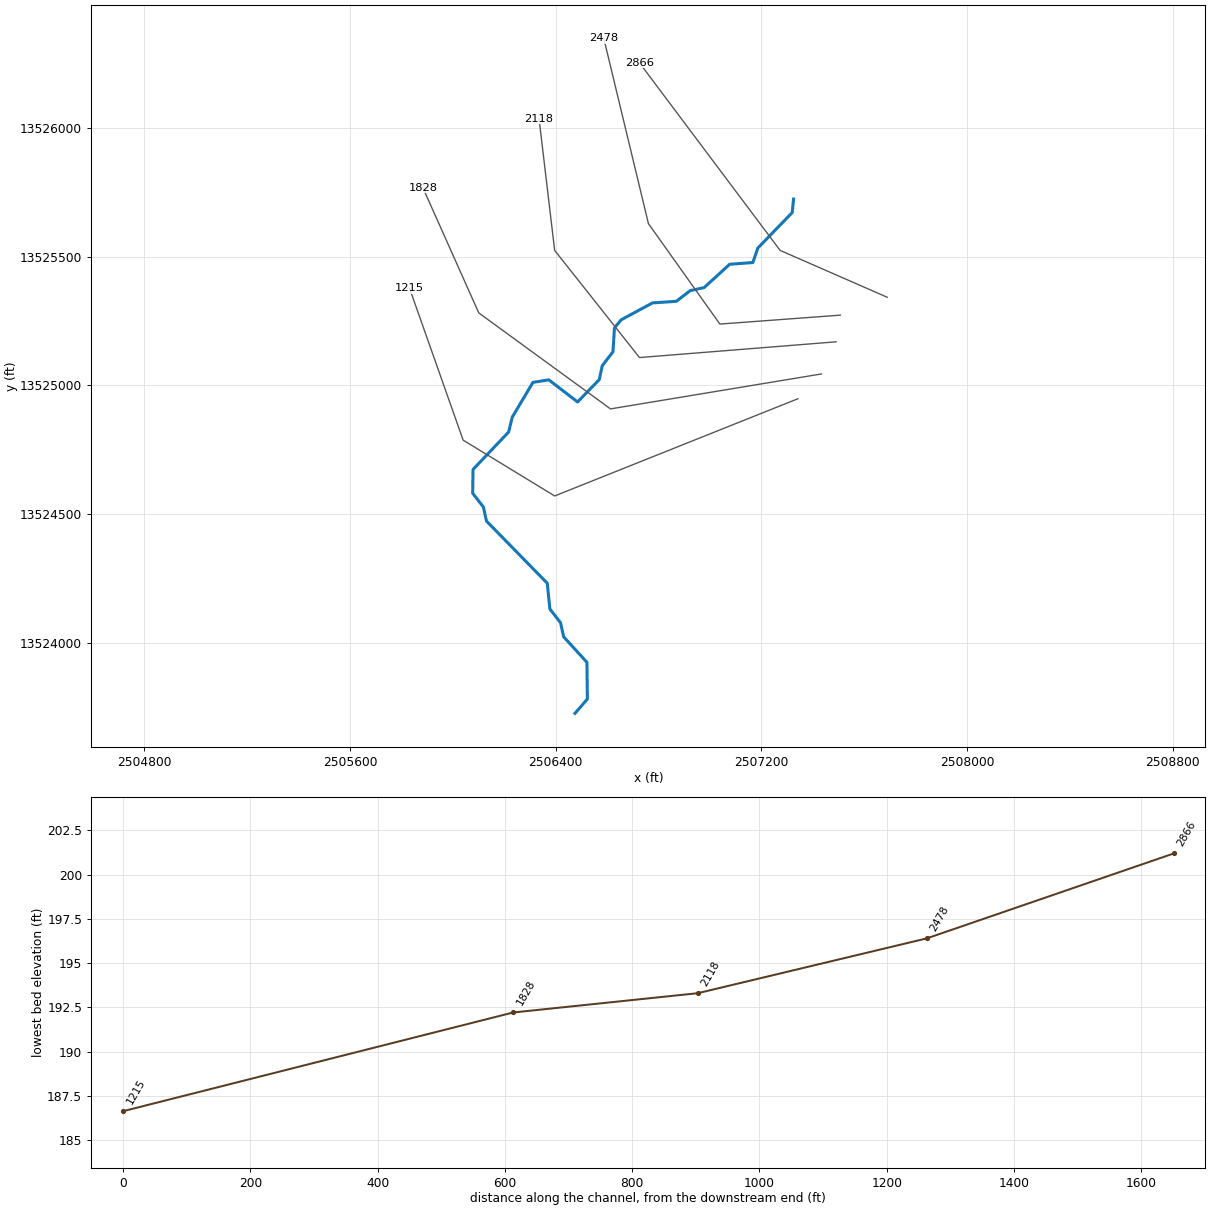
--- TRIB 9 TO TWELVEMILE CREEK.prj (project) ---

Proj Title=TRIB 9 TO TWELVEMILE CREEK Base Level Engineering
Current Plan=p01
Default Exp/Contr=0.3,0.1
English Units
Geom File=g01
Flow File=f01
Plan File=p01
BEGIN DESCRIPTION:
TRIB 9 TO TWELVEMILE CREEK
END DESCRIPTION:

--- TRIB 9 TO TWELVEMILE CREEK.p01 (plan) ---

Plan Title=Multiple Run
Short Identifier=Multiple
Geom File=g01
Flow File=f01
Subcritical Flow
K Sum by GR= 0
Std Step Tol= 0.01
Critical Tol= 0.01
Num of Std Step Trials= 20
Max Error Tol= 0.3
Flow Tol Ratio= 0.001
Split Flow NTrial= 30
Split Flow Tol= 0.02
Split Flow Ratio= 0.02
Log Output Level= 0
Friction Slope Method= 1
Unsteady Friction Slope Method= 2
Unsteady Bridges Friction Slope Method= 1
Parabolic Critical Depth
Global Vel Dist=  1 , 1 , 1
Global Log Level= 0
CheckData=True
Encroach Param= -1, 0, 0, 0
BEGIN DESCRIPTION:
Multiple Run
END DESCRIPTION:

--- TRIB 9 TO TWELVEMILE CREEK.f01 (steady flow) ---

Flow Title=Multiple
Number of Profiles=7
Profile Names=10-year,25-year,50-year,1pct_min,100-year,1pct_plu,500-year
River Rch & RM= TRIB 9 TO TWELVE,Reach-1,2866
     440     691     911     583    1164    2322    1874
River Rch & RM= TRIB 9 TO TWELVE,Reach-1,1215
     458     721     954     611    1219    2433    1971
Boundary for River Rch & Prof#=TRIB 9 TO TWELVE,Reach-1,1
Up Type=0
Dn Type=3
Dn Slope=0.005
Boundary for River Rch & Prof#=TRIB 9 TO TWELVE,Reach-1,2
Up Type=0
Dn Type=3
Dn Slope=0.005
Boundary for River Rch & Prof#=TRIB 9 TO TWELVE,Reach-1,3
Up Type=0
Dn Type=3
Dn Slope=0.005
Boundary for River Rch & Prof#=TRIB 9 TO TWELVE,Reach-1,4
Up Type=0
Dn Type=3
Dn Slope=0.005
Boundary for River Rch & Prof#=TRIB 9 TO TWELVE,Reach-1,5
Up Type=0
Dn Type=3
Dn Slope=0.005
Boundary for River Rch & Prof#=TRIB 9 TO TWELVE,Reach-1,6
Up Type=0
Dn Type=3
Dn Slope=0.005
Boundary for River Rch & Prof#=TRIB 9 TO TWELVE,Reach-1,7
Up Type=0
Dn Type=3
Dn Slope=0.005

--- TRIB 9 TO TWELVEMILE CREEK.g01 (geometry) ---

Geom Title=Existing Conditions

River Reach=TRIB 9 TO TWELVE,Reach-1
Reach XY= 30
      2507325.00     13525725.00      2507319.69     13525672.48
      2507185.90     13525534.38      2507166.66     13525478.17
      2507076.57     13525471.35      2506977.29     13525380.85
      2506922.83     13525368.86      2506869.03     13525327.33
      2506776.58     13525321.18      2506654.43     13525255.42
      2506628.52     13525223.72      2506622.66     13525130.97
      2506581.14     13525077.17      2506569.17     13525022.67
      2506485.02     13524935.95      2506373.32     13525021.89
      2506311.44     13525012.04      2506231.10     13524877.19
      2506216.86     13524818.94      2506078.46     13524673.50
      2506077.14     13524580.97      2506118.85     13524527.17
      2506130.83     13524472.70      2506367.14     13524231.17
      2506377.33     13524130.97      2506418.86     13524077.17
      2506430.85     13524022.71      2506521.46     13523923.53
      2506523.12     13523780.79      2506475.00     13523725.00

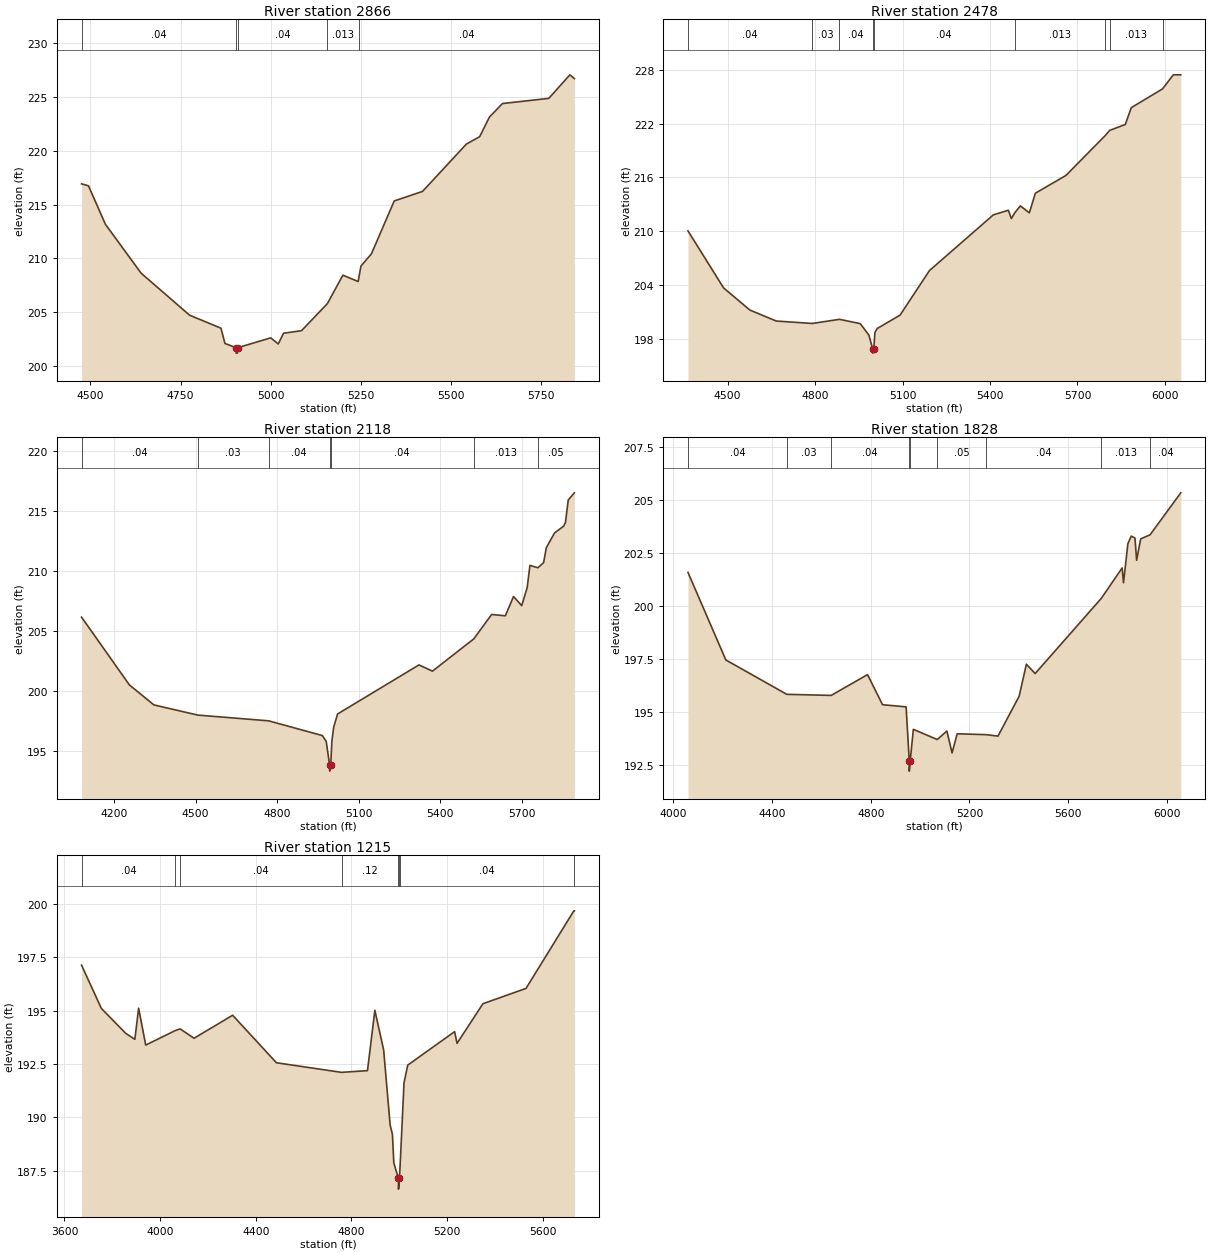
Type RM Length L Ch R = 1,2866,388,388,388
BEGIN DESCRIPTION:
LGII4571
END DESCRIPTION:
XS GIS Cut Line= 3
      2507689.31     13525343.05      2507272.69     13525525.33
      2506725.82     13526254.49
#Sta/Elev= 30
  4475.6  216.94  4494.8  216.76  4541.6  213.19  4640.6  208.64  4775.0  204.73
  4862.0  203.52  4873.2  202.10  4904.0  201.70  4904.2  201.20  4907.7  201.20
  4908.0  201.70  5000.1  202.62  5020.9  202.05  5035.5  203.05  5085.5  203.29
  5157.2  205.81  5200.1  208.45  5242.4  207.86  5244.8  208.31  5250.1  209.29
  5279.3  210.44  5342.4  215.35  5420.9  216.24  5542.4  220.64  5579.3  221.33
  5606.3  223.15  5642.4  224.41  5770.9  224.89  5829.3  227.08  5841.8  226.73
#Mann=5,-1,0
  4475.6    0.04       0  4904.0    0.04       0  4908.0    0.04       0
  5157.2   0.013       0  5244.8    0.04       0
Bank Sta=4904,4908
Exp/Cntr=0.3,0.1

Type RM Length L Ch R = 1,2478,360,360,360
BEGIN DESCRIPTION:
LGII4570
END DESCRIPTION:
XS GIS Cut Line= 4
      2507507.10     13525273.59      2507038.31     13525238.87
      2506760.53     13525629.49      2506586.92     13526349.97
#Sta/Elev= 30
  4363.9  210.04  4486.3  203.67  4576.6  201.20  4666.8  199.98  4790.3  199.71
  4883.7  200.17  4955.0  199.69  4984.5  198.41  4997.3  196.90  4997.5  196.40
  5001.3  196.90  5005.4  198.73  5013.3  199.15  5091.5  200.64  5192.3  205.61
  5411.5  211.83  5463.0  212.34  5473.3  211.41  5484.7  212.05  5504.1  212.83
  5535.0  212.05  5555.5  214.24  5660.3  216.22  5794.9  220.66  5810.3  221.25
  5864.1  221.91  5884.7  223.79  5991.8  225.88  6028.7  227.45  6054.4  227.45
#Mann=9,-1,0
  4363.9    0.04       0  4790.3    0.03       0  4883.7    0.04       0
  4997.3    0.04       0  5001.3    0.04       0  5484.7   0.013       0
  5794.9   0.075       0  5810.3   0.013       0  5991.8    0.04       0
Bank Sta=4997.3,5001.3
Exp/Cntr=0.3,0.1

Type RM Length L Ch R = 1,2118,290,290,290
BEGIN DESCRIPTION:
LGII4569
END DESCRIPTION:
XS GIS Cut Line= 4
      2507490.41     13525169.86      2506725.81     13525108.66
      2506395.95     13525525.33      2506335.19     13526037.46
#Sta/Elev= 30
  4080.1  206.16  4256.1  200.50  4346.4  198.83  4507.9  197.98  4768.8  197.50
  4966.5  196.27  4980.9  195.78  4993.3  193.80  4993.6  193.30  4997.3  193.80
  5001.7  195.82  5008.3  196.97  5022.5  198.07  5322.2  202.17  5371.9  201.65
  5523.9  204.34  5589.7  206.38  5640.1  206.27  5670.3  207.88  5700.5  207.12
  5720.6  208.63  5730.7  210.48  5759.9  210.28  5781.0  210.71  5791.1  211.96
  5821.3  213.19  5855.0  213.76  5861.6  214.08  5871.7  215.94  5894.3  216.54
#Mann=7,-1,0
  4080.1    0.04       0  4507.9    0.03       0  4768.8    0.04       0
  4993.3    0.04       0  4997.3    0.04       0  5523.9   0.013       0
  5759.9    0.05       0
Bank Sta=4993.3,4997.3
Exp/Cntr=0.3,0.1

Type RM Length L Ch R = 1,1828,613,613,613
BEGIN DESCRIPTION:
LGII4568
END DESCRIPTION:
XS GIS Cut Line= 4
      2507433.07     13525044.86      2506612.96     13524909.01
      2506100.81     13525282.27      2505883.79     13525768.41
#Sta/Elev= 30
  4059.1  201.58  4212.7  197.45  4459.8  195.83  4639.7  195.78  4787.0  196.76
  4847.8  195.34  4943.3  195.24  4956.0  192.71  4956.2  192.21  4960.0  192.71
  4972.6  194.18  5069.6  193.70  5108.6  194.10  5129.5  193.07  5150.3  193.97
  5266.9  193.93  5315.6  193.86  5401.4  195.74  5430.8  197.25  5466.3  196.81
  5734.1  200.35  5818.9  201.79  5824.4  201.09  5842.1  202.93  5855.6  203.29
  5870.8  203.20  5877.6  202.15  5894.0  203.16  5932.0  203.35  6056.5  205.33
#Mann=9,-1,0
  4059.1    0.04       0  4459.8    0.03       0  4639.7    0.04       0
  4956.0    0.04       0  4960.0    0.04       0  5069.6    0.05       0
  5266.9    0.04       0  5734.1   0.013       0  5932.0    0.04       0
Bank Sta=4956,4960
Exp/Cntr=0.3,0.1

Type RM Length L Ch R = 1,1215,0,0,0
BEGIN DESCRIPTION:
LGII4567
END DESCRIPTION:
XS GIS Cut Line= 4
      2507341.96     13524948.52      2506395.95     13524570.46
      2506040.05     13524787.48      2505831.70     13525377.79
#Sta/Elev= 30
  3671.5  197.14  3754.4  195.11  3856.4  193.94  3894.4  193.66  3910.3  195.12
  3939.9  193.39  4063.4  194.07  4084.1  194.15  4142.1  193.71  4303.6  194.79
  4486.7  192.56  4759.2  192.11  4867.6  192.19  4898.5  195.02  4935.3  193.16
  4962.4  189.64  4972.0  189.20  4977.9  187.85  4997.2  187.13  4997.5  186.63
  5001.2  187.13  5003.9  187.67  5020.5  191.62  5036.0  192.45  5232.2  194.02
  5242.3  193.47  5350.6  195.33  5530.9  196.05  5730.9  199.69  5733.1  199.69
#Mann=8,-1,0
  3671.5    0.04       0  4063.4    0.03       0  4084.1    0.04       0
  4759.2    0.12       0  4997.2    0.05       0  5001.2    0.12       0
  5003.9    0.04       0  5730.9   0.013       0
Bank Sta=4997.2,5001.2
Exp/Cntr=0.3,0.1

Chan Stop Cuts=-1