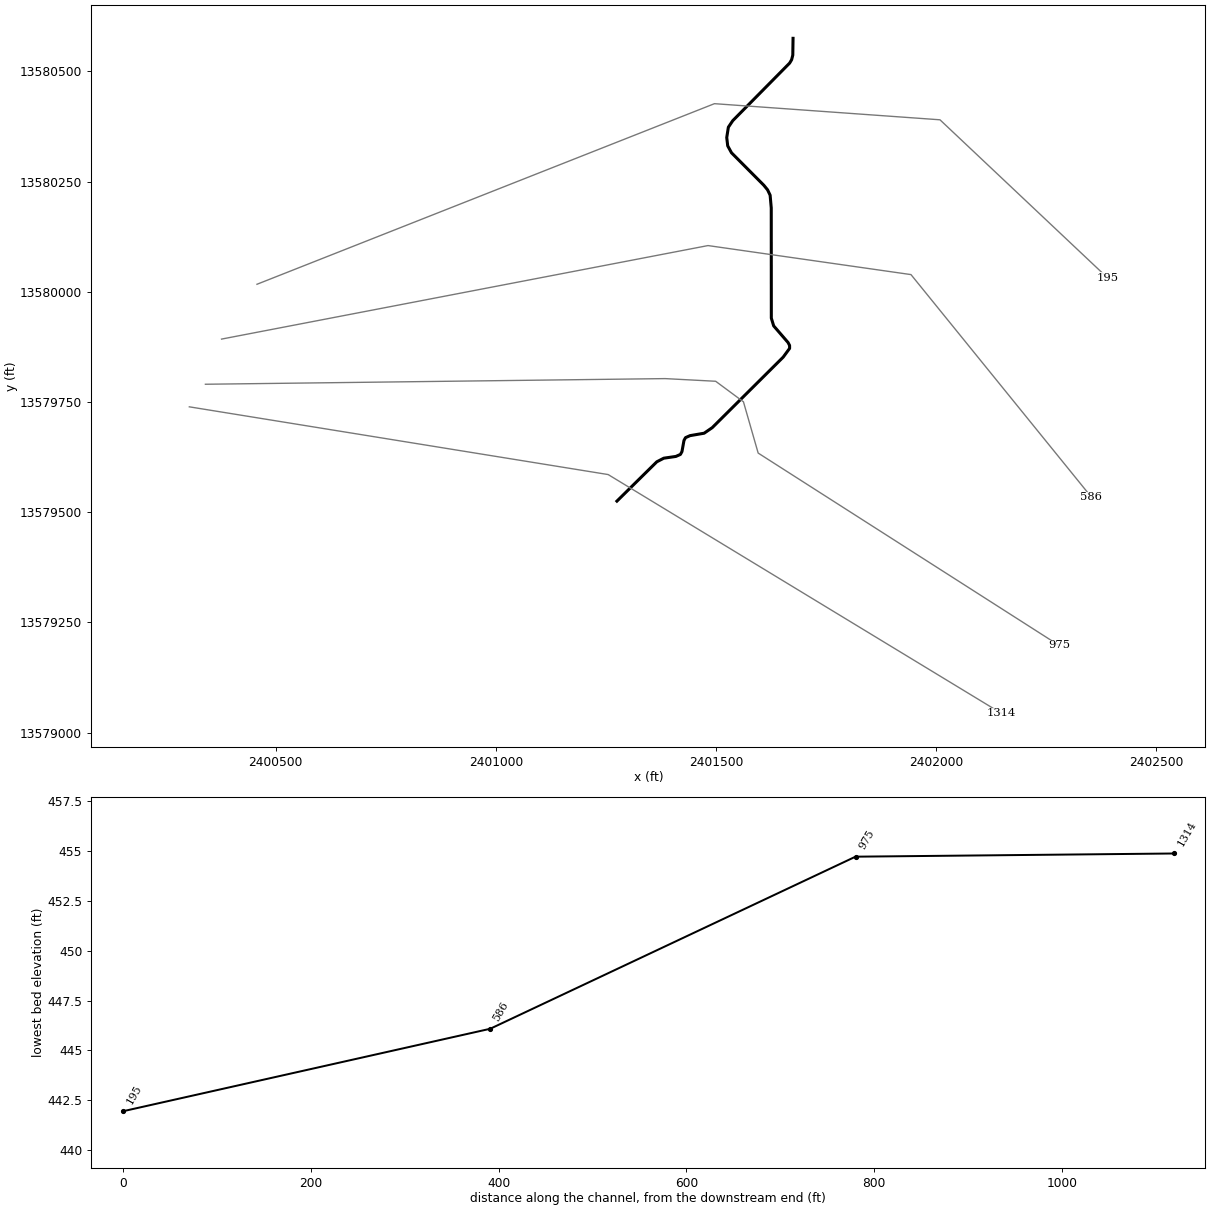
--- TRIB 9_1 TO SALT CREEK.prj (project) ---

Proj Title=TRIB 9_1 TO SALT CREEK Base Level Engineering
Current Plan=p01
Default Exp/Contr=0.3,0.1
English Units
Geom File=g01
Flow File=f01
Plan File=p01
BEGIN DESCRIPTION:
TRIB 9_1 TO SALT CREEK
END DESCRIPTION:

--- TRIB 9_1 TO SALT CREEK.p01 (plan) ---

Plan Title=Multiple Run
Short Identifier=Multiple
Geom File=g01
Flow File=f01
Subcritical Flow
K Sum by GR= 0
Std Step Tol= 0.01
Critical Tol= 0.01
Num of Std Step Trials= 20
Max Error Tol= 0.3
Flow Tol Ratio= 0.001
Split Flow NTrial= 30
Split Flow Tol= 0.02
Split Flow Ratio= 0.02
Log Output Level= 0
Friction Slope Method= 1
Unsteady Friction Slope Method= 2
Unsteady Bridges Friction Slope Method= 1
Parabolic Critical Depth
Global Vel Dist=  1 , 1 , 1
Global Log Level= 0
CheckData=True
Encroach Param= -1, 0, 0, 0
BEGIN DESCRIPTION:
Multiple Run
END DESCRIPTION:

--- TRIB 9_1 TO SALT CREEK.f01 (steady flow) ---

Flow Title=Multiple
Number of Profiles=7
Profile Names=10-year,25-year,50-year,1pct_min,100-year,1pct_plu,500-year
River Rch & RM= TRIB 9_1 TO SALT,Reach-1,1314
     280     438     577     370     739    1474    1195
Boundary for River Rch & Prof#=TRIB 9_1 TO SALT,Reach-1,1
Up Type=0
Dn Type=3
Dn Slope=0.005
Boundary for River Rch & Prof#=TRIB 9_1 TO SALT,Reach-1,2
Up Type=0
Dn Type=3
Dn Slope=0.005
Boundary for River Rch & Prof#=TRIB 9_1 TO SALT,Reach-1,3
Up Type=0
Dn Type=3
Dn Slope=0.005
Boundary for River Rch & Prof#=TRIB 9_1 TO SALT,Reach-1,4
Up Type=0
Dn Type=3
Dn Slope=0.005
Boundary for River Rch & Prof#=TRIB 9_1 TO SALT,Reach-1,5
Up Type=0
Dn Type=3
Dn Slope=0.005
Boundary for River Rch & Prof#=TRIB 9_1 TO SALT,Reach-1,6
Up Type=0
Dn Type=3
Dn Slope=0.005
Boundary for River Rch & Prof#=TRIB 9_1 TO SALT,Reach-1,7
Up Type=0
Dn Type=3
Dn Slope=0.005

--- TRIB 9_1 TO SALT CREEK.g01 (geometry) ---

Geom Title=Existing Conditions

River Reach=TRIB 9_1 TO SALT,Reach-1
Reach XY= 30
      2401275.00     13579525.00      2401365.56     13579614.21
      2401381.41     13579622.40      2401408.87     13579626.39
      2401419.24     13579630.97      2401422.72     13579637.41
      2401427.28     13579662.59      2401430.77     13579669.02
      2401441.14     13579673.59      2401473.02     13579679.05
      2401491.49     13579691.71      2401652.55     13579851.64
      2401667.21     13579871.58      2401667.13     13579878.21
      2401663.67     13579884.84      2401631.03     13579922.55
      2401625.66     13579940.16      2401625.49     13580190.20
      2401622.93     13580219.14      2401617.17     13580231.19
      2401608.53     13580241.75      2401535.20     13580315.33
      2401526.59     13580331.05      2401524.41     13580350.00
      2401528.10     13580373.35      2401538.11     13580388.21
      2401667.24     13580518.79      2401671.73     13580526.36
      2401674.41     13580536.84      2401675.00     13580575.00

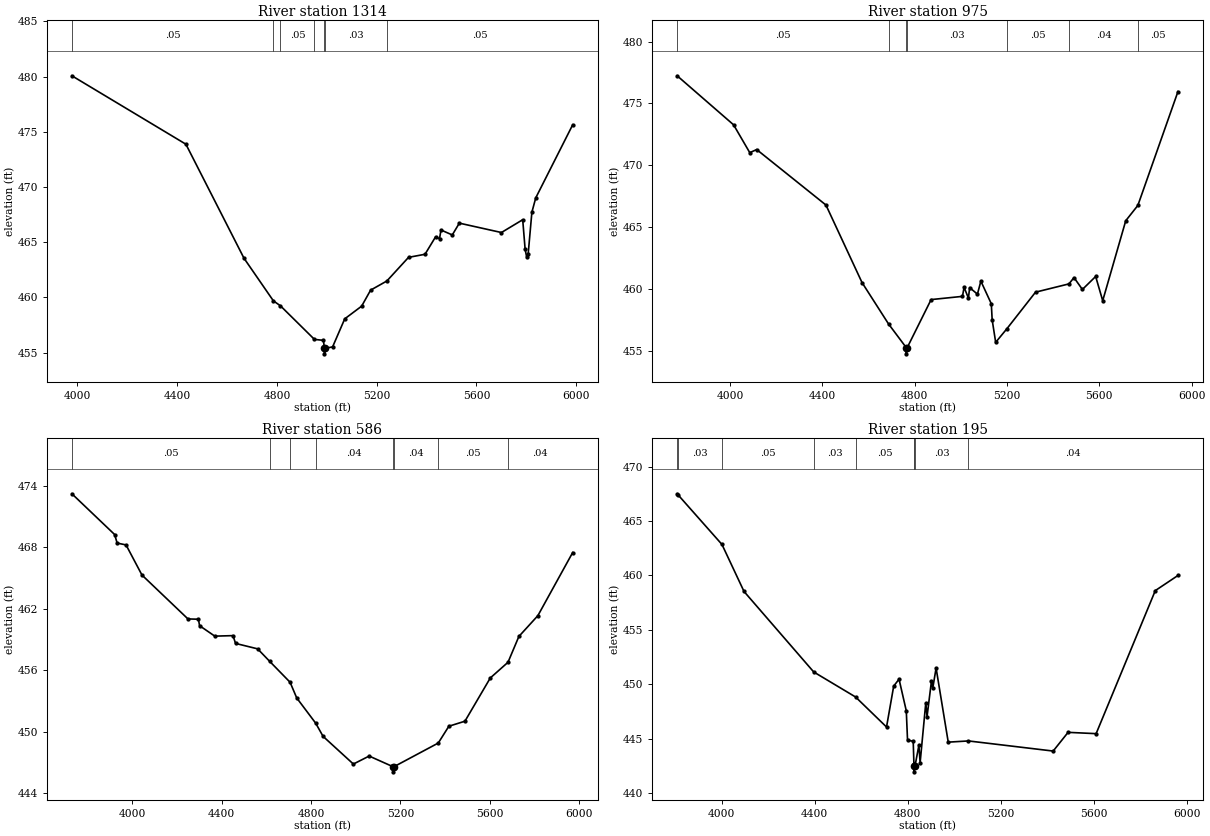
Type RM Length L Ch R = 1,1314,339,339,339
BEGIN DESCRIPTION:
LGII4675
END DESCRIPTION:
XS GIS Cut Line= 3
      2400303.89     13579738.94      2401255.05     13579585.29
      2402147.68     13579043.86
#Sta/Elev= 30
  3978.2  480.08  4435.2  473.88  4668.1  463.55  4785.9  459.69  4814.2  459.24
  4950.4  456.20  4986.5  456.11  4990.4  455.39  4990.6  454.89  4994.4  455.39
  5023.3  455.52  5071.9  458.06  5139.7  459.21  5175.6  460.66  5240.8  461.49
  5327.6  463.63  5393.7  463.91  5436.3  465.50  5451.8  465.31  5457.7  466.11
  5503.0  465.66  5531.3  466.73  5700.0  465.88  5785.3  467.04  5795.0  464.37
  5800.8  463.70  5807.1  463.91  5822.1  467.72  5837.6  469.02  5985.7  475.64
#Mann=7,-1,0
  3978.2    0.05       0  4785.9    0.12       0  4814.2    0.05       0
  4950.4    0.03       0  4990.4    0.03       0  4994.4    0.03       0
  5240.8    0.05       0
Bank Sta=4990.4,4994.4
Exp/Cntr=0.3,0.1

Type RM Length L Ch R = 1,975,389,389,389
BEGIN DESCRIPTION:
LGII4674
END DESCRIPTION:
XS GIS Cut Line= 6
      2400340.39     13579790.17      2401384.60     13579802.97
      2401499.23     13579796.94      2401562.36     13579750.32
      2401595.77     13579634.03      2402279.44     13579197.49
#Sta/Elev= 30
  3771.0  477.23  4015.6  473.26  4085.6  471.01  4115.6  471.26  4415.7  466.77
  4571.9  460.50  4686.8  457.15  4763.7  455.23  4763.9  454.73  4767.7  455.23
  4871.3  459.12  5007.1  459.38  5014.1  460.11  5033.0  459.24  5038.2  460.09
  5071.9  459.56  5086.9  460.61  5132.1  458.78  5135.8  457.48  5151.0  455.66
  5200.4  456.78  5323.6  459.72  5468.5  460.39  5490.3  460.90  5526.7  459.94
  5584.2  460.99  5614.7  459.03  5714.5  465.50  5767.0  466.74  5940.7  475.95
#Mann=7,-1,0
  3771.0    0.05       0  4686.8    0.03       0  4763.7    0.03       0
  4767.7    0.03       0  5200.4    0.05       0  5468.5    0.04       0
  5767.0    0.05       0
Bank Sta=4763.7,4767.7
Exp/Cntr=0.3,0.1

Type RM Length L Ch R = 1,586,391,391,391
BEGIN DESCRIPTION:
LGII4673
END DESCRIPTION:
XS GIS Cut Line= 4
      2400377.07     13579892.62      2401481.88     13580104.80
      2401942.84     13580038.95      2402352.61     13579534.05
#Sta/Elev= 30
  3730.4  473.22  3921.8  469.24  3932.8  468.41  3972.7  468.23  4044.0  465.29
  4249.7  461.01  4296.6  460.98  4301.7  460.35  4369.8  459.33  4451.3  459.38
  4462.7  458.62  4561.5  458.09  4615.4  456.87  4706.7  454.83  4736.4  453.30
  4821.2  450.84  4854.4  449.55  4989.9  446.85  5060.6  447.63  5167.4  446.59
  5167.7  446.09  5171.4  446.59  5369.8  448.90  5417.2  450.54  5489.1  451.03
  5602.6  455.25  5681.8  456.78  5730.5  459.30  5815.5  461.33  5971.3  467.49
#Mann=8,-1,0
  3730.4    0.05       0  4615.4    0.03       0  4706.7    0.05       0
  4821.2    0.04       0  5167.4    0.04       0  5171.4    0.04       0
  5369.8    0.05       0  5681.8    0.04       0
Bank Sta=5167.4,5171.4
Exp/Cntr=0.3,0.1

Type RM Length L Ch R = 1,195,0,0,0
BEGIN DESCRIPTION:
LGII4672
END DESCRIPTION:
XS GIS Cut Line= 4
      2400457.54     13580017.01      2401496.51     13580426.74
      2402008.70     13580390.16      2402389.16     13580031.64
#Sta/Elev= 30
  3808.5  467.51  3814.1  467.37  4001.2  462.85  4096.0  458.53  4395.7  451.13
  4575.6  448.83  4708.7  446.07  4739.5  449.83  4762.5  450.47  4793.6  447.56
  4799.0  444.86  4823.4  444.76  4826.5  442.65  4826.8  442.45  4827.0  441.95
  4830.8  442.45  4847.8  444.39  4853.1  442.79  4877.5  448.30  4882.9  447.03
  4901.9  450.30  4907.3  449.62  4921.8  451.49  4974.0  444.68  5061.0  444.79
  5425.1  443.86  5489.2  445.58  5609.8  445.46  5864.2  458.61  5961.6  460.00
#Mann=9,-1,0
  3808.5    0.05       0  3814.1    0.03       0  4001.2    0.05       0
  4395.7    0.03       0  4575.6    0.05       0  4826.5    0.03       0
  4826.8    0.03       0  4830.8    0.03       0  5061.0    0.04       0
Bank Sta=4826.8,4830.8
Exp/Cntr=0.3,0.1

Chan Stop Cuts=-1