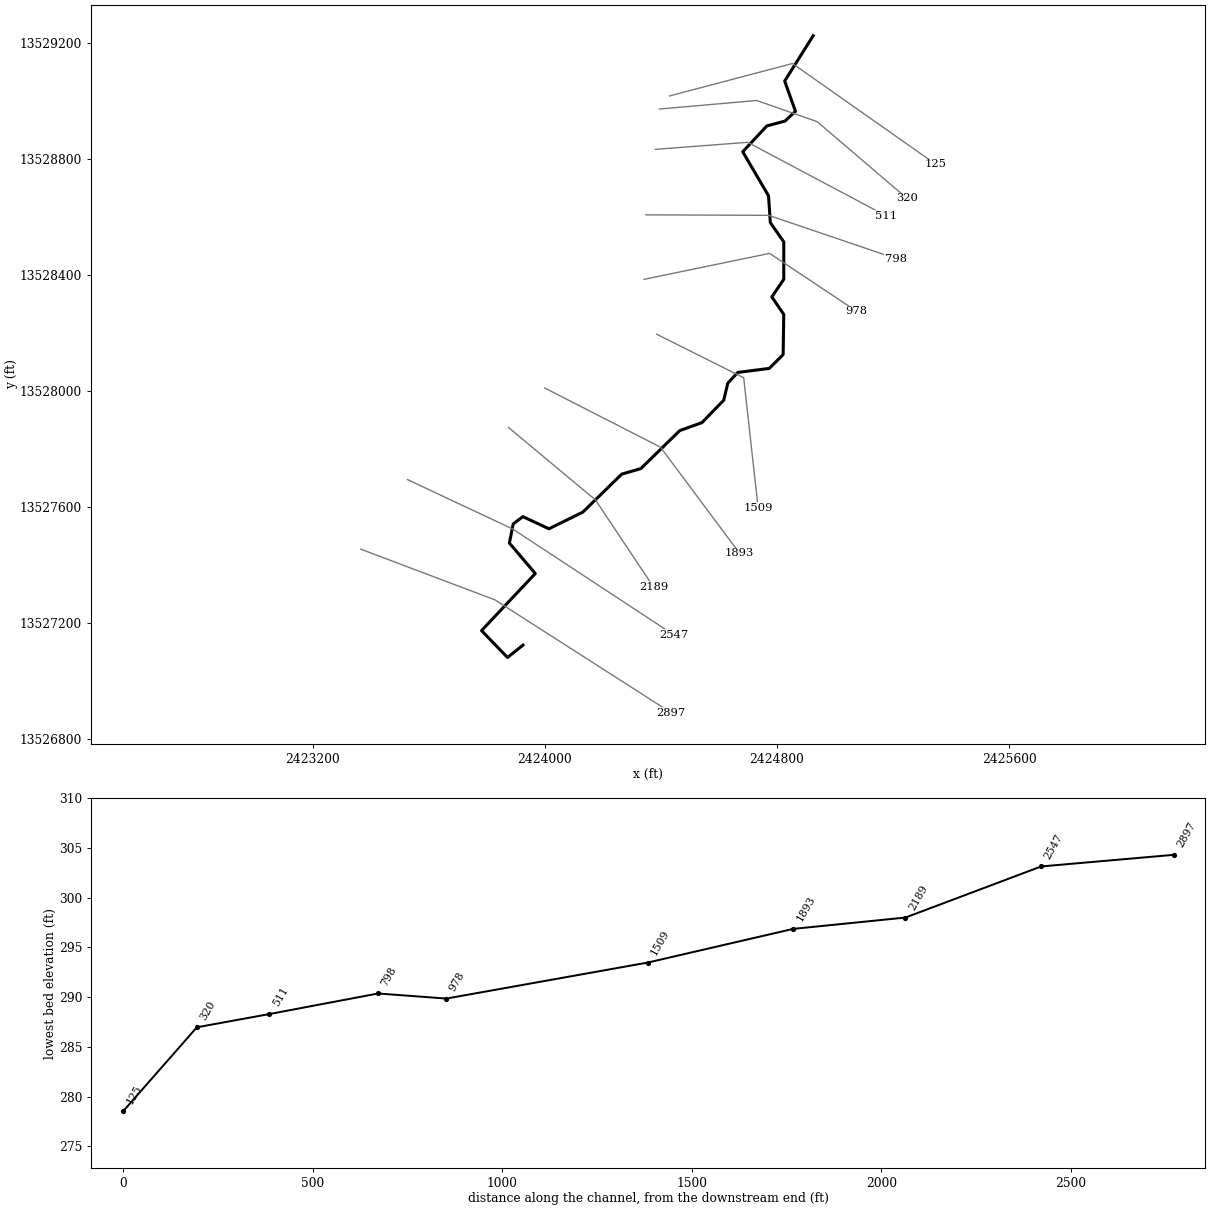
--- TRIB 9_1 TO SMITH CREEK.prj (project) ---

Proj Title=TRIB 9_1 TO SMITH CREEK Base Level Engineering
Current Plan=p01
Default Exp/Contr=0.3,0.1
English Units
Geom File=g01
Flow File=f01
Plan File=p01
BEGIN DESCRIPTION:
TRIB 9_1 TO SMITH CREEK
END DESCRIPTION:

--- TRIB 9_1 TO SMITH CREEK.p01 (plan) ---

Plan Title=Multiple Run
Short Identifier=Multiple
Geom File=g01
Flow File=f01
Subcritical Flow
K Sum by GR= 0
Std Step Tol= 0.01
Critical Tol= 0.01
Num of Std Step Trials= 20
Max Error Tol= 0.3
Flow Tol Ratio= 0.001
Split Flow NTrial= 30
Split Flow Tol= 0.02
Split Flow Ratio= 0.02
Log Output Level= 0
Friction Slope Method= 1
Unsteady Friction Slope Method= 2
Unsteady Bridges Friction Slope Method= 1
Parabolic Critical Depth
Global Vel Dist=  1 , 1 , 1
Global Log Level= 0
CheckData=True
Encroach Param= -1, 0, 0, 0
BEGIN DESCRIPTION:
Multiple Run
END DESCRIPTION:

--- TRIB 9_1 TO SMITH CREEK.f01 (steady flow) ---

Flow Title=Multiple
Number of Profiles=7
Profile Names=10-year,25-year,50-year,1pct_min,100-year,1pct_plu,500-year
River Rch & RM= TRIB 9_1 TO SMIT,Reach-1,2897
     563     919    1244     817    1630    3252    2769
River Rch & RM= TRIB 9_1 TO SMIT,Reach-1,2547
     748    1239    1695    1124    2242    4473    3881
Boundary for River Rch & Prof#=TRIB 9_1 TO SMIT,Reach-1,1
Up Type=0
Dn Type=3
Dn Slope=0.005
Boundary for River Rch & Prof#=TRIB 9_1 TO SMIT,Reach-1,2
Up Type=0
Dn Type=3
Dn Slope=0.005
Boundary for River Rch & Prof#=TRIB 9_1 TO SMIT,Reach-1,3
Up Type=0
Dn Type=3
Dn Slope=0.005
Boundary for River Rch & Prof#=TRIB 9_1 TO SMIT,Reach-1,4
Up Type=0
Dn Type=3
Dn Slope=0.005
Boundary for River Rch & Prof#=TRIB 9_1 TO SMIT,Reach-1,5
Up Type=0
Dn Type=3
Dn Slope=0.005
Boundary for River Rch & Prof#=TRIB 9_1 TO SMIT,Reach-1,6
Up Type=0
Dn Type=3
Dn Slope=0.005
Boundary for River Rch & Prof#=TRIB 9_1 TO SMIT,Reach-1,7
Up Type=0
Dn Type=3
Dn Slope=0.005

--- TRIB 9_1 TO SMITH CREEK.g01 (geometry) ---

Geom Title=Existing Conditions

River Reach=TRIB 9_1 TO SMIT,Reach-1
Reach XY= 30
      2423925.00     13527125.00      2423871.63     13527082.25
      2423782.06     13527174.98      2423967.40     13527371.66
      2423878.12     13527476.71      2423891.19     13527542.56
      2423924.63     13527567.74      2424014.29     13527525.80
      2424131.06     13527583.14      2424265.32     13527714.22
      2424331.05     13527733.16      2424465.32     13527864.22
      2424541.71     13527891.64      2424616.84     13527968.96
      2424630.74     13528027.57      2424664.90     13528064.61
      2424773.75     13528078.51      2424821.57     13528126.23
      2424823.63     13528264.56      2424782.56     13528325.00
      2424823.63     13528385.44      2424823.80     13528514.49
      2424777.36     13528580.98      2424771.17     13528673.42
      2424682.28     13528825.10      2424765.31     13528914.22
      2424827.84     13528930.85      2424864.02     13528964.63
      2424826.83     13529068.88      2424925.00     13529225.00

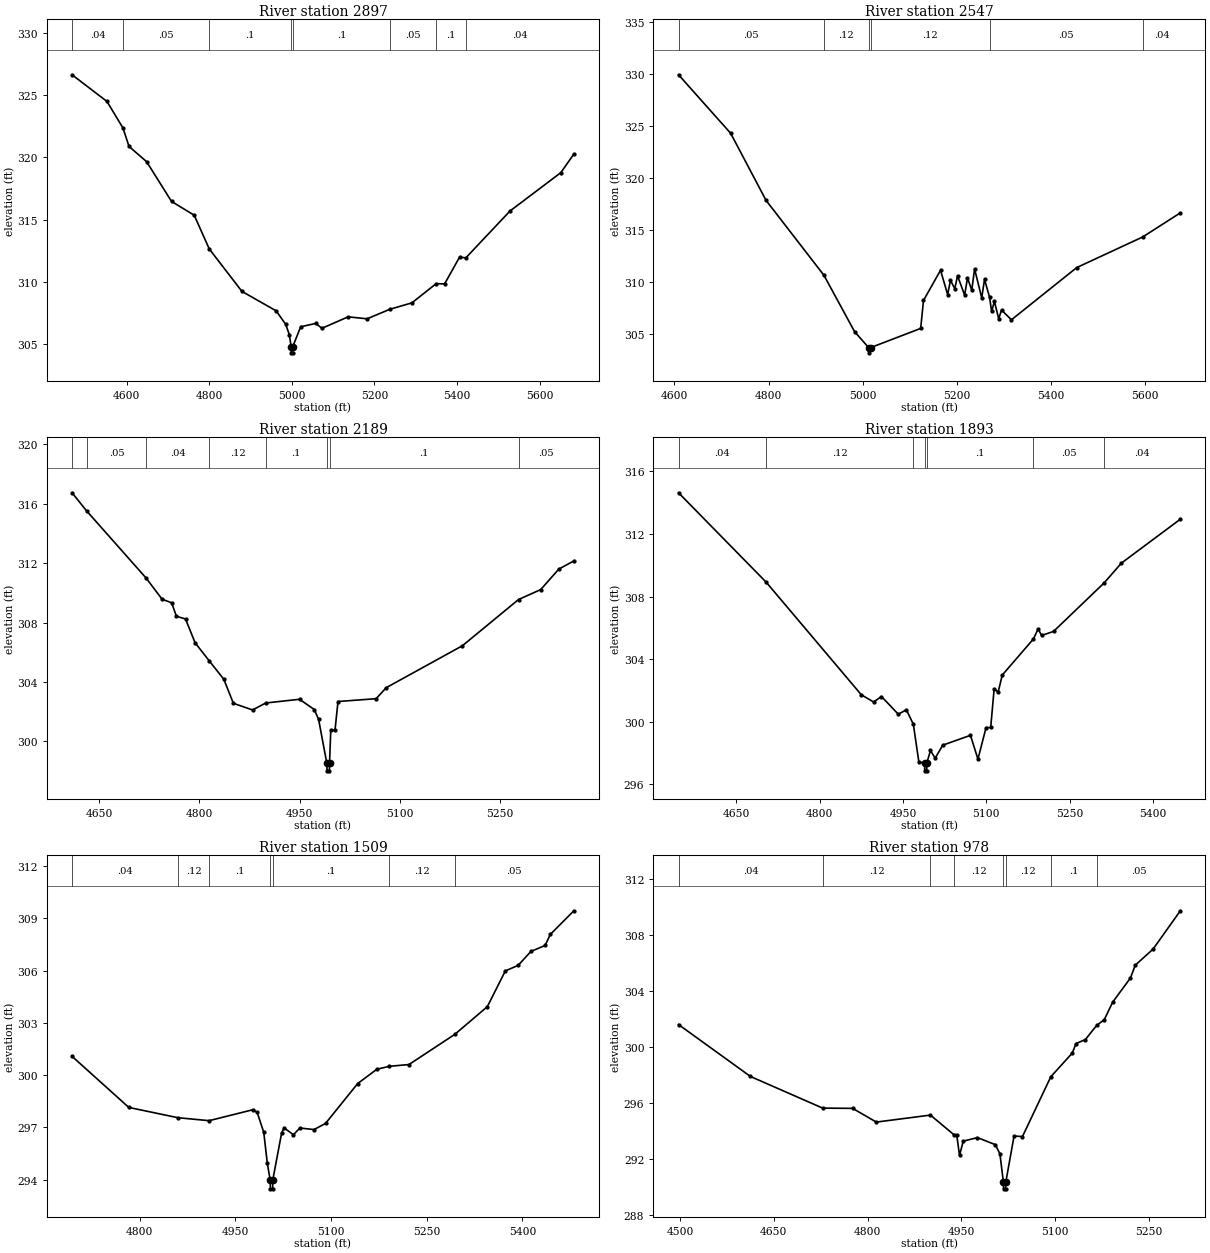
Type RM Length L Ch R = 1,2897,350,350,350
BEGIN DESCRIPTION:
LGII4642
END DESCRIPTION:
XS GIS Cut Line= 3
      2423366.00     13527455.55      2423828.20     13527280.98
      2424435.19     13526892.19
#Sta/Elev= 30
  4467.8  326.63  4552.3  324.49  4591.0  322.36  4605.7  320.88  4648.2  319.66
  4708.6  316.47  4763.6  315.36  4799.9  312.66  4879.0  309.25  4961.9  307.69
  4985.0  306.61  4993.7  305.79  4998.2  304.82  4998.5  304.32  5002.0  304.32
  5002.2  304.82  5021.3  306.41  5057.7  306.68  5072.9  306.29  5136.3  307.21
  5182.0  307.05  5237.6  307.82  5290.6  308.33  5349.3  309.87  5369.7  309.85
  5406.0  312.00  5421.1  311.94  5528.1  315.70  5651.2  318.78  5682.7  320.27
#Mann=8,-1,0
  4467.8    0.04       0  4591.0    0.05       0  4799.9     0.1       0
  4998.2    0.05       0  5002.2     0.1       0  5237.6    0.05       0
  5349.3     0.1       0  5421.1    0.04       0
Bank Sta=4998.2,5002.2
Exp/Cntr=0.3,0.1

Type RM Length L Ch R = 1,2547,358,358,358
BEGIN DESCRIPTION:
TRIB 9_1-1 TO SMITH CREEK 3.0
END DESCRIPTION:
XS GIS Cut Line= 3
      2423526.71     13527695.55      2423889.69     13527524.96
      2424445.05     13527160.02
#Sta/Elev= 30
  4608.7  329.89  4719.3  324.27  4794.6  317.81  4917.6  310.60  4982.5  305.19
  5012.5  303.65  5012.7  303.15  5016.5  303.65  5122.9  305.50  5128.9  308.19
  5165.1  311.09  5180.2  308.75  5186.2  310.13  5195.3  309.32  5201.2  310.55
  5216.3  308.70  5222.3  310.35  5231.4  309.18  5237.4  311.22  5252.5  308.44
  5258.5  310.21  5269.2  308.50  5273.6  307.13  5279.5  308.10  5288.6  306.43
  5294.6  307.26  5315.7  306.33  5454.3  311.35  5594.3  314.29  5674.3  316.61
#Mann=6,-1,0
  4608.7    0.05       0  4917.6    0.12       0  5012.5    0.05       0
  5016.5    0.12       0  5269.2    0.05       0  5594.3    0.04       0
Bank Sta=5012.5,5016.5
Exp/Cntr=0.3,0.1

Type RM Length L Ch R = 1,2189,296,296,296
BEGIN DESCRIPTION:
TRIB 9_1-1 TO SMITH CREEK 2.0
END DESCRIPTION:
XS GIS Cut Line= 3
      2423875.04     13527874.97      2424175.00     13527625.00
      2424374.99     13527325.02
#Sta/Elev= 30
  4609.3  316.74  4630.9  315.53  4720.6  310.97  4744.0  309.57  4758.3  309.33
  4765.5  308.42  4779.1  308.24  4793.4  306.64  4814.9  305.40  4836.4  304.18
  4850.7  302.56  4879.4  302.11  4899.1  302.58  4949.7  302.83  4971.8  302.14
  4978.3  301.47  4990.6  298.51  4990.9  298.01  4994.4  298.01  4994.6  298.51
  4996.5  300.74  5002.8  300.74  5007.3  302.68  5064.4  302.87  5079.4  303.61
  5193.6  306.44  5277.5  309.55  5310.7  310.22  5337.8  311.60  5360.3  312.15
#Mann=8,-1,0
  4609.3    0.04       0  4630.9    0.05       0  4720.6    0.04       0
  4814.9    0.12       0  4899.1     0.1       0  4990.6    0.05       0
  4994.6     0.1       0  5277.5    0.05       0
Bank Sta=4990.6,4994.6
Exp/Cntr=0.3,0.1

Type RM Length L Ch R = 1,1893,384,384,384
BEGIN DESCRIPTION:
Mapping XS e6ef51f1
END DESCRIPTION:
XS GIS Cut Line= 3
      2423999.44     13528011.16      2424398.77     13527807.15
      2424671.08     13527441.91
#Sta/Elev= 30
  4545.6  314.64  4703.4  308.93  4874.9  301.73  4897.1  301.27  4911.2  301.62
  4941.5  300.49  4956.1  300.77  4968.6  299.85  4978.6  297.43  4988.9  297.37
  4989.1  296.87  4992.6  296.87  4992.9  297.37  4999.5  298.17  5007.9  297.68
  5021.6  298.51  5071.5  299.14  5085.0  297.62  5099.6  299.63  5108.0  299.64
  5114.2  302.12  5121.4  301.90  5128.8  302.99  5185.0  305.30  5193.4  305.94
  5199.7  305.52  5221.2  305.78  5312.6  308.89  5343.6  310.15  5449.6  312.95
#Mann=7,-1,0
  4545.6    0.04       0  4703.4    0.12       0  4968.6     0.1       0
  4988.9    0.05       0  4992.9     0.1       0  5185.0    0.05       0
  5312.6    0.04       0
Bank Sta=4988.9,4992.9
Exp/Cntr=0.3,0.1

Type RM Length L Ch R = 1,1509,531,531,531
BEGIN DESCRIPTION:
TRIB 9_1-1 TO SMITH CREEK 1.0
END DESCRIPTION:
XS GIS Cut Line= 3
      2424385.49     13528196.45      2424685.50     13528046.44
      2424735.31     13527598.22
#Sta/Elev= 30
  4694.2  301.08  4783.1  298.15  4860.1  297.56  4908.9  297.39  4977.8  298.02
  4984.3  297.87  4994.6  296.72  5000.2  294.94  5004.7  293.98  5005.0  293.48
  5008.5  293.48  5008.7  293.98  5022.6  296.68  5026.5  296.98  5041.1  296.58
  5051.2  296.97  5073.3  296.88  5091.4  297.23  5141.8  299.52  5171.9  300.34
  5191.6  300.51  5222.2  300.61  5294.0  302.34  5345.0  303.93  5373.2  305.98
  5393.3  306.30  5413.4  307.10  5435.6  307.44  5443.6  308.07  5480.6  309.43
#Mann=7,-1,0
  4694.2    0.04       0  4860.1    0.12       0  4908.9     0.1       0
  5004.7    0.05       0  5008.7     0.1       0  5191.6    0.12       0
  5294.0    0.05       0
Bank Sta=5004.7,5008.7
Exp/Cntr=0.3,0.1

Type RM Length L Ch R = 1,978,180,180,180
BEGIN DESCRIPTION:
TRIB 9_1 TO SMITH CREEK 2.0
END DESCRIPTION:
XS GIS Cut Line= 3
      2424342.35     13528385.50      2424775.00     13528475.00
      2425075.03     13528274.98
#Sta/Elev= 30
  4497.6  301.60  4612.6  297.89  4728.0  295.63  4776.0  295.61  4813.9  294.63
  4900.4  295.13  4937.9  293.73  4942.4  293.73  4946.9  292.25  4952.9  293.27
  4975.5  293.52  5004.0  293.02  5011.5  292.37  5017.0  290.36  5017.3  289.86
  5020.8  289.86  5021.0  290.36  5034.1  293.63  5047.6  293.60  5092.9  297.87
  5127.2  299.56  5133.2  300.24  5148.2  300.53  5166.2  301.54  5178.3  301.94
  5191.8  303.20  5220.3  304.93  5227.9  305.84  5256.4  306.99  5300.0  309.73
#Mann=8,-1,0
  4497.6    0.04       0  4728.0    0.12       0  4900.4     0.1       0
  4937.9    0.12       0  5017.0    0.05       0  5021.0    0.12       0
  5092.9     0.1       0  5166.2    0.05       0
Bank Sta=5017,5021
Exp/Cntr=0.3,0.1

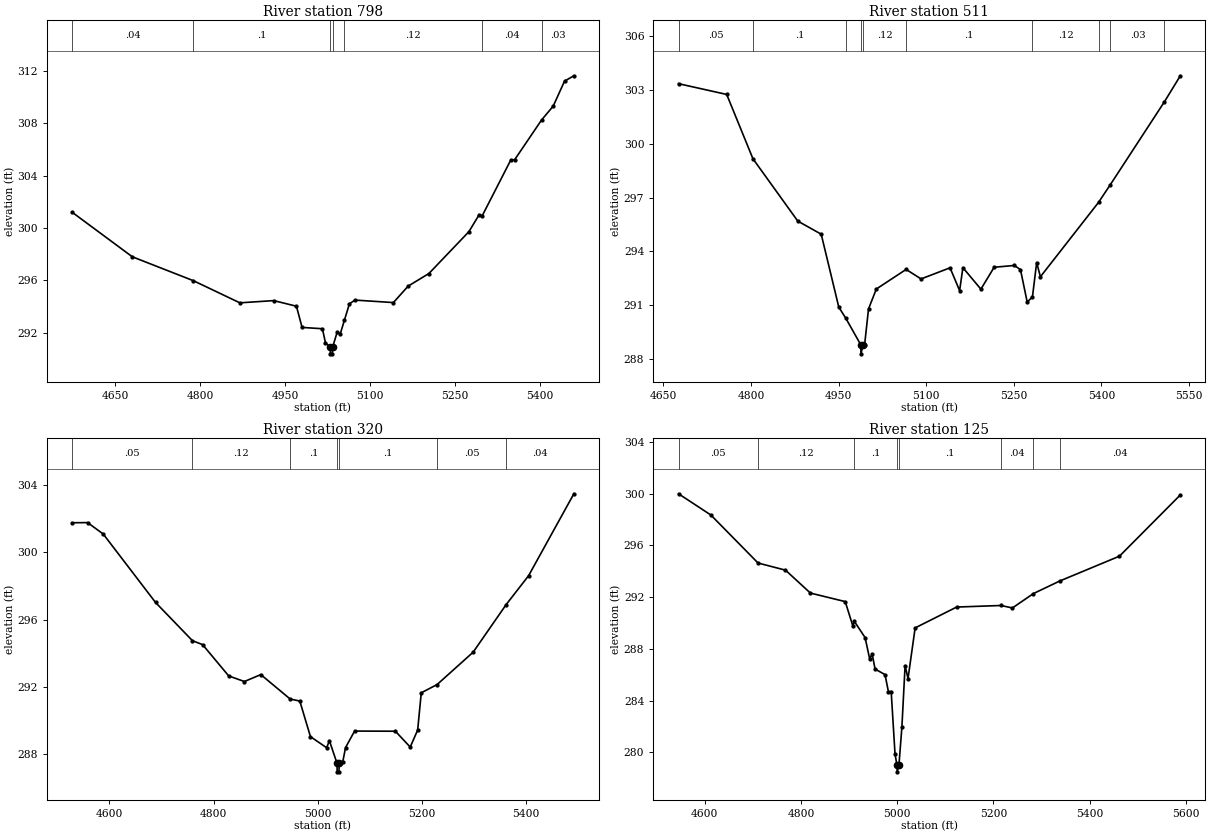
Type RM Length L Ch R = 1,798,287,287,287
BEGIN DESCRIPTION:
Mapping XS a7640adc
END DESCRIPTION:
XS GIS Cut Line= 3
      2424348.49     13528607.73      2424772.06     13528606.00
      2425210.64     13528456.92
#Sta/Elev= 30
  4573.4  301.20  4679.9  297.79  4787.9  295.96  4869.9  294.27  4929.9  294.44
  4969.9  294.01  4979.9  292.39  5015.8  292.29  5021.2  291.22  5029.8  290.87
  5030.0  290.37  5033.5  290.37  5033.8  290.87  5041.9  292.03  5047.1  291.86
  5054.7  292.94  5063.5  294.19  5073.2  294.48  5141.3  294.29  5167.4  295.55
  5204.0  296.51  5274.7  299.71  5292.9  301.01  5298.4  300.94  5348.6  305.18
  5355.7  305.22  5403.3  308.26  5423.7  309.31  5443.7  311.22  5460.2  311.63
#Mann=7,-1,0
  4573.4    0.04       0  4787.9     0.1       0  5029.8    0.05       0
  5033.8     0.1       0  5054.7    0.12       0  5298.4    0.04       0
  5403.3    0.03       0
Bank Sta=5029.8,5033.8
Exp/Cntr=0.3,0.1

Type RM Length L Ch R = 1,511,191,191,191
BEGIN DESCRIPTION:
Mapping XS 60eb59de
END DESCRIPTION:
XS GIS Cut Line= 3
      2424381.44     13528833.43      2424699.15     13528857.73
      2425176.59     13528604.25
#Sta/Elev= 30
  4675.8  303.34  4758.3  302.74  4803.2  299.16  4880.0  295.69  4920.1  294.96
  4950.2  290.90  4962.4  290.27  4987.9  288.80  4988.1  288.30  4991.9  288.80
  4994.4  288.80  5001.1  290.80  5014.5  291.91  5065.5  293.00  5091.1  292.47
  5140.7  293.09  5157.1  291.82  5162.7  293.10  5193.5  291.90  5216.2  293.12
  5250.7  293.22  5261.3  292.99  5272.8  291.18  5281.8  291.47  5289.0  293.38
  5295.4  292.59  5394.9  296.73  5415.2  297.72  5507.9  302.34  5535.0  303.78
#Mann=10,-1,0
  4675.8    0.05       0  4803.2     0.1       0  4962.4    0.12       0
  4987.9    0.05       0  4991.9    0.12       0  5065.5     0.1       0
  5281.8    0.12       0  5394.9    0.05       0  5415.2    0.03       0
  5507.9    0.04       0
Bank Sta=4987.9,4991.9
Exp/Cntr=0.3,0.1

Type RM Length L Ch R = 1,320,195,195,195
BEGIN DESCRIPTION:
Mapping XS 13df4db1
END DESCRIPTION:
XS GIS Cut Line= 4
      2424395.33     13528972.32      2424730.40     13529001.83
      2424938.73     13528928.91      2425247.79     13528665.00
#Sta/Elev= 30
  4528.3  301.75  4558.1  301.76  4588.2  301.08  4688.6  297.02  4759.5  294.75
  4778.9  294.52  4829.1  292.66  4859.2  292.33  4890.7  292.74  4947.1  291.29
  4965.6  291.17  4986.0  289.06  5017.1  288.40  5022.4  288.82  5037.1  287.47
  5037.3  286.97  5040.8  286.97  5041.1  287.47  5048.1  287.57  5053.4  288.41
  5070.8  289.39  5149.1  289.38  5177.6  288.44  5191.9  289.45  5198.8  291.66
  5229.2  292.15  5298.4  294.07  5361.7  296.89  5404.9  298.61  5491.8  303.47
#Mann=7,-1,0
  4528.3    0.05       0  4759.5    0.12       0  4947.1     0.1       0
  5037.1    0.05       0  5041.1     0.1       0  5229.2    0.05       0
  5361.7    0.04       0
Bank Sta=5037.1,5041.1
Exp/Cntr=0.3,0.1

Type RM Length L Ch R = 1,125,0,0,0
BEGIN DESCRIPTION:
TRIB 9_1 TO SMITH CREEK 1.0
END DESCRIPTION:
XS GIS Cut Line= 3
      2424430.03     13529017.45      2424853.50     13529129.26
      2425348.46     13528781.34
#Sta/Elev= 30
  4545.5  299.98  4612.7  298.34  4710.8  294.63  4767.8  294.08  4819.6  292.31
  4892.0  291.65  4907.7  289.78  4911.0  290.12  4933.3  288.87  4942.8  287.22
  4948.0  287.60  4954.0  286.44  4974.7  286.01  4981.7  284.70  4987.5  284.70
  4995.5  279.87  4999.6  279.00  4999.9  278.50  5003.6  279.00  5009.8  281.98
  5016.4  286.71  5022.5  285.71  5037.3  289.62  5123.6  291.23  5215.7  291.35
  5239.5  291.16  5283.1  292.27  5338.4  293.25  5462.0  295.16  5588.5  299.89
#Mann=8,-1,0
  4545.5    0.05       0  4710.8    0.12       0  4911.0     0.1       0
  4999.6    0.05       0  5003.6     0.1       0  5215.7    0.04       0
  5283.1    0.05       0  5338.4    0.04       0
Bank Sta=4999.6,5003.6
Exp/Cntr=0.3,0.1

Chan Stop Cuts=-1