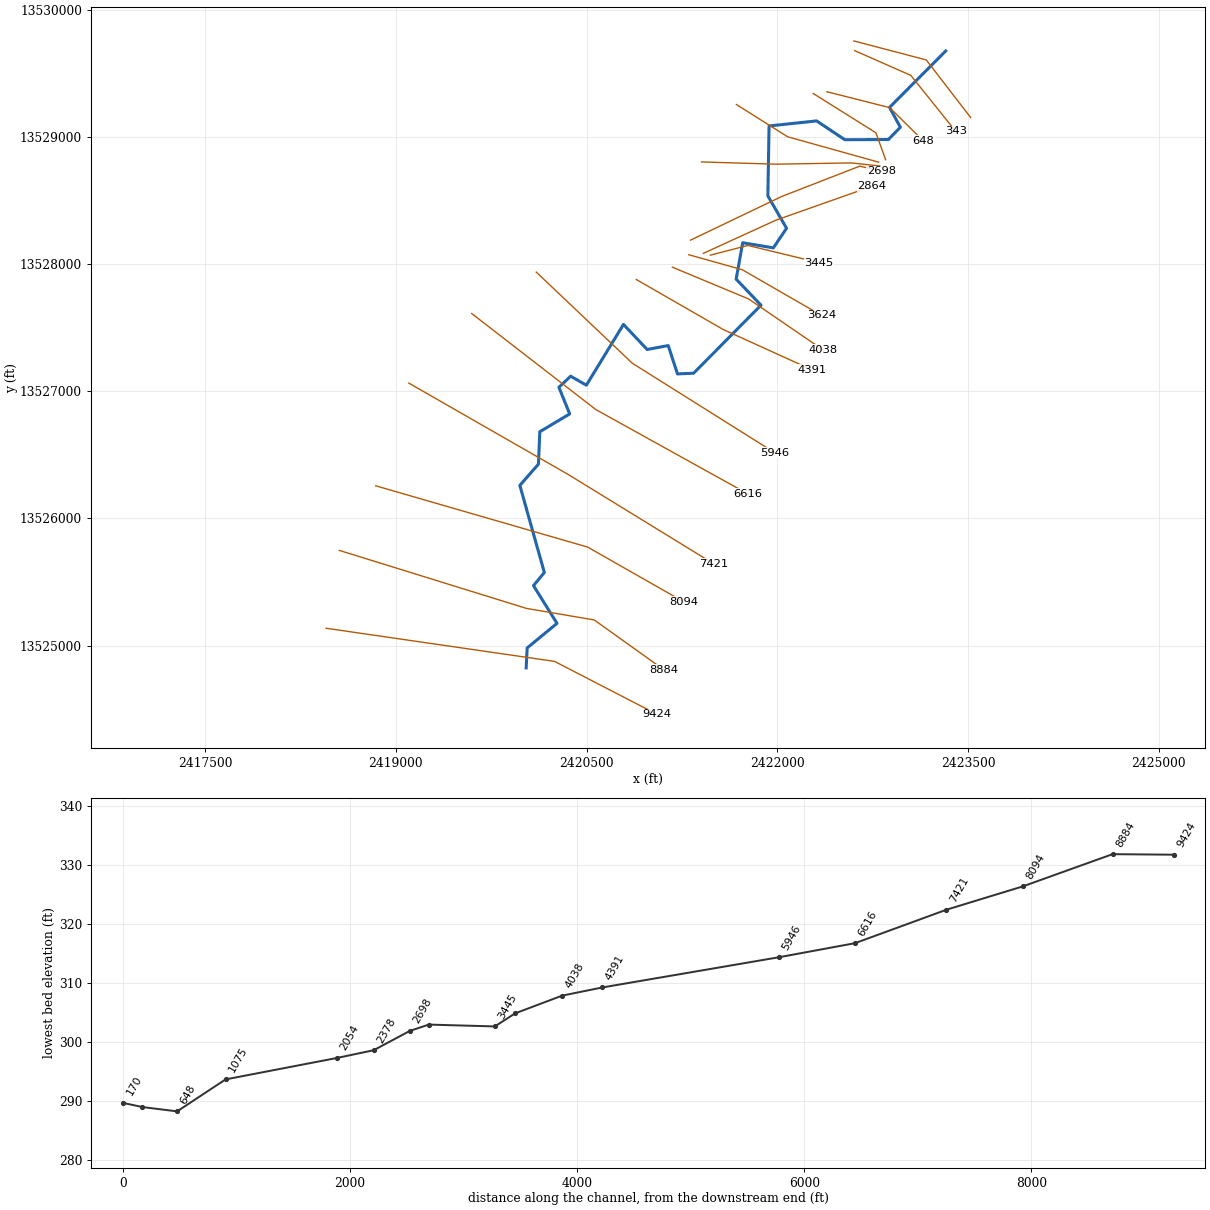
--- TRIB 9_2 TO SMITH CREEK.prj (project) ---

Proj Title=TRIB 9_2 TO SMITH CREEK Base Level Engineering
Current Plan=p01
Default Exp/Contr=0.3,0.1
English Units
Geom File=g01
Flow File=f01
Plan File=p01
Y Axis Title=Elevation
X Axis Title(PF)=Main Channel Distance
X Axis Title(XS)=Station
BEGIN DESCRIPTION:
TRIB 9_2 TO SMITH CREEK
END DESCRIPTION:
DSS Export Rating Curves= 0
DSS Export Rating Curve Sorted= 0
DSS Export Volume Flow Curves= 0
DXF OffsetX= 0
DXF OffsetY= 0
DXF ScaleX= 1
DXF ScaleY= 10

--- TRIB 9_2 TO SMITH CREEK.p01 (plan) ---

Plan Title=Multiple Run
Short Identifier=Multiple
Geom File=g01
Flow File=f01
Subcritical Flow
K Sum by GR= 0
Std Step Tol= 0.01
Critical Tol= 0.01
Num of Std Step Trials= 20
Max Error Tol= 0.3
Flow Tol Ratio= 0.001
Split Flow NTrial= 30
Split Flow Tol= 0.02
Split Flow Ratio= 0.02
Log Output Level= 0
Friction Slope Method= 1
Unsteady Friction Slope Method= 2
Unsteady Bridges Friction Slope Method= 1
Parabolic Critical Depth
Global Vel Dist=  1 , 1 , 1
Global Log Level= 0
CheckData=True
Encroach Param= -1, 0, 0, 0
BEGIN DESCRIPTION:
Multiple Run
END DESCRIPTION:

--- TRIB 9_2 TO SMITH CREEK.f01 (steady flow) ---

Flow Title=Multiple
Number of Profiles=7
Profile Names=10-year,25-year,50-year,1pct_min,100-year,1pct_plu,500-year
River Rch & RM= TRIB 9_2 TO SMIT,Reach-1,9424
     760    1247    1694    1113    2221    4431    3780
River Rch & RM= TRIB 9_2 TO SMIT,Reach-1,8094
     939    1555    2123    1401    2796    5579    4805
Boundary for River Rch & Prof#=TRIB 9_2 TO SMIT,Reach-1,1
Up Type=0
Dn Type=3
Dn Slope=0.005
Boundary for River Rch & Prof#=TRIB 9_2 TO SMIT,Reach-1,2
Up Type=0
Dn Type=3
Dn Slope=0.005
Boundary for River Rch & Prof#=TRIB 9_2 TO SMIT,Reach-1,3
Up Type=0
Dn Type=3
Dn Slope=0.005
Boundary for River Rch & Prof#=TRIB 9_2 TO SMIT,Reach-1,4
Up Type=0
Dn Type=3
Dn Slope=0.005
Boundary for River Rch & Prof#=TRIB 9_2 TO SMIT,Reach-1,5
Up Type=0
Dn Type=3
Dn Slope=0.005
Boundary for River Rch & Prof#=TRIB 9_2 TO SMIT,Reach-1,6
Up Type=0
Dn Type=3
Dn Slope=0.005
Boundary for River Rch & Prof#=TRIB 9_2 TO SMIT,Reach-1,7
Up Type=0
Dn Type=3
Dn Slope=0.005

--- TRIB 9_2 TO SMITH CREEK.g01 (geometry) ---

Geom Title=Existing Conditions
Program Version=4.10

River Reach=TRIB 9_2 TO SMIT,Reach-1
Reach XY= 30
        2420025.       13524825.      2420032.79     13524981.84
      2420267.47     13525174.99      2420082.61     13525471.67
      2420167.88       13525575.      2419975.24     13526259.78
      2420121.39      13526426.5      2420132.37     13526681.38
      2420367.24     13526821.58      2420282.48     13527031.09
      2420374.99     13527117.91      2420498.39     13527047.37
      2420790.36     13527525.11      2420976.42     13527328.04
      2421142.22     13527358.94      2421214.95     13527136.23
      2421341.67     13527141.38      2421872.01     13527676.41
      2421676.54     13527880.85      2421727.93     13528167.15
      2421969.29     13528126.89      2422072.86     13528280.97
      2421925.93     13528535.48      2421935.34     13529085.24
      2422309.59     13529124.86      2422530.86     13528977.06
      2422873.56     13528978.54      2422967.99     13529075.19
      2422882.76     13529231.12        2423325.       13529675.

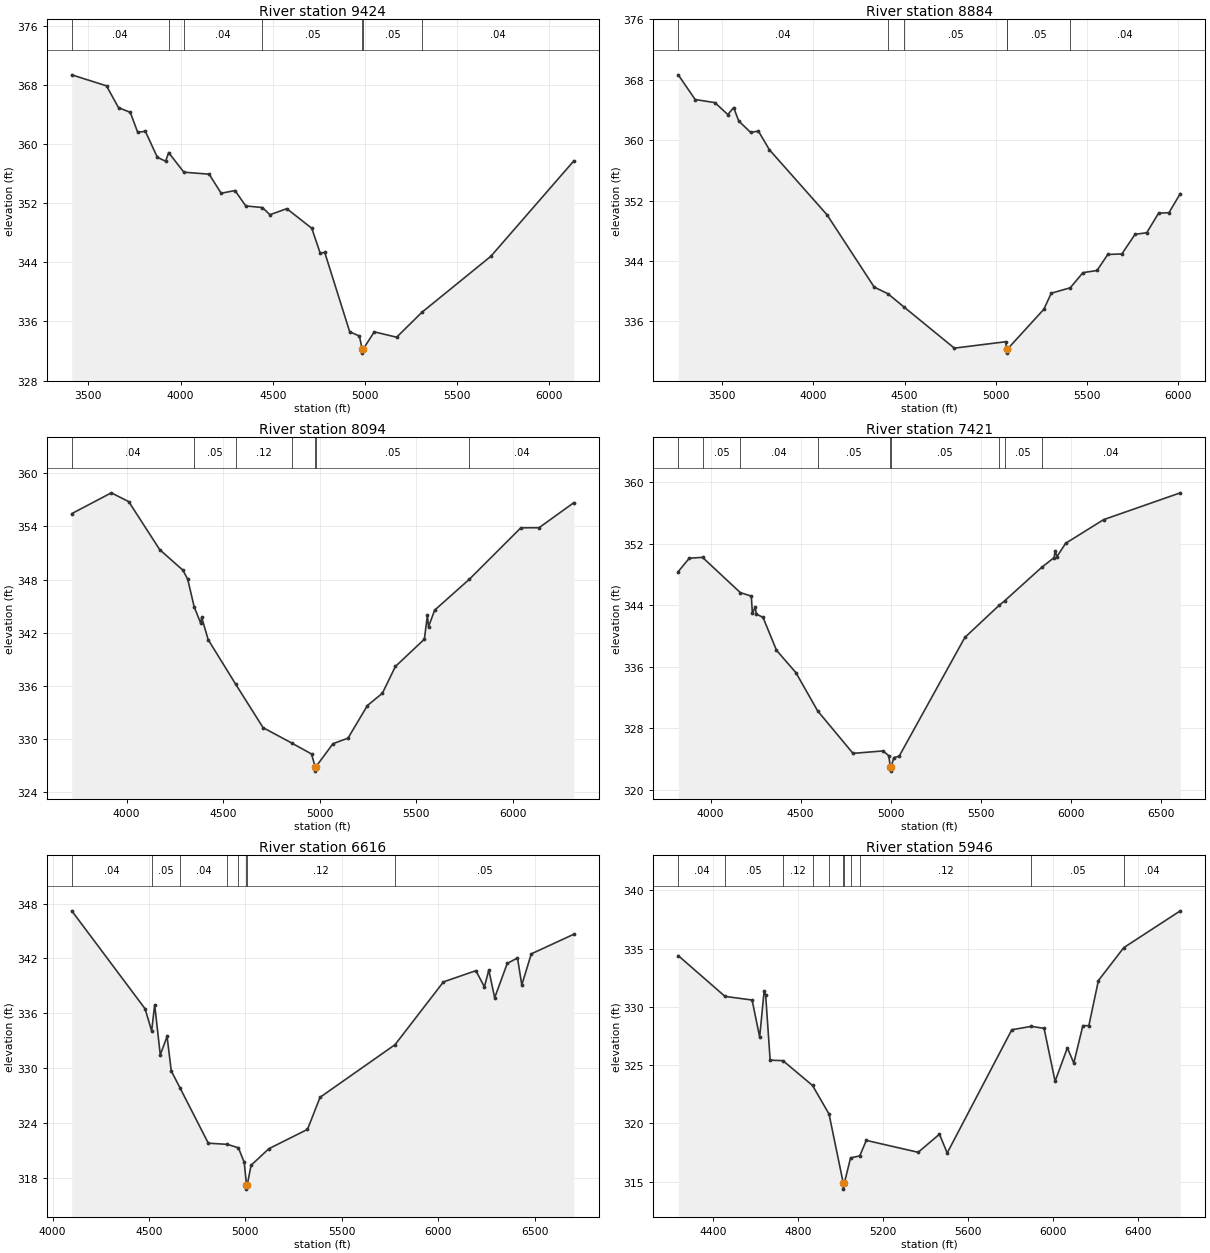
Type RM Length L Ch R = 1 ,9424    ,540,540,540
BEGIN DESCRIPTION:
LGII4651
END DESCRIPTION:
XS GIS Cut Line= 3
      2418450.97     13525136.65      2420247.82     13524876.24
      2421054.67      13524459.8
#Sta/Elev= 30
  3409.9  369.34  3598.3  367.85  3663.5   364.9  3727.2  364.27  3767.6  361.57
    3809  361.71  3874.2  358.19  3919.2  357.66  3935.3  358.83    4018  356.18
  4155.1  355.91  4220.3  353.33  4295.5   353.7  4353.7  351.62    4444   351.4
    4485  350.43  4576.4  351.25  4711.8   348.6  4757.9  345.21  4782.1  345.34
  4917.5  334.61  4970.1  334.03  4985.7  332.22  4985.9  331.72  4989.7  332.22
  5050.9   334.6  5172.2  333.87  5308.9  337.23  5683.7  344.82  6133.5  357.71
#Mann= 7 ,-1 , 0
  3409.9     .04       0  3935.3     .05       0    4018     .04       0
    4444     .05       0  4985.7     .05       0  4989.7     .05       0
  5308.9     .04       0
Bank Sta=4985.7,4989.7
XS Rating Curve= 0 ,0
Exp/Cntr=0.3,0.1

Type RM Length L Ch R = 1 ,8884    ,790,790,790
BEGIN DESCRIPTION:
LGII4650
END DESCRIPTION:
XS GIS Cut Line= 4
      2418555.08     13525748.65      2420026.46     13525292.91
      2420560.32     13525201.76       2421107.2     13524811.13
#Sta/Elev= 30
  3258.3  368.65  3351.2  365.38  3459.4  364.97  3530.4  363.39  3562.5  364.32
  3589.8  362.55  3655.1  361.03  3698.1   361.2  3758.1  358.74  4074.8  350.11
  4333.3  340.55  4408.6  339.67    4498  337.89  4772.8  332.47  5054.7  333.32
  5058.9  332.31  5059.1  331.81    5063  332.31  5263.8  337.62  5304.4  339.74
  5408.6  340.46    5478  342.46  5555.4  342.75  5614.4  344.87  5691.8  344.94
  5763.8  347.53  5828.2  347.75  5893.3  350.34  5949.9   350.4  6012.3  352.93
#Mann= 6 ,-1 , 0
  3258.3     .04       0  4408.6     .12       0    4498     .05       0
  5058.9     .05       0    5063     .05       0  5408.6     .04       0
Bank Sta=5058.9,5063
XS Rating Curve= 0 ,0
Exp/Cntr=0.3,0.1

Type RM Length L Ch R = 1 ,8094    ,673,673,673
BEGIN DESCRIPTION:
LGII4649
END DESCRIPTION:
XS GIS Cut Line= 3
      2418841.56     13526256.45      2420508.23     13525774.68
      2421261.71     13525345.98
#Sta/Elev= 30
  3716.1  355.44    3921  357.79  4011.1   356.8    4172  351.37  4292.2  349.05
  4316.9  348.04  4350.1  344.94  4384.1  343.07  4389.3  343.73  4422.9  341.21
    4566  336.16  4707.5  331.27    4857  329.52  4958.4   328.3  4977.1  326.86
  4977.3  326.36  4981.4  326.86  5069.7  329.46  5147.4  330.08  5248.2  333.77
  5325.9  335.16  5393.1  338.18  5543.2  341.26  5559.1  343.94  5564.8  342.66
  5596.6  344.54  5775.5  348.01  6043.3  353.84  6137.6  353.85  6317.9  356.68
#Mann= 7 ,-1 , 0
  3716.1     .04       0  4350.1     .05       0    4566     .12       0
    4857     .05       0  4977.1     .05       0  4981.4     .05       0
  5775.5     .04       0
Bank Sta=4977.1,4981.4
XS Rating Curve= 0 ,0
Exp/Cntr=0.3,0.1

Type RM Length L Ch R = 1 ,7421    ,805,805,805
BEGIN DESCRIPTION:
LGII4648
END DESCRIPTION:
XS GIS Cut Line= 3
      2419102.02     13527063.72      2420351.98      13526347.6
      2421497.79     13525644.49
#Sta/Elev= 30
    3821  348.38  3882.1  350.12  3955.9  350.23  4165.4  345.64  4226.4  345.19
  4232.2  342.95    4248  343.76  4253.8  342.86  4291.2  342.42    4366  338.14
  4473.9  335.22  4594.3  330.25  4790.4  324.72  4957.3  325.04  4988.4  324.42
  4998.3  322.91  4998.6  322.41  5002.7  322.91  5016.3  324.17  5046.1  324.34
  5410.8  339.81  5601.5     344  5633.2  344.61  5836.5  348.92  5905.8   350.2
  5911.7  351.08  5921.2  350.31  5969.7  352.06  6180.4  355.14  6605.9  358.63
#Mann= 9 ,-1 , 0
    3821     .04       0  3955.9     .05       0  4165.4     .04       0
  4594.3     .05       0  4998.3     .05       0  5002.7     .05       0
  5601.5     .12       0  5633.2     .05       0  5836.5     .04       0
Bank Sta=4998.3,5002.7
XS Rating Curve= 0 ,0
Exp/Cntr=0.3,0.1

Type RM Length L Ch R = 1 ,6616    ,670,670,670
BEGIN DESCRIPTION:
LGII4647
END DESCRIPTION:
XS GIS Cut Line= 3
       2419596.8      13527610.6      2420573.34     13526855.41
       2421770.6     13526191.71
#Sta/Elev= 30
  4099.7  347.21  4479.8  336.49  4513.9  334.06  4529.6  336.94  4558.6  331.45
  4593.9  333.46  4615.7  329.68    4662  327.79  4807.6  321.78  4906.9  321.65
  4963.8  321.27  4994.2  319.67  5005.4  317.25  5005.7  316.75  5009.8  317.25
  5029.5  319.36  5121.4  321.17    5322  323.29  5387.1   326.8  5775.9  332.56
  6026.9  339.43  6195.2  340.66  6239.3  338.89  6262.2  340.73  6292.5  337.69
  6357.7  341.45  6410.9  342.05  6433.2   339.1  6482.5   342.5  6703.1  344.65
#Mann= 8 ,-1 , 0
  4099.7     .04       0  4513.9     .05       0    4662     .04       0
  4906.9     .05       0  4963.8     .12       0  5005.4     .05       0
  5009.8     .12       0  5775.9     .05       0
Bank Sta=5005.4,5009.8
XS Rating Curve= 0 ,0
Exp/Cntr=0.3,0.1

Type RM Length L Ch R = 1 ,5946    ,1555,1555,1555
BEGIN DESCRIPTION:
LGII4646
END DESCRIPTION:
XS GIS Cut Line= 3
      2420104.57     13527936.16       2420859.8     13527219.99
      2421979.55     13526516.89
#Sta/Elev= 30
  4235.3   334.4  4455.5   330.9  4582.9  330.59  4618.5  327.42  4639.5  331.35
  4646.8     331  4667.9  325.43  4728.1  325.39  4867.4  323.26    4945  320.81
  5012.2  314.87  5012.5  314.37  5016.8  314.87  5046.4  317.05  5089.5  317.22
  5120.5  318.55  5364.6  317.53  5464.7  319.08  5501.2  317.47  5805.2  328.04
  5897.2  328.33  5957.1  328.16    6009  323.62  6066.7  326.49    6097  325.19
  6139.7  328.39  6167.8  328.39  6212.8  332.26  6332.1  335.08  6598.3  338.24
#Mann= 11 ,-1 , 0
  4235.3     .04       0  4455.5     .05       0  4728.1     .12       0
  4867.4     .05       0    4945     .12       0  5012.2     .05       0
  5016.8     .12       0  5046.4     .05       0  5089.5     .12       0
  5897.2     .05       0  6332.1     .04       0
Bank Sta=5012.2,5016.8
XS Rating Curve= 0 ,0
Exp/Cntr=0.3,0.1

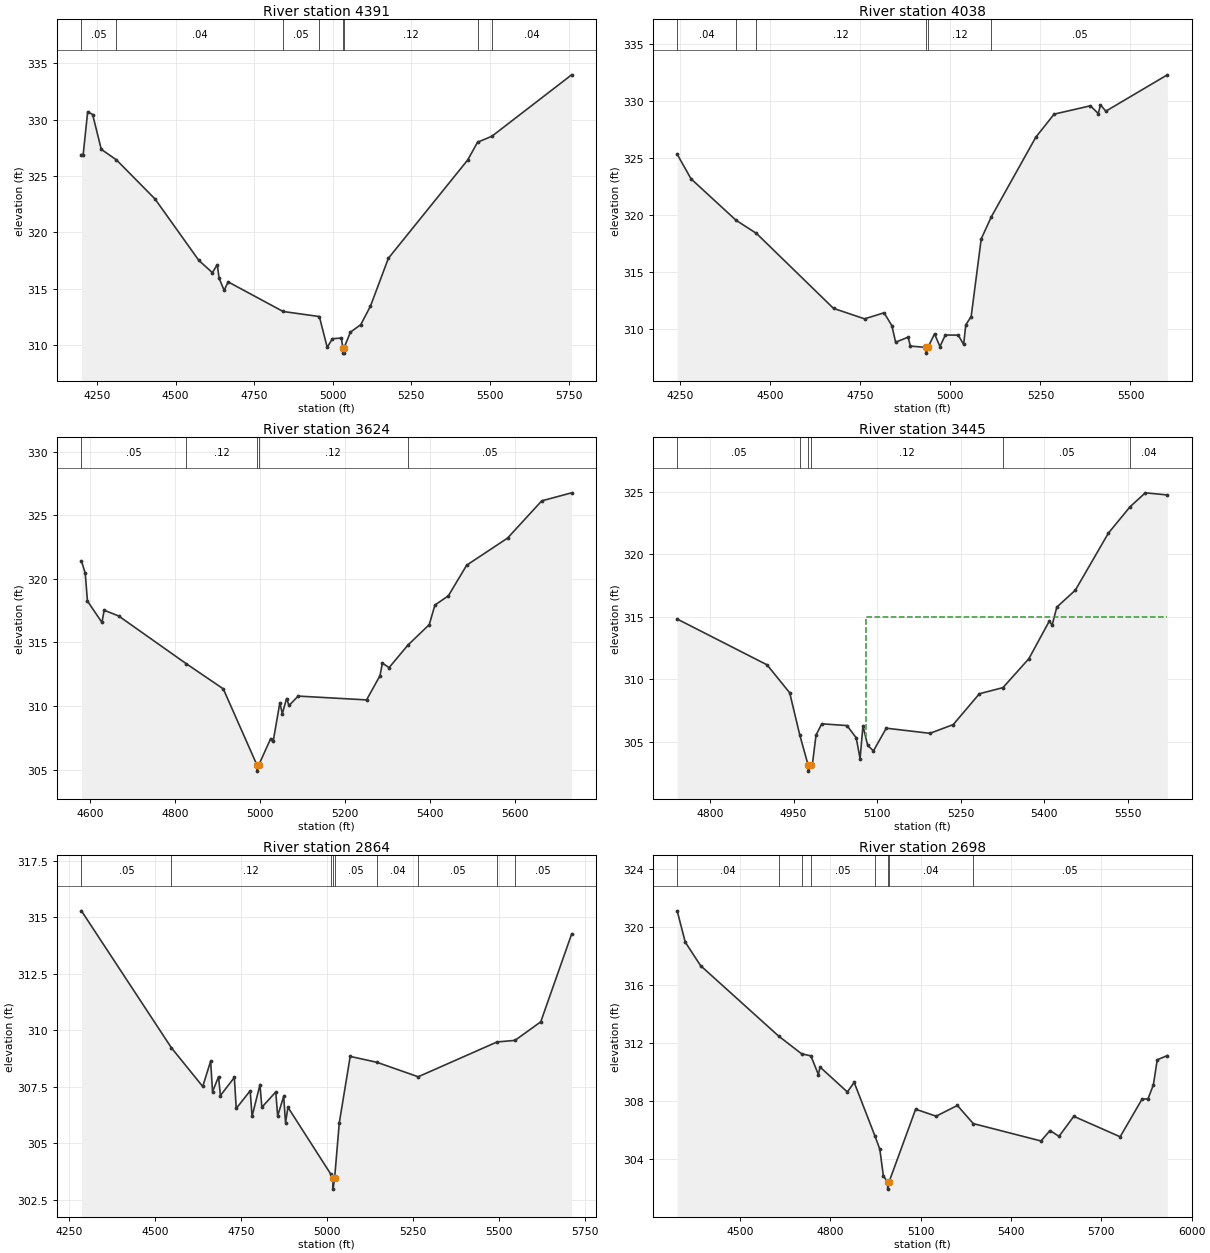
Type RM Length L Ch R = 1 ,4391    ,353,353,353
BEGIN DESCRIPTION:
TRIB 9_2 TO SMITH CREEK 6.0
END DESCRIPTION:
XS GIS Cut Line= 3
      2420890.37     13527878.59      2421574.55     13527485.19
      2422275.83     13527166.77
#Sta/Elev= 30
  4200.4   326.9    4206   326.9  4220.3  330.72  4236.1  330.46  4263.5  327.37
  4311.9  326.43  4434.5  322.96  4573.9   317.5  4617.1  316.41  4632.5  317.12
  4638.6   315.9  4654.4  314.84  4667.2  315.59    4842  312.96  4957.3  312.51
  4982.2  309.78  4998.9  310.54  5027.5   310.6  5031.6  309.76    5032  309.26
  5036.1  309.26  5036.4  309.76    5056  311.12    5089  311.79  5119.8  313.43
  5176.9  317.69  5429.4  326.43  5460.5     328  5506.1  328.53  5759.8  333.99
#Mann= 8 ,-1 , 0
  4200.4     .05       0  4311.9     .04       0    4842     .05       0
  4957.3     .12       0  5031.6     .05       0  5036.4     .12       0
  5460.5     .05       0  5506.1     .04       0
Bank Sta=5031.6,5036.4
XS Rating Curve= 0 ,0
Exp/Cntr=0.3,0.1

Type RM Length L Ch R = 1 ,4038    ,414,414,414
BEGIN DESCRIPTION:
TRIB 9_2 TO SMITH CREEK 5.0
END DESCRIPTION:
XS GIS Cut Line= 3
      2421174.97     13527975.01        2421775.       13527725.
       2422361.3     13527323.92
#Sta/Elev= 30
  4241.9  325.34  4280.4  323.18  4405.4  319.54  4461.9  318.39  4675.8  311.81
  4761.9  310.89  4816.1  311.42  4837.8  310.29  4848.1  308.84  4882.7  309.28
  4889.2   308.5  4932.9  308.38  4933.2  307.88  4937.7  308.38  4956.2  309.57
  4971.2  308.46  4986.1  309.47    5022  309.46  5036.9  308.64  5042.9  310.37
  5057.8  311.09  5085.8  317.92    5114  319.86  5237.3  326.84  5288.1  328.86
  5388.7  329.59  5410.6  328.91  5416.7  329.67  5431.6  329.12  5602.3  332.31
#Mann= 6 ,-1 , 0
  4241.9     .04       0  4405.4     .05       0  4461.9     .12       0
  4932.9     .05       0  4937.7     .12       0    5114     .05       0
Bank Sta=4932.9,4937.7
XS Rating Curve= 0 ,0
Exp/Cntr=0.3,0.1

Type RM Length L Ch R = 1 ,3624    ,179,179,179
BEGIN DESCRIPTION:
TRIB 9_2 TO SMITH CREEK 4.0
END DESCRIPTION:
XS GIS Cut Line= 3
      2421303.56     13528073.04       2421724.8     13527954.94
      2422345.24     13527597.34
#Sta/Elev= 30
    4579  321.41    4588  320.43  4593.2  318.25  4627.3  316.57  4632.5  317.53
  4666.6  317.08  4825.1  313.34  4912.8  311.35  4991.8  305.38  4992.2  304.88
  4996.6  305.38  5024.4  307.44  5030.2  307.21    5046  310.26  5051.8   309.4
  5061.8  310.59  5067.5  310.04  5089.1  310.78    5250  310.48  5281.6  312.38
  5287.3  313.37  5303.1  313.02  5347.1  314.78  5397.6   316.4  5410.9  317.94
  5442.5  318.66  5485.6  321.07  5581.8   323.2  5662.3  326.13  5732.6  326.76
#Mann= 5 ,-1 , 0
    4579     .05       0  4825.1     .12       0  4991.8     .05       0
  4996.6     .12       0  5347.1     .05       0
Bank Sta=4991.8,4996.6
XS Rating Curve= 0 ,0
Exp/Cntr=0.3,0.1

Type RM Length L Ch R = 1 ,3445    ,581,581,581
BEGIN DESCRIPTION:
Mapping XS e0f73d76
END DESCRIPTION:
XS GIS Cut Line= 3
      2421473.69     13528069.56      2421768.84     13528145.95
      2422327.89     13528010.53
#Sta/Elev= 30
  4741.1  314.82  4902.5  311.16  4943.1  308.93  4961.1  305.58  4976.1  303.17
  4976.5  302.67    4981  303.17  4983.8  303.19  4990.4  305.55  5000.7  306.45
    5046  306.31  5062.6  305.33  5069.5  303.66  5074.7   306.3  5083.2  304.72
  5093.5  304.29  5116.5   306.1    5195  305.69  5236.8  306.39  5283.7  308.85
    5326  309.34  5372.5  311.65  5409.2  314.65  5414.3  314.33  5422.7  315.77
  5456.1  317.13  5515.3  321.68  5554.3  323.79  5581.6   324.9  5621.2  324.73
#Mann= 6 ,-1 , 0
  4741.1     .05       0  4961.1     .12       0  4976.1     .05       0
    4981     .12       0    5326     .05       0  5554.3     .04       0
#XS Ineff= 2 , 0
       0                    5080       0     315
Permanent Ineff=
       F       F
Bank Sta=4976.1,4981
XS Rating Curve= 0 ,0
Exp/Cntr=0.3,0.1

Type RM Length L Ch R = 1 ,2864    ,166,166,166
BEGIN DESCRIPTION:
Mapping XS 9059bbb9
END DESCRIPTION:
XS GIS Cut Line= 3
      2421418.14     13528083.45      2421987.59     13528343.87
      2422742.79     13528610.62
#Sta/Elev= 30
  4284.8  315.29  4546.4  309.24  4637.9  307.52    4661  308.64  4666.5  307.29
    4684  307.95  4689.5  307.12    4730  307.92  4735.5  306.55  4776.1  307.33
  4781.6   306.2  4804.6   307.6  4810.1   306.6  4850.6  307.28  4856.1  306.22
  4873.6  307.08  4879.1  305.92  4886.1   306.6  5010.9  303.64  5017.1  303.48
  5017.4  302.98    5022  303.48  5035.5  305.91  5067.3  308.85  5145.2  308.59
  5265.2  307.95  5494.8  309.49  5547.1  309.56    5622  310.38  5711.9  314.26
#Mann= 9 ,-1 , 0
  4284.8     .05       0  4546.4     .12       0  5010.9     .05       0
  5017.1     .05       0    5022     .05       0  5145.2     .04       0
  5265.2     .05       0  5494.8     .04       0  5547.1     .05       0
Bank Sta=5017.1,5022
XS Rating Curve= 0 ,0
Exp/Cntr=0.3,0.1

Type RM Length L Ch R = 1 ,2698    ,320,320,320
BEGIN DESCRIPTION:
Mapping XS afee9c59
END DESCRIPTION:
XS GIS Cut Line= 4
      2421317.41      13528187.6       2422036.2     13528531.37
      2422649.06     13528769.34      2422817.74     13528730.04
#Sta/Elev= 30
  4291.9  321.11  4318.8  318.95  4369.7  317.33  4628.4  312.48  4705.1  311.25
  4735.9  311.11  4760.7  309.82  4766.2  310.34  4856.9  308.62  4879.6  309.28
  4948.2   305.6  4964.7  304.67  4976.5  302.83  4990.5  302.42  4990.8  301.92
  4995.4  302.42  5083.6  307.43  5151.7  306.95  5222.2  307.69  5274.9  306.44
  5499.8  305.24  5529.7  305.96  5559.6  305.56  5608.7  306.94  5762.5  305.53
  5835.4  308.13  5854.9  308.14  5872.9  309.11  5885.7  310.84  5919.3  311.13
#Mann= 8 ,-1 , 0
  4291.9     .04       0  4628.4     .05       0  4705.1     .04       0
  4735.9     .05       0  4948.2     .04       0  4990.5     .04       0
  4995.4     .04       0  5274.9     .05       0
Bank Sta=4990.5,4995.4
XS Rating Curve= 0 ,0
Exp/Cntr=0.3,0.1

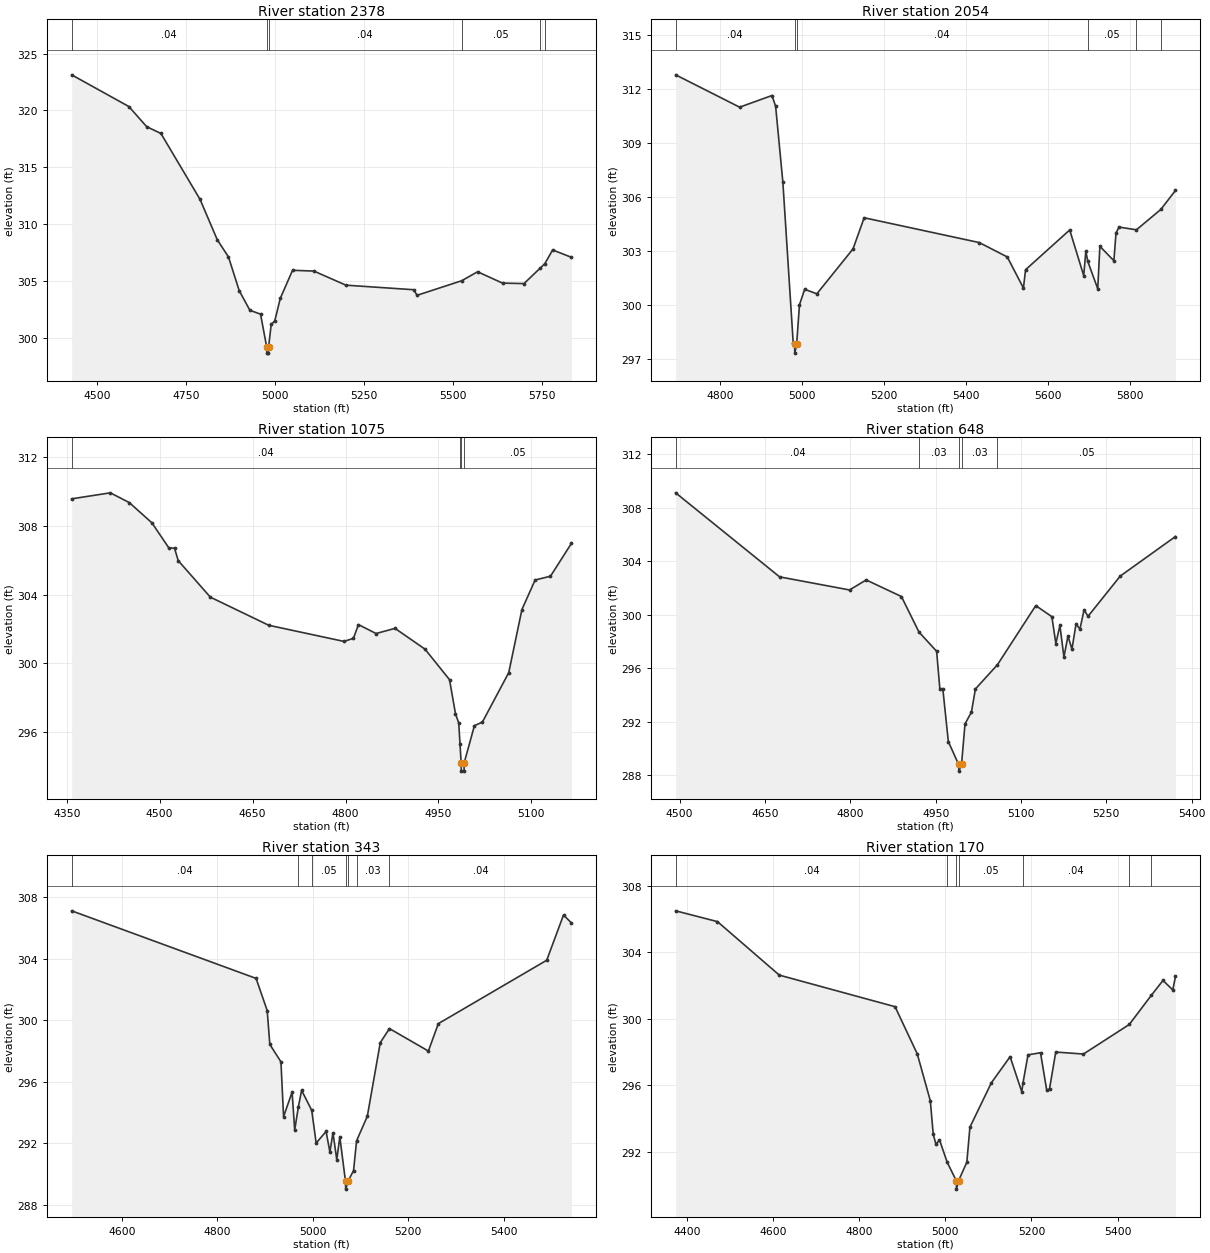
Type RM Length L Ch R = 1 ,2378    ,324,324,324
BEGIN DESCRIPTION:
Mapping XS 0b94df18
END DESCRIPTION:
XS GIS Cut Line= 4
      2421404.25      13528802.2      2421991.06     13528784.84
      2422581.39     13528794.74      2422807.69     13528770.27
#Sta/Elev= 30
  4428.5  323.13  4589.3  320.34  4639.3  318.57  4679.4  317.97  4789.4  312.17
  4837.8  308.62  4869.4   307.1  4899.5  304.14  4929.5  302.41  4959.5  302.07
    4977  299.14  4977.4  298.64  4981.6  298.64  4981.9  299.14  4989.5  301.16
  4999.5  301.48    5015  303.46  5049.5  305.93  5109.5  305.86  5199.5  304.62
  5389.6  304.22  5399.6  303.73  5524.9  305.01  5569.6   305.8  5639.8   304.8
  5700.1  304.76  5745.6  306.12  5758.6  306.51  5780.6  307.72  5833.6  307.07
#Mann= 6 ,-1 , 0
  4428.5     .04       0    4977     .04       0  4981.9     .04       0
  5524.9     .05       0  5745.6     .04       0  5758.6     .05       0
Bank Sta=4977,4981.9
XS Rating Curve= 0 ,0
Exp/Cntr=0.3,0.1

Type RM Length L Ch R = 1 ,2054    ,979,979,979
BEGIN DESCRIPTION:
Mapping XS cd49b113
END DESCRIPTION:
XS GIS Cut Line= 3
      2421678.58     13529253.59      2422081.34     13529000.12
      2422797.65     13528800.43
#Sta/Elev= 30
  4692.3  312.81  4848.4  311.01  4927.3  311.66  4936.2  311.06  4953.9  306.83
  4979.1   297.9  4982.6  297.83  4982.9  297.33  4987.5  297.83  4994.4  300.02
  5007.1  300.88  5036.8  300.63  5125.1  303.13  5152.2  304.86    5433  303.48
  5501.4  302.68  5540.8  300.95    5546  301.97  5653.7  304.18  5687.9  301.64
  5693.1  303.01  5697.7  302.44  5722.1  300.91  5727.3  303.27  5761.5  302.47
  5766.7  304.02  5774.1  304.34  5816.5  304.19  5875.9  305.32  5911.8  306.38
#Mann= 6 ,-1 , 0
  4692.3     .04       0  4982.6     .04       0  4987.5     .04       0
  5697.7     .05       0  5816.5     .04       0  5875.9     .05       0
Bank Sta=4982.6,4987.5
XS Rating Curve= 0 ,0
Exp/Cntr=0.3,0.1

Type RM Length L Ch R = 1 ,1075    ,427,427,427
BEGIN DESCRIPTION:
Mapping XS 4afcd4ee
END DESCRIPTION:
XS GIS Cut Line= 3
       2422282.7     13529340.42      2422775.79     13529031.37
      2422852.11     13528819.74
#Sta/Elev= 30
  4357.9  309.58  4420.3  309.93    4451  309.36  4487.5  308.18  4514.6  306.73
    4524   306.7  4529.9  305.98  4581.8  303.85  4676.1  302.21  4797.5  301.27
  4812.8  301.45  4820.9  302.25  4849.3  301.73  4879.9  302.03  4928.3  300.82
  4967.9  299.04  4977.5  297.06  4982.8  296.51  4984.8   295.3  4986.6  294.21
    4987  293.71  4991.3  293.71  4991.7  294.21  5008.1  296.36    5021  296.57
  5063.5  299.45  5084.8  303.13  5106.1  304.85  5130.9  305.07  5164.8  306.99
#Mann= 4 ,-1 , 0
  4357.9     .04       0  4984.8     .05       0  4986.6     .05       0
  4991.7     .05       0
Bank Sta=4986.6,4991.7
XS Rating Curve= 0 ,0
Exp/Cntr=0.3,0.1

Type RM Length L Ch R = 1 ,648     ,305,305,305
BEGIN DESCRIPTION:
Mapping XS 7ea69f26
END DESCRIPTION:
XS GIS Cut Line= 3
       2422390.4     13529354.28      2422883.42     13529229.29
      2423146.77     13528969.41
#Sta/Elev= 30
    4493  309.13  4675.7  302.84  4798.7  301.86  4827.9  302.61  4889.8  301.37
  4920.7  298.71  4951.7  297.27  4957.4  294.46  4962.6  294.47  4972.3  290.51
  4990.4   288.8  4990.8   288.3  4995.5   288.8  5001.6  291.83  5012.9  292.72
  5019.9  294.45  5058.6  296.26    5126  300.69  5154.3  299.86  5161.3  297.85
  5168.4   299.2  5175.5  296.84  5182.6  298.41  5189.6  297.43  5196.7   299.3
  5203.7  298.94  5210.9  300.37  5217.9  299.89  5274.5   302.9  5371.6  305.86
#Mann= 5 ,-1 , 0
    4493     .04       0  4920.7     .03       0  4990.4     .03       0
  4995.5     .03       0  5058.6     .05       0
Bank Sta=4990.4,4995.5
XS Rating Curve= 0 ,0
Exp/Cntr=0.3,0.1

Type RM Length L Ch R = 1 ,343     ,173,173,173
BEGIN DESCRIPTION:
Mapping XS c0c9b16a
END DESCRIPTION:
XS GIS Cut Line= 3
      2422609.15     13529677.19      2423050.09     13529482.76
      2423404.26     13529041.78
#Sta/Elev= 30
  4494.9  307.11  4881.4  302.72  4904.7  300.63  4910.2  298.43  4933.5   297.3
    4939  293.74  4956.9  295.33  4962.3  292.87  4970.1  294.39  4976.8  295.45
    4998  294.15  5007.3  292.02  5028.1  292.78  5036.1  291.44  5042.5  292.69
  5050.5  290.95  5056.9  292.42  5068.8  289.53  5069.2  289.03  5073.9  289.53
  5085.7  290.24    5092  292.17  5114.5  293.76  5141.7  298.55  5160.9  299.46
  5242.5     298  5263.3  299.78  5490.5   303.9  5525.7  306.84  5542.4  306.32
#Mann= 7 ,-1 , 0
  4494.9     .04       0  4970.1     .03       0    4998     .05       0
  5068.8     .05       0  5073.9     .05       0    5092     .03       0
  5160.9     .04       0
Bank Sta=5068.8,5073.9
XS Rating Curve= 0 ,0
Exp/Cntr=0.3,0.1

Type RM Length L Ch R = 1 ,170     ,0,0,0
BEGIN DESCRIPTION:
Mapping XS ae713e56
END DESCRIPTION:
XS GIS Cut Line= 3
       2422602.2     13529753.59      2423171.62     13529604.29
      2423520.95     13529151.19
#Sta/Elev= 30
  4373.8  306.49  4470.9  305.84  4614.5  302.62  4883.3  300.72  4934.9  297.88
  4965.2  295.06    4972  293.04  4978.4  292.43  4986.5  292.71  5004.2  291.37
  5025.6  290.24    5026  289.74  5030.7  290.24    5050  291.36  5057.2  293.47
    5107  296.14  5150.5  297.71  5177.6   295.6  5180.5  296.14  5192.1  297.82
  5221.1  297.95  5235.6  295.69    5242  295.77  5256.5  297.99  5320.8  297.87
  5427.3  299.65  5478.6  301.41  5505.6   302.3  5528.3  301.73  5534.6  302.54
#Mann= 7 ,-1 , 0
  4373.8     .04       0  5004.2     .05       0  5025.6     .04       0
  5030.7     .05       0  5180.5     .04       0  5427.3     .05       0
  5478.6     .04       0
Bank Sta=5025.6,5030.7
XS Rating Curve= 0 ,0
Exp/Cntr=0.3,0.1

Chan Stop Cuts=-1
Use User Specified Reach Order=0
Composite Channel Slope=5