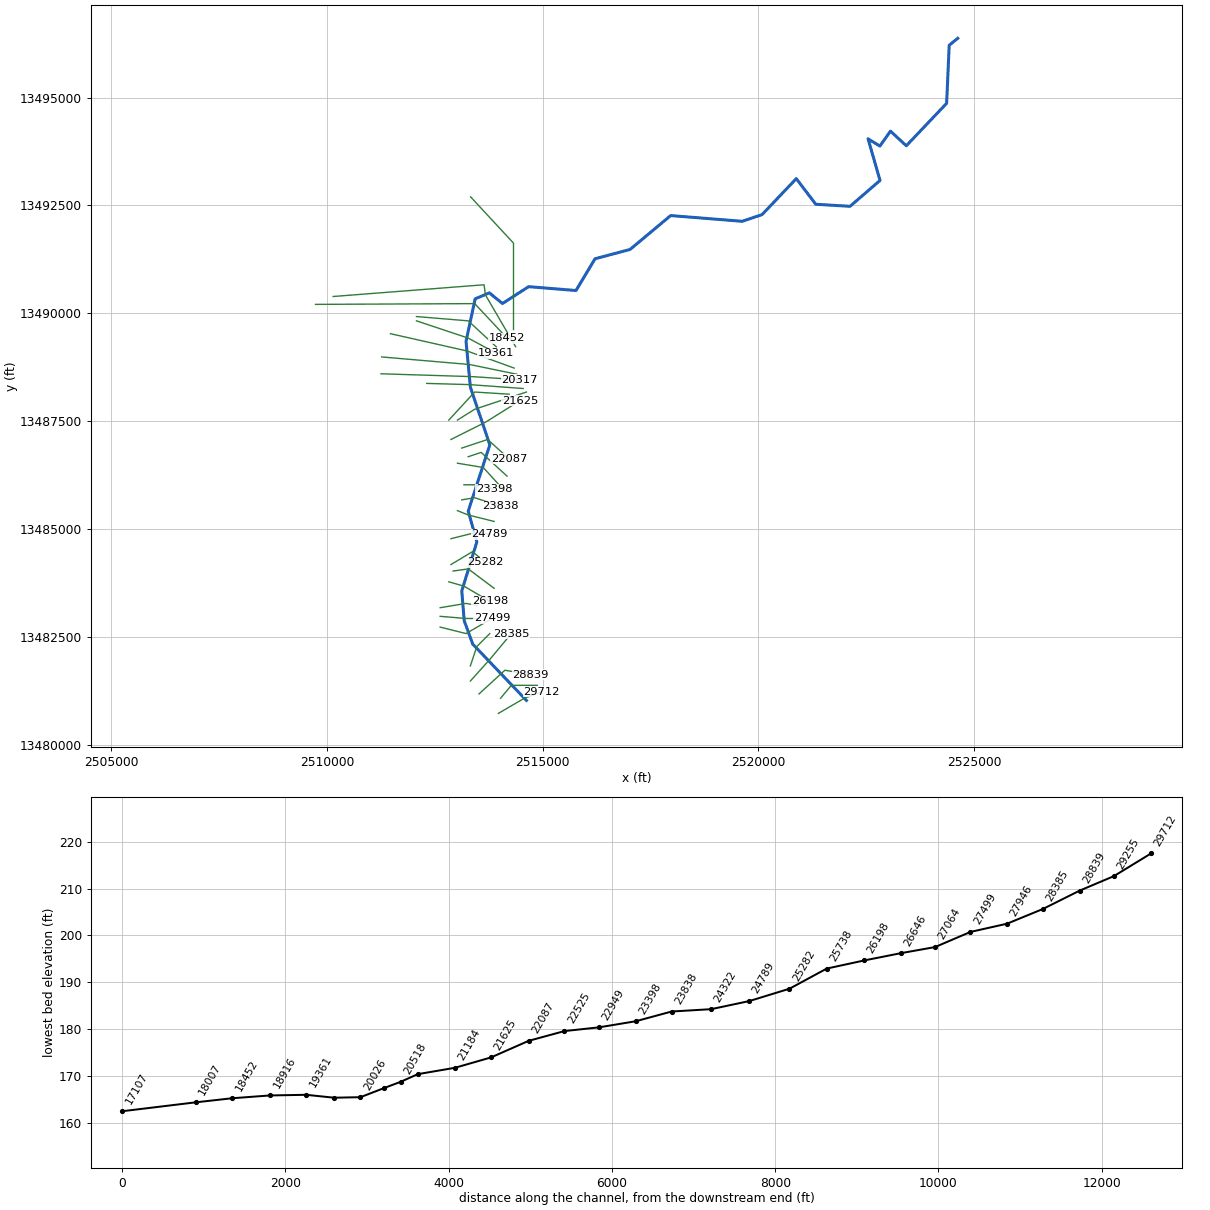
--- TRIB TO FIFTEENMILE CREEK.prj (project) ---

Proj Title=TRIB TO FIFTEENMILE CREEK Detailed Study
Current Plan=p01
Default Exp/Contr=0.3,0.1
English Units
Geom File=g01
Flow File=f01
Plan File=p01
BEGIN DESCRIPTION:
TRIB TO FIFTEENMILE CREEK
END DESCRIPTION:

--- TRIB TO FIFTEENMILE CREEK.p01 (plan) ---

Plan Title=Multiple Run
Short Identifier=Multiple
Geom File=g01
Flow File=f01
Subcritical Flow
K Sum by GR= 0
Std Step Tol= 0.01
Critical Tol= 0.01
Num of Std Step Trials= 20
Max Error Tol= 0.3
Flow Tol Ratio= 0.001
Split Flow NTrial= 30
Split Flow Tol= 0.02
Split Flow Ratio= 0.02
Log Output Level= 0
Friction Slope Method= 1
Unsteady Friction Slope Method= 2
Unsteady Bridges Friction Slope Method= 1
Parabolic Critical Depth
Global Vel Dist=  1 , 1 , 1
Global Log Level= 0
CheckData=True
Encroach Param= -1, 0, 0, 0
BEGIN DESCRIPTION:
Multiple Run
END DESCRIPTION:

--- TRIB TO FIFTEENMILE CREEK.f01 (steady flow) ---

Flow Title=Multiple
Number of Profiles=4
Profile Names=10-year,50-year,100-year,500-year
River Rch & RM= TRIB TO FIFTEENM,Reach-1,29712
     300     500     600     700
Boundary for River Rch & Prof#=TRIB TO FIFTEENM,Reach-1,1
Up Type=0
Dn Type=3
Dn Slope=0.005
Boundary for River Rch & Prof#=TRIB TO FIFTEENM,Reach-1,2
Up Type=0
Dn Type=3
Dn Slope=0.005
Boundary for River Rch & Prof#=TRIB TO FIFTEENM,Reach-1,3
Up Type=0
Dn Type=3
Dn Slope=0.005
Boundary for River Rch & Prof#=TRIB TO FIFTEENM,Reach-1,4
Up Type=0
Dn Type=3
Dn Slope=0.005

--- TRIB TO FIFTEENMILE CREEK.g01 (geometry) ---

Geom Title=Existing Conditions

River Reach=TRIB TO FIFTEENM,Reach-1
Reach XY= 30
      2514625.00     13481025.00      2513380.19     13482330.44
      2513182.12     13482875.00      2513126.20     13483564.49
      2513475.29     13484699.88      2513275.87     13485414.67
      2513775.53     13486949.87      2513325.38     13488290.16
      2513224.59     13489350.00      2513436.24     13490335.05
      2513764.69     13490474.45      2514069.11     13490226.97
      2514674.90     13490617.68      2515773.53     13490528.55
      2516215.19     13491264.57      2517027.45     13491480.46
      2517968.05     13492265.82      2519628.29     13492133.10
      2520088.40     13492288.53      2520880.93     13493122.77
      2521333.01     13492528.03      2522127.45     13492480.46
      2522822.76     13493080.93      2522544.60     13494046.15
      2522818.95     13493876.58      2523064.45     13494223.92
      2523431.70     13493883.95      2524366.86     13494868.94
      2524426.04     13496214.57      2524625.00     13496375.00

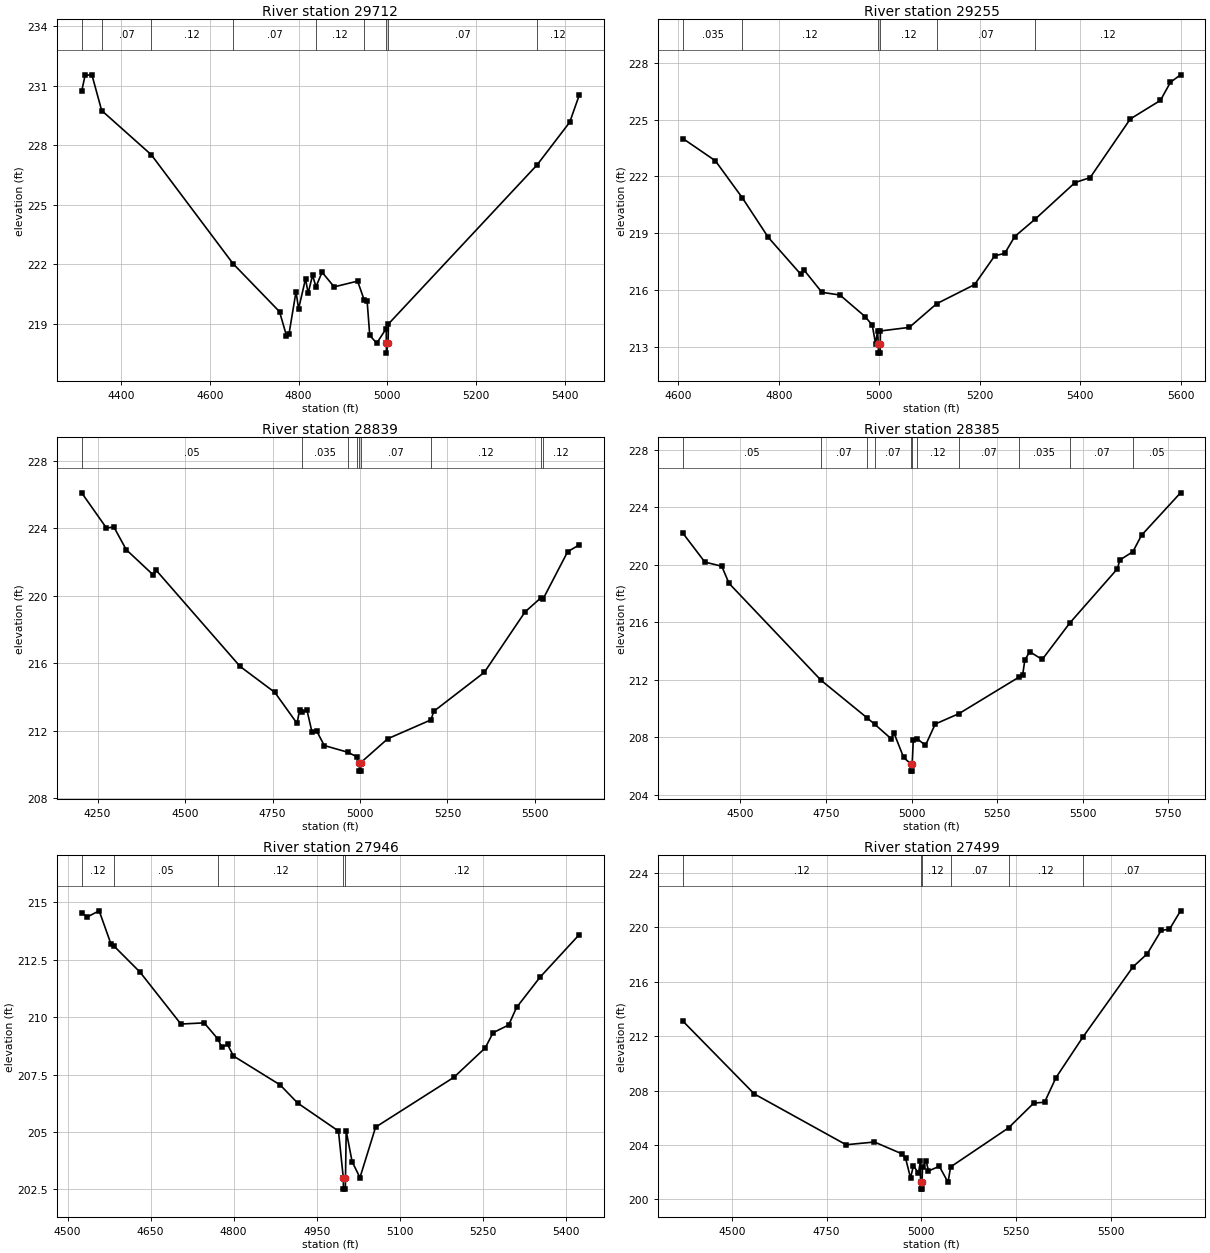
Type RM Length L Ch R = 1,29712,457,457,457
BEGIN DESCRIPTION:
TRIB TO FIFTEENMILE CREEK 59.0
END DESCRIPTION:
XS GIS Cut Line= 3
      2513975.04     13480725.02      2514575.00     13481075.00
      2514975.02     13481225.01
#Sta/Elev= 30
  4311.1  230.73  4318.9  231.54  4334.2  231.56  4356.2  229.76  4468.1  227.53
  4652.4  222.04  4757.2  219.62  4772.9  218.41  4778.7  218.51  4794.4  220.63
  4800.2  219.76  4815.9  221.28  4821.7  220.55  4831.6  221.45  4839.5  220.88
  4853.1  221.61  4880.4  220.87  4933.3  221.16  4947.9  220.22  4954.8  220.14
  4960.6  218.43  4976.3  218.03  4997.8  218.77  4998.0  218.03  4998.3  217.53
  5002.0  218.03  5002.8  219.00  5338.0  227.02  5411.5  229.17  5432.9  230.53
#Mann=9,-1,0
  4311.1   0.035       0  4356.2    0.07       0  4468.1    0.12       0
  4652.4    0.07       0  4839.5    0.12       0  4947.9    0.07       0
  4998.0    0.05       0  5002.0    0.07       0  5338.0    0.12       0
Bank Sta=4998,5002
Exp/Cntr=0.3,0.1

Type RM Length L Ch R = 1,29255,416,416,416
BEGIN DESCRIPTION:
TRIB TO FIFTEENMILE CREEK 58.0
END DESCRIPTION:
XS GIS Cut Line= 3
      2514025.00     13481075.01      2514275.00     13481375.00
      2514874.99     13481375.00
#Sta/Elev= 30
  4609.2  224.00  4673.6  222.83  4727.1  220.88  4779.1  218.78  4843.5  216.84
  4850.7  217.04  4885.8  215.88  4921.6  215.74  4971.7  214.60  4986.0  214.15
  4992.5  213.17  4996.5  213.84  4998.0  213.17  4998.3  212.67  5001.8  212.67
  5002.0  213.17  5002.2  213.84  5059.7  214.03  5114.2  215.28  5189.7  216.29
  5229.7  217.81  5249.7  217.94  5269.7  218.83  5310.8  219.76  5389.7  221.68
  5419.7  221.94  5499.7  225.04  5559.7  226.02  5579.7  226.98  5599.7  227.37
#Mann=6,-1,0
  4609.2   0.035       0  4727.1    0.12       0  4998.0    0.05       0
  5002.0    0.12       0  5114.2    0.07       0  5310.8    0.12       0
Bank Sta=4998,5002
Exp/Cntr=0.3,0.1

Type RM Length L Ch R = 1,28839,454,454,454
BEGIN DESCRIPTION:
TRIB TO FIFTEENMILE CREEK 57.0
END DESCRIPTION:
XS GIS Cut Line= 3
      2513525.00     13481175.00      2514125.00     13481725.00
      2514724.98     13481625.00
#Sta/Elev= 30
  4204.4  226.11  4275.0  224.03  4296.6  224.08  4331.7  222.74  4409.4  221.23
  4416.8  221.53  4657.3  215.81  4756.6  214.27  4820.1  212.43  4827.5  213.25
  4835.1  213.10  4848.5  213.21  4862.6  211.93  4876.8  211.96  4897.8  211.12
  4965.1  210.72  4990.2  210.46  4998.0  210.10  4998.3  209.60  5001.8  209.60
  5002.0  210.10  5079.2  211.52  5202.8  212.64  5211.0  213.15  5355.4  215.46
  5472.0  219.05  5517.0  219.88  5523.3  219.81  5593.7  222.62  5626.6  223.02
#Mann=9,-1,0
  4204.4    0.05       0  4835.1   0.035       0  4965.1    0.12       0
  4990.2    0.07       0  4998.0    0.05       0  5002.0    0.07       0
  5202.8    0.12       0  5517.0    0.07       0  5523.3    0.12       0
Bank Sta=4998,5002
Exp/Cntr=0.3,0.1

Type RM Length L Ch R = 1,28385,439,439,439
BEGIN DESCRIPTION:
TRIB TO FIFTEENMILE CREEK 56.0
END DESCRIPTION:
XS GIS Cut Line= 3
      2513325.00     13481475.00      2513775.00     13481975.00
      2514274.99     13482574.99
#Sta/Elev= 30
  4332.3  222.20  4396.2  220.20  4445.5  219.91  4466.8  218.72  4735.8  211.97
  4869.5  209.37  4893.0  208.90  4941.1  207.89  4948.6  208.31  4977.0  206.60
  4998.0  206.15  4998.3  205.65  5001.8  205.65  5002.0  206.15  5005.0  207.79
  5016.8  207.89  5040.8  207.45  5069.4  208.93  5138.5  209.65  5313.8  212.19
  5324.6  212.33  5331.1  213.39  5345.4  213.96  5381.8  213.42  5462.4  215.96
  5601.8  219.74  5608.3  220.34  5646.7  220.92  5672.1  222.07  5786.0  225.02
#Mann=11,-1,0
  4332.3    0.05       0  4735.8    0.07       0  4869.5    0.05       0
  4893.0    0.07       0  4998.0    0.05       0  5002.0    0.07       0
  5016.8    0.12       0  5138.5    0.07       0  5313.8   0.035       0
  5462.4    0.07       0  5646.7    0.05       0
Bank Sta=4998,5002
Exp/Cntr=0.3,0.1

Type RM Length L Ch R = 1,27946,447,447,447
BEGIN DESCRIPTION:
TRIB TO FIFTEENMILE CREEK 55.0
END DESCRIPTION:
XS GIS Cut Line= 3
      2513325.01     13481825.04      2513475.00     13482275.00
      2513775.02     13482575.02
#Sta/Elev= 30
  4525.5  214.53  4536.0  214.37  4557.1  214.63  4578.2  213.20  4583.7  213.10
  4630.9  211.96  4704.7  209.70  4746.8  209.75  4771.8  209.04  4778.4  208.69
  4789.0  208.81  4799.5  208.31  4883.9  207.05  4915.5  206.26  4989.3  205.04
  4998.0  203.01  4998.3  202.51  5001.8  202.51  5002.0  203.01  5003.3  205.04
  5013.9  203.71  5028.1  203.01  5056.4  205.21  5197.8  207.38  5254.4  208.66
  5268.5  209.32  5296.8  209.66  5310.9  210.42  5353.4  211.74  5424.1  213.59
#Mann=5,-1,0
  4525.5    0.12       0  4583.7    0.05       0  4771.8    0.12       0
  4998.0    0.05       0  5002.0    0.12       0
Bank Sta=4998,5002
Exp/Cntr=0.3,0.1

Type RM Length L Ch R = 1,27499,435,435,435
BEGIN DESCRIPTION:
TRIB TO FIFTEENMILE CREEK 54.0
END DESCRIPTION:
XS GIS Cut Line= 3
      2512624.96     13482725.01      2513225.00     13482575.00
      2513824.98     13482924.99
#Sta/Elev= 30
  4371.1  213.09  4559.3  207.75  4801.5  204.02  4876.2  204.22  4948.4  203.36
  4958.7  203.01  4971.6  201.58  4979.3  202.49  4992.5  201.92  4997.5  202.80
  4998.0  201.26  4998.3  200.76  5001.8  200.76  5002.0  201.26  5003.2  202.38
  5012.8  202.84  5019.0  202.09  5047.5  202.44  5070.6  201.26  5077.3  202.39
  5230.3  205.26  5296.8  207.08  5325.3  207.14  5355.5  208.95  5426.8  211.94
  5558.9  217.09  5596.2  218.04  5633.4  219.77  5654.9  219.84  5684.2  221.20
#Mann=6,-1,0
  4371.1    0.12       0  4998.0    0.05       0  5002.0    0.12       0
  5077.3    0.07       0  5230.3    0.12       0  5426.8    0.07       0
Bank Sta=4998,5002
Exp/Cntr=0.3,0.1

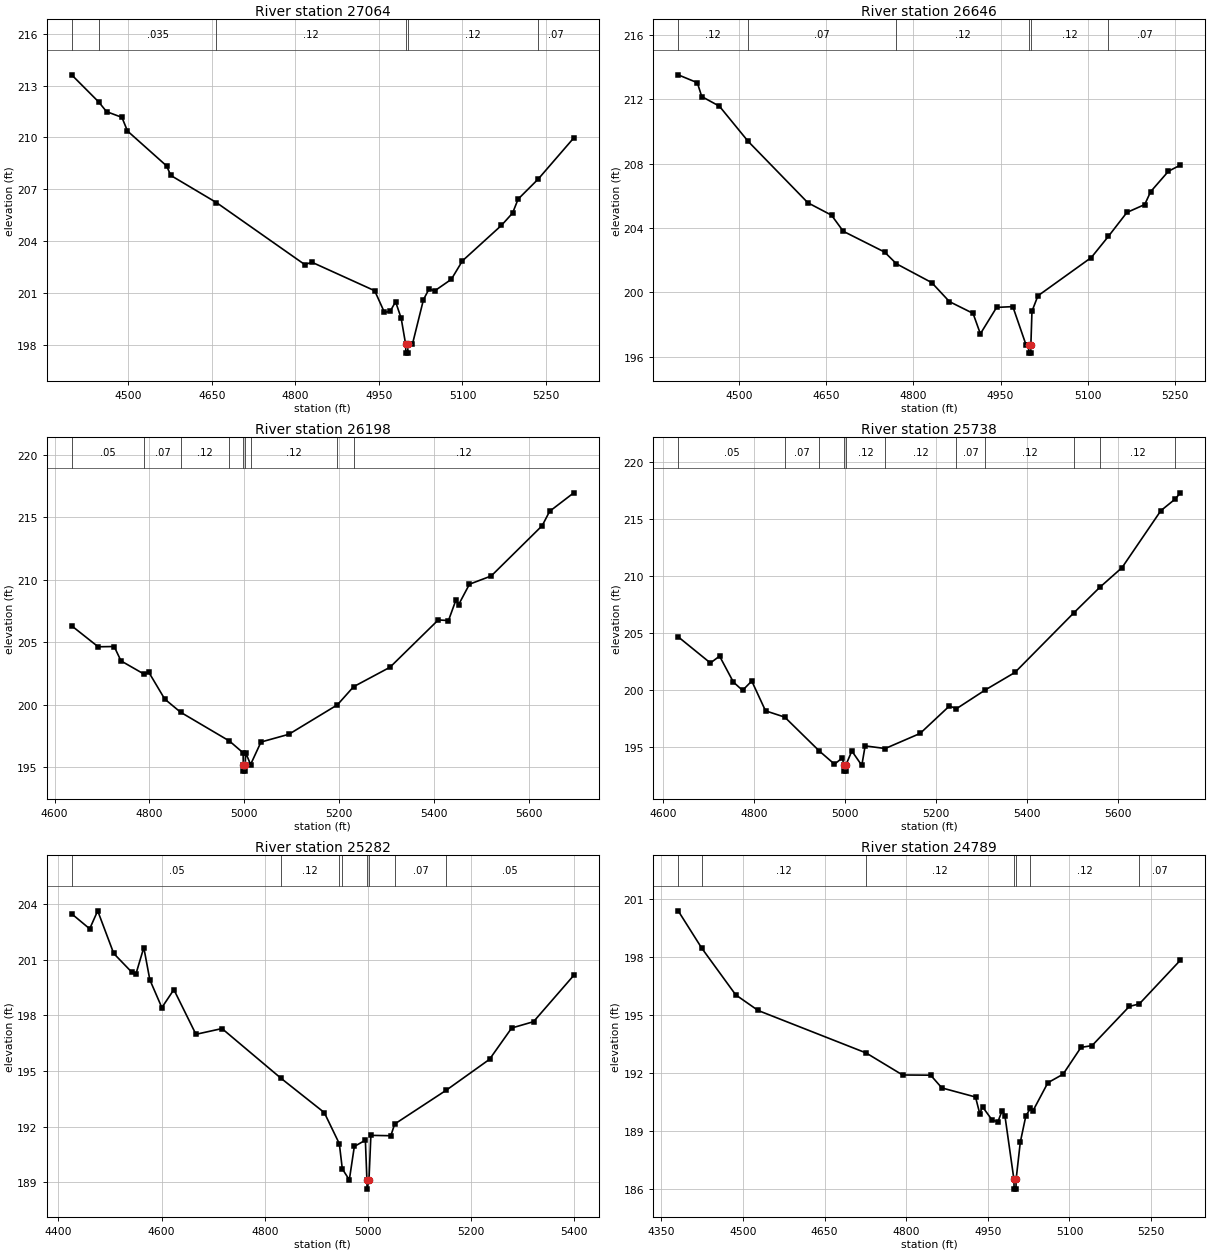
Type RM Length L Ch R = 1,27064,418,418,418
BEGIN DESCRIPTION:
TRIB TO FIFTEENMILE CREEK 53.0
END DESCRIPTION:
XS GIS Cut Line= 3
      2512625.00     13482975.00      2513225.00     13482925.00
      2513525.02     13482925.00
#Sta/Elev= 30
  4397.9  213.62  4446.5  212.05  4460.6  211.49  4488.2  211.16  4498.2  210.37
  4568.5  208.35  4576.0  207.80  4658.0  206.23  4816.8  202.64  4829.4  202.78
  4942.3  201.13  4959.8  199.88  4969.9  199.93  4979.9  200.49  4989.9  199.54
  4998.0  198.02  4998.3  197.52  5001.8  197.52  5002.0  198.02  5010.0  198.02
  5030.0  200.62  5040.0  201.23  5050.0  201.12  5080.0  201.79  5100.0  202.86
  5170.0  204.91  5190.0  205.62  5200.0  206.43  5236.1  207.59  5300.0  209.97
#Mann=6,-1,0
  4397.9    0.12       0  4446.5   0.035       0  4658.0    0.12       0
  4998.0    0.05       0  5002.0    0.12       0  5236.1    0.07       0
Bank Sta=4998,5002
Exp/Cntr=0.3,0.1

Type RM Length L Ch R = 1,26646,448,448,448
BEGIN DESCRIPTION:
TRIB TO FIFTEENMILE CREEK 52.0
END DESCRIPTION:
XS GIS Cut Line= 3
      2512625.03     13483175.01      2513225.00     13483275.00
      2513475.01     13483225.00
#Sta/Elev= 30
  4395.7  213.51  4428.6  213.02  4436.2  212.16  4466.6  211.56  4515.9  209.38
  4618.7  205.56  4659.3  204.79  4679.5  203.79  4750.5  202.50  4770.9  201.77
  4831.6  200.60  4862.0  199.42  4902.6  198.69  4915.2  197.42  4943.1  199.06
  4971.0  199.11  4993.8  196.72  4998.0  196.72  4998.3  196.22  5001.8  196.22
  5002.0  196.72  5003.9  198.82  5014.1  199.78  5105.9  202.16  5135.2  203.47
  5167.1  204.96  5197.7  205.45  5207.9  206.25  5238.5  207.52  5258.9  207.90
#Mann=6,-1,0
  4395.7    0.12       0  4515.9    0.07       0  4770.9    0.12       0
  4998.0    0.05       0  5002.0    0.12       0  5135.2    0.07       0
Bank Sta=4998,5002
Exp/Cntr=0.3,0.1

Type RM Length L Ch R = 1,26198,460,460,460
BEGIN DESCRIPTION:
TRIB TO FIFTEENMILE CREEK 51.0
END DESCRIPTION:
XS GIS Cut Line= 3
      2512824.97     13483775.01      2513175.00     13483675.00
      2513775.03     13483324.98
#Sta/Elev= 30
  4636.0  206.31  4691.9  204.63  4725.7  204.65  4740.0  203.50  4789.6  202.42
  4798.5  202.60  4832.3  200.44  4865.6  199.39  4968.7  197.08  4997.4  196.14
  4998.0  195.17  4998.3  194.67  5001.8  194.67  5002.0  195.17  5002.9  196.14
  5013.3  195.20  5035.2  197.00  5093.9  197.62  5196.3  199.98  5230.4  201.43
  5307.2  202.99  5409.0  206.78  5430.5  206.73  5446.2  208.37  5452.0  208.01
  5474.7  209.64  5520.6  210.30  5628.1  214.33  5643.8  215.48  5694.7  216.96
#Mann=9,-1,0
  4636.0    0.05       0  4789.6    0.07       0  4865.6    0.12       0
  4968.7    0.12       0  4998.0    0.05       0  5002.0    0.12       0
  5013.3    0.12       0  5196.3    0.12       0  5230.4    0.12       0
Bank Sta=4998,5002
Exp/Cntr=0.3,0.1

Type RM Length L Ch R = 1,25738,456,456,456
BEGIN DESCRIPTION:
TRIB TO FIFTEENMILE CREEK 50.0
END DESCRIPTION:
XS GIS Cut Line= 3
      2512924.96     13484024.99      2513275.00     13484075.00
      2513875.00     13483625.00
#Sta/Elev= 30
  4633.8  204.69  4704.6  202.40  4724.8  203.00  4755.1  200.73  4775.3  200.00
  4795.5  200.82  4825.8  198.21  4868.0  197.66  4944.3  194.68  4977.3  193.54
  4994.7  194.09  4998.0  193.43  4998.3  192.93  5001.8  192.93  5002.0  193.43
  5015.5  194.69  5037.4  193.43  5044.7  195.14  5088.8  194.91  5165.5  196.23
  5230.1  198.64  5245.2  198.39  5309.2  200.05  5373.9  201.57  5504.1  206.82
  5560.3  209.02  5609.3  210.75  5694.7  215.74  5726.3  216.76  5737.4  217.30
#Mann=11,-1,0
  4633.8    0.05       0  4868.0    0.07       0  4944.3    0.12       0
  4998.0    0.05       0  5002.0    0.12       0  5088.8    0.12       0
  5245.2    0.07       0  5309.2    0.12       0  5504.1    0.07       0
  5560.3    0.12       0  5726.3    0.07       0
Bank Sta=4998,5002
Exp/Cntr=0.3,0.1

Type RM Length L Ch R = 1,25282,493,493,493
BEGIN DESCRIPTION:
TRIB TO FIFTEENMILE CREEK 49.0
END DESCRIPTION:
XS GIS Cut Line= 3
      2512875.02     13484175.01      2513375.00     13484475.00
      2513675.01     13484224.99
#Sta/Elev= 30
  4425.5  203.48  4460.5  202.67  4476.0  203.64  4507.1  201.34  4542.1  200.33
  4549.9  200.21  4565.4  201.66  4577.1  199.92  4600.4  198.42  4623.7  199.39
  4666.5  196.98  4717.0  197.29  4831.8  194.60  4915.3  192.76  4944.5  191.08
  4950.3  189.72  4963.9  189.13  4973.6  190.93  4995.0  191.27  4998.0  189.13
  4998.3  188.63  5002.0  189.13  5005.7  191.53  5044.4  191.51  5051.8  192.14
  5152.1  193.97  5235.7  195.63  5278.7  197.32  5321.0  197.66  5399.1  200.16
#Mann=8,-1,0
  4425.5    0.05       0  4831.8    0.12       0  4944.5    0.07       0
  4950.3    0.12       0  4998.0    0.05       0  5002.0    0.12       0
  5051.8    0.07       0  5152.1    0.05       0
Bank Sta=4998,5002
Exp/Cntr=0.3,0.1

Type RM Length L Ch R = 1,24789,467,467,467
BEGIN DESCRIPTION:
TRIB TO FIFTEENMILE CREEK 48.0
END DESCRIPTION:
XS GIS Cut Line= 3
      2512874.98     13484774.99      2513475.00     13484925.00
      2513774.97     13484875.00
#Sta/Elev= 30
  4381.1  200.40  4424.6  198.46  4486.8  196.05  4528.0  195.24  4726.5  193.04
  4793.4  191.90  4845.0  191.89  4865.6  191.23  4927.4  190.76  4935.2  189.90
  4940.3  190.25  4958.4  189.55  4968.7  189.49  4976.4  190.06  4981.5  189.78
  4998.0  186.49  4998.3  185.99  5001.8  185.99  5002.0  186.49  5009.7  188.42
  5019.9  189.78  5028.2  190.17  5032.5  190.02  5060.4  191.50  5088.3  191.94
  5121.2  193.33  5141.5  193.42  5210.0  195.45  5228.4  195.58  5303.7  197.84
#Mann=7,-1,0
  4381.1    0.07       0  4424.6    0.12       0  4726.5    0.12       0
  4998.0    0.05       0  5002.0    0.12       0  5028.2    0.12       0
  5228.4    0.07       0
Bank Sta=4998,5002
Exp/Cntr=0.3,0.1

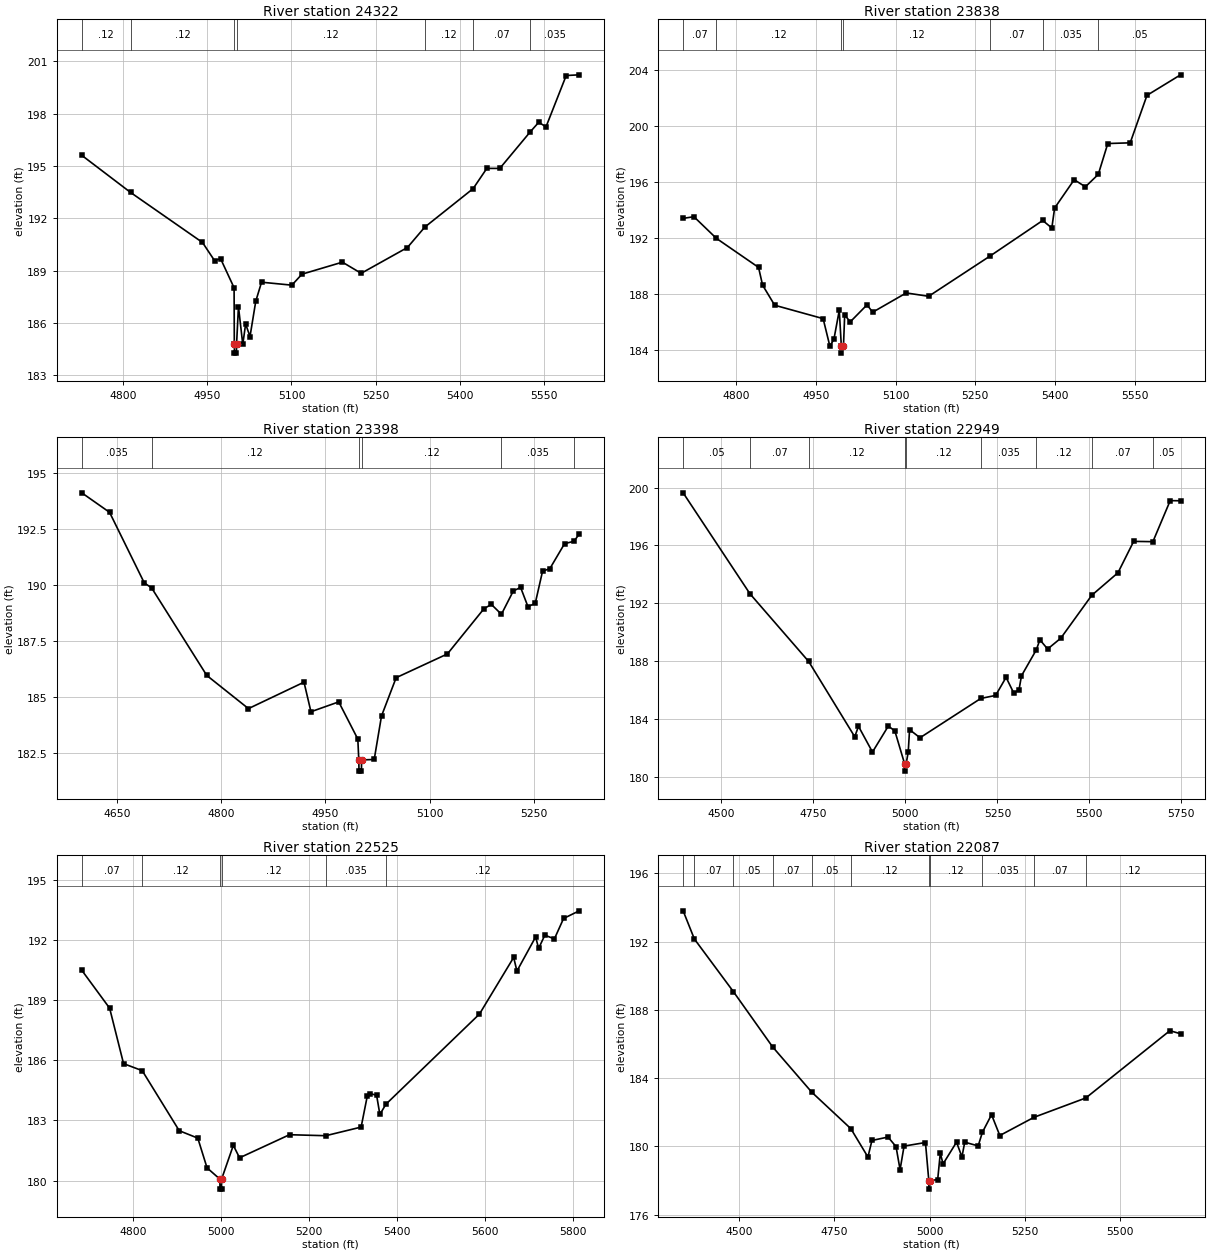
Type RM Length L Ch R = 1,24322,484,484,484
BEGIN DESCRIPTION:
TRIB TO FIFTEENMILE CREEK 47.0
END DESCRIPTION:
XS GIS Cut Line= 3
      2513025.01     13485424.99      2513275.00     13485325.00
      2513874.99     13485175.00
#Sta/Elev= 30
  4725.8  195.61  4812.9  193.48  4941.2  190.61  4962.7  189.57  4973.5  189.68
  4997.6  188.01  4998.0  184.76  4998.3  184.26  5001.8  184.26  5002.0  184.76
  5005.4  186.93  5013.1  184.76  5018.2  185.93  5026.0  185.21  5036.3  187.24
  5046.6  188.33  5100.7  188.16  5118.7  188.79  5190.9  189.48  5224.4  188.84
  5306.9  190.32  5337.9  191.49  5424.2  193.70  5448.6  194.86  5471.8  194.86
  5526.2  196.96  5541.4  197.51  5554.2  197.24  5590.3  200.19  5613.5  200.23
#Mann=7,-1,0
  4725.8    0.12       0  4812.9    0.12       0  4998.0    0.05       0
  5002.0    0.12       0  5337.9    0.12       0  5424.2    0.07       0
  5526.2   0.035       0
Bank Sta=4998,5002
Exp/Cntr=0.3,0.1

Type RM Length L Ch R = 1,23838,440,440,440
BEGIN DESCRIPTION:
TRIB TO FIFTEENMILE CREEK 46.0
END DESCRIPTION:
XS GIS Cut Line= 3
      2513124.96     13485674.99      2513425.00     13485725.00
      2514024.97     13485525.01
#Sta/Elev= 30
  4700.1  193.41  4720.4  193.53  4762.7  191.98  4842.1  189.90  4849.7  188.63
  4872.5  187.19  4963.7  186.23  4976.4  184.26  4984.0  184.75  4994.1  186.82
  4998.0  184.26  4998.3  183.76  5002.0  184.26  5004.3  186.49  5014.8  186.00
  5046.4  187.22  5057.0  186.69  5120.2  188.07  5162.4  187.83  5277.9  190.71
  5377.2  193.26  5394.3  192.72  5399.6  194.15  5436.5  196.18  5457.5  195.67
  5481.8  196.56  5499.7  198.77  5541.9  198.82  5573.5  202.22  5636.7  203.69
#Mann=7,-1,0
  4700.1    0.07       0  4762.7    0.12       0  4998.0    0.05       0
  5002.0    0.12       0  5277.9    0.07       0  5377.2   0.035       0
  5481.8    0.05       0
Bank Sta=4998,5002
Exp/Cntr=0.3,0.1

Type RM Length L Ch R = 1,23398,449,449,449
BEGIN DESCRIPTION:
TRIB TO FIFTEENMILE CREEK 45.0
END DESCRIPTION:
XS GIS Cut Line= 3
      2513174.98     13486025.00      2513575.00     13486025.00
      2513875.05     13485924.98
#Sta/Elev= 30
  4599.1  194.10  4639.1  193.23  4689.1  190.08  4699.6  189.86  4779.1  185.95
  4839.1  184.47  4919.1  185.65  4929.1  184.33  4969.1  184.77  4996.6  183.11
  4998.0  182.18  4998.3  181.68  5001.8  181.68  5002.0  182.18  5020.2  182.20
  5030.7  184.14  5051.8  185.85  5125.6  186.91  5178.3  188.93  5188.9  189.12
  5203.4  188.68  5220.5  189.72  5231.0  189.88  5241.6  189.02  5252.1  189.17
  5262.6  190.60  5273.2  190.72  5294.3  191.83  5308.0  191.94  5315.4  192.26
#Mann=6,-1,0
  4599.1   0.035       0  4699.6    0.12       0  4998.0    0.05       0
  5002.0    0.12       0  5203.4   0.035       0  5308.0    0.12       0
Bank Sta=4998,5002
Exp/Cntr=0.3,0.1

Type RM Length L Ch R = 1,22949,424,424,424
BEGIN DESCRIPTION:
TRIB TO FIFTEENMILE CREEK 44.0
END DESCRIPTION:
XS GIS Cut Line= 3
      2513025.02     13486525.00      2513625.00     13486425.00
      2514125.03     13485874.97
#Sta/Elev= 30
  4396.1  199.64  4577.8  192.65  4737.2  187.97  4862.4  182.76  4872.6  183.48
  4910.6  181.70  4953.7  183.50  4971.4  183.16  4998.0  180.88  4998.3  180.38
  5002.0  180.88  5007.7  181.69  5011.4  183.25  5039.8  182.69  5204.9  185.41
  5245.3  185.62  5273.6  186.87  5294.6  185.78  5308.8  186.01  5315.5  186.98
  5355.7  188.77  5365.5  189.47  5386.5  188.83  5422.3  189.58  5506.5  192.55
  5577.7  194.11  5620.3  196.28  5672.6  196.26  5719.6  199.10  5747.7  199.09
#Mann=9,-1,0
  4396.1    0.05       0  4577.8    0.07       0  4737.2    0.12       0
  4998.0    0.05       0  5002.0    0.12       0  5204.9   0.035       0
  5355.7    0.12       0  5506.5    0.07       0  5672.6    0.05       0
Bank Sta=4998,5002
Exp/Cntr=0.3,0.1

Type RM Length L Ch R = 1,22525,438,438,438
BEGIN DESCRIPTION:
TRIB TO FIFTEENMILE CREEK 43.0
END DESCRIPTION:
XS GIS Cut Line= 3
      2513274.97     13486674.99      2513575.00     13486775.00
      2514175.00     13486225.00
#Sta/Elev= 30
  4684.3  190.48  4747.6  188.59  4779.2  185.83  4821.6  185.48  4905.7  182.49
  4947.9  182.12  4968.9  180.64  4998.0  180.08  4998.3  179.58  5001.8  179.58
  5002.0  180.08  5028.6  181.76  5042.8  181.14  5156.3  182.29  5238.5  182.24
  5319.0  182.67  5333.2  184.24  5340.0  184.34  5354.2  184.25  5361.6  183.30
  5375.4  183.81  5587.9  188.30  5665.6  191.12  5673.0  190.44  5715.5  192.14
  5722.3  191.57  5736.5  192.23  5758.1  192.04  5779.0  193.06  5814.5  193.44
#Mann=6,-1,0
  4684.3    0.07       0  4821.6    0.12       0  4998.0    0.05       0
  5002.0    0.12       0  5238.5   0.035       0  5375.4    0.12       0
Bank Sta=4998,5002
Exp/Cntr=0.3,0.1

Type RM Length L Ch R = 1,22087,462,462,462
BEGIN DESCRIPTION:
TRIB TO FIFTEENMILE CREEK 42.0
END DESCRIPTION:
XS GIS Cut Line= 3
      2513125.03     13486875.01      2513725.00     13487075.00
      2514224.99     13486625.01
#Sta/Elev= 30
  4353.4  193.80  4382.9  192.15  4485.5  189.06  4588.2  185.83  4690.8  183.18
  4793.5  181.04  4838.3  179.38  4848.8  180.35  4891.0  180.55  4912.0  179.99
  4922.6  178.64  4933.1  180.02  4989.2  180.23  4998.0  178.00  4998.3  177.50
  5002.0  178.00  5021.3  178.06  5028.1  179.60  5035.5  178.98  5070.7  180.25
  5084.9  179.39  5092.3  180.25  5127.5  180.03  5138.6  180.83  5162.6  181.86
  5184.3  180.64  5274.3  181.71  5410.0  182.84  5630.5  186.78  5658.5  186.60
#Mann=11,-1,0
  4353.4    0.12       0  4382.9    0.07       0  4485.5    0.05       0
  4588.2    0.07       0  4690.8    0.05       0  4793.5    0.12       0
  4998.0    0.05       0  5002.0    0.12       0  5138.6   0.035       0
  5274.3    0.07       0  5410.0    0.12       0
Bank Sta=4998,5002
Exp/Cntr=0.3,0.1

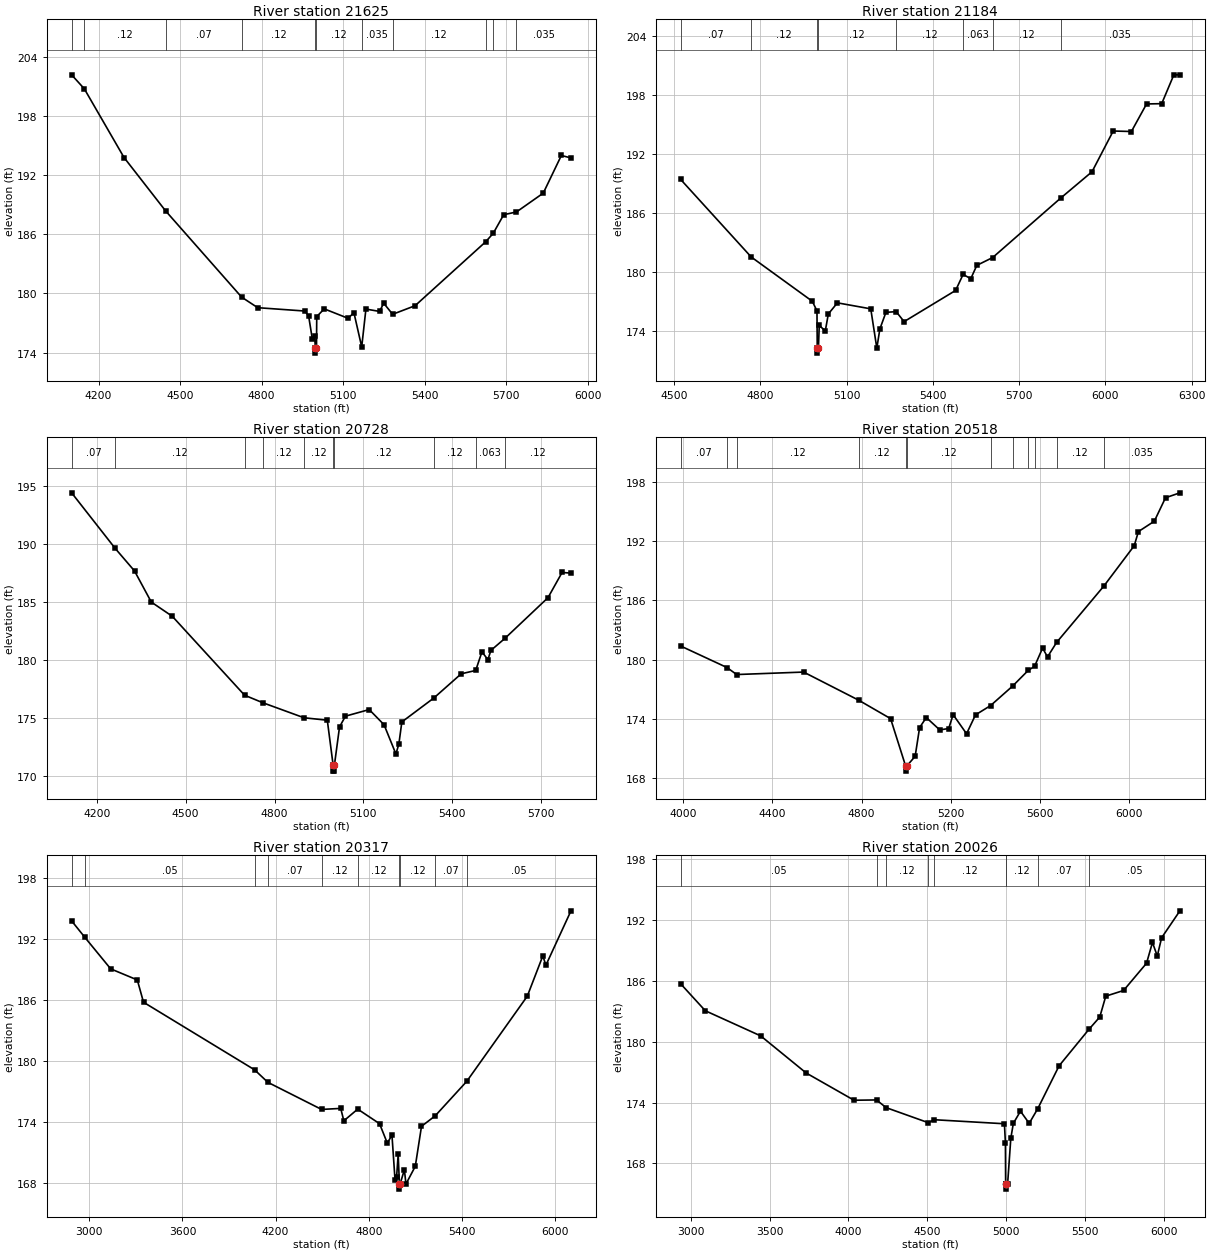
Type RM Length L Ch R = 1,21625,441,441,441
BEGIN DESCRIPTION:
TRIB TO FIFTEENMILE CREEK 41.0
END DESCRIPTION:
XS GIS Cut Line= 3
      2512875.00     13487075.00      2513675.00     13487475.00
      2514474.98     13487974.99
#Sta/Elev= 30
  4100.9  202.18  4147.6  200.76  4293.8  193.79  4446.4  188.39  4726.6  179.63
  4785.7  178.56  4959.0  178.22  4973.0  177.74  4986.9  175.36  4995.3  175.64
  4998.0  174.45  4998.2  173.95  5002.1  174.45  5003.0  177.66  5030.7  178.44
  5118.6  177.48  5139.8  178.06  5168.5  174.58  5184.0  178.42  5234.1  178.18
  5249.5  179.01  5282.4  177.89  5365.0  178.76  5624.2  185.23  5652.5  186.10
  5691.1  187.99  5738.1  188.27  5836.7  190.18  5903.3  194.00  5938.7  193.75
#Mann=11,-1,0
  4100.9    0.07       0  4147.6    0.12       0  4446.4    0.07       0
  4726.6    0.12       0  4998.0    0.05       0  5002.1    0.12       0
  5168.5   0.035       0  5282.4    0.12       0  5624.2    0.07       0
  5652.5    0.12       0  5738.1   0.035       0
Bank Sta=4998,5002.1
Exp/Cntr=0.3,0.1

Type RM Length L Ch R = 1,21184,456,456,456
BEGIN DESCRIPTION:
TRIB TO FIFTEENMILE CREEK 40.0
END DESCRIPTION:
XS GIS Cut Line= 3
      2513024.97     13487524.98      2513425.00     13487775.00
      2514625.05     13488175.02
#Sta/Elev= 30
  4522.6  189.40  4768.3  181.51  4980.8  177.01  4997.0  176.03  4998.0  172.24
  4998.2  171.74  5002.1  172.24  5004.9  174.55  5026.0  174.00  5036.5  175.72
  5068.1  176.85  5184.1  176.24  5205.2  172.24  5215.7  174.19  5236.8  175.88
  5272.4  175.96  5300.0  174.94  5479.2  178.11  5505.3  179.74  5531.9  179.30
  5553.0  180.66  5608.0  181.45  5844.5  187.49  5953.6  190.17  6027.3  194.31
  6090.6  194.26  6143.3  197.06  6196.0  197.09  6238.2  200.02  6259.3  200.02
#Mann=8,-1,0
  4522.6    0.07       0  4768.3    0.12       0  4998.0    0.05       0
  5002.1    0.12       0  5272.4    0.12       0  5505.3   0.063       0
  5608.0    0.12       0  5844.5   0.035       0
Bank Sta=4998,5002.1
Exp/Cntr=0.3,0.1

Type RM Length L Ch R = 1,20728,210,210,210
BEGIN DESCRIPTION:
TRIB TO FIFTEENMILE CREEK 39.0
END DESCRIPTION:
XS GIS Cut Line= 3
      2512825.02     13487525.02      2513425.00     13488175.00
      2514224.97     13488125.00
#Sta/Elev= 30
  4114.9  194.43  4262.2  189.62  4327.2  187.68  4383.9  184.99  4454.8  183.76
  4698.9  176.94  4760.5  176.29  4899.7  174.99  4978.2  174.78  4998.0  170.88
  4998.2  170.38  5001.8  170.38  5002.1  170.88  5019.5  174.20  5039.5  175.13
  5119.7  175.70  5169.8  174.39  5209.9  171.86  5219.9  172.73  5229.9  174.63
  5338.0  176.70  5430.3  178.79  5479.3  179.08  5500.4  180.69  5520.5  180.01
  5530.5  180.81  5577.9  181.85  5723.4  185.37  5771.0  187.55  5801.0  187.49
#Mann=10,-1,0
  4114.9    0.07       0  4262.2    0.12       0  4698.9    0.12       0
  4760.5    0.12       0  4899.7    0.12       0  4998.0    0.05       0
  5002.1    0.12       0  5338.0    0.12       0  5479.3   0.063       0
  5577.9    0.12       0
Bank Sta=4998,5002.1
Exp/Cntr=0.3,0.1

Type RM Length L Ch R = 1,20518,201,201,201
BEGIN DESCRIPTION:
Mapping XS d674b12d
END DESCRIPTION:
XS GIS Cut Line= 3
      2512313.36     13488374.85      2513306.37     13488347.07
      2514549.40     13488256.80
#Sta/Elev= 30
  3988.2  181.40  4196.2  179.22  4239.9  178.51  4540.1  178.76  4786.7  175.92
  4930.2  174.05  4997.9  169.24  4998.2  168.74  5002.1  169.24  5040.4  170.24
  5060.4  173.15  5090.5  174.16  5150.7  172.91  5190.8  173.05  5210.8  174.45
  5271.0  172.52  5311.1  174.43  5378.7  175.37  5477.4  177.34  5547.2  178.92
  5576.2  179.35  5611.9  181.18  5634.2  180.30  5674.9  181.76  5886.8  187.46
  6023.0  191.54  6041.8  192.97  6113.2  194.02  6163.3  196.39  6227.9  196.89
#Mann=12,-1,0
  3988.2    0.07       0  4196.2   0.035       0  4239.9    0.12       0
  4786.7    0.12       0  4997.9    0.05       0  5002.1    0.12       0
  5378.7    0.12       0  5477.4   0.035       0  5547.2    0.12       0
  5576.2   0.063       0  5674.9    0.12       0  5886.8   0.035       0
Bank Sta=4997.9,5002.1
Exp/Cntr=0.3,0.1

Type RM Length L Ch R = 1,20317,291,291,291
BEGIN DESCRIPTION:
Mapping XS 0ddb51ed
END DESCRIPTION:
XS GIS Cut Line= 3
      2511252.08     13488597.94      2513370.88     13488531.90
      2514466.01     13488460.36
#Sta/Elev= 30
  2885.8  193.77  2969.1  192.19  3137.3  189.06  3308.9  187.97  3348.9  185.78
  4064.6  179.14  4150.3  177.91  4496.2  175.25  4619.6  175.35  4639.6  174.13
  4729.0  175.28  4869.7  173.85  4919.7  171.94  4949.7  172.73  4969.7  168.27
  4979.7  168.63  4989.7  170.83  4997.8  167.92  4998.1  167.42  5002.2  167.92
  5029.8  169.33  5039.8  167.92  5100.0  169.66  5140.0  173.59  5228.2  174.62
  5431.7  178.01  5821.5  186.37  5921.7  190.33  5941.7  189.42  6103.1  194.76
#Mann=10,-1,0
  2885.8   0.035       0  2969.1    0.05       0  4064.6   0.035       0
  4150.3    0.07       0  4496.2    0.12       0  4729.0    0.12       0
  4997.8    0.05       0  5002.2    0.12       0  5228.2    0.07       0
  5431.7    0.05       0
Bank Sta=4997.8,5002.2
Exp/Cntr=0.3,0.1

Type RM Length L Ch R = 1,20026,324,324,324
BEGIN DESCRIPTION:
Mapping XS 708d2887
END DESCRIPTION:
XS GIS Cut Line= 3
      2511268.60     13488988.67      2513310.34     13488812.57
      2514405.52     13488586.93
#Sta/Elev= 30
  2935.7  185.73  3092.7  183.06  3444.0  180.58  3732.4  176.92  4036.2  174.23
  4178.6  174.26  4239.8  173.50  4508.1  172.01  4543.0  172.31  4990.0  171.91
  4996.3  170.04  4997.8  165.96  4998.1  165.46  5002.2  165.96  5010.2  165.96
  5030.6  170.48  5046.6  171.95  5091.8  173.15  5147.2  171.95  5201.9  173.41
  5336.9  177.63  5526.9  181.24  5594.8  182.44  5633.0  184.50  5745.8  185.06
  5891.6  187.75  5929.1  189.80  5959.7  188.46  5987.1  190.26  6103.2  192.92
#Mann=9,-1,0
  2935.7    0.05       0  4178.6    0.12       0  4239.8    0.12       0
  4508.1    0.07       0  4543.0    0.12       0  4997.8    0.05       0
  5002.2    0.12       0  5201.9    0.07       0  5526.9    0.05       0
Bank Sta=4997.8,5002.2
Exp/Cntr=0.3,0.1

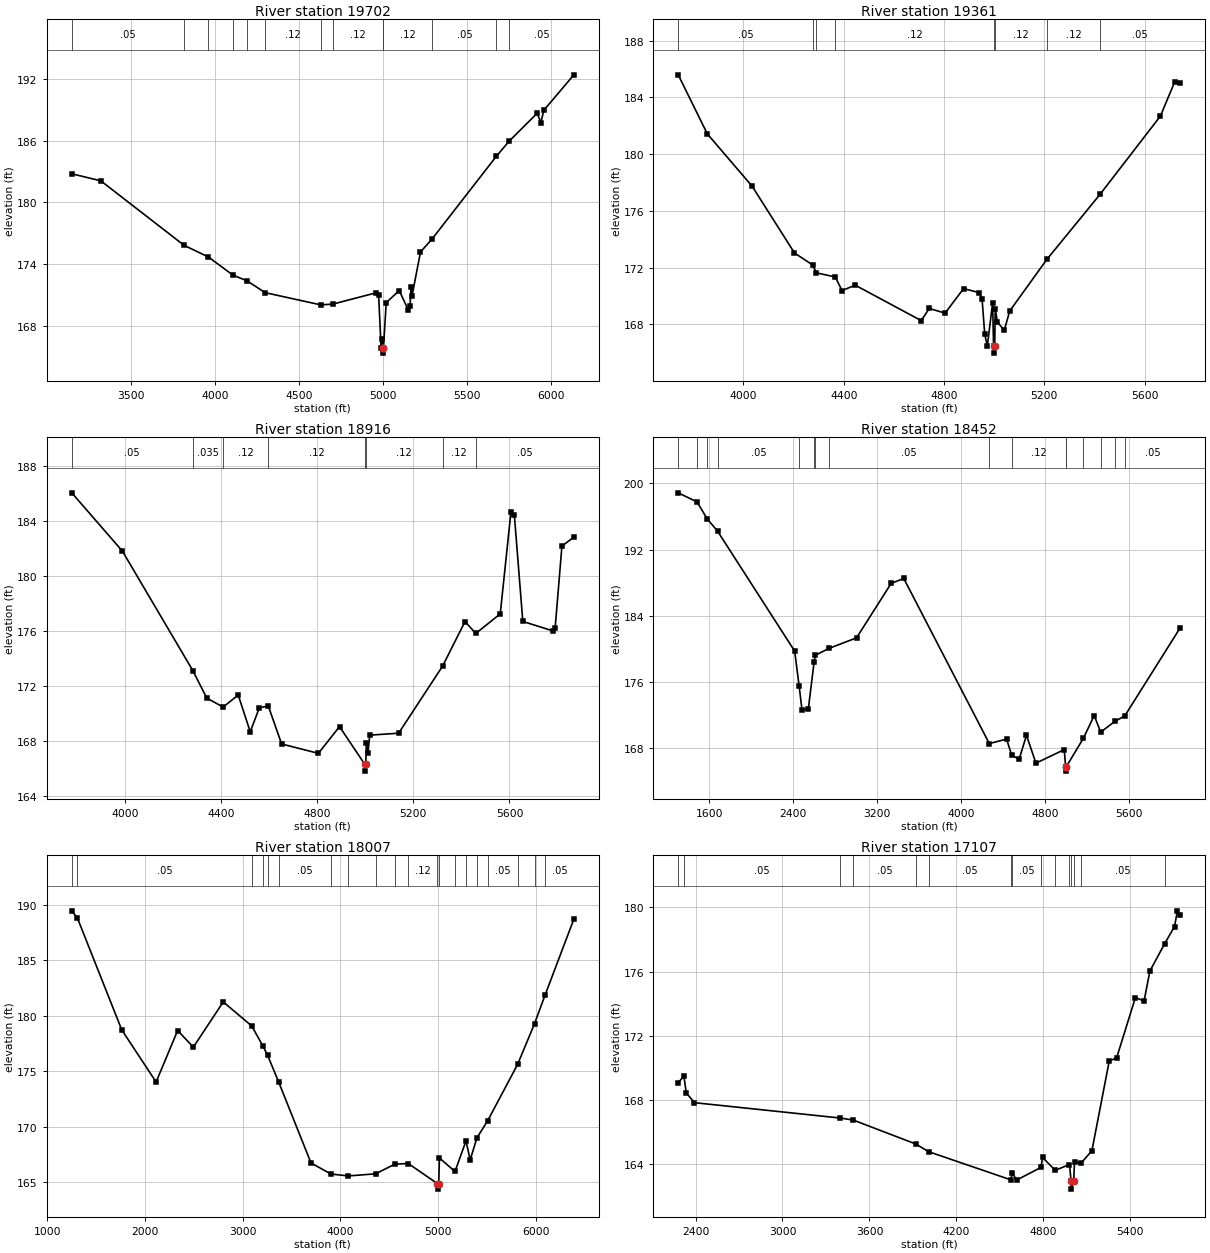
Type RM Length L Ch R = 1,19702,341,341,341
BEGIN DESCRIPTION:
Mapping XS f534d482
END DESCRIPTION:
XS GIS Cut Line= 3
      2511472.25     13489527.99      2513249.81     13489126.25
      2514339.42     13488730.03
#Sta/Elev= 30
  3151.2  182.78  3323.4  182.10  3818.9  175.82  3961.9  174.70  4109.6  172.92
  4191.9  172.38  4299.3  171.23  4629.9  170.04  4702.8  170.12  4960.1  171.22
  4973.6  170.97  4988.2  165.89  4993.5  166.72  4997.8  165.85  4998.1  165.35
  5002.2  165.85  5018.7  170.26  5096.2  171.43  5149.4  169.55  5160.0  169.92
  5166.4  171.76  5171.7  170.89  5222.2  175.18  5292.8  176.48  5673.2  184.49
  5748.6  185.95  5915.5  188.67  5936.8  187.76  5955.1  188.96  6133.0  192.40
#Mann=13,-1,0
  3151.2    0.05       0  3818.9    0.12       0  3961.9    0.05       0
  4109.6    0.12       0  4191.9    0.05       0  4299.3    0.12       0
  4629.9    0.12       0  4702.8    0.12       0  4997.8    0.05       0
  5002.2    0.12       0  5292.8    0.05       0  5673.2    0.07       0
  5748.6    0.05       0
Bank Sta=4997.8,5002.2
Exp/Cntr=0.3,0.1

Type RM Length L Ch R = 1,19361,445,445,445
BEGIN DESCRIPTION:
TRIB TO FIFTEENMILE CREEK 36.0
END DESCRIPTION:
XS GIS Cut Line= 3
      2512075.04     13489824.99      2513275.00     13489425.00
      2513924.99     13489075.00
#Sta/Elev= 30
  3739.7  185.59  3855.6  181.43  4034.8  177.73  4203.5  173.03  4275.5  172.19
  4291.1  171.63  4366.3  171.34  4393.2  170.38  4445.9  170.76  4709.4  168.26
  4741.0  169.12  4804.3  168.79  4878.1  170.52  4941.3  170.23  4951.9  169.80
  4962.4  167.32  4972.9  166.47  4994.0  169.52  4997.8  166.47  4998.1  165.97
  5002.2  166.47  5004.6  169.11  5012.7  168.18  5040.3  167.57  5062.2  168.94
  5210.9  172.59  5422.4  177.16  5663.3  182.68  5720.1  185.08  5742.8  185.04
#Mann=8,-1,0
  3739.7    0.05       0  4275.5   0.035       0  4291.1    0.05       0
  4366.3    0.12       0  4997.8    0.05       0  5002.2    0.12       0
  5210.9    0.12       0  5422.4    0.05       0
Bank Sta=4997.8,5002.2
Exp/Cntr=0.3,0.1

Type RM Length L Ch R = 1,18916,464,464,464
BEGIN DESCRIPTION:
TRIB TO FIFTEENMILE CREEK 35.0
END DESCRIPTION:
XS GIS Cut Line= 3
      2512075.02     13489925.00      2513275.00     13489825.00
      2513924.98     13489225.02
#Sta/Elev= 30
  3779.1  186.02  3989.8  181.79  4282.8  173.12  4341.0  171.12  4409.1  170.48
  4471.5  171.35  4521.6  168.68  4559.3  170.42  4596.6  170.56  4652.1  167.80
  4805.1  167.12  4892.9  169.06  4997.8  166.33  4998.1  165.83  5002.2  166.33
  5004.5  167.86  5011.3  167.14  5018.7  168.44  5138.9  168.58  5321.8  173.45
  5415.0  176.68  5460.0  175.82  5561.6  177.24  5606.1  184.63  5620.3  184.40
  5655.5  176.69  5783.1  175.99  5789.9  176.20  5818.2  182.15  5867.8  182.81
#Mann=8,-1,0
  3779.1    0.05       0  4282.8   0.035       0  4409.1    0.12       0
  4596.6    0.12       0  4997.8    0.05       0  5002.2    0.12       0
  5321.8    0.12       0  5460.0    0.05       0
Bank Sta=4997.8,5002.2
Exp/Cntr=0.3,0.1

Type RM Length L Ch R = 1,18452,445,445,445
BEGIN DESCRIPTION:
TRIB TO FIFTEENMILE CREEK 34.0
END DESCRIPTION:
XS GIS Cut Line= 3
      2509734.80     13490206.95      2513425.00     13490225.00
      2514174.98     13489425.02
#Sta/Elev= 30
  1304.4  198.86  1483.2  197.76  1581.5  195.70  1679.8  194.22  2414.6  179.73
  2457.4  175.47  2484.6  172.60  2544.6  172.74  2599.9  178.43  2611.6  179.23
  2741.5  180.06  3004.6  181.34  3334.6  187.92  3454.6  188.51  4270.2  168.56
  4434.6  169.10  4483.8  167.15  4554.6  166.67  4624.6  169.56  4714.6  166.19
  4984.6  167.83  4997.8  165.73  4998.1  165.23  5002.3  165.73  5166.2  169.18
  5270.4  171.95  5331.8  169.94  5467.1  171.24  5561.9  171.91  6091.2  182.57
#Mann=16,-1,0
  1304.4    0.05       0  1483.2    0.07       0  1581.5   0.035       0
  1679.8    0.05       0  2457.4   0.063       0  2599.9    0.05       0
  2611.6   0.063       0  2741.5    0.05       0  4270.2    0.12       0
  4483.8    0.12       0  4997.8    0.05       0  5002.3    0.12       0
  5166.2    0.12       0  5331.8    0.05       0  5467.1    0.12       0
  5561.9    0.05       0
Bank Sta=4997.8,5002.3
Exp/Cntr=0.3,0.1

Type RM Length L Ch R = 1,18007,900,900,900
BEGIN DESCRIPTION:
TRIB TO FIFTEENMILE CREEK 33.0
END DESCRIPTION:
XS GIS Cut Line= 4
      2510144.84     13490389.92      2513642.99     13490661.76
      2513675.00     13490425.00      2514375.02     13489224.96
#Sta/Elev= 30
  1252.4  189.45  1311.0  188.78  1764.1  178.71  2115.2  174.02  2335.8  178.66
  2496.3  177.16  2802.2  181.24  3093.4  179.07  3205.9  177.30  3256.6  176.41
  3369.7  174.01  3699.9  166.72  3904.6  165.72  4083.7  165.55  4360.9  165.74
  4557.7  166.61  4694.9  166.67  4993.4  164.86  4994.3  164.36  5006.9  164.86
  5013.7  167.17  5173.5  165.95  5285.8  168.71  5328.7  167.00  5398.1  168.99
  5507.9  170.53  5813.5  175.60  5986.8  179.27  6094.3  181.84  6389.3  188.70
#Mann=20,-1,0
  1252.4   0.035       0  1311.0    0.05       0  3093.4   0.035       0
  3205.9    0.05       0  3256.6   0.035       0  3369.7    0.05       0
  3904.6    0.12       0  4083.7    0.05       0  4360.9    0.12       0
  4557.7    0.07       0  4694.9    0.12       0  4993.4    0.05       0
  5006.9    0.12       0  5173.5    0.12       0  5285.8    0.05       0
  5398.1    0.12       0  5507.9    0.05       0  5813.5    0.05       0
  5986.8    0.07       0  6094.3    0.05       0
Bank Sta=4993.4,5006.9
Exp/Cntr=0.3,0.1

Type RM Length L Ch R = 1,17107,441,441,441
BEGIN DESCRIPTION:
TRIB TO FIFTEENMILE CREEK 31.0
END DESCRIPTION:
XS GIS Cut Line= 4
      2513331.23     13492699.52      2514325.00     13491626.90
      2514325.00     13490375.00      2514325.00     13489625.03
#Sta/Elev= 30
  2280.8  169.09  2319.9  169.49  2336.3  168.45  2393.0  167.84  3393.5  166.89
  3488.1  166.76  3919.2  165.27  4008.4  164.79  4574.9  163.04  4585.9  163.47
  4614.9  163.02  4783.1  163.81  4794.9  164.43  4881.7  163.63  4980.3  163.99
  4991.2  162.96  4992.4  162.46  5009.2  162.96  5014.9  164.15  5058.6  164.06
  5134.9  164.85  5254.9  170.45  5304.9  170.61  5434.9  174.38  5494.9  174.17
  5534.9  176.03  5637.2  177.74  5704.9  178.80  5724.9  179.78  5744.9  179.54
#Mann=15,-1,0
  2280.8   0.045       0  2319.9    0.05       0  3393.5   0.035       0
  3488.1    0.05       0  3919.2    0.12       0  4008.4    0.05       0
  4574.9    0.12       0  4585.9    0.05       0  4783.1    0.12       0
  4881.7    0.05       0  4980.3    0.12       0  4991.2    0.05       0
  5009.2    0.12       0  5058.6    0.05       0  5637.2    0.07       0
Bank Sta=4991.2,5009.2
Exp/Cntr=0.3,0.1