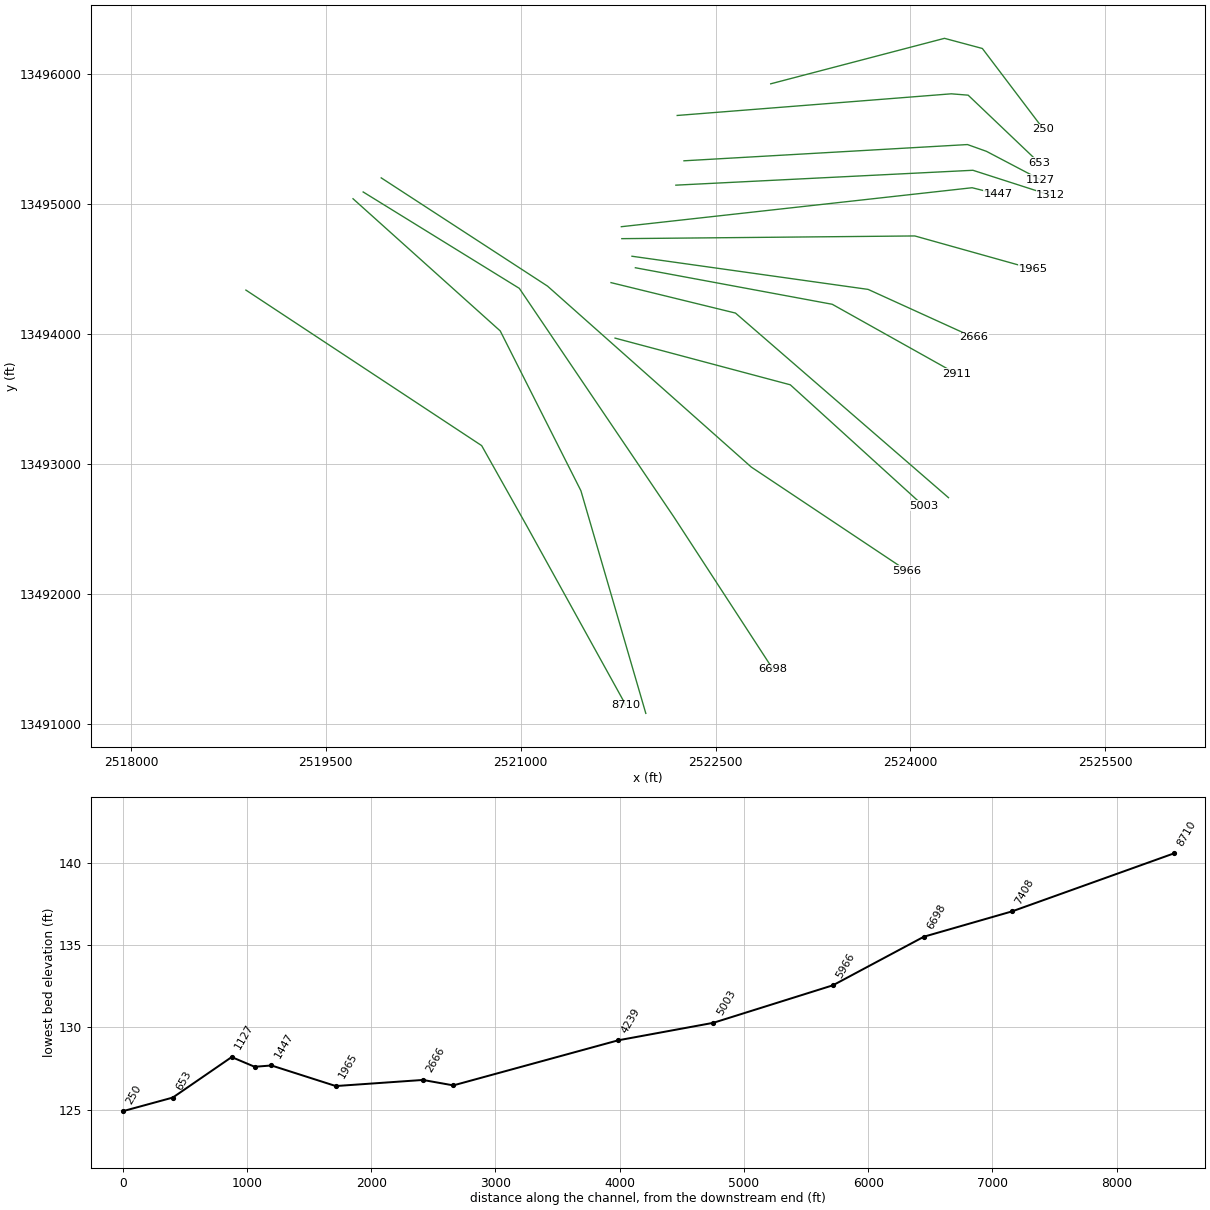
HEC-RAS study TRIB TO FIFTEENMILE CREEK.prj: TRIB TO FIFTEENMILE CREEK Detailed Study

--- TRIB TO FIFTEENMILE CREEK.g01 (geometry) --- (continued)

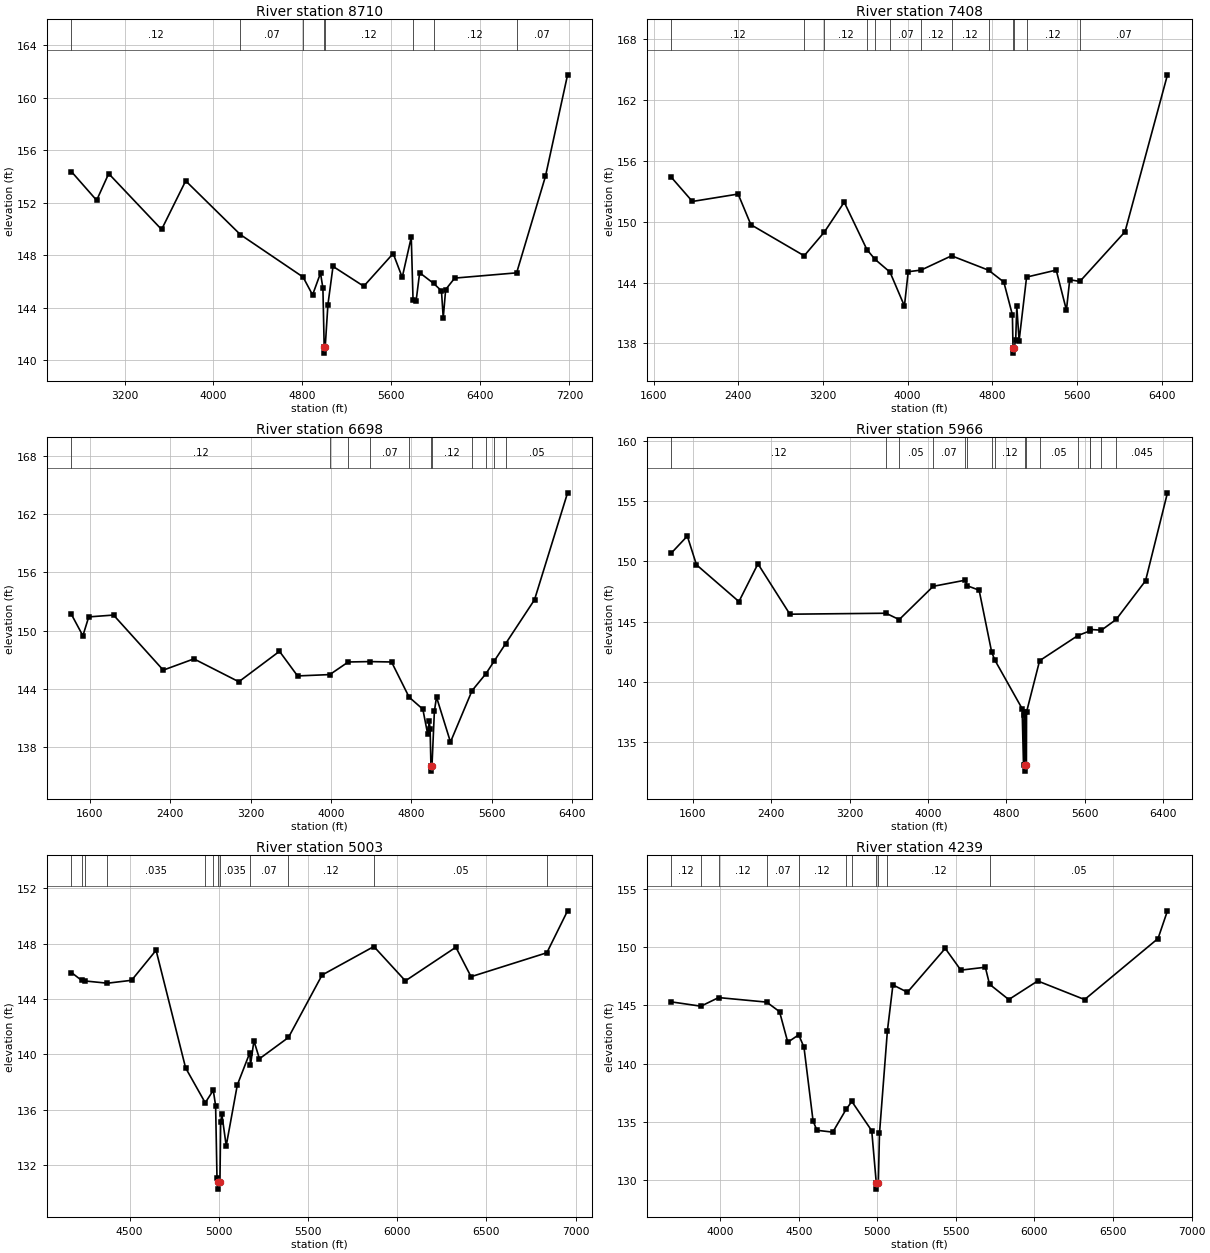
Type RM Length L Ch R = 1,8710,1302,1302,1302
BEGIN DESCRIPTION:
Mapping XS d7abceed
END DESCRIPTION:
XS GIS Cut Line= 4
      2518884.95     13494337.16      2520699.86     13493139.83
      2521047.08     13492521.77      2521810.43     13491140.80
#Sta/Elev= 30
  2722.9  154.37  2949.2  152.19  3057.6  154.22  3533.3  149.97  3750.0  153.67
  4241.8  149.58  4805.4  146.35  4891.1  144.99  4962.3  146.65  4983.9  145.51
  4995.3  141.06  4995.8  140.56  5004.8  141.06  5028.9  144.24  5074.8  147.16
  5351.2  145.65  5615.8  148.14  5697.2  146.33  5778.5  149.38  5794.5  144.59
  5822.0  144.53  5853.8  146.68  5980.2  145.86  6050.0  145.30  6066.0  143.24
  6087.8  145.40  6169.1  146.27  6726.0  146.67  6985.0  154.01  7184.0  161.74
#Mann=8,-1,0
  2722.9    0.12       0  4241.8    0.07       0  4805.4    0.12       0
  4995.3    0.05       0  5004.8    0.12       0  5794.5    0.05       0
  5980.2    0.12       0  6726.0    0.07       0
Bank Sta=4995.3,5004.8
Exp/Cntr=0.3,0.1

Type RM Length L Ch R = 1,7408,710,710,710
BEGIN DESCRIPTION:
Mapping XS f6973493
END DESCRIPTION:
XS GIS Cut Line= 4
      2519709.58     13495040.30      2520842.75     13494022.66
      2521463.75     13492792.60      2521963.35     13491078.71
#Sta/Elev= 30
  1767.8  154.38  1966.4  152.00  2398.5  152.73  2518.8  149.71  3022.5  146.64
  3212.7  148.98  3400.8  151.93  3615.2  147.25  3690.8  146.30  3833.0  145.03
  3969.3  141.69  4005.2  145.07  4126.4  145.23  4414.6  146.64  4764.1  145.22
  4908.3  144.05  4989.2  140.82  4995.1  137.54  4995.6  137.04  5005.0  137.54
  5020.4  138.34  5030.8  141.64  5052.7  138.27  5123.3  144.54  5403.2  145.23
  5499.6  141.28  5530.8  144.28  5626.7  144.11  6052.9  149.01  6454.0  164.49
#Mann=13,-1,0
  1767.8    0.12       0  3022.5    0.07       0  3212.7    0.12       0
  3615.2    0.07       0  3690.8    0.12       0  3833.0    0.07       0
  4126.4    0.12       0  4414.6    0.12       0  4764.1    0.12       0
  4995.1    0.05       0  5005.0    0.12       0  5123.3    0.12       0
  5626.7    0.07       0
Bank Sta=4995.1,5005
Exp/Cntr=0.3,0.1

Type RM Length L Ch R = 1,6698,732,732,732
BEGIN DESCRIPTION:
Mapping XS d3e80f47
END DESCRIPTION:
XS GIS Cut Line= 4
      2519787.69     13495092.39      2520989.96     13494350.20
      2522179.03     13492591.22      2522942.15     13491418.78
#Sta/Elev= 30
  1419.0  151.66  1532.6  149.46  1590.6  151.41  1837.7  151.60  2332.0  145.92
  2637.0  147.08  3083.8  144.72  3488.3  147.86  3668.1  145.32  3988.8  145.46
  4172.5  146.76  4386.6  146.80  4603.1  146.76  4777.7  143.13  4914.3  141.89
  4962.7  139.30  4977.8  140.65  4986.4  139.87  4995.0  136.00  4995.5  135.50
  5005.0  136.00  5029.2  141.69  5050.3  143.14  5189.2  138.50  5403.6  143.80
  5541.8  145.55  5623.3  146.84  5738.5  148.66  6025.2  153.18  6354.0  164.21
#Mann=11,-1,0
  1419.0    0.12       0  3988.8    0.07       0  4172.5   0.035       0
  4386.6    0.07       0  4777.7    0.12       0  4995.0    0.05       0
  5005.0    0.12       0  5403.6    0.07       0  5541.8    0.12       0
  5623.3    0.07       0  5738.5    0.05       0
Bank Sta=4995,5005
Exp/Cntr=0.3,0.1

Type RM Length L Ch R = 1,5966,963,963,963
BEGIN DESCRIPTION:
TRIB TO FIFTEENMILE CREEK 9.0
END DESCRIPTION:
XS GIS Cut Line= 4
      2519926.57     13495200.90      2521206.98     13494367.56
      2522775.00     13492975.00      2523975.04     13492174.97
#Sta/Elev= 30
  1379.8  150.70  1542.7  152.11  1636.3  149.72  2069.9  146.66  2264.1  149.80
  2590.2  145.61  3572.0  145.69  3706.8  145.16  4054.2  147.93  4381.1  148.44
  4400.2  147.98  4523.2  147.61  4650.8  142.48  4681.1  141.83  4962.4  137.75
  4976.6  133.05  4983.3  137.20  4990.8  137.44  4993.9  133.05  4994.4  132.55
  5006.1  133.05  5007.6  137.47  5141.1  141.74  5531.5  143.83  5651.9  144.21
  5652.8  144.34  5772.3  144.28  5922.8  145.17  6223.0  148.39  6446.9  155.71
#Mann=16,-1,0
  1379.8    0.12       0  3572.0    0.07       0  3706.8    0.05       0
  4054.2    0.07       0  4381.1    0.12       0  4400.2    0.07       0
  4650.8    0.12       0  4681.1    0.12       0  4993.9    0.05       0
  5006.1    0.12       0  5141.1    0.05       0  5531.5   0.035       0
  5651.9    0.12       0  5652.8   0.035       0  5772.3    0.12       0
  5922.8   0.045       0
Bank Sta=4993.9,5006.1
Exp/Cntr=0.3,0.1

Type RM Length L Ch R = 1,5003,764,764,764
BEGIN DESCRIPTION:
Mapping XS d08e36d8
END DESCRIPTION:
XS GIS Cut Line= 3
      2521726.69     13493967.40      2523075.67     13493608.02
      2524100.85     13492676.51
#Sta/Elev= 30
  4173.9  145.92  4231.0  145.35  4251.3  145.31  4375.5  145.15  4510.9  145.36
  4648.2  147.53  4813.8  139.03  4923.7  136.51  4968.9  137.41  4982.0  136.30
  4989.7  131.10  4993.8  130.77  4994.3  130.27  5006.2  130.77  5010.4  135.15
  5017.0  135.68  5041.4  133.40  5103.5  137.79  5173.9  140.13  5177.5  139.23
  5196.7  140.99  5227.7  139.69  5390.4  141.23  5578.8  145.74  5869.2  147.80
  6045.8  145.32  6328.9  147.75  6414.0  145.62  6838.9  147.35  6955.1  150.38
#Mann=12,-1,0
  4173.9    0.05       0  4231.0    0.07       0  4251.3    0.05       0
  4375.5   0.035       0  4923.7    0.12       0  4968.9   0.035       0
  4993.8   0.035       0  5006.2   0.035       0  5173.9    0.07       0
  5390.4    0.12       0  5869.2    0.05       0  6838.9   0.045       0
Bank Sta=4993.8,5006.2
Exp/Cntr=0.3,0.1

Type RM Length L Ch R = 1,4239,1328,1328,1328
BEGIN DESCRIPTION:
Mapping XS 58801156
END DESCRIPTION:
XS GIS Cut Line= 3
      2521695.46     13494394.47      2522653.79     13494160.10
      2524293.36     13492739.14
#Sta/Elev= 30
  3689.8  145.31  3877.8  144.94  3990.5  145.68  4296.2  145.29  4378.0  144.47
  4430.5  141.84  4500.0  142.48  4533.5  141.41  4591.4  135.07  4615.8  134.27
  4716.7  134.11  4801.1  136.06  4837.9  136.75  4964.6  134.23  4993.7  129.71
  4994.2  129.21  5006.4  129.71  5013.9  134.00  5064.2  142.82  5099.4  146.77
  5191.6  146.14  5432.2  149.91  5531.5  148.04  5687.3  148.29  5713.9  146.83
  5836.4  145.51  6020.6  147.11  6318.9  145.51  6786.1  150.76  6846.0  153.14
#Mann=11,-1,0
  3689.8    0.12       0  3877.8    0.07       0  3990.5    0.12       0
  4296.2    0.07       0  4500.0    0.12       0  4801.1    0.12       0
  4837.9    0.12       0  4993.7    0.05       0  5006.4    0.12       0
  5064.2    0.12       0  5713.9    0.05       0
Bank Sta=4993.7,5006.4
Exp/Cntr=0.3,0.1

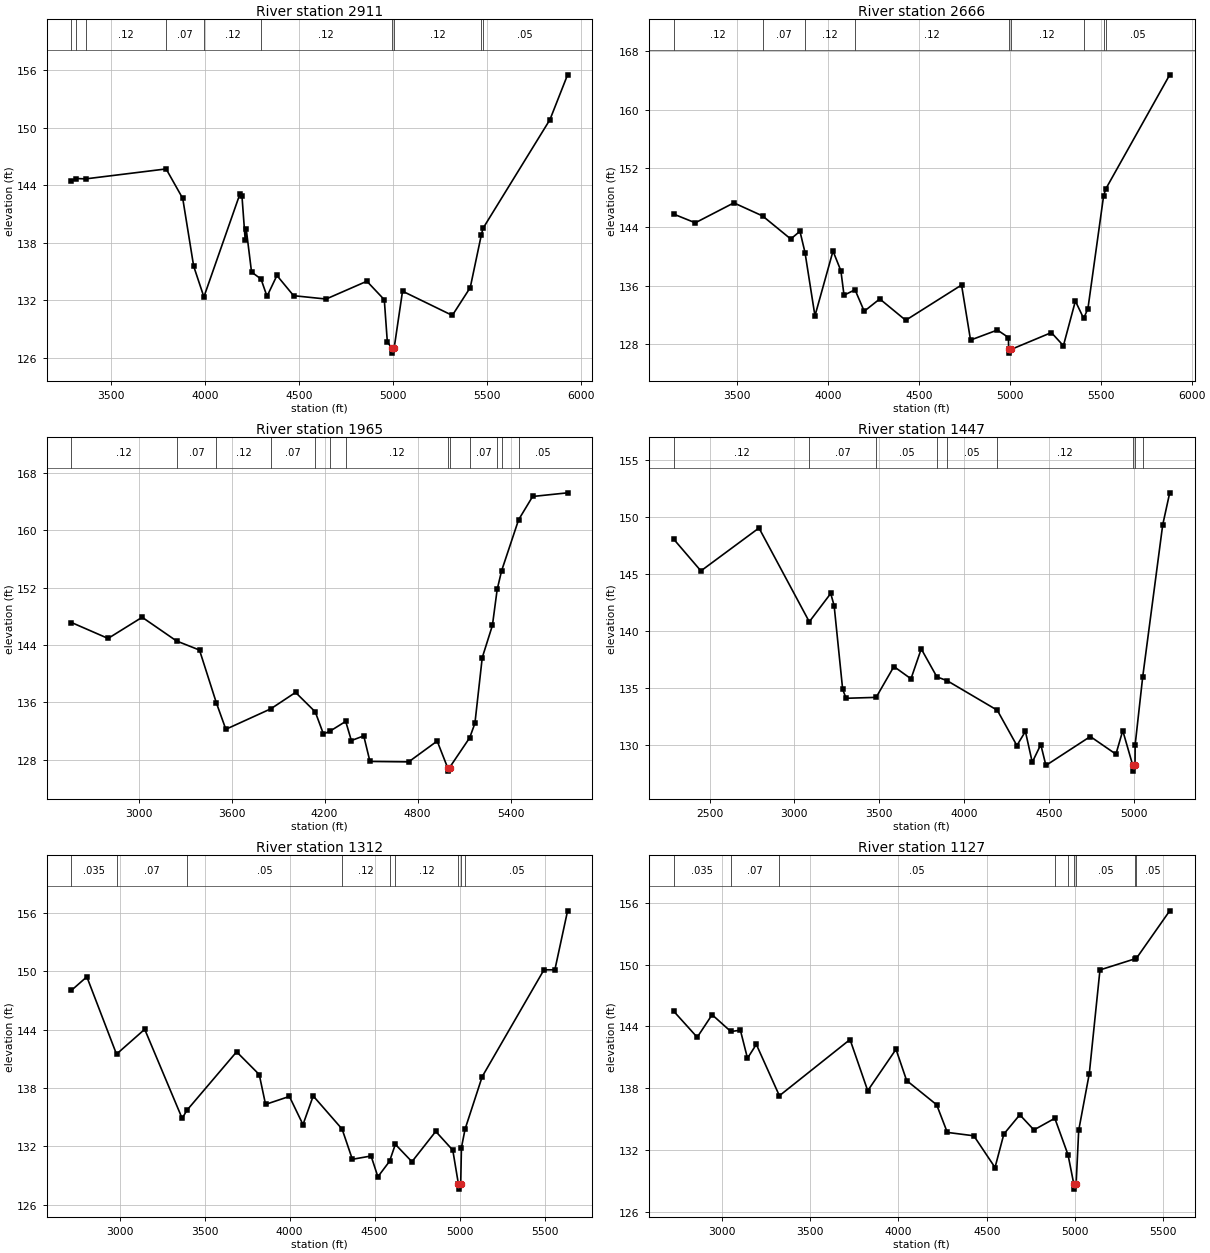
Type RM Length L Ch R = 1,2911,245,245,245
BEGIN DESCRIPTION:
Mapping XS 9781e59c
END DESCRIPTION:
XS GIS Cut Line= 3
      2521882.98     13494509.05      2523398.58     13494227.81
      2524356.88     13493691.37
#Sta/Elev= 30
  3289.8  144.45  3315.9  144.71  3364.7  144.67  3793.4  145.71  3881.8  142.63
  3940.0  135.55  3994.4  132.34  4186.9  143.14  4197.0  142.87  4214.3  138.25
  4219.4  139.47  4247.9  134.94  4298.4  134.21  4330.2  132.40  4383.0  134.58
  4471.7  132.47  4644.6  132.12  4861.5  133.98  4954.3  132.05  4970.3  127.67
  4993.6  126.97  4994.1  126.47  5006.5  126.97  5051.3  132.94  5316.2  130.41
  5411.6  133.32  5470.8  138.84  5479.7  139.51  5835.7  150.86  5929.5  155.54
#Mann=10,-1,0
  3289.8    0.12       0  3315.9    0.07       0  3364.7    0.12       0
  3793.4    0.07       0  3994.4    0.12       0  4298.4    0.12       0
  4993.6    0.05       0  5006.5    0.12       0  5470.8    0.12       0
  5479.7    0.05       0
Bank Sta=4993.6,5006.5
Exp/Cntr=0.3,0.1

Type RM Length L Ch R = 1,2666,701,701,701
BEGIN DESCRIPTION:
Mapping XS f81f06d4
END DESCRIPTION:
XS GIS Cut Line= 3
      2521856.93     13494597.60      2523674.62     13494342.39
      2524487.11     13493972.61
#Sta/Elev= 30
  3151.1  145.76  3270.3  144.57  3482.4  147.29  3640.2  145.51  3795.4  142.36
  3845.9  143.42  3873.7  140.52  3928.4  131.88  4027.7  140.72  4071.0  138.03
  4088.3  134.70  4148.8  135.44  4199.4  132.51  4284.9  134.19  4427.5  131.28
  4734.6  136.09  4784.0  128.58  4931.7  129.95  4992.5  128.93  4993.5  127.30
  4994.0  126.80  5006.5  127.30  5228.5  129.60  5294.7  127.81  5360.6  133.90
  5406.0  131.54  5429.5  132.86  5515.4  148.18  5527.0  149.16  5879.3  164.75
#Mann=9,-1,0
  3151.1    0.12       0  3640.2    0.07       0  3873.7    0.12       0
  4148.8    0.12       0  4993.5    0.05       0  5006.5    0.12       0
  5406.0    0.05       0  5515.4    0.07       0  5527.0    0.05       0
Bank Sta=4993.5,5006.5
Exp/Cntr=0.3,0.1

Type RM Length L Ch R = 1,1965,518,518,518
BEGIN DESCRIPTION:
Mapping XS b21d0382
END DESCRIPTION:
XS GIS Cut Line= 3
      2521778.78     13494733.02      2524034.00     13494753.85
      2524945.43     13494498.65
#Sta/Elev= 30
  2566.3  147.14  2802.5  144.92  3022.5  147.87  3244.2  144.57  3392.6  143.30
  3501.6  135.93  3562.6  132.26  3852.6  135.11  4012.6  137.40  4139.5  134.69
  4192.6  131.59  4237.8  132.04  4336.1  133.36  4372.6  130.69  4452.6  131.34
  4492.6  127.78  4742.6  127.72  4926.5  130.62  4993.5  126.93  4994.0  126.43
  5006.6  126.93  5136.5  131.09  5170.1  133.10  5217.3  142.24  5282.9  146.73
  5313.7  151.74  5342.3  154.35  5452.0  161.46  5542.5  164.70  5768.1  165.21
#Mann=13,-1,0
  2566.3    0.12       0  3244.2    0.07       0  3501.6    0.12       0
  3852.6    0.07       0  4139.5    0.05       0  4237.8    0.07       0
  4336.1    0.12       0  4993.5    0.05       0  5006.6    0.12       0
  5136.5    0.07       0  5313.7    0.12       0  5342.3    0.07       0
  5452.0    0.05       0
Bank Sta=4993.5,5006.6
Exp/Cntr=0.3,0.1

Type RM Length L Ch R = 1,1447,135,135,135
BEGIN DESCRIPTION:
TRIB TO FIFTEENMILE CREEK 3.0
END DESCRIPTION:
XS GIS Cut Line= 3
      2521775.05     13494825.01      2524475.00     13495125.00
      2524674.98     13495075.01
#Sta/Elev= 30
  2288.3  148.07  2449.2  145.27  2791.3  149.04  3087.7  140.80  3213.9  143.29
  3234.0  142.22  3284.3  134.86  3304.5  134.08  3481.5  134.16  3586.2  136.87
  3686.8  135.79  3747.2  138.42  3839.3  135.96  3899.2  135.63  4195.2  133.03
  4310.6  129.93  4360.9  131.17  4401.2  128.46  4451.5  130.01  4481.7  128.18
  4743.3  130.72  4894.2  129.17  4934.4  131.24  4993.5  128.18  4994.0  127.68
  5006.6  128.18  5007.4  129.99  5052.1  135.98  5169.8  149.32  5211.0  152.13
#Mann=9,-1,0
  2288.3    0.12       0  3087.7    0.07       0  3481.5    0.05       0
  3839.3    0.07       0  3899.2    0.05       0  4195.2    0.12       0
  4993.5    0.05       0  5006.6    0.12       0  5052.1    0.12       0
Bank Sta=4993.5,5006.6
Exp/Cntr=0.3,0.1

Type RM Length L Ch R = 1,1312,185,185,185
BEGIN DESCRIPTION:
Mapping XS f819001c
END DESCRIPTION:
XS GIS Cut Line= 3
      2522194.74     13495144.82      2524481.19     13495259.40
      2525080.04     13495066.73
#Sta/Elev= 30
  2716.9  148.06  2807.3  149.45  2981.8  141.49  3147.7  144.05  3368.0  134.88
  3395.8  135.71  3688.4  141.73  3821.5  139.39  3858.6  136.32  3998.8  137.14
  4078.9  134.24  4138.9  137.19  4308.9  133.78  4369.2  130.67  4479.4  131.01
  4519.4  128.87  4587.9  130.46  4622.1  132.21  4719.7  130.42  4859.8  133.54
  4960.0  131.61  4993.4  128.10  4993.9  127.60  5006.6  128.10  5010.9  131.87
  5032.4  133.78  5132.9  139.17  5496.4  150.17  5560.5  150.17  5635.3  156.24
#Mann=9,-1,0
  2716.9   0.035       0  2981.8    0.07       0  3395.8    0.05       0
  4308.9    0.12       0  4587.9    0.05       0  4622.1    0.12       0
  4993.4    0.05       0  5006.6    0.12       0  5032.4    0.05       0
Bank Sta=4993.4,5006.6
Exp/Cntr=0.3,0.1

Type RM Length L Ch R = 1,1127,474,474,474
BEGIN DESCRIPTION:
Mapping XS b55dfa34
END DESCRIPTION:
XS GIS Cut Line= 4
      2522257.23     13495332.32      2524439.53     13495457.32
      2524585.36     13495405.23      2525001.03     13495187.01
#Sta/Elev= 30
  2726.5  145.48  2860.2  142.94  2944.6  145.13  3050.6  143.50  3104.9  143.62
  3145.0  140.90  3195.0  142.25  3325.7  137.26  3725.9  142.72  3826.1  137.75
  3986.3  141.77  4046.4  138.74  4216.7  136.38  4276.8  133.70  4427.1  133.37
  4547.2  130.29  4597.3  133.54  4687.5  135.41  4767.6  133.94  4885.9  135.07
  4960.8  131.52  4993.4  128.69  4993.9  128.19  5006.6  128.69  5021.2  133.90
  5081.1  139.40  5141.6  149.48  5342.2  150.57  5347.4  150.59  5536.7  155.22
#Mann=9,-1,0
  2726.5   0.035       0  3050.6    0.07       0  3325.7    0.05       0
  4885.9    0.12       0  4960.8    0.05       0  4993.4    0.05       0
  5006.6    0.05       0  5342.2    0.12       0  5347.4    0.05       0
Bank Sta=4993.4,5006.6
Exp/Cntr=0.3,0.1

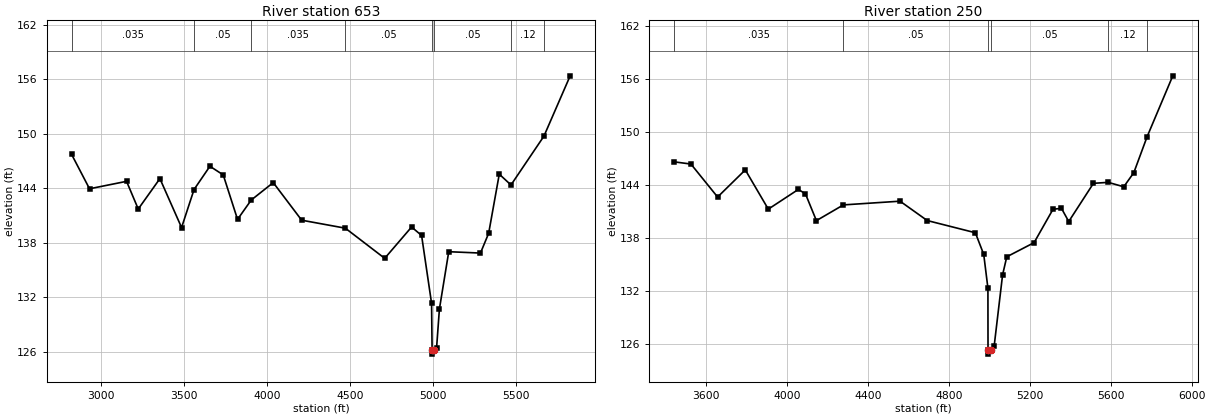
Type RM Length L Ch R = 1,653,403,403,403
BEGIN DESCRIPTION:
Mapping XS f338428a
END DESCRIPTION:
XS GIS Cut Line= 4
      2522205.19     13495681.28      2524314.53     13495847.94
      2524444.74     13495837.52      2524990.78     13495317.48
#Sta/Elev= 30
  2823.8  147.73  2931.7  143.94  3154.6  144.76  3224.9  141.71  3355.3  145.06
  3485.7  139.67  3560.8  143.86  3656.2  146.42  3736.4  145.47  3822.5  140.57
  3904.9  142.70  4037.4  144.62  4208.5  140.48  4471.4  139.60  4708.2  136.28
  4870.0  139.73  4930.2  138.80  4990.3  131.32  4993.4  126.23  4993.9  125.73
  5006.7  126.23  5020.4  126.41  5037.4  130.69  5093.6  137.01  5284.5  136.86
  5333.9  139.04  5397.7  145.55  5468.2  144.36  5666.6  149.74  5824.4  156.38
#Mann=8,-1,0
  2823.8   0.035       0  3560.8    0.05       0  3904.9   0.035       0
  4471.4    0.05       0  4993.4    0.05       0  5006.7    0.05       0
  5468.2    0.12       0  5666.6    0.05       0
Bank Sta=4993.4,5006.7
Exp/Cntr=0.3,0.1

Type RM Length L Ch R = 1,250,0,0,0
BEGIN DESCRIPTION:
TRIB TO FIFTEENMILE CREEK 1.0
END DESCRIPTION:
XS GIS Cut Line= 4
      2522925.04     13495925.01      2524262.44     13496275.02
      2524554.11     13496196.90      2525025.03     13495574.97
#Sta/Elev= 30
  3442.2  146.65  3524.9  146.40  3656.7  142.67  3793.6  145.74  3907.3  141.30
  4055.8  143.53  4091.0  143.03  4145.1  140.00  4278.5  141.78  4558.5  142.20
  4692.9  140.01  4930.8  138.63  4972.2  136.18  4992.9  132.36  4993.4  125.40
  4993.9  124.90  5006.7  125.40  5024.0  125.86  5065.4  133.87  5086.1  135.91
  5221.1  137.51  5314.7  141.29  5356.4  141.39  5392.4  139.90  5514.5  144.22
  5587.4  144.33  5664.3  143.83  5714.2  145.43  5779.2  149.46  5906.7  156.38
#Mann=6,-1,0
  3442.2   0.035       0  4278.5    0.05       0  4993.4    0.05       0
  5006.7    0.05       0  5587.4    0.12       0  5779.2    0.05       0
Bank Sta=4993.4,5006.7
Exp/Cntr=0.3,0.1

Chan Stop Cuts=-1