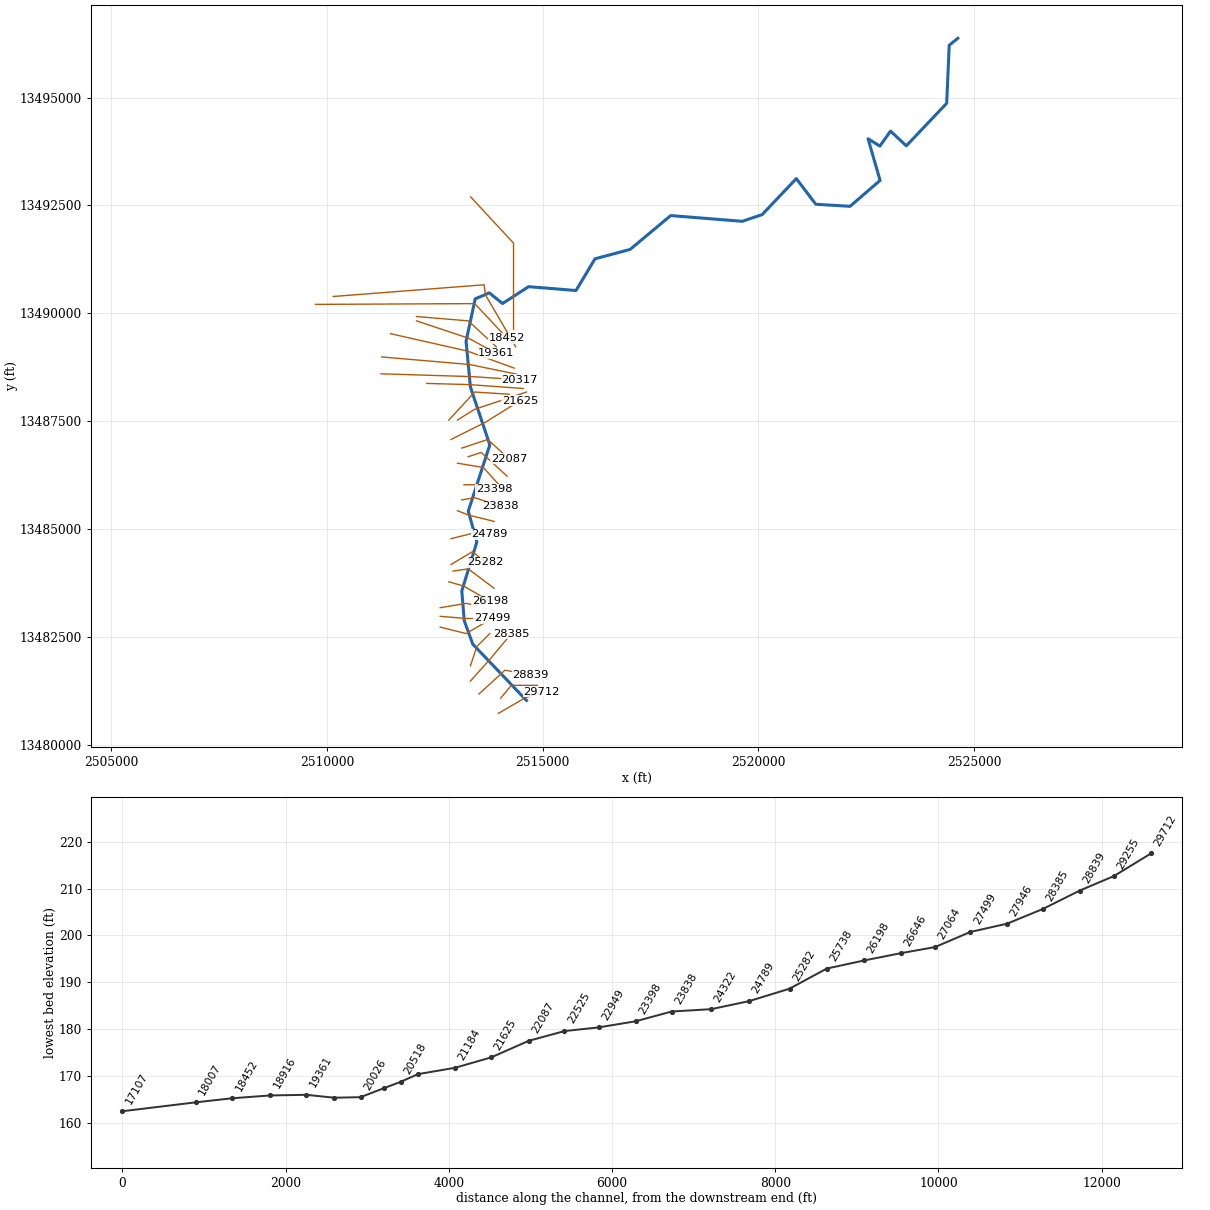
--- TRIB TO FIFTEENMILE CREEK.prj (project) ---

Proj Title=TRIB TO FIFTEENMILE CREEK Base Level Engineering
Current Plan=p01
Default Exp/Contr=0.3,0.1
English Units
Geom File=g01
Flow File=f01
Plan File=p01
Y Axis Title=Elevation
X Axis Title(PF)=Main Channel Distance
X Axis Title(XS)=Station
BEGIN DESCRIPTION:
TRIB TO FIFTEENMILE CREEK
END DESCRIPTION:
DSS Export Rating Curves= 0
DSS Export Rating Curve Sorted= 0
DSS Export Volume Flow Curves= 0
DXF OffsetX= 0
DXF OffsetY= 0
DXF ScaleX= 1
DXF ScaleY= 10

--- TRIB TO FIFTEENMILE CREEK.p01 (plan) ---

Plan Title=Multiple Run
Short Identifier=Multiple
Geom File=g01
Flow File=f01
Subcritical Flow
K Sum by GR= 0
Std Step Tol= 0.01
Critical Tol= 0.01
Num of Std Step Trials= 20
Max Error Tol= 0.3
Flow Tol Ratio= 0.001
Split Flow NTrial= 30
Split Flow Tol= 0.02
Split Flow Ratio= 0.02
Log Output Level= 0
Friction Slope Method= 1
Unsteady Friction Slope Method= 2
Unsteady Bridges Friction Slope Method= 1
Parabolic Critical Depth
Global Vel Dist=  1 , 1 , 1
Global Log Level= 0
CheckData=True
Encroach Param= -1, 0, 0, 0
BEGIN DESCRIPTION:
Multiple Run
END DESCRIPTION:

--- TRIB TO FIFTEENMILE CREEK.f01 (steady flow) ---

Flow Title=Multiple
Number of Profiles=7
Profile Names=10-year,25-year,50-year,1pct_min,100-year,1pct_plu,500-year
River Rch & RM= TRIB TO FIFTEENM,Reach-1,29712
     433     672     880     558    1113    2221    1762
River Rch & RM= TRIB TO FIFTEENM,Reach-1,24789
     742    1188    1588    1027    2048    4087    3369
River Rch & RM= TRIB TO FIFTEENM,Reach-1,19361
     761    1217    1624    1047    2090    4169    3423
River Rch & RM= TRIB TO FIFTEENM,Reach-1,15331
    1145    1874    2538    1660    3312    6608    5580
River Rch & RM= TRIB TO FIFTEENM,Reach-1,14872
    1282    2105    2861    1875    3741    7464    6333
River Rch & RM= TRIB TO FIFTEENM,Reach-1,9943
    1524    2525    3448    2271    4531    9040    7745
River Rch & RM= TRIB TO FIFTEENM,Reach-1,6698
    1698    2826    3874    2559    5106   10188    8783
River Rch & RM= TRIB TO FIFTEENM,Reach-1,5966
    1898    3178    4372    2898    5783   11538   10017
River Rch & RM= TRIB TO FIFTEENM,Reach-1,5003
    1964    3288    4523    2997    5980   11933   10355
River Rch & RM= TRIB TO FIFTEENM,Reach-1,1965
    1973    3301    4540    3007    6000   11972   10378
Boundary for River Rch & Prof#=TRIB TO FIFTEENM,Reach-1,1
Up Type=0
Dn Type=3
Dn Slope=0.005
Boundary for River Rch & Prof#=TRIB TO FIFTEENM,Reach-1,2
Up Type=0
Dn Type=3
Dn Slope=0.005
Boundary for River Rch & Prof#=TRIB TO FIFTEENM,Reach-1,3
Up Type=0
Dn Type=3
Dn Slope=0.005
Boundary for River Rch & Prof#=TRIB TO FIFTEENM,Reach-1,4
Up Type=0
Dn Type=3
Dn Slope=0.005
Boundary for River Rch & Prof#=TRIB TO FIFTEENM,Reach-1,5
Up Type=0
Dn Type=3
Dn Slope=0.005
Boundary for River Rch & Prof#=TRIB TO FIFTEENM,Reach-1,6
Up Type=0
Dn Type=3
Dn Slope=0.005
Boundary for River Rch & Prof#=TRIB TO FIFTEENM,Reach-1,7
Up Type=0
Dn Type=3
Dn Slope=0.005

--- TRIB TO FIFTEENMILE CREEK.g01 (geometry) ---

Geom Title=Existing Conditions
Program Version=4.10

River Reach=TRIB TO FIFTEENM,Reach-1
Reach XY= 30
        2514625.       13481025.      2513380.19     13482330.44
      2513182.12       13482875.       2513126.2     13483564.49
      2513475.29     13484699.88      2513275.87     13485414.67
      2513775.53     13486949.87      2513325.38     13488290.16
      2513224.59       13489350.      2513436.24     13490335.05
      2513764.69     13490474.45      2514069.11     13490226.97
       2514674.9     13490617.68      2515773.53     13490528.55
      2516215.19     13491264.57      2517027.45     13491480.46
      2517968.05     13492265.82      2519628.29      13492133.1
       2520088.4     13492288.53      2520880.93     13493122.77
      2521333.01     13492528.03      2522127.45     13492480.46
      2522822.76     13493080.93       2522544.6     13494046.15
      2522818.95     13493876.58      2523064.45     13494223.92
       2523431.7     13493883.95      2524366.86     13494868.94
      2524426.04     13496214.57        2524625.       13496375.

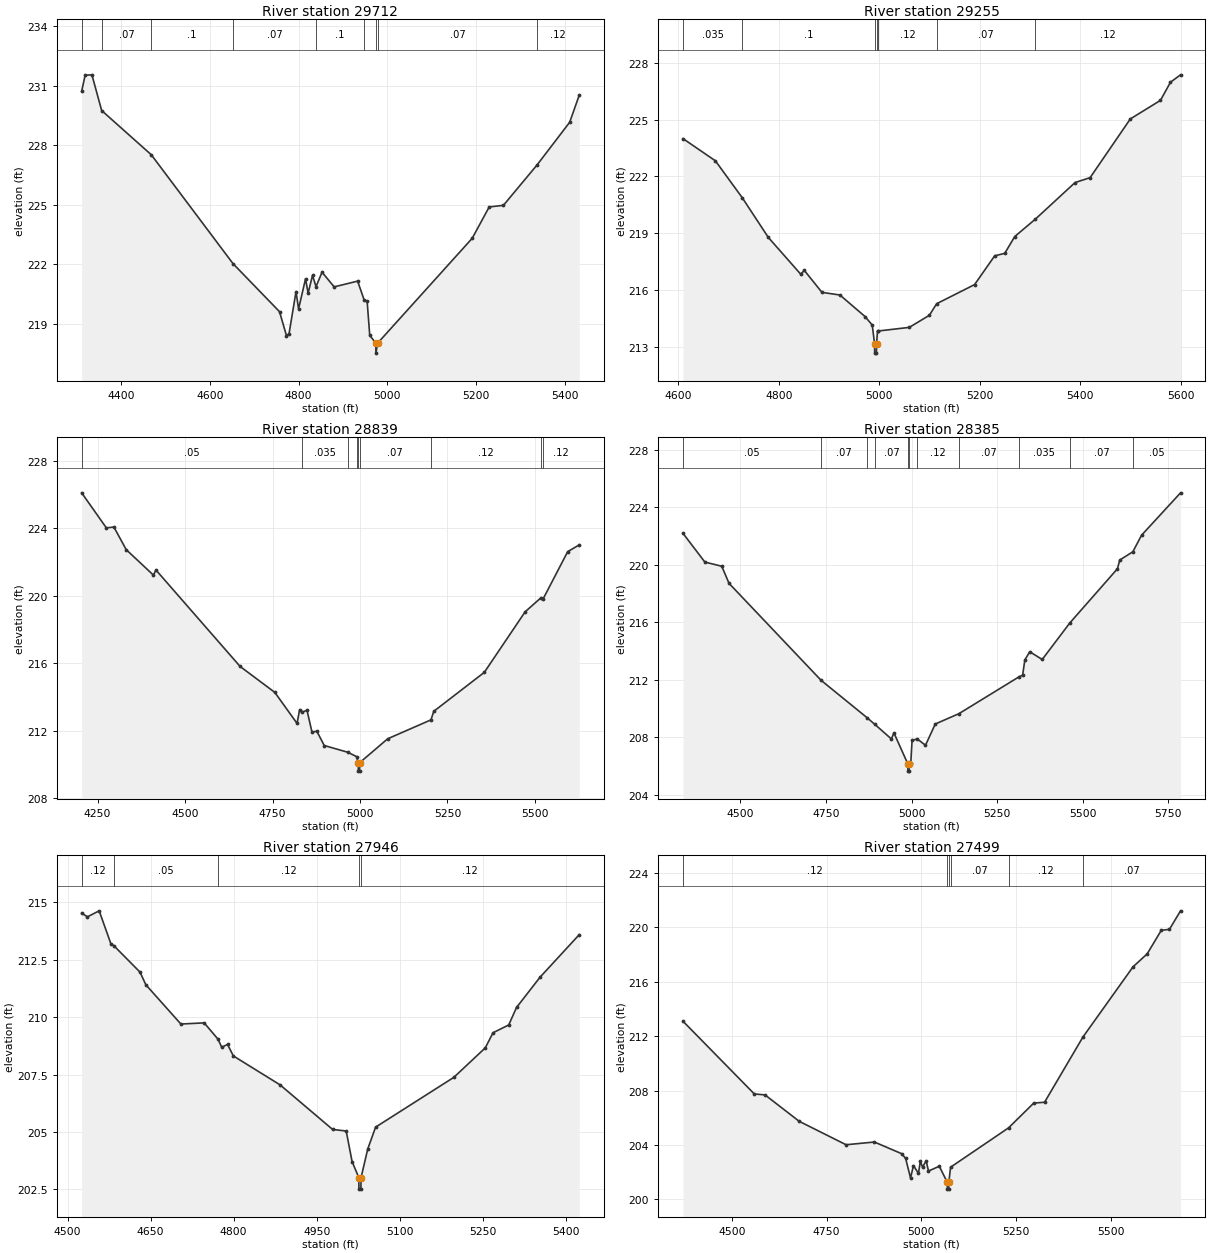
Type RM Length L Ch R = 1 ,29712   ,457,457,457
BEGIN DESCRIPTION:
TRIB TO FIFTEENMILE CREEK 59.0
END DESCRIPTION:
XS GIS Cut Line= 3
      2513975.04     13480725.02        2514575.       13481075.
      2514975.02     13481225.01
#Sta/Elev= 30
  4311.1  230.73  4318.9  231.54  4334.2  231.56  4356.2  229.76  4468.1  227.53
  4652.4  222.04  4757.2  219.62  4772.9  218.41  4778.7  218.51  4794.4  220.63
  4800.2  219.76  4815.9  221.28  4821.7  220.55  4831.6  221.45  4839.5  220.88
  4853.1  221.61  4880.4  220.87  4933.3  221.16  4947.9  220.22  4954.8  220.14
  4960.6  218.43  4974.3  218.03  4974.6  217.53  4978.3  218.03  5191.7  223.32
    5230   224.9    5262  224.98    5338  227.02  5411.5  229.17  5432.9  230.53
#Mann= 9 ,-1 , 0
  4311.1    .035       0  4356.2     .07       0  4468.1      .1       0
  4652.4     .07       0  4839.5      .1       0  4947.9     .07       0
  4974.3     .05       0  4978.3     .07       0    5338     .12       0
Bank Sta=4974.3,4978.3
XS Rating Curve= 0 ,0
Exp/Cntr=0.3,0.1

Type RM Length L Ch R = 1 ,29255   ,416,416,416
BEGIN DESCRIPTION:
TRIB TO FIFTEENMILE CREEK 58.0
END DESCRIPTION:
XS GIS Cut Line= 3
        2514025.     13481075.01        2514275.       13481375.
      2514874.99       13481375.
#Sta/Elev= 30
  4609.2     224  4673.6  222.83  4727.1  220.88  4779.1  218.78  4843.5  216.84
  4850.7  217.04  4885.8  215.88  4921.6  215.74  4971.7   214.6    4986  214.15
  4990.5  213.17  4990.8  212.67  4994.3  212.67  4994.5  213.17  4996.5  213.84
  4998.3  213.84  5059.7  214.03  5099.7  214.67  5114.2  215.28  5189.7  216.29
  5229.7  217.81  5249.7  217.94  5269.7  218.83  5310.8  219.75  5389.7  221.68
  5419.7  221.94  5499.7  225.04  5559.7  226.02  5579.7  226.98  5599.7  227.37
#Mann= 7 ,-1 , 0
  4609.2    .035       0  4727.1      .1       0  4990.5     .05       0
  4994.5      .1       0  4998.3     .12       0  5114.2     .07       0
  5310.8     .12       0
Bank Sta=4990.5,4994.5
XS Rating Curve= 0 ,0
Exp/Cntr=0.3,0.1

Type RM Length L Ch R = 1 ,28839   ,454,454,454
BEGIN DESCRIPTION:
TRIB TO FIFTEENMILE CREEK 57.0
END DESCRIPTION:
XS GIS Cut Line= 3
        2513525.       13481175.        2514125.       13481725.
      2514724.98       13481625.
#Sta/Elev= 30
  4204.4  226.11    4275  224.03  4296.6  224.08  4331.7  222.74  4409.4  221.23
  4416.8  221.53  4657.3  215.81  4756.6  214.27  4820.1  212.43  4827.5  213.25
  4835.1   213.1  4848.5  213.21  4862.6  211.93  4876.8  211.96  4897.8  211.12
  4965.1  210.72  4990.2  210.46  4995.1   210.1  4995.3   209.6  4998.8   209.6
  4999.1   210.1  5079.2  211.52  5202.8  212.64    5211  213.15  5355.4  215.46
    5472  219.05    5517  219.88  5523.3  219.81  5593.7  222.62  5626.6  223.02
#Mann= 9 ,-1 , 0
  4204.4     .05       0  4835.1    .035       0  4965.1     .12       0
  4990.2     .07       0  4995.1     .05       0  4999.1     .07       0
  5202.8     .12       0    5517     .07       0  5523.3     .12       0
Bank Sta=4995.1,4999.1
XS Rating Curve= 0 ,0
Exp/Cntr=0.3,0.1

Type RM Length L Ch R = 1 ,28385   ,439,439,439
BEGIN DESCRIPTION:
TRIB TO FIFTEENMILE CREEK 56.0
END DESCRIPTION:
XS GIS Cut Line= 3
        2513325.       13481475.        2513775.       13481975.
      2514274.99     13482574.99
#Sta/Elev= 30
  4332.3   222.2  4396.2   220.2  4445.5  219.91  4466.8  218.72  4735.8  211.97
  4869.5  209.38    4893   208.9  4941.1  207.89  4948.6  208.31  4989.2  206.15
  4989.4  205.65  4992.9  205.65  4993.2  206.15  4997.9  206.24  5001.6  207.79
  5016.8  207.89  5040.8  207.45  5069.4  208.93  5138.5  209.65  5313.8  212.21
  5324.6  212.33  5331.1  213.39  5345.4  213.96  5381.8  213.42  5462.4  215.96
  5601.8  219.74  5608.3  220.34  5646.7  220.92  5672.1  222.07    5786  225.02
#Mann= 11 ,-1 , 0
  4332.3     .05       0  4735.8     .07       0  4869.5     .05       0
    4893     .07       0  4989.2     .05       0  4993.2     .07       0
  5016.8     .12       0  5138.5     .07       0  5313.8    .035       0
  5462.4     .07       0  5646.7     .05       0
Bank Sta=4989.2,4993.2
XS Rating Curve= 0 ,0
Exp/Cntr=0.3,0.1

Type RM Length L Ch R = 1 ,27946   ,447,447,447
BEGIN DESCRIPTION:
TRIB TO FIFTEENMILE CREEK 55.0
END DESCRIPTION:
XS GIS Cut Line= 3
      2513325.01     13481825.04        2513475.       13482275.
      2513775.02     13482575.02
#Sta/Elev= 30
  4525.5  214.53    4536  214.37  4557.1  214.63  4578.2   213.2  4583.7  213.11
  4630.9  211.96  4641.4  211.41  4704.7   209.7  4746.8  209.75  4771.8  209.04
  4778.4  208.69    4789  208.81  4799.5  208.31  4883.9  207.05  4978.7  205.11
  5003.3  205.04  5013.9  203.71  5026.1  203.01  5026.3  202.51  5029.8  202.51
  5030.1  203.01  5042.2  204.26  5056.4  205.21  5197.8  207.38  5254.4  208.66
  5268.5  209.32  5296.8  209.66  5310.9  210.42  5353.4  211.74  5424.1  213.59
#Mann= 5 ,-1 , 0
  4525.5     .12       0  4583.7     .05       0  4771.8     .12       0
  5026.1     .05       0  5030.1     .12       0
Bank Sta=5026.1,5030.1
XS Rating Curve= 0 ,0
Exp/Cntr=0.3,0.1

Type RM Length L Ch R = 1 ,27499   ,435,435,435
BEGIN DESCRIPTION:
TRIB TO FIFTEENMILE CREEK 54.0
END DESCRIPTION:
XS GIS Cut Line= 3
      2512624.96     13482725.01        2513225.       13482575.
      2513824.98     13482924.99
#Sta/Elev= 30
  4371.1  213.09  4559.3  207.75  4587.6  207.68  4677.8  205.74  4801.5  204.02
  4876.2  204.22  4948.4  203.36  4958.7  203.01  4971.6  201.58  4979.3  202.49
  4992.5  201.92  4997.5   202.8  5003.2  202.38  5012.8  202.84    5019  202.09
  5047.5  202.44  5068.6  201.26  5068.9  200.76  5072.4  200.76  5072.6  201.26
  5077.3  202.37  5230.3  205.26  5296.8  207.08  5325.3  207.14  5426.8  211.94
  5558.9  217.09  5596.2  218.04  5633.4  219.77  5654.9  219.84  5684.2   221.2
#Mann= 6 ,-1 , 0
  4371.1     .12       0  5068.6     .05       0  5072.6     .12       0
  5077.3     .07       0  5230.3     .12       0  5426.8     .07       0
Bank Sta=5068.6,5072.6
XS Rating Curve= 0 ,0
Exp/Cntr=0.3,0.1

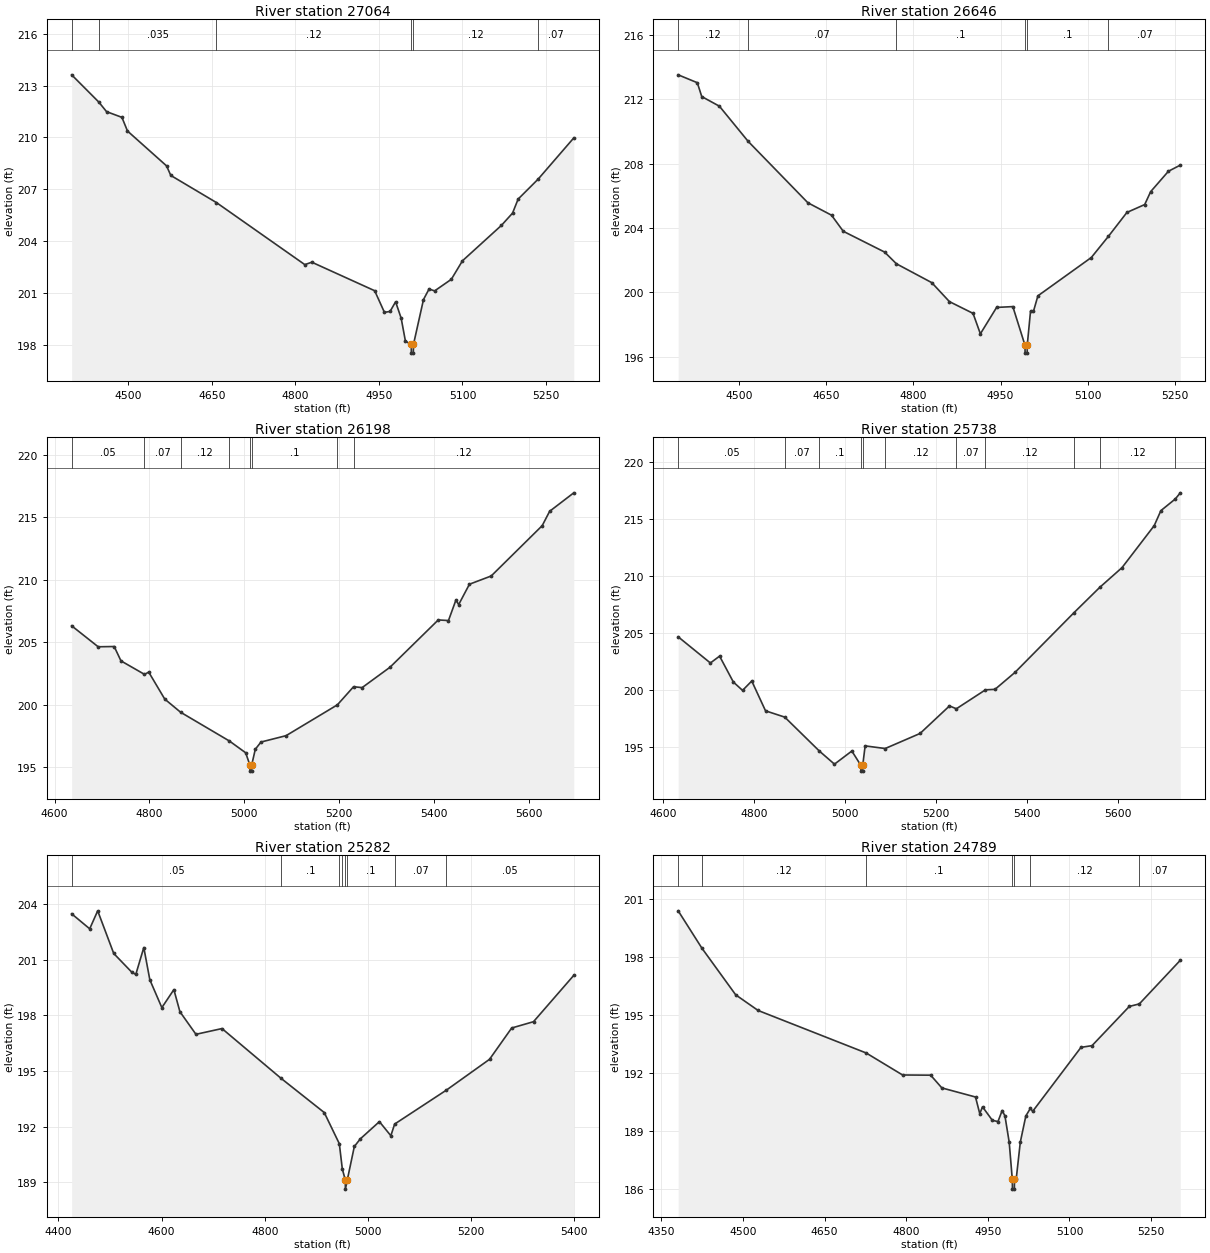
Type RM Length L Ch R = 1 ,27064   ,418,418,418
BEGIN DESCRIPTION:
TRIB TO FIFTEENMILE CREEK 53.0
END DESCRIPTION:
XS GIS Cut Line= 3
        2512625.       13482975.        2513225.       13482925.
      2513525.02       13482925.
#Sta/Elev= 30
  4397.9  213.62  4446.5  212.05  4460.6  211.49  4488.2  211.16  4498.2  210.37
  4568.5  208.35    4576   207.8    4658  206.23  4816.8  202.64  4829.4  202.78
  4942.3  201.13  4959.8  199.88  4969.9  199.93  4979.9  200.49  4989.9  199.54
  4997.5  198.22    5008  198.02  5008.2  197.52  5011.7  197.52    5012  198.02
    5030  200.62    5040  201.23    5050  201.12    5080  201.79    5100  202.86
    5170  204.91    5190  205.62    5200  206.43  5236.1  207.59    5300  209.97
#Mann= 6 ,-1 , 0
  4397.9     .12       0  4446.5    .035       0    4658     .12       0
    5008     .05       0    5012     .12       0  5236.1     .07       0
Bank Sta=5008,5012
XS Rating Curve= 0 ,0
Exp/Cntr=0.3,0.1

Type RM Length L Ch R = 1 ,26646   ,448,448,448
BEGIN DESCRIPTION:
TRIB TO FIFTEENMILE CREEK 52.0
END DESCRIPTION:
XS GIS Cut Line= 3
      2512625.03     13483175.01        2513225.       13483275.
      2513475.01       13483225.
#Sta/Elev= 30
  4395.7  213.51  4428.6  213.02  4436.2  212.16  4466.6  211.56  4515.9  209.38
  4618.7  205.56  4659.3  204.79  4679.5  203.79  4750.5   202.5  4770.9  201.77
  4831.6   200.6    4862  199.42  4902.6  198.69  4915.2  197.42  4943.1  199.06
    4971  199.11  4991.8  196.72  4992.1  196.22  4995.6  196.22  4995.8  196.72
  5001.4  198.82  5006.5  198.82  5014.1  199.78  5105.9  202.16  5135.2  203.47
  5167.1  204.96  5197.7  205.45  5207.9  206.25  5238.5  207.52  5258.9   207.9
#Mann= 6 ,-1 , 0
  4395.7     .12       0  4515.9     .07       0  4770.9      .1       0
  4991.8     .05       0  4995.8      .1       0  5135.2     .07       0
Bank Sta=4991.8,4995.8
XS Rating Curve= 0 ,0
Exp/Cntr=0.3,0.1

Type RM Length L Ch R = 1 ,26198   ,460,460,460
BEGIN DESCRIPTION:
TRIB TO FIFTEENMILE CREEK 51.0
END DESCRIPTION:
XS GIS Cut Line= 3
      2512824.97     13483775.01        2513175.       13483675.
      2513775.03     13483324.98
#Sta/Elev= 30
    4636  206.31  4691.9  204.63  4725.7  204.65    4740   203.5  4789.6  202.42
  4798.5   202.6  4832.3  200.44  4865.6  199.39  4968.7  197.08  5002.9  196.14
  5011.7  195.17  5011.9  194.67  5015.4  194.67  5015.7  195.17  5023.2  196.42
  5035.2     197  5088.1  197.51  5196.3  199.98  5230.4  201.43  5248.5  201.36
  5307.2  202.99    5409  206.78  5430.5  206.73  5446.2  208.37    5452  208.01
  5474.7  209.64  5520.6   210.3  5628.1  214.33  5643.8  215.48  5694.7  216.96
#Mann= 8 ,-1 , 0
    4636     .05       0  4789.6     .07       0  4865.6     .12       0
  4968.7      .1       0  5011.7     .05       0  5015.7      .1       0
  5196.3      .1       0  5230.4     .12       0
Bank Sta=5011.7,5015.7
XS Rating Curve= 0 ,0
Exp/Cntr=0.3,0.1

Type RM Length L Ch R = 1 ,25738   ,456,456,456
BEGIN DESCRIPTION:
TRIB TO FIFTEENMILE CREEK 50.0
END DESCRIPTION:
XS GIS Cut Line= 3
      2512924.96     13484024.99        2513275.       13484075.
        2513875.       13483625.
#Sta/Elev= 30
  4633.8  204.69  4704.6   202.4  4724.8     203  4755.1  200.73  4775.3     200
  4795.5  200.82  4825.8  198.21    4868  197.66  4944.3  194.68  4977.3  193.54
  5015.5  194.69  5035.4  193.43  5035.6  192.93  5039.1  192.93  5039.4  193.43
  5044.7  195.14  5088.8  194.91  5165.5  196.23  5230.1  198.64  5245.2  198.39
  5309.2  200.05  5330.1  200.09  5373.9  201.57  5504.1  206.82  5560.3  209.02
  5609.3  210.75  5680.1  214.43  5694.7  215.74  5726.3  216.76  5737.4   217.3
#Mann= 11 ,-1 , 0
  4633.8     .05       0    4868     .07       0  4944.3      .1       0
  5035.4     .05       0  5039.4      .1       0  5088.8     .12       0
  5245.2     .07       0  5309.2     .12       0  5504.1     .07       0
  5560.3     .12       0  5726.3     .07       0
Bank Sta=5035.4,5039.4
XS Rating Curve= 0 ,0
Exp/Cntr=0.3,0.1

Type RM Length L Ch R = 1 ,25282   ,493,493,493
BEGIN DESCRIPTION:
TRIB TO FIFTEENMILE CREEK 49.0
END DESCRIPTION:
XS GIS Cut Line= 3
      2512875.02     13484175.01        2513375.       13484475.
      2513675.01     13484224.99
#Sta/Elev= 30
  4425.5  203.48  4460.5  202.67    4476  203.64  4507.1  201.34  4542.1  200.33
  4549.9  200.21  4565.4  201.66  4577.1  199.92  4600.4  198.42  4623.7  199.39
  4635.4   198.2  4666.5  196.98    4717  197.29  4831.8   194.6  4915.3  192.76
  4944.5  191.08  4950.3  189.72    4956  189.13  4956.3  188.63    4960  189.13
  4973.6  190.93  4985.2  191.34  5022.2  192.27  5044.4  191.51  5051.8  192.14
  5152.1  193.97  5235.7  195.63  5278.7  197.32    5321  197.66  5399.1  200.16
#Mann= 8 ,-1 , 0
  4425.5     .05       0  4831.8      .1       0  4944.5     .07       0
  4950.3      .1       0    4956     .05       0    4960      .1       0
  5051.8     .07       0  5152.1     .05       0
Bank Sta=4956,4960
XS Rating Curve= 0 ,0
Exp/Cntr=0.3,0.1

Type RM Length L Ch R = 1 ,24789   ,467,467,467
BEGIN DESCRIPTION:
TRIB TO FIFTEENMILE CREEK 48.0
END DESCRIPTION:
XS GIS Cut Line= 3
      2512874.98     13484774.99        2513475.       13484925.
      2513774.97       13484875.
#Sta/Elev= 30
  4381.1   200.4  4424.6  198.47  4486.8  196.05    4528  195.24  4726.5  193.04
  4793.4   191.9    4845  191.89  4865.6  191.23  4927.4  190.76  4935.2   189.9
  4940.3  190.25  4958.4  189.55  4968.7  189.49  4976.4  190.06  4981.5  189.78
  4989.3  188.42    4995  186.49  4995.3  185.99  4998.8  185.99    4999  186.49
  5002.1  186.49  5009.7  188.42  5019.9  189.78  5028.2  190.17  5032.5  190.02
  5121.2  193.33  5141.5  193.42    5210  195.45  5228.4  195.58  5303.7  197.84
#Mann= 7 ,-1 , 0
  4381.1     .07       0  4424.6     .12       0  4726.5      .1       0
    4995     .05       0    4999      .1       0  5028.2     .12       0
  5228.4     .07       0
Bank Sta=4995,4999
XS Rating Curve= 0 ,0
Exp/Cntr=0.3,0.1

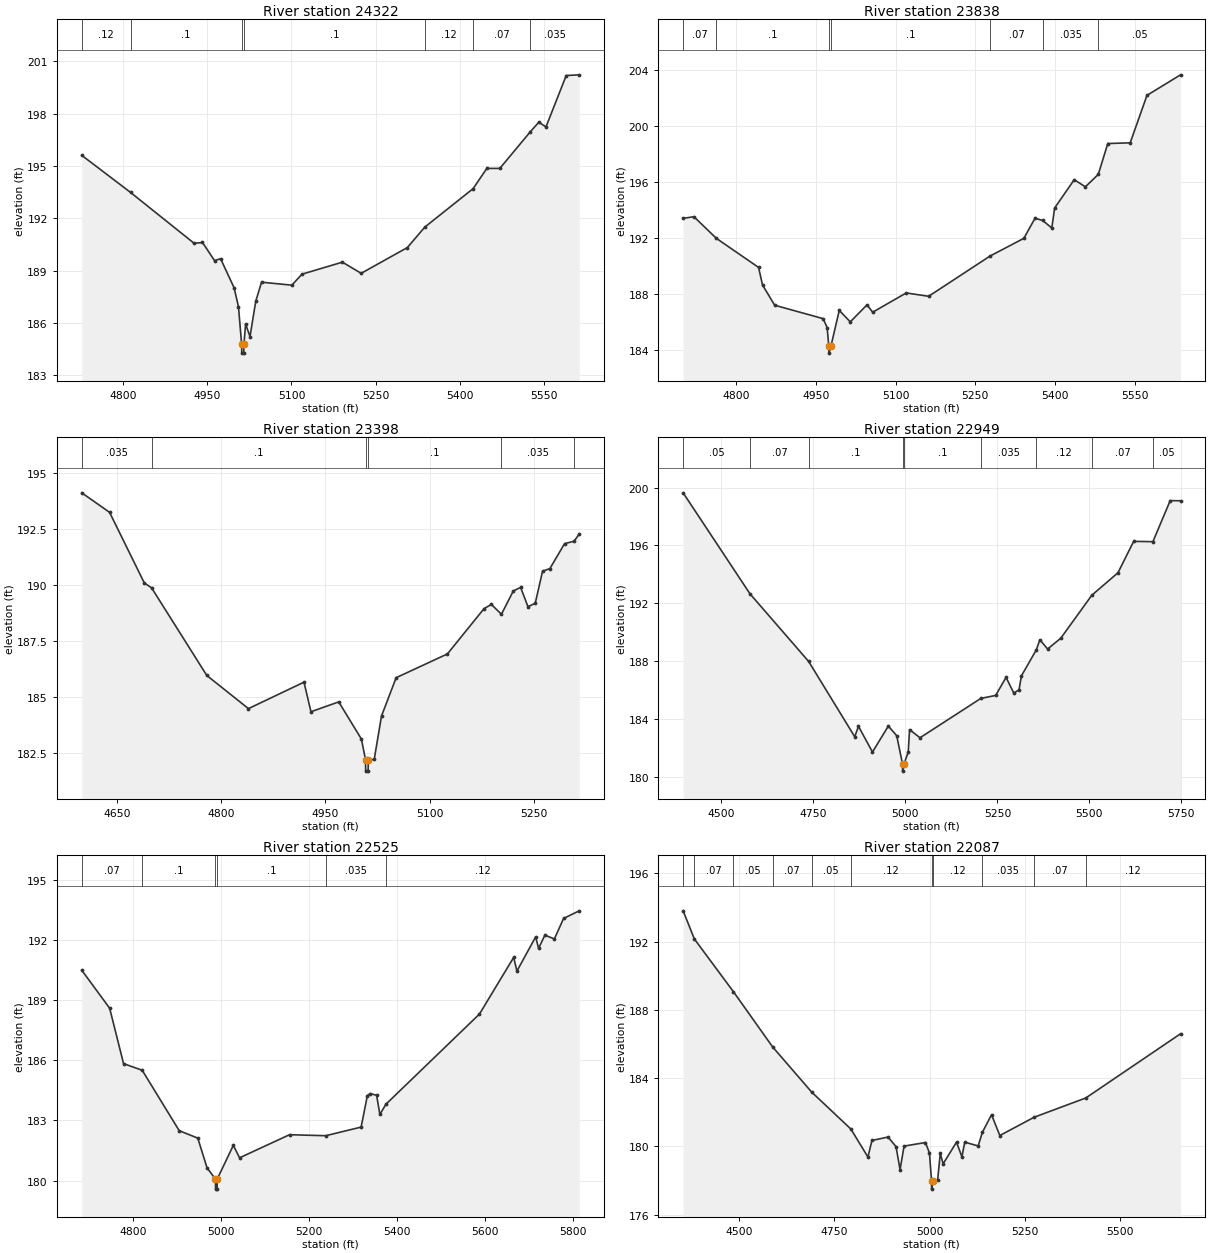
Type RM Length L Ch R = 1 ,24322   ,484,484,484
BEGIN DESCRIPTION:
TRIB TO FIFTEENMILE CREEK 47.0
END DESCRIPTION:
XS GIS Cut Line= 3
      2513025.01     13485424.99        2513275.       13485325.
      2513874.99       13485175.
#Sta/Elev= 30
  4725.8  195.61  4812.9  193.48  4926.4  190.56  4941.2  190.61  4962.7  189.57
  4973.5  189.68  4997.6  188.01  5005.4  186.93  5011.1  184.76  5011.3  184.26
  5014.8  184.26  5015.1  184.76  5018.2  185.93    5026  185.21  5036.3  187.24
  5046.6  188.33  5100.7  188.16  5118.7  188.79  5190.9  189.48  5224.4  188.84
  5306.9  190.32  5337.9  191.49  5424.2   193.7  5448.6  194.86  5471.8  194.86
  5526.2  196.96  5541.4  197.51  5554.2  197.24  5590.3  200.19  5613.5  200.23
#Mann= 7 ,-1 , 0
  4725.8     .12       0  4812.9      .1       0  5011.1     .05       0
  5015.1      .1       0  5337.9     .12       0  5424.2     .07       0
  5526.2    .035       0
Bank Sta=5011.1,5015.1
XS Rating Curve= 0 ,0
Exp/Cntr=0.3,0.1

Type RM Length L Ch R = 1 ,23838   ,440,440,440
BEGIN DESCRIPTION:
TRIB TO FIFTEENMILE CREEK 46.0
END DESCRIPTION:
XS GIS Cut Line= 3
      2513124.96     13485674.99        2513425.       13485725.
      2514024.97     13485525.01
#Sta/Elev= 30
  4700.1  193.41  4720.4  193.53  4762.7  191.98  4842.1   189.9  4849.7  188.63
  4872.5  187.19  4963.7  186.23  4971.3  185.59  4974.4  184.26  4974.6  183.76
  4978.4  184.26  4994.1  186.82  5014.8     186  5046.4  187.22    5057  186.69
  5120.2  188.07  5162.4  187.83  5277.9  190.71  5341.6  191.98  5362.7  193.42
  5377.2  193.26  5394.3  192.72  5399.6  194.15  5436.5  196.18  5457.5  195.67
  5481.8  196.56  5499.7  198.77  5541.9  198.82  5573.5  202.22  5636.7  203.69
#Mann= 7 ,-1 , 0
  4700.1     .07       0  4762.7      .1       0  4974.4     .05       0
  4978.4      .1       0  5277.9     .07       0  5377.2    .035       0
  5481.8     .05       0
Bank Sta=4974.4,4978.4
XS Rating Curve= 0 ,0
Exp/Cntr=0.3,0.1

Type RM Length L Ch R = 1 ,23398   ,449,449,449
BEGIN DESCRIPTION:
TRIB TO FIFTEENMILE CREEK 45.0
END DESCRIPTION:
XS GIS Cut Line= 3
      2513174.98       13486025.        2513575.       13486025.
      2513875.05     13485924.98
#Sta/Elev= 30
  4599.1   194.1  4639.1  193.23  4689.1  190.08  4699.6  189.86  4779.1  185.95
  4839.1  184.47  4919.1  185.65  4929.1  184.33  4969.1  184.77  5001.8  183.11
  5007.7  182.18  5007.9  181.68  5011.4  181.68  5011.7  182.18  5020.2   182.2
  5030.7  184.14  5051.8  185.85  5125.6  186.91  5178.3  188.93  5188.9  189.12
  5203.4  188.68  5220.5  189.72    5231  189.88  5241.6  189.02  5252.1  189.17
  5262.6   190.6  5273.2  190.72  5294.3  191.83    5308  191.94  5315.4  192.26
#Mann= 6 ,-1 , 0
  4599.1    .035       0  4699.6      .1       0  5007.7     .05       0
  5011.7      .1       0  5203.4    .035       0    5308     .12       0
Bank Sta=5007.7,5011.7
XS Rating Curve= 0 ,0
Exp/Cntr=0.3,0.1

Type RM Length L Ch R = 1 ,22949   ,424,424,424
BEGIN DESCRIPTION:
TRIB TO FIFTEENMILE CREEK 44.0
END DESCRIPTION:
XS GIS Cut Line= 3
      2513025.02       13486525.        2513625.       13486425.
      2514125.03     13485874.97
#Sta/Elev= 30
  4396.1  199.64  4577.8  192.65  4737.2  187.97  4862.4  182.76  4872.6  183.48
  4910.6   181.7  4953.7   183.5  4976.5  182.83  4992.2  180.88  4992.5  180.38
  4996.2  180.88  5007.7  181.69  5011.4  183.25  5039.8  182.69  5204.9  185.41
  5245.3  185.62  5273.6  186.87  5294.6  185.78  5308.8  186.01  5315.5  186.98
  5355.7  188.77  5365.5  189.47  5386.5  188.83  5422.3  189.58  5506.5  192.55
  5577.7  194.11  5620.3  196.28  5672.6  196.26  5719.6   199.1  5747.7  199.09
#Mann= 9 ,-1 , 0
  4396.1     .05       0  4577.8     .07       0  4737.2      .1       0
  4992.2     .05       0  4996.2      .1       0  5204.9    .035       0
  5355.7     .12       0  5506.5     .07       0  5672.6     .05       0
Bank Sta=4992.2,4996.2
XS Rating Curve= 0 ,0
Exp/Cntr=0.3,0.1

Type RM Length L Ch R = 1 ,22525   ,438,438,438
BEGIN DESCRIPTION:
TRIB TO FIFTEENMILE CREEK 43.0
END DESCRIPTION:
XS GIS Cut Line= 3
      2513274.97     13486674.99        2513575.       13486775.
        2514175.       13486225.
#Sta/Elev= 30
  4684.3  190.48  4747.6  188.59  4779.2  185.83  4821.6   185.5  4905.7  182.49
  4947.9  182.12  4968.9  180.64    4988  180.08  4988.3  179.58  4991.8  179.58
    4992  180.08  5028.6  181.76  5042.8  181.14  5156.3  182.29  5238.5  182.24
    5319  182.67  5333.2  184.24    5340  184.34  5354.2  184.25  5361.6   183.3
  5375.4  183.81  5587.9   188.3  5665.6  191.12    5673  190.44  5715.5  192.14
  5722.3  191.57  5736.5  192.23  5758.1  192.04    5779  193.06  5814.5  193.44
#Mann= 6 ,-1 , 0
  4684.3     .07       0  4821.6      .1       0    4988     .05       0
    4992      .1       0  5238.5    .035       0  5375.4     .12       0
Bank Sta=4988,4992
XS Rating Curve= 0 ,0
Exp/Cntr=0.3,0.1

Type RM Length L Ch R = 1 ,22087   ,462,462,462
BEGIN DESCRIPTION:
TRIB TO FIFTEENMILE CREEK 42.0
END DESCRIPTION:
XS GIS Cut Line= 3
      2513125.03     13486875.01        2513725.       13487075.
      2514224.99     13486625.01
#Sta/Elev= 30
  4353.4   193.8  4382.9  192.15  4485.5  189.06  4588.2  185.83  4690.8  183.18
  4793.5  181.02  4838.3  179.38  4848.8  180.35    4891  180.55    4912  179.99
  4922.6  178.64  4933.1  180.02  4989.2  180.23  4999.7  179.62  5005.1     178
  5005.4   177.5  5009.1     178  5021.3  178.06  5028.1   179.6  5035.5  178.98
  5070.7  180.25  5084.9  179.39  5092.3  180.25  5127.5  180.03  5138.6  180.83
  5162.6  181.86  5184.3  180.64  5274.3  181.71    5410  182.84  5658.5   186.6
#Mann= 11 ,-1 , 0
  4353.4     .12       0  4382.9     .07       0  4485.5     .05       0
  4588.2     .07       0  4690.8     .05       0  4793.5     .12       0
  5005.1     .05       0  5009.1     .12       0  5138.6    .035       0
  5274.3     .07       0    5410     .12       0
Bank Sta=5005.1,5009.1
XS Rating Curve= 0 ,0
Exp/Cntr=0.3,0.1

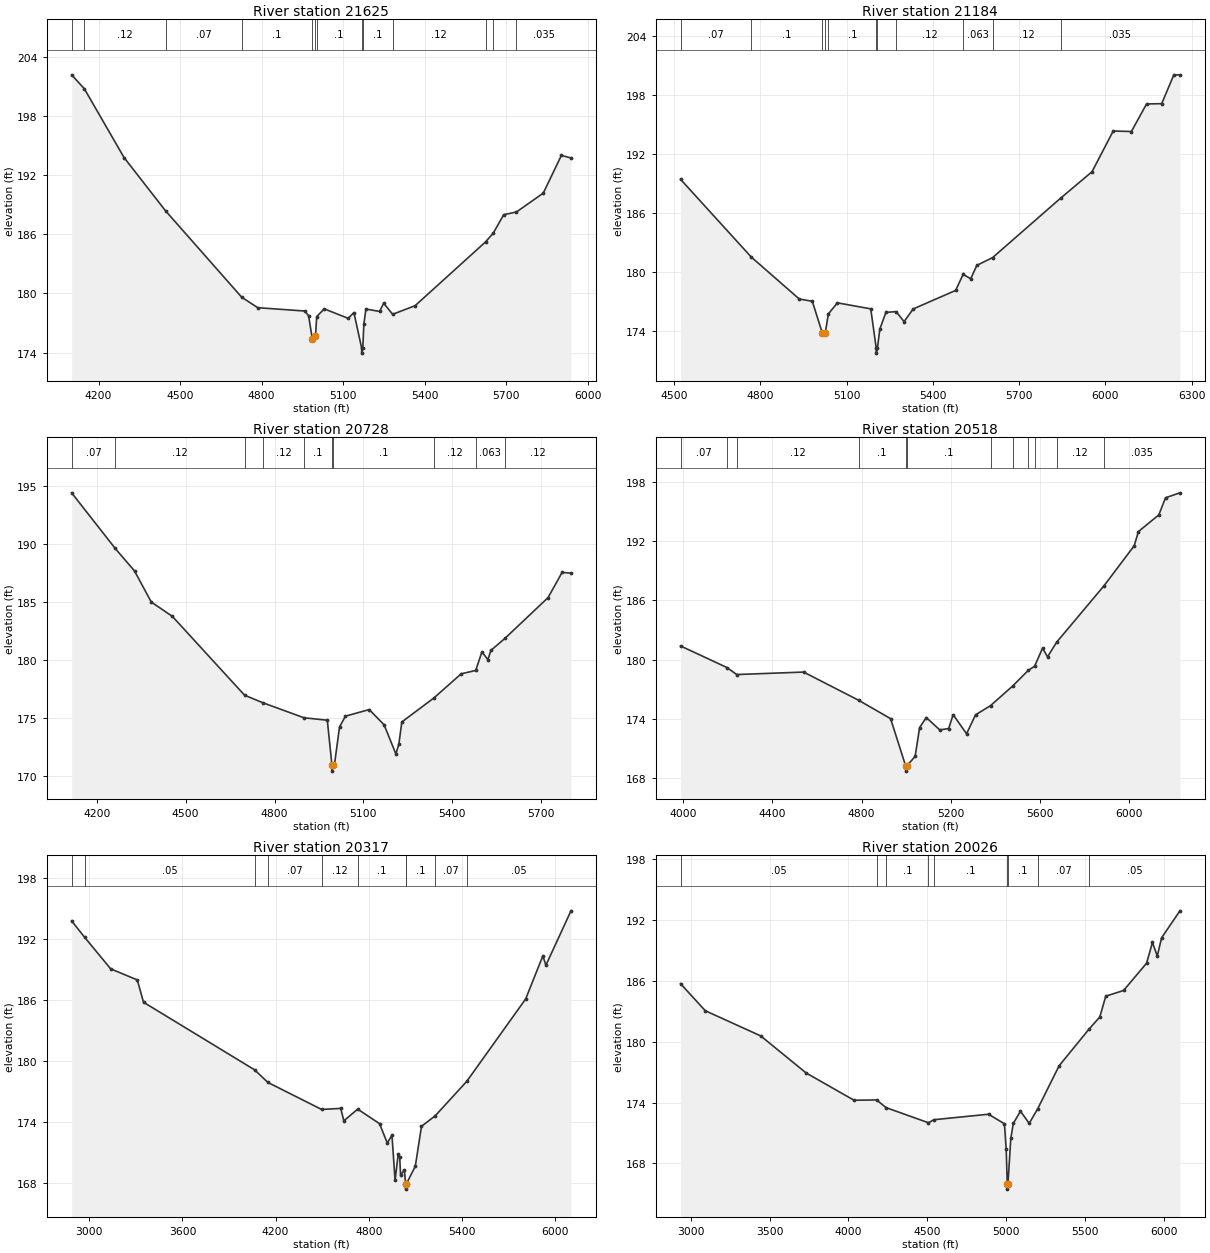
Type RM Length L Ch R = 1 ,21625   ,441,441,441
BEGIN DESCRIPTION:
TRIB TO FIFTEENMILE CREEK 41.0
END DESCRIPTION:
XS GIS Cut Line= 3
        2512875.       13487075.        2513675.       13487475.
      2514474.98     13487974.99
#Sta/Elev= 30
  4100.9  202.18  4147.6  200.77  4293.8  193.79  4446.4  188.39  4726.6  179.63
  4785.7  178.56    4959  178.22    4973  177.74  4986.9  175.36  4998.3  175.64
    5003  177.66  5030.7  178.44  5118.6  177.48  5139.8  178.06  5168.4  174.45
  5168.6  173.95  5172.5  174.45  5176.3  176.87    5184  178.42  5234.1  178.18
  5249.5  179.01  5282.4  177.89    5365  178.76  5624.2  185.23  5652.5  186.11
  5691.1  187.99  5738.1  188.27  5836.7  190.18  5903.3     194  5938.7  193.75
#Mann= 13 ,-1 , 0
  4100.9     .07       0  4147.6     .12       0  4446.4     .07       0
  4726.6      .1       0  4986.9     .05       0  4998.3     .07       0
    5003      .1       0  5168.4     .07       0  5172.5      .1       0
  5282.4     .12       0  5624.2     .07       0  5652.5     .12       0
  5738.1    .035       0
Bank Sta=4986.9,4998.3
XS Rating Curve= 0 ,0
Exp/Cntr=0.3,0.1

Type RM Length L Ch R = 1 ,21184   ,456,456,456
BEGIN DESCRIPTION:
TRIB TO FIFTEENMILE CREEK 40.0
END DESCRIPTION:
XS GIS Cut Line= 3
      2513024.97     13487524.98        2513425.       13487775.
      2514625.05     13488175.02
#Sta/Elev= 30
  4522.6   189.4  4768.3  181.51  4935.4  177.24  4980.8  177.01  5015.4   173.8
    5026   173.8  5036.5  175.72  5068.1  176.85  5184.1  176.24  5203.1  172.24
  5203.4  171.74  5207.2  172.24  5215.7  174.19  5236.8  175.88  5272.4  175.96
    5300  174.94  5331.6  176.23  5479.2  178.11  5505.3  179.74  5531.9   179.3
    5553  180.66    5608  181.45  5844.5  187.49  5953.6  190.17  6027.3  194.31
  6090.6  194.26  6143.3  197.06    6196  197.09  6238.2  200.02  6259.3  200.02
#Mann= 11 ,-1 , 0
  4522.6     .07       0  4768.3      .1       0  5015.4     .05       0
    5026     .07       0  5036.5      .1       0  5203.1     .07       0
  5207.2      .1       0  5272.4     .12       0  5505.3    .063       0
    5608     .12       0  5844.5    .035       0
Bank Sta=5015.4,5026
XS Rating Curve= 0 ,0
Exp/Cntr=0.3,0.1

Type RM Length L Ch R = 1 ,20728   ,210,210,210
BEGIN DESCRIPTION:
TRIB TO FIFTEENMILE CREEK 39.0
END DESCRIPTION:
XS GIS Cut Line= 3
      2512825.02     13487525.02        2513425.       13488175.
      2514224.97       13488125.
#Sta/Elev= 30
  4114.9  194.43  4262.2  189.62  4327.2  187.68  4383.9  184.99  4454.8  183.76
  4698.9  176.94  4760.5  176.29  4899.7  174.99  4978.2  174.78    4994  170.88
  4994.3  170.38  4998.1  170.88    5002  170.88  5019.5   174.2  5039.5  175.13
  5119.7   175.7  5169.8  174.39  5209.9  171.86  5219.9  172.73  5229.9  174.63
    5338   176.7  5430.3  178.79  5479.3  179.08  5500.4  180.69  5520.5  180.01
  5530.5  180.81  5577.9  181.85  5723.4  185.37    5771  187.55    5801  187.49
#Mann= 10 ,-1 , 0
  4114.9     .07       0  4262.2     .12       0  4698.9      .1       0
  4760.5     .12       0  4899.7      .1       0    4994     .05       0
  4998.1      .1       0    5338     .12       0  5479.3    .063       0
  5577.9     .12       0
Bank Sta=4994,4998.1
XS Rating Curve= 0 ,0
Exp/Cntr=0.3,0.1

Type RM Length L Ch R = 1 ,20518   ,201,201,201
BEGIN DESCRIPTION:
Mapping XS d674b12d
END DESCRIPTION:
XS GIS Cut Line= 3
      2512313.36     13488374.85      2513306.37     13488347.07
       2514549.4      13488256.8
#Sta/Elev= 30
  3988.2   181.4  4196.2  179.22  4239.9  178.51  4540.1  178.76  4786.7  175.91
  4930.2  174.05  4998.2  169.24  4998.5  168.74  5002.4  169.24  5040.4  170.24
  5060.4  173.15  5090.5  174.16  5150.7  172.91  5190.8  173.05  5210.8  174.45
    5271  172.52  5311.1  174.43  5378.7  175.37  5477.4  177.34  5547.2  178.92
  5576.2  179.35  5611.9  181.18  5634.2   180.3  5674.9  181.78  5886.8  187.47
    6023  191.54  6041.8  192.97  6133.3  194.66  6163.3  196.39  6227.9  196.89
#Mann= 12 ,-1 , 0
  3988.2     .07       0  4196.2    .035       0  4239.9     .12       0
  4786.7      .1       0  4998.2     .05       0  5002.4      .1       0
  5378.7     .12       0  5477.4    .035       0  5547.2     .12       0
  5576.2    .063       0  5674.9     .12       0  5886.8    .035       0
Bank Sta=4998.2,5002.4
XS Rating Curve= 0 ,0
Exp/Cntr=0.3,0.1

Type RM Length L Ch R = 1 ,20317   ,291,291,291
BEGIN DESCRIPTION:
Mapping XS 0ddb51ed
END DESCRIPTION:
XS GIS Cut Line= 3
      2511252.08     13488597.94      2513370.88      13488531.9
      2514466.01     13488460.36
#Sta/Elev= 30
  2885.8  193.77  2969.1  192.17  3137.3  189.06  3308.9  187.97  3348.9  185.78
  4064.6  179.14  4150.3   177.9  4496.2  175.25  4619.6  175.35  4639.6  174.13
    4729  175.28  4869.7  173.85  4919.7  171.94  4949.7  172.73  4969.7  168.27
  4989.7  170.83  4999.7  170.54  5005.2  168.79  5029.8  169.33  5037.6  167.92
  5037.9  167.42    5042  167.92    5100  169.66    5140  173.59  5228.2  174.62
  5431.7  178.01  5811.5  186.11  5921.7  190.33  5941.7  189.42  6103.1  194.76
#Mann= 10 ,-1 , 0
  2885.8    .035       0  2969.1     .05       0  4064.6    .035       0
  4150.3     .07       0  4496.2     .12       0    4729      .1       0
  5037.6     .05       0    5042      .1       0  5228.2     .07       0
  5431.7     .05       0
Bank Sta=5037.6,5042
XS Rating Curve= 0 ,0
Exp/Cntr=0.3,0.1

Type RM Length L Ch R = 1 ,20026   ,324,324,324
BEGIN DESCRIPTION:
Mapping XS 708d2887
END DESCRIPTION:
XS GIS Cut Line= 3
       2511268.6     13488988.67      2513310.34     13488812.57
      2514405.52     13488586.93
#Sta/Elev= 30
  2935.7  185.73  3092.7  183.06    3444  180.58  3732.4  176.92  4036.2  174.23
  4178.6  174.26  4239.8   173.5  4508.1  172.01    4543  172.31  4889.3  172.85
    4990  171.91  5001.4  169.38    5008  165.96  5008.3  165.46  5012.4  165.96
  5030.6  170.48  5046.6  171.95  5091.8  173.15  5147.2  171.95  5201.9  173.41
  5336.9  177.63  5526.9  181.25  5594.8  182.44    5633   184.5  5745.8  185.06
  5891.6  187.75  5929.1   189.8  5959.7  188.46  5987.1  190.26  6103.2  192.92
#Mann= 9 ,-1 , 0
  2935.7     .05       0  4178.6     .12       0  4239.8      .1       0
  4508.1     .07       0    4543      .1       0    5008     .05       0
  5012.4      .1       0  5201.9     .07       0  5526.9     .05       0
Bank Sta=5008,5012.4
XS Rating Curve= 0 ,0
Exp/Cntr=0.3,0.1

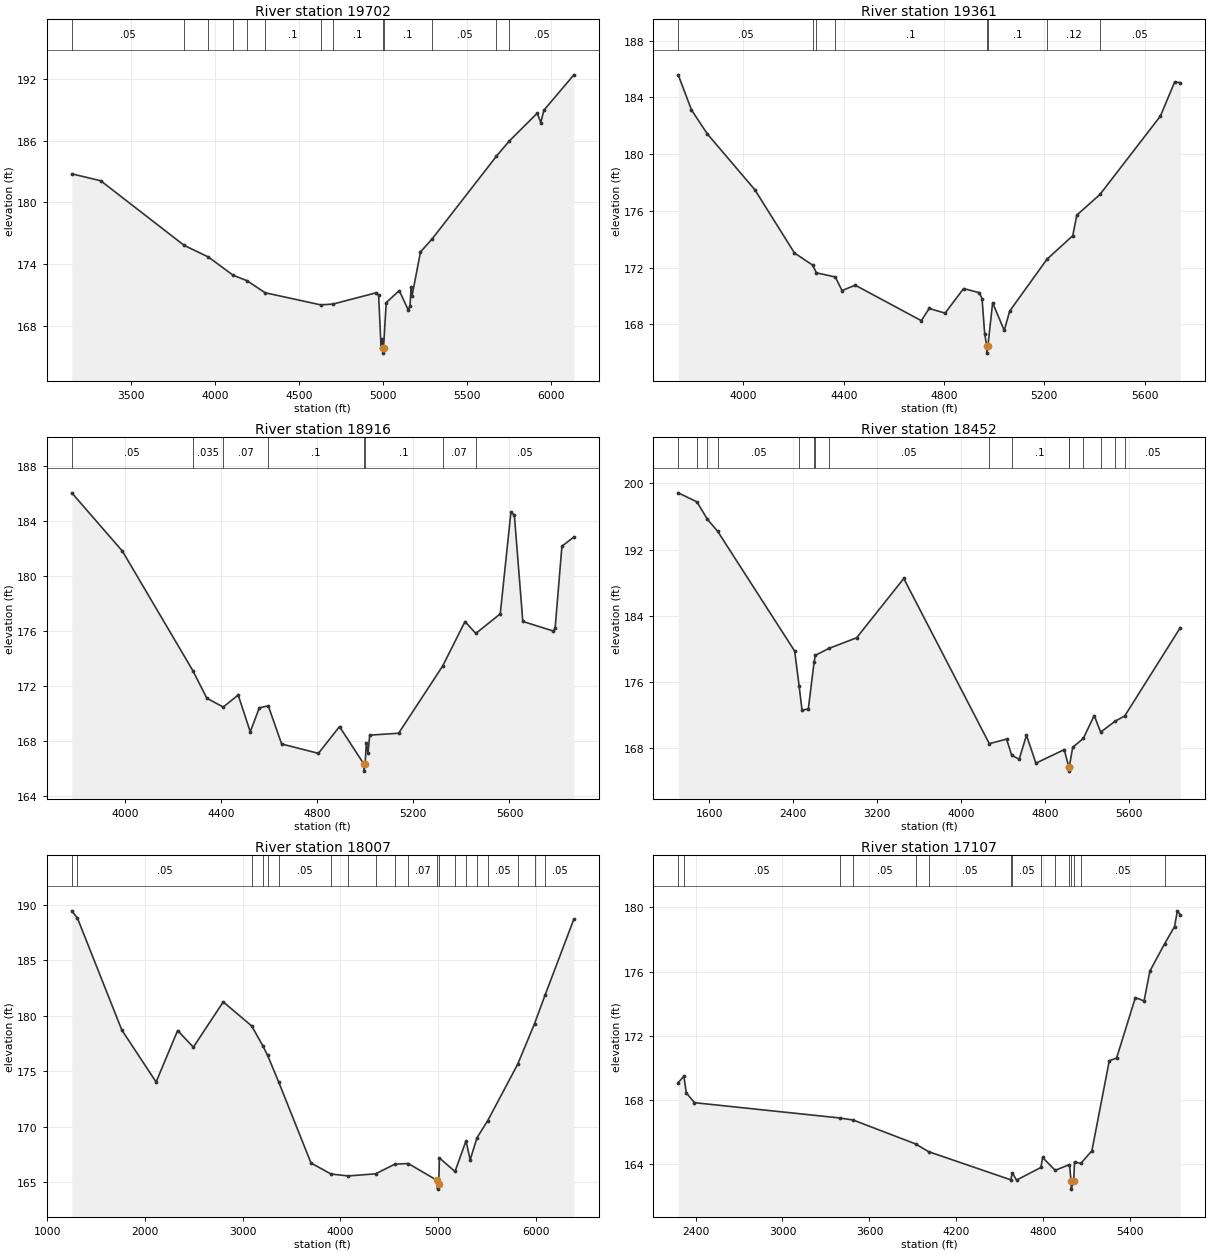
Type RM Length L Ch R = 1 ,19702   ,341,341,341
BEGIN DESCRIPTION:
Mapping XS f534d482
END DESCRIPTION:
XS GIS Cut Line= 3
      2511472.25     13489527.99      2513249.81     13489126.25
      2514339.42     13488730.03
#Sta/Elev= 30
  3151.2  182.78  3323.4   182.1  3818.9  175.82  3961.9   174.7  4109.6  172.92
  4191.9  172.39  4299.3  171.22  4629.9  170.04  4702.8  170.12  4960.1  171.22
  4973.6  170.97  4988.2  165.89  4993.5  166.72  4998.2  165.85  4998.5  165.35
  5002.6  165.85  5018.7  170.26  5096.2  171.43  5149.4  169.55    5160  169.92
  5166.4  171.76  5171.7  170.89  5222.2  175.18  5292.8  176.48  5673.2  184.49
  5748.6  185.95  5915.5  188.67  5936.8  187.76  5955.1  188.96    6133   192.4
#Mann= 13 ,-1 , 0
  3151.2     .05       0  3818.9     .12       0  3961.9     .05       0
  4109.6      .1       0  4191.9     .05       0  4299.3      .1       0
  4629.9     .12       0  4702.8      .1       0  4998.2     .05       0
  5002.6      .1       0  5292.8     .05       0  5673.2     .07       0
  5748.6     .05       0
Bank Sta=4998.2,5002.6
XS Rating Curve= 0 ,0
Exp/Cntr=0.3,0.1

Type RM Length L Ch R = 1 ,19361   ,445,445,445
BEGIN DESCRIPTION:
TRIB TO FIFTEENMILE CREEK 36.0
END DESCRIPTION:
XS GIS Cut Line= 3
      2512075.04     13489824.99        2513275.       13489425.
      2513924.99       13489075.
#Sta/Elev= 30
  3739.7  185.59  3792.4  183.12  3855.6  181.43  4045.3  177.49  4203.5  173.03
  4275.5  172.18  4291.1  171.63  4366.3  171.34  4393.2  170.38  4445.9  170.76
  4709.4  168.26    4741  169.12  4804.3  168.79  4878.1  170.52  4941.3  170.23
  4951.9   169.8  4962.4  167.32  4970.7  166.47    4971  165.97  4975.1  166.47
    4994  169.52  5040.3  167.57  5062.2  168.94  5210.9  172.59  5313.7  174.25
  5329.9   175.7  5422.4  177.16  5663.3  182.68  5720.1  185.08  5742.8  185.04
#Mann= 8 ,-1 , 0
  3739.7     .05       0  4275.5    .035       0  4291.1     .05       0
  4366.3      .1       0  4970.7     .05       0  4975.1      .1       0
  5210.9     .12       0  5422.4     .05       0
Bank Sta=4970.7,4975.1
XS Rating Curve= 0 ,0
Exp/Cntr=0.3,0.1

Type RM Length L Ch R = 1 ,18916   ,464,464,464
BEGIN DESCRIPTION:
TRIB TO FIFTEENMILE CREEK 35.0
END DESCRIPTION:
XS GIS Cut Line= 3
      2512075.02       13489925.        2513275.       13489825.
      2513924.98     13489225.02
#Sta/Elev= 30
  3779.1  186.02  3989.8  181.79  4282.8  173.12    4341  171.12  4409.1  170.48
  4471.5  171.35  4521.6  168.68  4559.3  170.42  4596.6  170.57  4652.1   167.8
  4805.1  167.12  4892.9  169.06  4994.9  166.33  4995.2  165.83  4999.3  166.33
  5004.5  167.86  5011.3  167.14  5018.7  168.44  5138.9  168.58  5321.8  173.45
    5415  176.68    5460  175.82  5561.6  177.24  5606.1  184.63  5620.3   184.4
  5655.5  176.69  5783.1  175.99  5789.9   176.2  5818.2  182.15  5867.8  182.81
#Mann= 8 ,-1 , 0
  3779.1     .05       0  4282.8    .035       0  4409.1     .07       0
  4596.6      .1       0  4994.9     .05       0  4999.3      .1       0
  5321.8     .07       0    5460     .05       0
Bank Sta=4994.9,4999.3
XS Rating Curve= 0 ,0
Exp/Cntr=0.3,0.1

Type RM Length L Ch R = 1 ,18452   ,445,445,445
BEGIN DESCRIPTION:
TRIB TO FIFTEENMILE CREEK 34.0
END DESCRIPTION:
XS GIS Cut Line= 3
       2509734.8     13490206.95        2513425.       13490225.
      2514174.98     13489425.02
#Sta/Elev= 30
  1304.4  198.86  1483.2  197.76  1581.5  195.68  1679.8  194.22  2414.6  179.73
  2457.4  175.47  2484.6   172.6  2544.6  172.74  2599.9  178.43  2611.6  179.23
  2741.5  180.06  3004.6  181.34  3454.6  188.51  4270.2  168.55  4434.6   169.1
  4483.8  167.15  4554.6  166.67  4624.6  169.56  4714.6  166.19  4984.6  167.83
  5027.8  165.73  5028.2  165.23  5032.3  165.73  5065.2   168.1  5166.2  169.18
  5270.4  171.95  5331.8  169.94  5467.1  171.24  5561.9  171.91  6091.2  182.57
#Mann= 16 ,-1 , 0
  1304.4     .05       0  1483.2     .05       0  1581.5    .035       0
  1679.8     .05       0  2457.4    .063       0  2599.9     .05       0
  2611.6    .063       0  2741.5     .05       0  4270.2     .07       0
  4483.8      .1       0  5027.8     .05       0  5032.3      .1       0
  5166.2     .07       0  5331.8     .05       0  5467.1     .07       0
  5561.9     .05       0
Bank Sta=5027.8,5032.3
XS Rating Curve= 0 ,0
Exp/Cntr=0.3,0.1

Type RM Length L Ch R = 1 ,18007   ,900,900,900
BEGIN DESCRIPTION:
TRIB TO FIFTEENMILE CREEK 33.0
END DESCRIPTION:
XS GIS Cut Line= 4
      2510144.84     13490389.92      2513642.99     13490661.76
        2513675.       13490425.      2514375.02     13489224.96
#Sta/Elev= 30
  1252.4  189.45    1311  188.78  1764.1  178.71  2115.2  174.02  2335.8  178.66
  2496.3  177.16  2802.2  181.24  3093.4  179.07  3205.9   177.3  3256.6  176.41
  3369.7  174.01  3699.9  166.72  3904.6  165.72  4083.7  165.55  4360.9  165.74
  4557.7  166.61  4694.9  166.67  4989.9  165.15  4994.3  164.36  5006.9  164.86
  5013.7  167.17  5173.5  165.95  5285.8  168.71  5328.7     167  5398.1  168.99
  5507.9  170.53  5813.5   175.6  5986.8  179.27  6094.3  181.84  6389.3   188.7
#Mann= 20 ,-1 , 0
  1252.4    .035       0    1311     .05       0  3093.4    .035       0
  3205.9     .05       0  3256.6    .035       0  3369.7     .05       0
  3904.6     .07       0  4083.7     .05       0  4360.9     .07       0
  4557.7     .05       0  4694.9     .07       0  4989.9     .05       0
  5006.9     .07       0  5173.5     .07       0  5285.8     .05       0
  5398.1     .07       0  5507.9     .05       0  5813.5     .05       0
  5986.8     .05       0  6094.3     .05       0
Bank Sta=4989.9,5006.9
XS Rating Curve= 0 ,0
Exp/Cntr=0.3,0.1

Type RM Length L Ch R = 1 ,17107   ,441,441,441
BEGIN DESCRIPTION:
TRIB TO FIFTEENMILE CREEK 31.0
END DESCRIPTION:
XS GIS Cut Line= 4
      2513331.23     13492699.52        2514325.      13491626.9
        2514325.       13490375.        2514325.     13489625.03
#Sta/Elev= 30
  2280.8  169.09  2319.9  169.49  2336.3  168.45    2393  167.84  3393.5  166.89
  3488.1  166.76  3919.2  165.27  4008.4  164.79  4574.9  163.04  4585.9  163.47
  4614.9  163.02  4783.1  163.81  4794.9  164.43  4881.7  163.63  4980.3  163.99
  4991.2  162.96  4992.4  162.46  5009.2  162.96  5014.9  164.15  5058.6  164.06
  5134.9  164.85  5254.9  170.45  5304.9  170.61  5434.9  174.38  5494.9  174.17
  5534.9  176.03  5637.2  177.74  5704.9   178.8  5724.9  179.78  5744.9  179.54
#Mann= 15 ,-1 , 0
  2280.8    .045       0  2319.9     .05       0  3393.5    .035       0
  3488.1     .05       0  3919.2     .07       0  4008.4     .05       0
  4574.9     .07       0  4585.9     .05       0  4783.1     .07       0
  4881.7     .05       0  4980.3     .07       0  4992.4     .05       0
  5009.2     .07       0  5058.6     .05       0  5637.2     .05       0
Bank Sta=4991.2,5009.2
XS Rating Curve= 0 ,0
Exp/Cntr=0.3,0.1