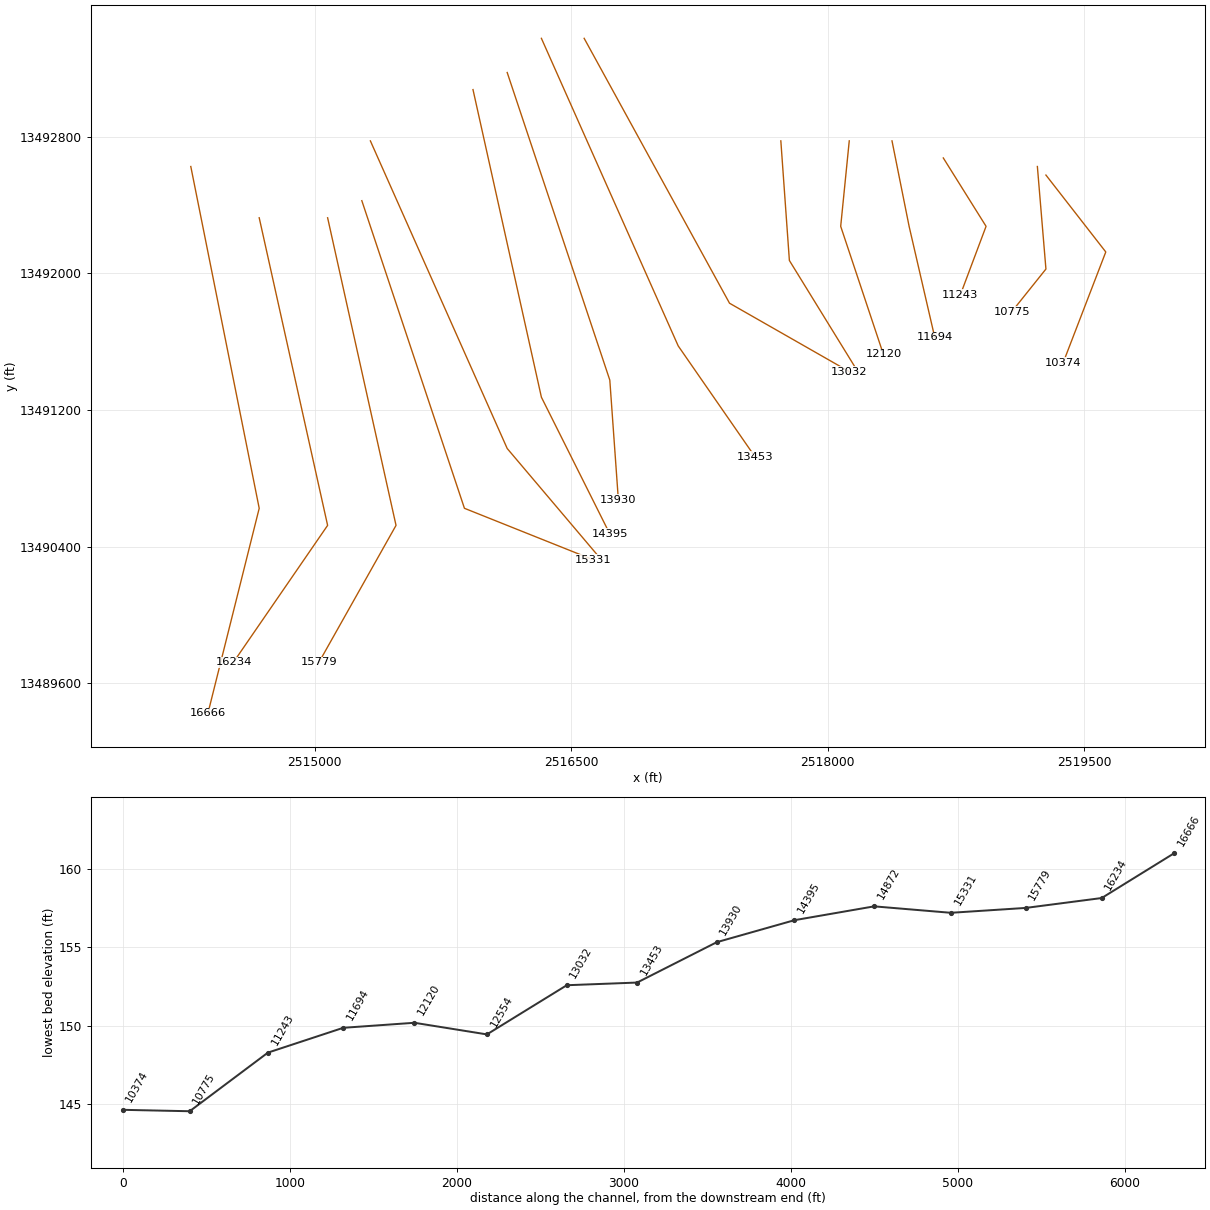
HEC-RAS study TRIB TO FIFTEENMILE CREEK.prj: TRIB TO FIFTEENMILE CREEK Base Level Engineering

--- TRIB TO FIFTEENMILE CREEK.g01 (geometry) --- (continued)

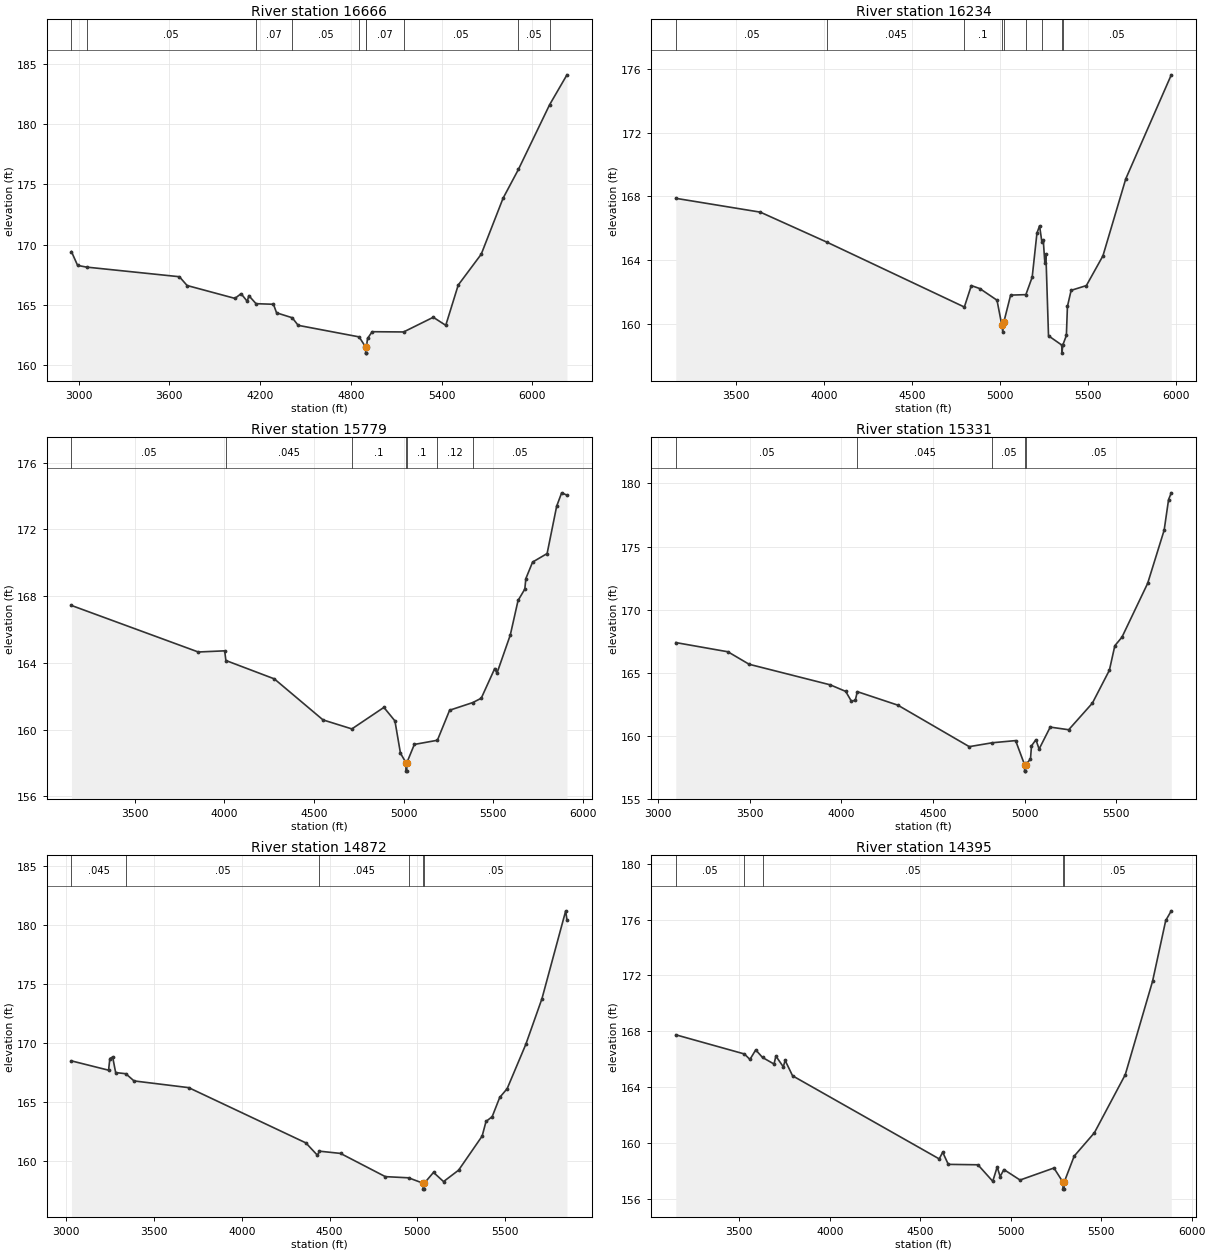
Type RM Length L Ch R = 1 ,16666   ,432,432,432
BEGIN DESCRIPTION:
TRIB TO FIFTEENMILE CREEK 30.0
END DESCRIPTION:
XS GIS Cut Line= 3
        2514275.     13492624.98        2514675.       13490625.
      2514375.01     13489425.02
#Sta/Elev= 30
  2952.6  169.42  2993.4  168.27  3052.4  168.13  3666.4  167.33  3717.4   166.6
  4033.6  165.53  4074.4  165.92  4115.2  165.28  4125.4  165.76  4173.1  165.09
  4288.5  165.04  4308.9  164.33  4412.6  163.92  4451.7  163.29  4854.7  162.33
  4898.2  161.48  4898.5  160.98  4902.4  160.98  4902.7  161.48  4910.6   162.2
  4941.2  162.76  5149.1  162.74  5345.2  163.96  5427.7  163.29  5510.2  166.64
  5662.2   169.2  5806.5  173.85  5908.2  176.25  6114.2  181.62  6229.1  184.11
#Mann= 10 ,-1 , 0
  2952.6    .045       0  3052.4     .05       0  4173.1     .07       0
  4412.6     .05       0  4854.7     .07       0  4898.2     .05       0
  4902.7     .07       0  5149.1     .05       0  5908.2     .05       0
  6114.2     .05       0
Bank Sta=4898.2,4902.7
XS Rating Curve= 0 ,0
Exp/Cntr=0.3,0.1

Type RM Length L Ch R = 1 ,16234   ,455,455,455
BEGIN DESCRIPTION:
TRIB TO FIFTEENMILE CREEK 29.0
END DESCRIPTION:
XS GIS Cut Line= 3
      2514674.99     13492325.03        2515075.       13490525.
      2514524.98     13489724.97
#Sta/Elev= 30
  3156.4  167.88  3636.6  167.01  4017.2  165.11  4795.6  161.04  4835.2  162.39
  4883.8   162.2  4981.1  161.47  5007.8  159.94  5013.9  159.49  5019.6  160.08
  5058.5  161.79  5145.1  161.82    5181  162.92    5208  165.69  5222.9  166.15
  5235.7  165.16  5243.9  165.26  5252.7  163.84  5258.8  164.37  5273.7  159.23
    5350  158.64  5350.3  158.14  5354.6  158.64  5375.2  159.25  5381.2  161.08
  5402.2  162.09  5488.8  162.39  5582.8  164.26  5712.7  169.11  5971.2  175.65
#Mann= 9 ,-1 , 0
  3156.4     .05       0  4017.2    .045       0  4795.6      .1       0
  5007.8     .05       0  5019.6     .05       0  5145.1     .07       0
  5235.7     .05       0    5350     .05       0  5354.6     .05       0
Bank Sta=5007.8,5019.6
XS Rating Curve= 0 ,0
Exp/Cntr=0.3,0.1

Type RM Length L Ch R = 1 ,15779   ,448,448,448
BEGIN DESCRIPTION:
TRIB TO FIFTEENMILE CREEK 28.0
END DESCRIPTION:
XS GIS Cut Line= 3
      2515074.99     13492325.05        2515475.       13490525.
      2515025.02     13489725.03
#Sta/Elev= 30
  3148.5  167.44  3855.4  164.65  4002.6  164.72  4009.2  164.14  4279.2  163.04
  4550.7  160.58  4711.5  160.04    4890  161.33  4951.5  160.52  4982.2  158.59
  5013.1  158.01  5013.4  157.51  5017.4  157.51  5017.8  158.01  5059.7  159.11
  5188.2  159.36  5256.3  161.16  5385.6  161.62  5432.6  161.88  5507.8  163.66
  5520.2  163.38  5594.5  165.67  5637.8  167.74  5675.4  168.42  5681.2  169.05
  5718.8  170.04  5799.7  170.55    5853  173.39  5880.7  174.19  5910.3  174.05
#Mann= 7 ,-1 , 0
  3148.5     .05       0  4009.2    .045       0  4711.5      .1       0
  5013.1     .05       0  5017.8      .1       0  5188.2     .12       0
  5385.6     .05       0
Bank Sta=5013.1,5017.8
XS Rating Curve= 0 ,0
Exp/Cntr=0.3,0.1

Type RM Length L Ch R = 1 ,15331   ,459,459,459
BEGIN DESCRIPTION:
TRIB TO FIFTEENMILE CREEK 27.0
END DESCRIPTION:
XS GIS Cut Line= 3
      2515275.01     13492424.96        2515875.       13490625.
        2516625.       13490325.
#Sta/Elev= 30
  3095.9  167.39  3380.5  166.66  3496.4  165.67  3939.1  164.04  4023.5  163.52
  4055.1  162.73  4076.2  162.83  4086.8   163.5  4308.1  162.43  4698.1  159.14
  4824.5  159.45  4951.1  159.62  5000.2   157.7  5000.5   157.2  5004.7   157.2
  5005.1   157.7  5032.3  158.16  5037.7   159.2  5061.9  159.69  5079.4  158.95
    5140  160.69  5240.9  160.48  5370.2  162.59  5463.1   165.2  5492.7  167.14
  5531.7  167.82  5671.8  172.08    5762   176.3  5786.2  178.73    5801  179.26
#Mann= 5 ,-1 , 0
  3095.9     .05       0  4086.8    .045       0  4824.5     .05       0
  5000.2     .05       0  5005.1     .05       0
Bank Sta=5000.2,5005.1
XS Rating Curve= 0 ,0
Exp/Cntr=0.3,0.1

Type RM Length L Ch R = 1 ,14872   ,477,477,477
BEGIN DESCRIPTION:
TRIB TO FIFTEENMILE CREEK 26.0
END DESCRIPTION:
XS GIS Cut Line= 3
      2515325.01     13492774.98        2516125.       13490975.
      2516674.99     13490325.02
#Sta/Elev= 30
  3030.2  168.49  3241.5   167.7    3249  168.69  3264.8  168.82  3281.9   167.5
  3339.7   167.4  3386.5  166.79  3697.7  166.22  4365.2  161.53  4430.9  160.48
  4441.9  160.83  4562.2  160.64  4817.3  158.67  4949.7  158.57  5032.3  158.11
  5032.8  157.61  5038.6  157.61  5039.1  158.11  5091.6  159.03  5148.8  158.25
  5234.6  159.22  5368.5  162.11  5390.6  163.35  5425.7  163.76  5468.6  165.39
  5510.8  166.13  5616.8  169.88  5709.1  173.77  5844.3  181.22  5851.4  180.44
#Mann= 6 ,-1 , 0
  3030.2    .045       0  3339.7     .05       0  4441.9    .045       0
  4949.7     .05       0  5032.3     .05       0  5039.1     .05       0
Bank Sta=5032.3,5039.1
XS Rating Curve= 0 ,0
Exp/Cntr=0.3,0.1

Type RM Length L Ch R = 1 ,14395   ,465,465,465
BEGIN DESCRIPTION:
TRIB TO FIFTEENMILE CREEK 25.0
END DESCRIPTION:
XS GIS Cut Line= 3
        2515925.     13493075.02        2516325.       13491275.
      2516725.02     13490474.96
#Sta/Elev= 30
  3149.1  167.76  3528.1  166.39  3558.9     166  3590.9  166.68  3628.5  166.14
    3692  165.67  3702.3  166.24  3743.3  165.47  3753.5  165.93  3794.5  164.83
    4605  158.89  4624.2  159.37    4655   158.5  4818.9  158.47  4900.8  157.29
  4925.2  158.31  4941.8  157.63  4962.3  158.13  5051.7  157.38    5239  158.24
  5288.7  157.23  5289.2  156.73  5295.1  156.73  5295.6  157.23  5350.8  159.09
  5462.6  160.76  5633.1  164.91    5784  171.59  5856.7  175.93  5887.5  176.62
#Mann= 5 ,-1 , 0
  3149.1     .05       0  3528.1     .07       0  3628.5     .05       0
  5288.7     .05       0  5295.6     .05       0
Bank Sta=5288.7,5295.6
XS Rating Curve= 0 ,0
Exp/Cntr=0.3,0.1

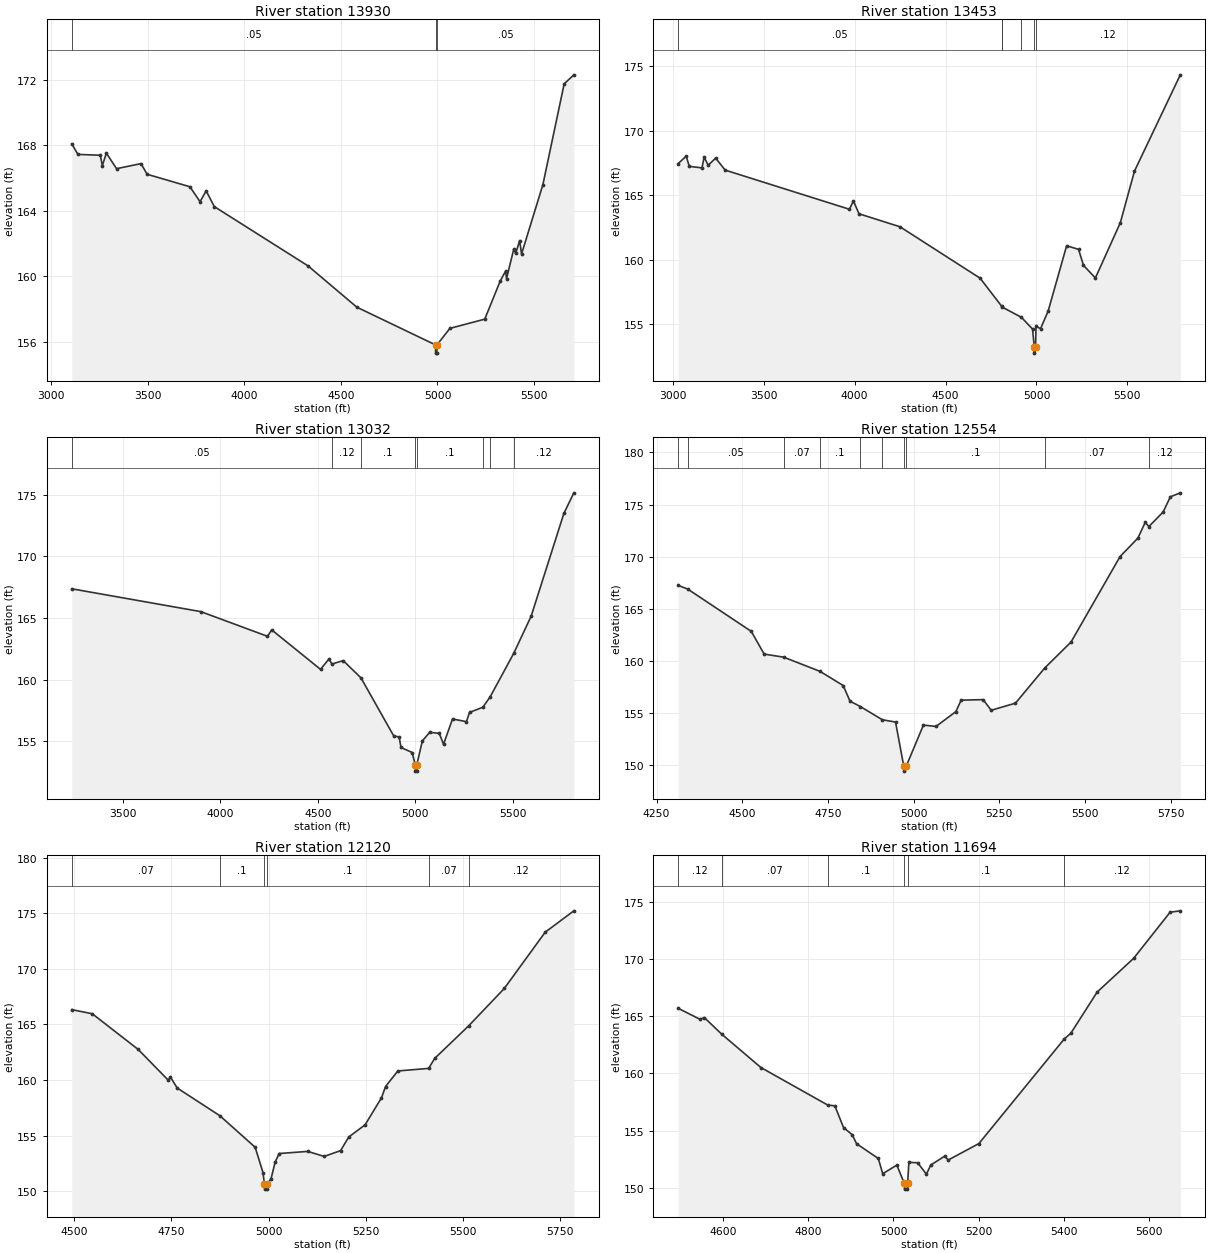
Type RM Length L Ch R = 1 ,13930   ,477,477,477
BEGIN DESCRIPTION:
TRIB TO FIFTEENMILE CREEK 24.0
END DESCRIPTION:
XS GIS Cut Line= 3
      2516124.99     13493175.04        2516725.       13491375.
        2516775.     13490674.99
#Sta/Elev= 30
  3106.9  168.09  3138.6  167.44  3254.5  167.39  3265.1  166.76  3286.1  167.52
  3338.8  166.57  3465.3  166.88    3497  166.23  3718.3  165.47    3771  164.56
  3802.6  165.22  3844.8  164.26  4329.7  160.65  4582.7  158.13  4990.2  155.83
  4990.7  155.33  4996.8  155.33  4997.3  155.83  5064.5  156.84  5244.9   157.4
  5325.1  159.73  5352.7  160.33  5357.7  159.87  5395.3  161.68  5405.3  161.41
  5425.4  162.19  5435.4  161.37  5545.7  165.59    5656  171.74  5706.1  172.29
#Mann= 3 ,-1 , 0
  3106.9     .05       0  4990.2     .05       0  4997.3     .05       0
Bank Sta=4990.2,4997.3
XS Rating Curve= 0 ,0
Exp/Cntr=0.3,0.1

Type RM Length L Ch R = 1 ,13453   ,421,421,421
BEGIN DESCRIPTION:
TRIB TO FIFTEENMILE CREEK 23.0
END DESCRIPTION:
XS GIS Cut Line= 3
      2516325.01     13493374.98        2517125.       13491575.
      2517574.99     13490925.01
#Sta/Elev= 30
  3030.5  167.47  3074.2  168.04  3091.3  167.25  3161.1  167.13  3172.7  167.96
  3195.3  167.34  3236.3  167.89  3288.3  166.96  3971.6  163.92  3993.5  164.57
  4024.3  163.57    4250  162.56  4690.4  158.57    4808  156.41  4810.5  156.34
    4917  155.54  4978.4  154.63  4987.7  153.26  4988.2  152.76  4995.1  153.26
  4997.5  154.84  5022.5  154.66  5064.4  156.03  5165.8  161.09  5231.3  160.81
  5258.4  159.57  5323.9  158.59  5461.1  162.88  5538.8  166.88  5790.8  174.35
#Mann= 6 ,-1 , 0
  3030.5     .05       0    4808     .12       0  4810.5     .05       0
    4917     .12       0  4987.7     .05       0  4995.1     .12       0
Bank Sta=4987.7,4995.1
XS Rating Curve= 0 ,0
Exp/Cntr=0.3,0.1

Type RM Length L Ch R = 1 ,13032   ,478,478,478
BEGIN DESCRIPTION:
TRIB TO FIFTEENMILE CREEK 22.0
END DESCRIPTION:
XS GIS Cut Line= 3
      2516575.01     13493374.99        2517425.       13491825.
      2518125.02     13491424.99
#Sta/Elev= 30
  3238.4  167.37  3899.9  165.52  4241.7  163.52  4263.5  164.04  4513.7  160.84
  4557.3  161.69  4571.7  161.27  4629.8  161.55    4721  160.15  4889.1  155.44
  4916.6  155.36  4926.3  154.51  4983.3   154.1  4999.6  153.09  5000.1  152.59
  5006.6  152.59  5007.1  153.09  5035.7  155.04  5073.1  155.73  5122.1  155.66
  5144.4  154.77  5190.4  156.82  5261.7   156.6  5277.5  157.35  5345.9  157.77
  5383.3  158.61  5503.9  162.13  5593.5  165.15  5761.3  173.48  5812.4  175.15
#Mann= 8 ,-1 , 0
  3238.4     .05       0  4571.7     .12       0    4721      .1       0
  4999.6     .05       0  5007.1      .1       0  5345.9     .12       0
  5383.3     .07       0  5503.9     .12       0
Bank Sta=4999.6,5007.1
XS Rating Curve= 0 ,0
Exp/Cntr=0.3,0.1

Type RM Length L Ch R = 1 ,12554   ,434,434,434
BEGIN DESCRIPTION:
TRIB TO FIFTEENMILE CREEK 21.0
END DESCRIPTION:
XS GIS Cut Line= 3
        2517725.     13492775.03        2517775.       13492075.
      2518174.98     13491425.03
#Sta/Elev= 30
  4313.4  167.25  4341.1   166.9  4526.5  162.85  4564.1  160.67  4620.8  160.38
  4726.9  159.02  4794.7  157.66  4814.7  156.16  4844.7  155.65  4909.1  154.38
  4947.5  154.16  4971.3  149.96  4971.8  149.46    4979  149.96  5028.8  153.87
  5065.5  153.74  5123.5  155.16  5138.9  156.26  5203.1  156.31  5226.6  155.29
  5297.4  155.97  5382.8  159.34  5459.6  161.83  5602.7  170.02  5654.8  171.79
  5676.1   173.3  5686.6  172.89  5728.2  174.28  5749.4  175.74  5778.4  176.12
#Mann= 10 ,-1 , 0
  4313.4     .07       0  4341.1     .05       0  4620.8     .07       0
  4726.9      .1       0  4844.7     .05       0  4909.1      .1       0
  4971.3     .05       0    4979      .1       0  5382.8     .07       0
  5686.6     .12       0
Bank Sta=4971.3,4979
XS Rating Curve= 0 ,0
Exp/Cntr=0.3,0.1

Type RM Length L Ch R = 1 ,12120   ,426,426,426
BEGIN DESCRIPTION:
TRIB TO FIFTEENMILE CREEK 20.0
END DESCRIPTION:
XS GIS Cut Line= 3
        2518125.     13492775.03        2518075.       13492275.
        2518325.     13491524.99
#Sta/Elev= 30
  4493.2  166.33    4546  165.96  4664.1  162.76    4742  159.98    4747  160.29
  4764.6  159.29  4874.5   156.8  4965.6  153.96  4985.7  151.68  4989.3   150.7
  4989.8   150.2  4996.6   150.2  4997.1   150.7  5006.3  151.11  5016.8  152.61
  5027.3   153.4  5101.1  153.59  5143.3  153.14  5185.5  153.66  5206.5  154.88
  5248.7  155.98  5290.9  158.41  5301.4  159.42    5333  160.82  5412.4  161.05
  5427.9  161.95  5515.3  164.87  5607.1  168.23  5712.5  173.29  5786.3  175.21
#Mann= 6 ,-1 , 0
  4493.2     .07       0  4874.5      .1       0  4989.3     .05       0
  4997.1      .1       0  5412.4     .07       0  5515.3     .12       0
Bank Sta=4989.3,4997.1
XS Rating Curve= 0 ,0
Exp/Cntr=0.3,0.1

Type RM Length L Ch R = 1 ,11694   ,451,451,451
BEGIN DESCRIPTION:
TRIB TO FIFTEENMILE CREEK 19.0
END DESCRIPTION:
XS GIS Cut Line= 3
        2518375.     13492775.01        2518475.       13492275.
        2518625.       13491625.
#Sta/Elev= 30
  4495.5   165.7  4546.5  164.74  4556.7  164.89  4597.7  163.43  4689.3  160.52
  4846.2  157.23  4862.6  157.17    4883  155.27  4903.4  154.64  4913.6  153.85
  4964.6  152.56  4974.8  151.23    5008  151.98  5025.5  150.38    5026  149.88
  5032.8  149.88  5033.3  150.38  5036.2  152.22  5056.7  152.19  5077.3  151.19
  5087.5  151.99    5120  152.76  5128.6  152.43  5200.4  153.87  5400.7  163.03
  5415.9  163.52  5477.5  167.12    5563  170.07  5648.6  174.11  5672.5  174.23
#Mann= 6 ,-1 , 0
  4495.5     .12       0  4597.7     .07       0  4846.2      .1       0
  5025.5     .05       0  5033.3      .1       0  5400.7     .12       0
Bank Sta=5025.5,5033.3
XS Rating Curve= 0 ,0
Exp/Cntr=0.3,0.1

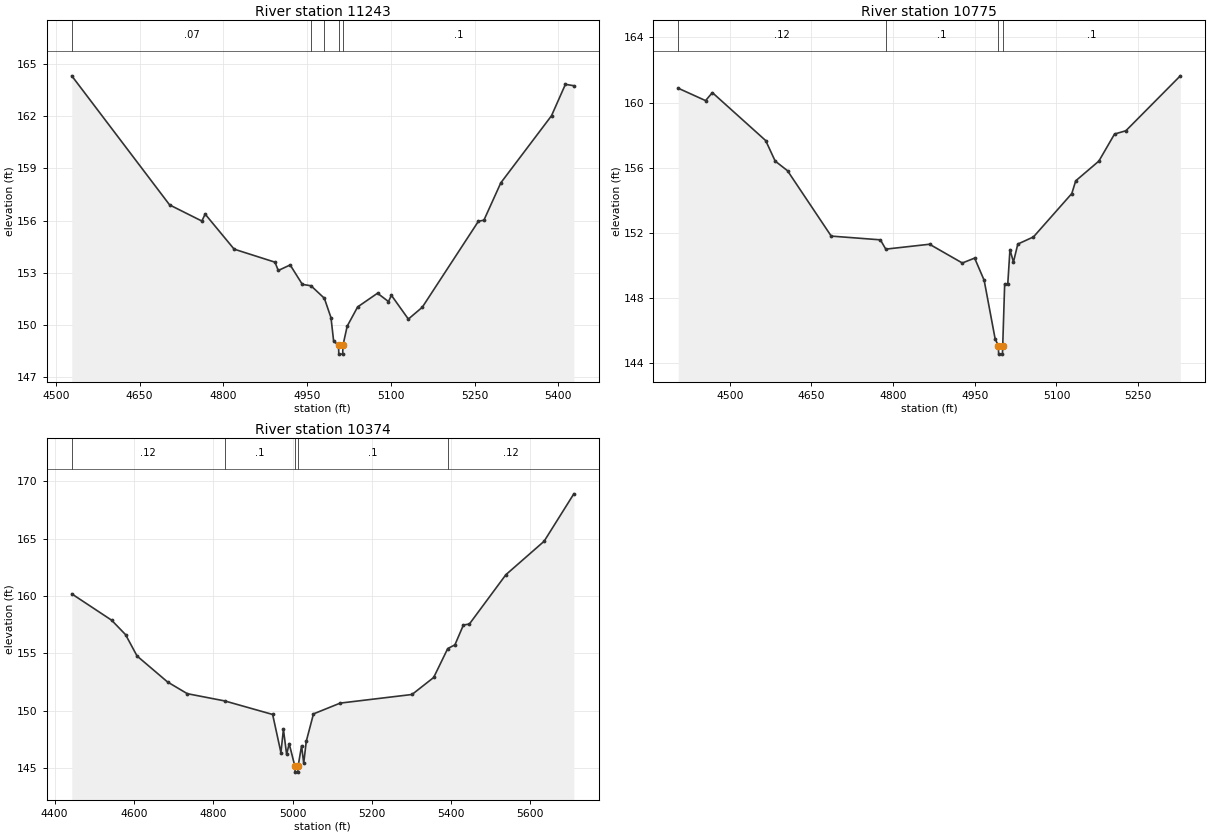
Type RM Length L Ch R = 1 ,11243   ,468,468,468
BEGIN DESCRIPTION:
TRIB TO FIFTEENMILE CREEK 18.0
END DESCRIPTION:
XS GIS Cut Line= 3
      2518674.97     13492675.04        2518925.       13492275.
      2518775.02     13491875.04
#Sta/Elev= 30
  4528.7  164.34  4703.9   156.9  4761.6  155.97  4767.5  156.37  4819.4  154.35
  4892.5   153.6  4898.4  153.12  4919.7  153.44  4941.5  152.32    4957  152.24
  4980.9  151.52  4992.8   150.4  4997.5  149.06  5006.3   148.8  5006.8   148.3
  5013.7   148.3  5014.2   148.8  5021.8  149.91  5040.5  151.02  5076.1  151.81
  5095.7  151.33    5101  151.69  5131.3  150.32  5156.2     151  5256.8  155.96
  5266.6  156.02  5296.8  158.17  5387.6  162.04  5412.5  163.85  5427.6  163.77
#Mann= 5 ,-1 , 0
  4528.7     .07       0    4957     .12       0  4980.9      .1       0
  5006.3     .05       0  5014.2      .1       0
Bank Sta=5006.3,5014.2
XS Rating Curve= 0 ,0
Exp/Cntr=0.3,0.1

Type RM Length L Ch R = 1 ,10775   ,401,401,401
BEGIN DESCRIPTION:
TRIB TO FIFTEENMILE CREEK 17.0
END DESCRIPTION:
XS GIS Cut Line= 3
        2519225.       13492625.        2519275.       13492025.
      2519075.02     13491775.03
#Sta/Elev= 30
  4405.3  160.88  4455.5  160.12    4468  160.61  4565.9  157.67  4583.4  156.41
    4606  155.82  4686.3  151.81  4776.6  151.58  4786.5  151.01  4866.9  151.31
  4927.1  150.16  4949.7  150.46  4967.2   149.1  4987.3  145.52  4993.3  145.07
  4993.8  144.57  5000.8  144.57  5001.3  145.07  5004.9  148.88  5010.6  148.88
  5014.6  150.98    5021  150.22    5029  151.32  5057.8  151.76  5128.2  154.42
  5135.4   155.2  5177.9  156.41  5206.7  158.07  5227.5  158.27  5327.5  161.64
#Mann= 4 ,-1 , 0
  4405.3     .12       0  4786.5      .1       0  4993.3     .05       0
  5001.3      .1       0
Bank Sta=4993.3,5001.3
XS Rating Curve= 0 ,0
Exp/Cntr=0.3,0.1

Type RM Length L Ch R = 1 ,10374   ,431,431,431
BEGIN DESCRIPTION:
TRIB TO FIFTEENMILE CREEK 16.0
END DESCRIPTION:
XS GIS Cut Line= 3
        2519275.       13492575.        2519625.       13492125.
        2519375.       13491475.
#Sta/Elev= 30
  4443.1  160.18  4543.5  157.89  4578.8  156.63  4607.8  154.77  4684.7  152.51
  4734.5  151.49  4828.8  150.86  4949.8  149.68  4970.7  146.36    4977  148.38
  4985.1   146.2  4991.5  147.14    5006  145.16  5006.5  144.66  5013.5  144.66
    5014  145.16  5022.8  146.96  5028.2  145.43  5034.6  147.34  5052.8  149.73
  5120.3  150.67  5301.4  151.42    5356   152.9  5391.5  155.42  5409.6  155.74
    5431  157.47    5446  157.55  5538.2  161.85  5634.6  164.76  5709.6  168.89
#Mann= 5 ,-1 , 0
  4443.1     .12       0  4828.8      .1       0    5006     .05       0
    5014      .1       0  5391.5     .12       0
Bank Sta=5006,5014
XS Rating Curve= 0 ,0
Exp/Cntr=0.3,0.1