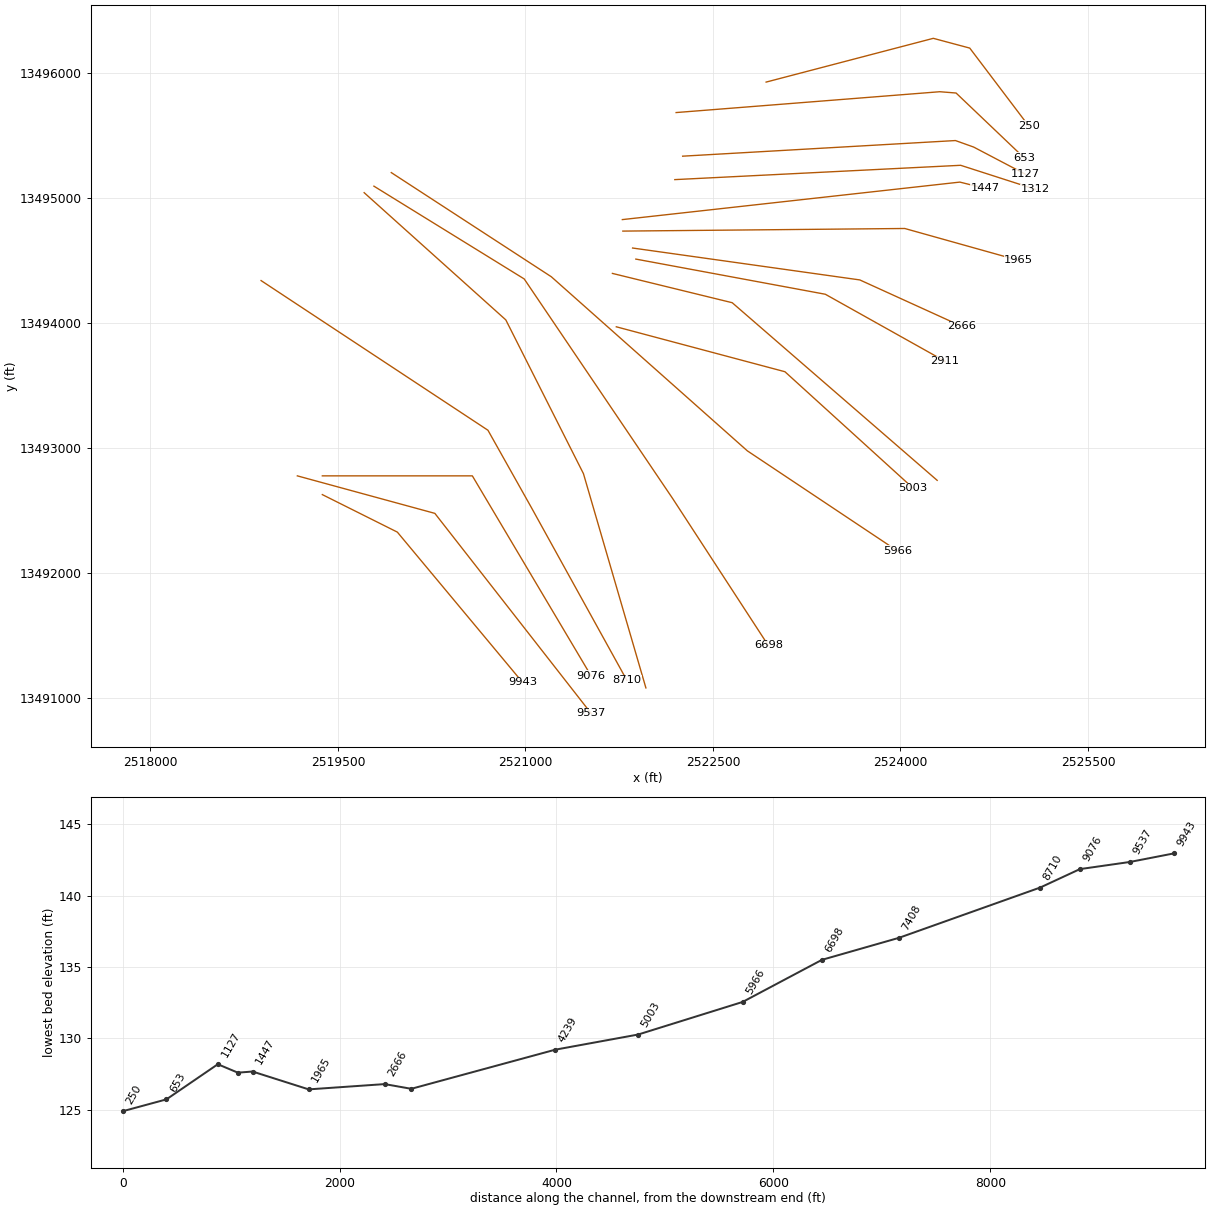
HEC-RAS study TRIB TO FIFTEENMILE CREEK.prj: TRIB TO FIFTEENMILE CREEK Base Level Engineering

--- TRIB TO FIFTEENMILE CREEK.g01 (geometry) --- (continued)

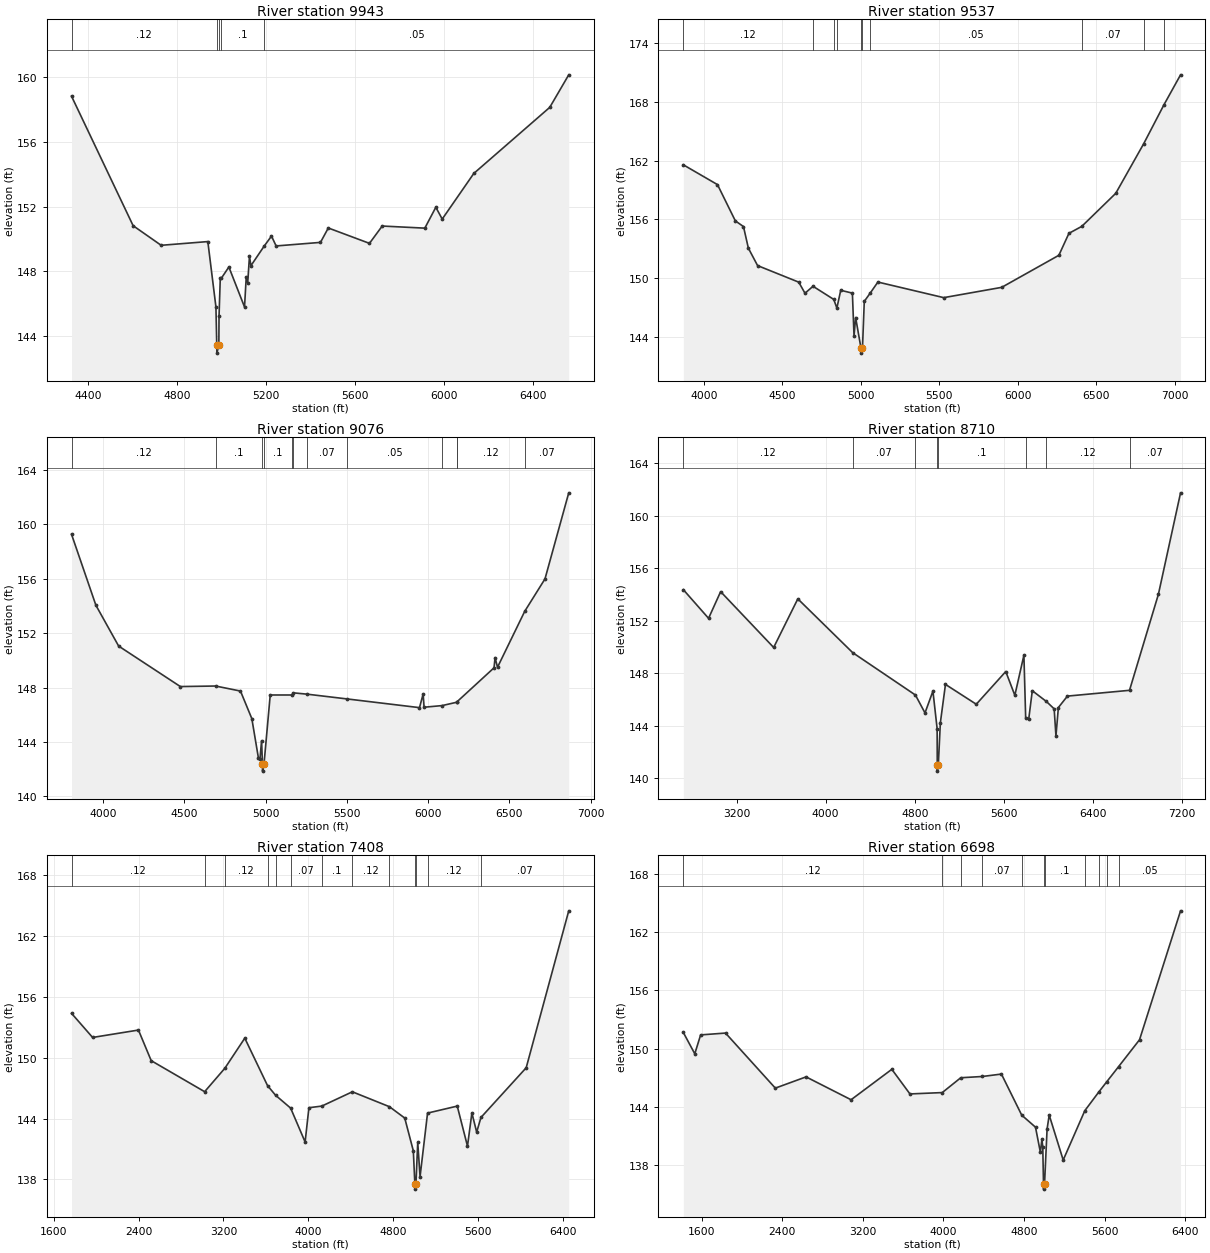
Type RM Length L Ch R = 1 ,9943    ,406,406,406
BEGIN DESCRIPTION:
TRIB TO FIFTEENMILE CREEK 15.0
END DESCRIPTION:
XS GIS Cut Line= 3
      2519374.99     13492625.01        2519975.       13492325.
      2520975.01     13491124.99
#Sta/Elev= 30
  4325.4  158.82  4602.1  150.82  4727.9  149.61  4937.5  149.84  4973.9   145.8
  4977.6  143.45  4978.1  142.95    4987  143.45  4987.8  145.23  4993.4  147.56
  4997.4  147.56    5032  148.27  5102.3   145.8  5110.1  147.67  5116.6   147.3
  5124.5  148.93    5131  148.35  5190.5  149.56  5223.4  150.18  5244.2  149.57
  5443.4  149.79  5478.5  150.68  5663.4  149.73  5720.6   150.8    5912  150.67
  5961.4  151.96  5990.1  151.23    6132  154.05    6473  158.13  6558.3  160.14
#Mann= 5 ,-1 , 0
  4325.4     .12       0  4977.6     .05       0    4987     .12       0
  4997.4      .1       0  5190.5     .05       0
Bank Sta=4977.6,4987
XS Rating Curve= 0 ,0
Exp/Cntr=0.3,0.1

Type RM Length L Ch R = 1 ,9537    ,461,461,461
BEGIN DESCRIPTION:
TRIB TO FIFTEENMILE CREEK 14.0
END DESCRIPTION:
XS GIS Cut Line= 3
        2519175.       13492775.        2520275.       13492475.
      2521525.02     13490874.98
#Sta/Elev= 30
  3867.8  161.56  4085.5  159.54  4199.5  155.84  4251.3  155.26  4282.4  153.06
  4341.2  151.28  4603.7  149.59  4643.5  148.46  4694.8  149.17  4826.9  147.83
  4846.8  146.95  4871.5  148.76  4945.8  148.47  4956.2  144.12  4966.5  145.98
  5000.7  142.85  5001.2  142.35  5010.1  142.85  5021.6  147.63  5058.8  148.46
  5108.4   149.6  5528.3  148.01  5897.9  149.06  6262.4  152.33  6326.6  154.57
  6408.5  155.28  6625.1  158.65  6803.3  163.71  6932.4  167.68  7038.4  170.74
#Mann= 10 ,-1 , 0
  3867.8     .12       0  4694.8      .1       0  4826.9     .12       0
  4846.8      .1       0  5000.7     .05       0  5010.1      .1       0
  5058.8     .05       0  6408.5     .07       0  6803.3     .05       0
  6932.4     .07       0
Bank Sta=5000.7,5010.1
XS Rating Curve= 0 ,0
Exp/Cntr=0.3,0.1

Type RM Length L Ch R = 1 ,9076    ,366,366,366
BEGIN DESCRIPTION:
TRIB TO FIFTEENMILE CREEK 13.0
END DESCRIPTION:
XS GIS Cut Line= 3
      2519375.03       13492775.        2520575.       13492775.
      2521525.02     13491174.96
#Sta/Elev= 30
    3805  159.27    3955  154.05    4095  151.05    4475  148.07  4691.6  148.11
    4845  147.74    4915  145.71    4955  142.85    4965  142.76    4975  144.09
  4980.3  142.35  4980.8  141.85  4989.7  142.35  5028.2  147.45    5163  147.45
  5169.1  147.61  5255.6  147.51  5501.4  147.16    5947  146.52  5969.5  147.52
  5975.3  146.55  6085.8  146.67  6177.6  146.92  6179.8  146.97  6405.9  149.45
  6412.2   150.2  6427.3  149.49  6595.1  153.61  6719.6  155.99  6865.8  162.32
#Mann= 12 ,-1 , 0
    3805     .12       0  4691.6      .1       0  4980.3     .05       0
  4989.7      .1       0    5163     .07       0  5169.1      .1       0
  5255.6     .07       0  5501.4     .05       0  6085.8     .12       0
  6177.6     .05       0  6179.8     .12       0  6595.1     .07       0
Bank Sta=4980.3,4989.7
XS Rating Curve= 0 ,0
Exp/Cntr=0.3,0.1

Type RM Length L Ch R = 1 ,8710    ,1302,1302,1302
BEGIN DESCRIPTION:
Mapping XS d7abceed
END DESCRIPTION:
XS GIS Cut Line= 4
      2518884.95     13494337.16      2520699.86     13493139.83
      2521047.08     13492521.77      2521810.43      13491140.8
#Sta/Elev= 30
  2722.9  154.37  2949.2  152.19  3057.6  154.22  3533.3  149.97    3750  153.67
  4241.8  149.58  4805.4  146.35  4891.1  144.99  4962.3  146.65  4999.9   143.8
  5001.2  141.06  5001.7  140.56  5010.7  141.06  5028.9  144.24  5074.8  147.16
  5351.2  145.65  5615.8  148.14  5697.2  146.33  5778.5  149.38  5794.5  144.59
    5822  144.53  5853.8  146.68  5980.2  145.86    6050   145.3    6066  143.24
  6087.8   145.4  6169.1  146.27    6726  146.71    6985  154.01    7184  161.74
#Mann= 8 ,-1 , 0
  2722.9     .12       0  4241.8     .07       0  4805.4      .1       0
  5001.2     .05       0  5010.7      .1       0  5794.5     .05       0
  5980.2     .12       0    6726     .07       0
Bank Sta=5001.2,5010.7
XS Rating Curve= 0 ,0
Exp/Cntr=0.3,0.1

Type RM Length L Ch R = 1 ,7408    ,710,710,710
BEGIN DESCRIPTION:
Mapping XS f6973493
END DESCRIPTION:
XS GIS Cut Line= 4
      2519709.58      13495040.3      2520842.75     13494022.66
      2521463.75      13492792.6      2521963.35     13491078.71
#Sta/Elev= 30
  1767.8  154.38  1966.4     152  2398.5  152.73  2518.8  149.71  3022.5  146.65
  3212.7  148.96  3400.8  151.93  3615.2  147.25  3690.8   146.3    3833  145.03
  3969.3  141.69  4005.2  145.07  4126.4  145.23  4414.6  146.64  4764.1  145.17
  4908.3  144.05  4989.2  140.82  5003.8  137.54  5004.3  137.04  5013.7  137.54
  5030.8  141.64  5052.7  138.27  5123.3  144.54  5403.2  145.23  5499.6  141.28
  5541.2  144.55  5586.3  142.66  5626.7  144.11  6052.9  149.01    6454  164.49
#Mann= 13 ,-1 , 0
  1767.8     .12       0  3022.5     .07       0  3212.7     .12       0
  3615.2     .07       0  3690.8     .12       0    3833     .07       0
  4126.4      .1       0  4414.6     .12       0  4764.1      .1       0
  5003.8     .05       0  5013.7      .1       0  5123.3     .12       0
  5626.7     .07       0
Bank Sta=5003.8,5013.7
XS Rating Curve= 0 ,0
Exp/Cntr=0.3,0.1

Type RM Length L Ch R = 1 ,6698    ,732,732,732
BEGIN DESCRIPTION:
Mapping XS d3e80f47
END DESCRIPTION:
XS GIS Cut Line= 4
      2519787.69     13495092.39      2520989.96      13494350.2
      2522179.03     13492591.22      2522942.15     13491418.78
#Sta/Elev= 30
    1419  151.66  1532.6  149.46  1590.6  151.41  1837.7   151.6    2332  145.92
    2637  147.08  3083.8  144.72  3488.3  147.86  3668.1  145.32  3988.8  145.46
  4172.5  146.99  4386.6  147.12  4576.1  147.37  4777.7  143.13  4914.3  141.89
  4962.7   139.3  4977.8  140.65  4986.4  139.87  4993.9     136  4994.4   135.5
  5003.9     136  5029.2  141.69  5050.3  143.14  5189.2   138.5  5403.6  143.59
  5541.8  145.51  5623.3   146.6  5738.5  148.13  5946.8  150.91    6354  164.21
#Mann= 11 ,-1 , 0
    1419     .12       0  3988.8     .07       0  4172.5    .035       0
  4386.6     .07       0  4777.7      .1       0  4993.9     .05       0
  5003.9      .1       0  5403.6     .07       0  5541.8      .1       0
  5623.3     .07       0  5738.5     .05       0
Bank Sta=4993.9,5003.9
XS Rating Curve= 0 ,0
Exp/Cntr=0.3,0.1

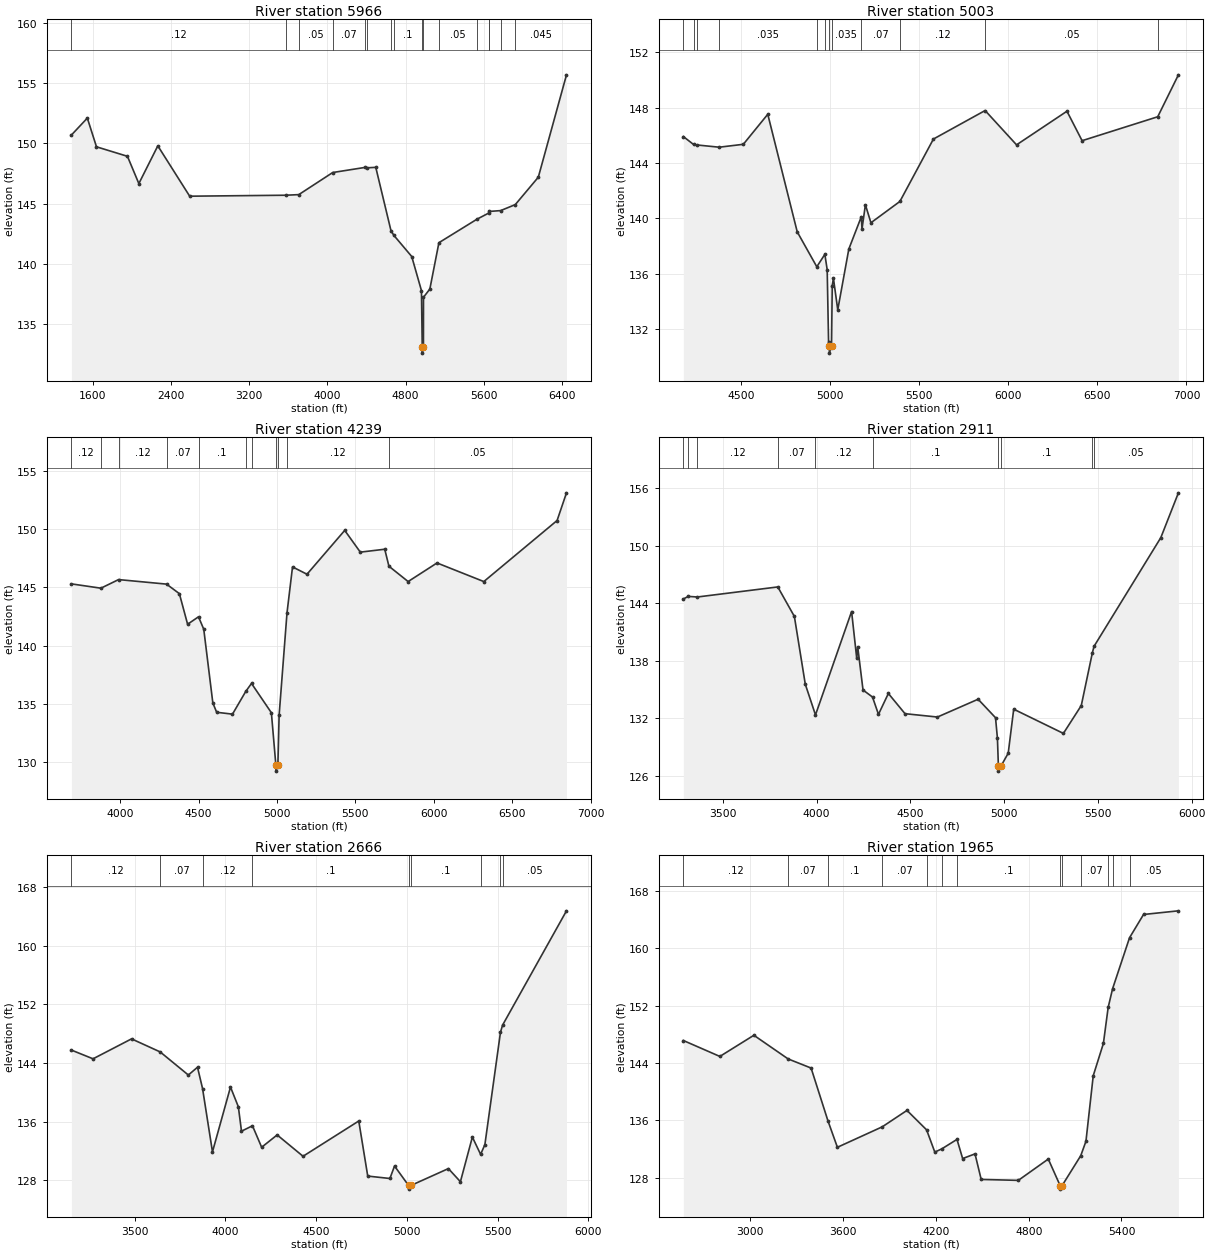
Type RM Length L Ch R = 1 ,5966    ,963,963,963
BEGIN DESCRIPTION:
TRIB TO FIFTEENMILE CREEK 9.0
END DESCRIPTION:
XS GIS Cut Line= 4
      2519926.57      13495200.9      2521206.98     13494367.56
        2522775.       13492975.      2523975.04     13492174.97
#Sta/Elev= 30
  1379.8   150.7  1542.7  152.11  1636.3  149.72  1953.2  148.93  2069.9  146.66
  2264.1   149.8  2590.2  145.61    3572  145.69  3706.8  145.74  4054.2  147.58
  4381.1     148  4400.2  147.97  4494.9  148.01  4650.8  142.73  4681.1  142.34
  4862.9  140.59  4962.4  137.75  4970.5  133.05    4971  132.55  4982.7  133.05
  4983.3   137.2  5048.2  137.88  5141.1  141.74  5531.5   143.7  5651.9  144.21
  5652.8  144.34  5772.3  144.41  5922.8  144.91  6158.4  147.19  6446.9  155.71
#Mann= 16 ,-1 , 0
  1379.8     .12       0    3572     .07       0  3706.8     .05       0
  4054.2     .07       0  4381.1      .1       0  4400.2     .07       0
  4650.8     .12       0  4681.1      .1       0  4970.5     .05       0
  4982.7      .1       0  5141.1     .05       0  5531.5    .035       0
  5651.9     .12       0  5652.8    .035       0  5772.3     .12       0
  5922.8    .045       0
Bank Sta=4970.5,4982.7
XS Rating Curve= 0 ,0
Exp/Cntr=0.3,0.1

Type RM Length L Ch R = 1 ,5003    ,764,764,764
BEGIN DESCRIPTION:
Mapping XS d08e36d8
END DESCRIPTION:
XS GIS Cut Line= 3
      2521726.69      13493967.4      2523075.67     13493608.02
      2524100.85     13492676.51
#Sta/Elev= 30
  4173.9  145.92    4231  145.35  4251.3  145.31  4375.5  145.15  4510.9  145.36
  4648.2  147.53  4813.8  139.03  4923.7  136.51  4968.9  137.41    4982   136.3
  4989.7   131.1  4993.9  130.77  4994.4  130.27  5006.3  130.77  5010.4  135.15
    5017  135.68  5041.4   133.4  5103.5  137.79  5173.9  140.13  5177.5  139.23
  5196.7  140.99  5227.7  139.69  5390.4  141.23  5578.8  145.74  5869.2   147.8
  6045.8  145.32  6328.9  147.75    6414  145.62  6838.9  147.35  6955.1  150.38
#Mann= 12 ,-1 , 0
  4173.9     .05       0    4231     .07       0  4251.3     .05       0
  4375.5    .035       0  4923.7      .1       0  4968.9    .035       0
  4993.9    .035       0  5006.3    .035       0  5173.9     .07       0
  5390.4     .12       0  5869.2     .05       0  6838.9    .045       0
Bank Sta=4993.9,5006.3
XS Rating Curve= 0 ,0
Exp/Cntr=0.3,0.1

Type RM Length L Ch R = 1 ,4239    ,1328,1328,1328
BEGIN DESCRIPTION:
Mapping XS 58801156
END DESCRIPTION:
XS GIS Cut Line= 3
      2521695.46     13494394.47      2522653.79      13494160.1
      2524293.36     13492739.14
#Sta/Elev= 30
  3689.8  145.31  3877.8  144.94  3990.5  145.68  4296.2  145.29    4378  144.47
  4430.5  141.84    4500  142.48  4533.5  141.41  4591.4  135.07  4615.8  134.27
  4716.7  134.11  4801.1  136.06  4837.9  136.75  4964.6  134.23  4993.3  129.71
  4993.8  129.21    5006  129.71  5013.9     134  5064.2  142.82  5099.4  146.77
  5191.6  146.14  5432.2  149.91  5531.5  148.04  5687.3  148.29  5713.9  146.83
  5836.4  145.51  6020.6  147.11  6318.9  145.51  6786.1  150.76    6846  153.14
#Mann= 11 ,-1 , 0
  3689.8     .12       0  3877.8     .07       0  3990.5     .12       0
  4296.2     .07       0    4500      .1       0  4801.1     .12       0
  4837.9      .1       0  4993.3     .05       0    5006      .1       0
  5064.2     .12       0  5713.9     .05       0
Bank Sta=4993.3,5006
XS Rating Curve= 0 ,0
Exp/Cntr=0.3,0.1

Type RM Length L Ch R = 1 ,2911    ,245,245,245
BEGIN DESCRIPTION:
Mapping XS 9781e59c
END DESCRIPTION:
XS GIS Cut Line= 3
      2521882.98     13494509.05      2523398.58     13494227.81
      2524356.88     13493691.37
#Sta/Elev= 30
  3289.8  144.45  3315.9  144.72  3364.7  144.66  3793.4  145.71  3881.8  142.63
    3940  135.55  3994.4  132.34  4186.9  143.14  4214.3  138.25  4219.4  139.47
  4247.9  134.94  4298.4  134.21  4330.2   132.4    4383  134.58  4471.7  132.47
  4644.6  132.12  4861.5  133.98  4954.3  132.05  4964.5   129.9  4969.7  126.97
  4970.2  126.47  4982.6  126.97    5022  128.34  5051.3  132.94  5316.2  130.41
  5411.6  133.32  5470.8  138.84  5479.7  139.51  5835.7  150.86  5929.5  155.54
#Mann= 10 ,-1 , 0
  3289.8     .12       0  3315.9     .07       0  3364.7     .12       0
  3793.4     .07       0  3994.4     .12       0  4298.4      .1       0
  4969.7     .05       0  4982.6      .1       0  5470.8     .12       0
  5479.7     .05       0
Bank Sta=4969.7,4982.6
XS Rating Curve= 0 ,0
Exp/Cntr=0.3,0.1

Type RM Length L Ch R = 1 ,2666    ,701,701,701
BEGIN DESCRIPTION:
Mapping XS f81f06d4
END DESCRIPTION:
XS GIS Cut Line= 3
      2521856.93      13494597.6      2523674.62     13494342.39
      2524487.11     13493972.61
#Sta/Elev= 30
  3151.1  145.76  3270.3  144.57  3482.4  147.29  3640.2  145.51  3795.4  142.36
  3845.9  143.42  3873.7  140.52  3928.4  131.88  4027.7  140.72    4071  138.03
  4088.3   134.7  4148.8  135.44  4199.4  132.51  4284.9  134.19  4427.5  131.28
  4734.6  136.09    4784  128.58  4906.2  128.25  4931.7  129.95    5009   127.3
  5009.5   126.8    5022   127.3  5228.5   129.6  5294.7  127.81  5360.6   133.9
    5406  131.54  5429.5  132.86  5515.4  148.18    5527  149.16  5879.3  164.75
#Mann= 9 ,-1 , 0
  3151.1     .12       0  3640.2     .07       0  3873.7     .12       0
  4148.8      .1       0    5009     .05       0    5022      .1       0
    5406     .05       0  5515.4     .07       0    5527     .05       0
Bank Sta=5009,5022
XS Rating Curve= 0 ,0
Exp/Cntr=0.3,0.1

Type RM Length L Ch R = 1 ,1965    ,518,518,518
BEGIN DESCRIPTION:
Mapping XS b21d0382
END DESCRIPTION:
XS GIS Cut Line= 3
      2521778.78     13494733.02        2524034.     13494753.85
      2524945.43     13494498.65
#Sta/Elev= 30
  2566.3  147.14  2802.5  144.92  3022.5  147.87  3244.2  144.57  3392.6   143.3
  3501.6  135.94  3562.6  132.26  3852.6  135.11  4012.6   137.4  4139.5  134.69
  4192.6  131.59  4237.8  132.04  4336.1  133.36  4372.6  130.69  4452.6  131.34
  4492.6  127.78  4732.6  127.65  4926.5  130.62    5003  126.93  5003.5  126.43
  5016.1  126.93  5136.5  131.09  5170.1   133.1  5217.3  142.24  5282.9  146.73
  5313.7  151.74  5342.3  154.35    5452  161.46  5542.5   164.7  5768.1  165.21
#Mann= 13 ,-1 , 0
  2566.3     .12       0  3244.2     .07       0  3501.6      .1       0
  3852.6     .07       0  4139.5     .05       0  4237.8     .07       0
  4336.1      .1       0    5003     .05       0  5016.1      .1       0
  5136.5     .07       0  5313.7      .1       0  5342.3     .07       0
    5452     .05       0
Bank Sta=5003,5016.1
XS Rating Curve= 0 ,0
Exp/Cntr=0.3,0.1

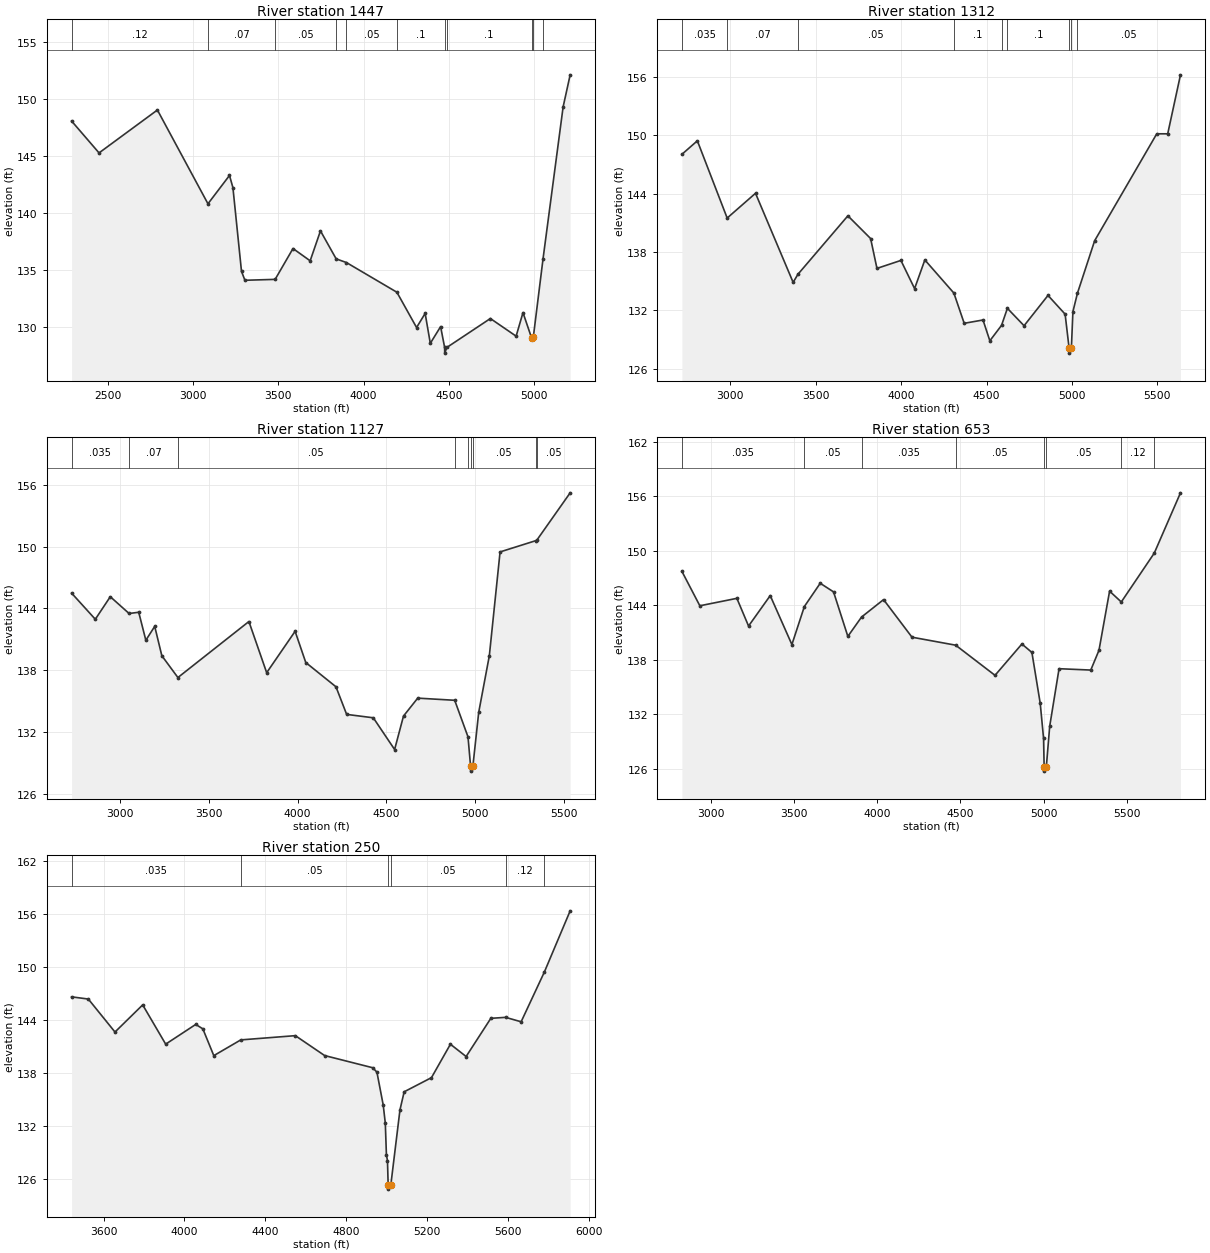
Type RM Length L Ch R = 1 ,1447    ,135,135,135
BEGIN DESCRIPTION:
TRIB TO FIFTEENMILE CREEK 3.0
END DESCRIPTION:
XS GIS Cut Line= 3
      2521775.05     13494825.01        2524475.       13495125.
      2524674.98     13495075.01
#Sta/Elev= 30
  2288.3  148.07  2449.2  145.27  2791.3  149.04  3087.7   140.8  3213.9  143.29
    3234  142.22  3284.3  134.86  3304.5  134.08  3481.5  134.16  3586.2  136.87
  3686.8  135.79  3747.2  138.42  3839.3  135.96  3899.2  135.64  4195.2  133.03
  4310.6  129.93  4360.9  131.17  4391.1  128.54  4451.5  130.01  4475.1  128.18
  4475.6  127.68  4488.2  128.18  4743.3  130.72  4894.2  129.17  4934.4  131.24
  4984.7  129.02  4994.8  129.06  5052.1  135.98  5169.8  149.32    5211  152.13
#Mann= 11 ,-1 , 0
  2288.3     .12       0  3087.7     .07       0  3481.5     .05       0
  3839.3     .07       0  3899.2     .05       0  4195.2      .1       0
  4475.1     .07       0  4488.2      .1       0  4984.7     .05       0
  4994.8     .07       0  5052.1     .12       0
Bank Sta=4984.7,4994.8
XS Rating Curve= 0 ,0
Exp/Cntr=0.3,0.1

Type RM Length L Ch R = 1 ,1312    ,185,185,185
BEGIN DESCRIPTION:
Mapping XS f819001c
END DESCRIPTION:
XS GIS Cut Line= 3
      2522194.74     13495144.82      2524481.19      13495259.4
      2525080.04     13495066.73
#Sta/Elev= 30
  2716.9  148.06  2807.3  149.45  2981.8   141.5  3147.7  144.05    3368  134.88
  3395.8  135.71  3688.4  141.73  3821.5  139.39  3858.6  136.32  3998.8  137.14
  4078.9  134.24  4138.9  137.19  4308.9  133.78  4369.2  130.67  4479.4  131.01
  4519.4  128.87  4587.9  130.46  4622.1  132.21  4719.7  130.42  4859.8  133.54
    4960  131.61  4983.4   128.1  4983.9   127.6  4996.6   128.1  5005.6  131.87
  5032.4  133.78  5132.9  139.17  5496.4  150.17  5560.5  150.17  5635.3  156.24
#Mann= 9 ,-1 , 0
  2716.9    .035       0  2981.8     .07       0  3395.8     .05       0
  4308.9      .1       0  4587.9     .05       0  4622.1      .1       0
  4983.4     .05       0  4996.6      .1       0  5032.4     .05       0
Bank Sta=4983.4,4996.6
XS Rating Curve= 0 ,0
Exp/Cntr=0.3,0.1

Type RM Length L Ch R = 1 ,1127    ,474,474,474
BEGIN DESCRIPTION:
Mapping XS b55dfa34
END DESCRIPTION:
XS GIS Cut Line= 4
      2522257.23     13495332.32      2524439.53     13495457.32
      2524585.36     13495405.23      2525001.03     13495187.01
#Sta/Elev= 30
  2726.5  145.48  2860.2  142.94  2944.6  145.13  3050.6   143.5  3104.9  143.62
    3145   140.9    3195  142.25  3235.1   139.4  3325.7  137.28  3725.9  142.72
  3826.1  137.75  3986.3  141.77  4046.4  138.74  4216.7  136.38  4276.8   133.7
  4427.1  133.37  4547.2  130.29  4597.3  133.54  4677.5  135.28  4885.9  135.07
  4960.8  131.52  4975.3  128.69  4975.8  128.19  4988.5  128.69  5021.2   133.9
  5081.1   139.4  5141.6  149.48  5342.2  150.57  5347.4  150.59  5536.7  155.22
#Mann= 9 ,-1 , 0
  2726.5    .035       0  3050.6     .07       0  3325.7     .05       0
  4885.9      .1       0  4960.8     .05       0  4975.3     .05       0
  4988.5     .05       0  5342.2     .12       0  5347.4     .05       0
Bank Sta=4975.3,4988.5
XS Rating Curve= 0 ,0
Exp/Cntr=0.3,0.1

Type RM Length L Ch R = 1 ,653     ,403,403,403
BEGIN DESCRIPTION:
Mapping XS f338428a
END DESCRIPTION:
XS GIS Cut Line= 4
      2522205.19     13495681.28      2524314.53     13495847.94
      2524444.74     13495837.52      2524990.78     13495317.48
#Sta/Elev= 30
  2823.8  147.73  2931.7  143.94  3154.6  144.76  3224.9  141.71  3355.3  145.06
  3485.7  139.67  3560.8  143.86  3656.2  146.42  3736.4  145.47  3822.5  140.57
  3904.9   142.7  4037.4  144.62  4208.5  140.48  4471.4   139.6  4708.2  136.28
    4870  139.73  4930.2   138.8  4980.3  133.19  5000.4  129.33  5003.8  126.23
  5004.3  125.73  5017.1  126.23  5037.4  130.69  5093.6  137.01  5284.5  136.86
  5333.9  139.04  5397.7  145.55  5468.2  144.36  5666.6  149.74  5824.4  156.38
#Mann= 8 ,-1 , 0
  2823.8    .035       0  3560.8     .05       0  3904.9    .035       0
  4471.4     .05       0  5003.8     .05       0  5017.1     .05       0
  5468.2     .12       0  5666.6     .05       0
Bank Sta=5003.8,5017.1
XS Rating Curve= 0 ,0
Exp/Cntr=0.3,0.1

Type RM Length L Ch R = 1 ,250     ,0,0,0
BEGIN DESCRIPTION:
TRIB TO FIFTEENMILE CREEK 1.0
END DESCRIPTION:
XS GIS Cut Line= 4
      2522925.04     13495925.01      2524262.44     13496275.02
      2524554.11      13496196.9      2525025.03     13495574.97
#Sta/Elev= 30
  3442.2  146.65  3524.9   146.4  3656.7  142.67  3793.6  145.74  3907.3   141.3
  4055.8  143.53    4091  143.03  4145.1     140  4278.5  141.78  4548.2  142.26
  4692.9  140.01  4930.8  138.63  4951.5  138.13  4982.6  134.41  4992.9  132.36
  4998.4  128.78  5003.6  128.13    5007   125.4  5007.5   124.9  5020.3   125.4
  5065.4  133.87  5086.1  135.91  5221.1  137.51  5314.7  141.29  5392.4   139.9
  5514.5  144.22  5587.4  144.33  5664.3  143.83  5779.2  149.46  5906.7  156.38
#Mann= 6 ,-1 , 0
  3442.2    .035       0  4278.5     .05       0    5007     .05       0
  5020.3     .05       0  5587.4     .12       0  5779.2     .05       0
Bank Sta=5007,5020.3
XS Rating Curve= 0 ,0
Exp/Cntr=0.3,0.1

Chan Stop Cuts=-1
Use User Specified Reach Order=0
Composite Channel Slope=5