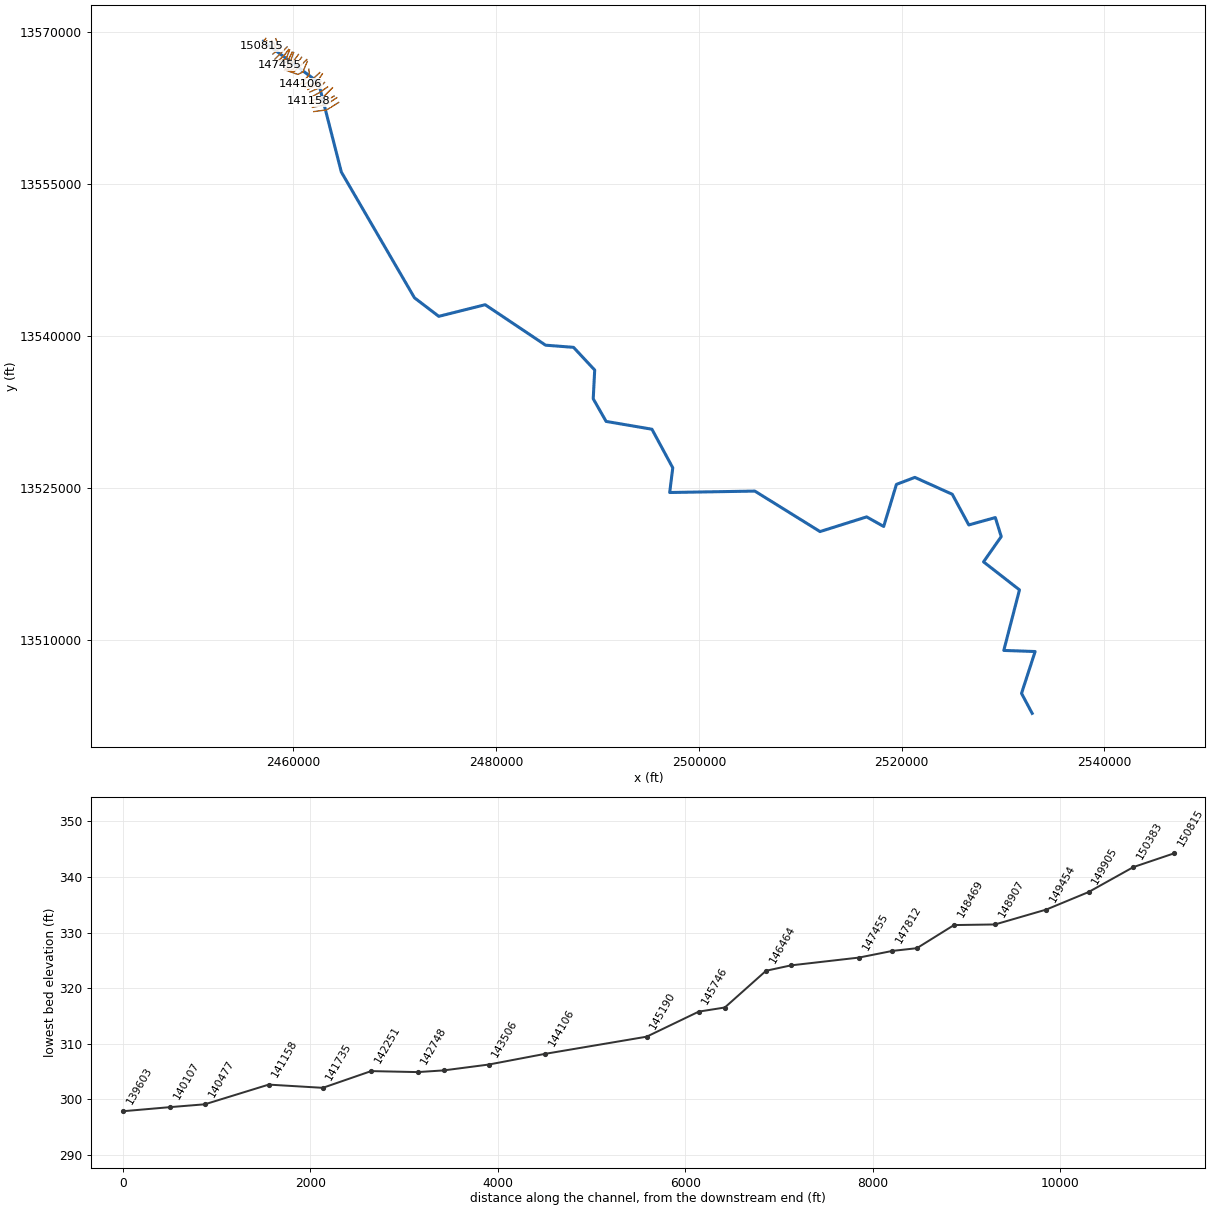
--- TWELVEMILE CREEK.prj (project) ---

Proj Title=TWELVEMILE CREEK Base Level Engineering
Current Plan=p01
Default Exp/Contr=0.3,0.1
English Units
Geom File=g01
Flow File=f01
Plan File=p01
Y Axis Title=Elevation
X Axis Title(PF)=Main Channel Distance
X Axis Title(XS)=Station
BEGIN DESCRIPTION:
TWELVEMILE CREEK
END DESCRIPTION:
DSS Export Rating Curves= 0
DSS Export Rating Curve Sorted= 0
DSS Export Volume Flow Curves= 0
DXF OffsetX= 0
DXF OffsetY= 0
DXF ScaleX= 1
DXF ScaleY= 10

--- TWELVEMILE CREEK.p01 (plan) ---

Plan Title=Multiple Run
Short Identifier=Multiple
Geom File=g01
Flow File=f01
Subcritical Flow
K Sum by GR= 0
Std Step Tol= 0.01
Critical Tol= 0.01
Num of Std Step Trials= 20
Max Error Tol= 0.3
Flow Tol Ratio= 0.001
Split Flow NTrial= 30
Split Flow Tol= 0.02
Split Flow Ratio= 0.02
Log Output Level= 0
Friction Slope Method= 1
Unsteady Friction Slope Method= 2
Unsteady Bridges Friction Slope Method= 1
Parabolic Critical Depth
Global Vel Dist=  1 , 1 , 1
Global Log Level= 0
CheckData=True
Encroach Param= -1, 0, 0, 0
BEGIN DESCRIPTION:
Multiple Run
END DESCRIPTION:

--- TWELVEMILE CREEK.f01 (steady flow) ---

Flow Title=Multiple
Number of Profiles=7
Profile Names=10-year,25-year,50-year,1pct_min,100-year,1pct_plu,500-year
River Rch & RM= TWELVEMILE CREEK,Reach-1,150815
     319     494     645     410     818    1631    1297
River Rch & RM= TWELVEMILE CREEK,Reach-1,148469
     716    1166    1577    1033    2061    4112    3486
River Rch & RM= TWELVEMILE CREEK,Reach-1,147455
     880    1450    1975    1301    2596    5181    4450
River Rch & RM= TWELVEMILE CREEK,Reach-1,144106
    1390    2349    3255    2179    4348    8675    7694
River Rch & RM= TWELVEMILE CREEK,Reach-1,143506
    1773    3025    4216    2837    5660   11293   10120
River Rch & RM= TWELVEMILE CREEK,Reach-1,140477
    1864    3181    4436    2985    5955   11883   10649
River Rch & RM= TWELVEMILE CREEK,Reach-1,137167
    1933    3302    4607    3101    6188   12346   11072
River Rch & RM= TWELVEMILE CREEK,Reach-1,136592
    2054    3516    4912    3310    6604   13177   11844
River Rch & RM= TWELVEMILE CREEK,Reach-1,134883
    2164    3711    5190    3500    6983   13934   12546
River Rch & RM= TWELVEMILE CREEK,Reach-1,133835
    2226    3813    5330    3591    7166   14298   12852
River Rch & RM= TWELVEMILE CREEK,Reach-1,128551
    2227    3814    5329    3590    7162   14290   12836
River Rch & RM= TWELVEMILE CREEK,Reach-1,127632
    2344    4021    5627    3795    7571   15107   13603
River Rch & RM= TWELVEMILE CREEK,Reach-1,127304
    2422    4159    5822    3927    7836   15635   14086
River Rch & RM= TWELVEMILE CREEK,Reach-1,124311
    3552    6175    8713    5915   11802   23548   21461
River Rch & RM= TWELVEMILE CREEK,Reach-1,118659
    3629    6310    8907    6047   12066   24074   21947
River Rch & RM= TWELVEMILE CREEK,Reach-1,117253
    3756    6534    9226    6265   12501   24942   22747
River Rch & RM= TWELVEMILE CREEK,Reach-1,115663
    3905    6794    9593    6514   12998   25934   23647
River Rch & RM= TWELVEMILE CREEK,Reach-1,112500
    3928    6829    9636    6539   13047   26032   23702
River Rch & RM= TWELVEMILE CREEK,Reach-1,109919
    3994    6944    9799    6649   13266   26468   24095
River Rch & RM= TWELVEMILE CREEK,Reach-1,107808
    3977    6909    9744    6608   13184   26306   23921
River Rch & RM= TWELVEMILE CREEK,Reach-1,105996
    5780   10133   14386    9813   19579   39065   35918
River Rch & RM= TWELVEMILE CREEK,Reach-1,102434
    5612    9856   14006    9562   19079   38068   35079
River Rch & RM= TWELVEMILE CREEK,Reach-1,101754
    5892   10314   14626    9964   19881   39667   36378
River Rch & RM= TWELVEMILE CREEK,Reach-1,100039
    6000   10494   14873   10126   20204   40312   36921
River Rch & RM= TWELVEMILE CREEK,Reach-1,96460
    6386   11187   15873   10817   21583   43063   39512
River Rch & RM= TWELVEMILE CREEK,Reach-1,88542
    6527   11436   16230   11062   22071   44038   40417
River Rch & RM= TWELVEMILE CREEK,Reach-1,85984
    6603   11561   16397   11168   22284   44462   40753
River Rch & RM= TWELVEMILE CREEK,Reach-1,83209
    7136   12517   17777   12122   24186   48257   44327
River Rch & RM= TWELVEMILE CREEK,Reach-1,79996
    7105   12454   17678   12048   24039   47965   44014
River Rch & RM= TWELVEMILE CREEK,Reach-1,78039
    7257   12729   18077   12325   24592   49068   45063
River Rch & RM= TWELVEMILE CREEK,Reach-1,76972
    7284   12761   18108   12335   24612   49107   45017
River Rch & RM= TWELVEMILE CREEK,Reach-1,72609
    7364   12896   18293   12457   24855   49592   45428
River Rch & RM= TWELVEMILE CREEK,Reach-1,67769
    7330   12824   18181   12373   24687   49256   45064
River Rch & RM= TWELVEMILE CREEK,Reach-1,66811
    7578   13269   18821   12814   25568   51015   46713
River Rch & RM= TWELVEMILE CREEK,Reach-1,63586
    7599   13300   18860   12837   25612   51103   46764
River Rch & RM= TWELVEMILE CREEK,Reach-1,61614
    7958   13904   19697   13394   26724   53322   48679
River Rch & RM= TWELVEMILE CREEK,Reach-1,59308
    8002   13973   19787   13449   26834   53541   48835
River Rch & RM= TWELVEMILE CREEK,Reach-1,55440
    8067   14090   19957   13566   27068   54008   49277
River Rch & RM= TWELVEMILE CREEK,Reach-1,54682
    8097   14139   20022   13608   27151   54174   49408
River Rch & RM= TWELVEMILE CREEK,Reach-1,52336
    8105   14148   20032   13613   27161   54192   49406
River Rch & RM= TWELVEMILE CREEK,Reach-1,49320
    8126   14183   20078   13642   27219   54308   49496
River Rch & RM= TWELVEMILE CREEK,Reach-1,47726
    8402   14669   20772   14115   28164   56194   51229
River Rch & RM= TWELVEMILE CREEK,Reach-1,41404
    8449   14750   20886   14193   28318   56503   51508
River Rch & RM= TWELVEMILE CREEK,Reach-1,40276
   12928   22813   32552   22278   44451   88690   81964
River Rch & RM= TWELVEMILE CREEK,Reach-1,39263
   12987   22899   32659   22339   44573   88934   82099
River Rch & RM= TWELVEMILE CREEK,Reach-1,35637
   12985   22881   32619   22301   44497   88784   81883
River Rch & RM= TWELVEMILE CREEK,Reach-1,32105
   13052   22992   32770   22399   44691   89171   82198
River Rch & RM= TWELVEMILE CREEK,Reach-1,28039
   13229   23281   33162   22652   45198   90181   83015
River Rch & RM= TWELVEMILE CREEK,Reach-1,22240
   13181   23183   33008   22536   44966   89719   82514
River Rch & RM= TWELVEMILE CREEK,Reach-1,18181
   13996   24580   34971   23859   47605   94984   87184
River Rch & RM= TWELVEMILE CREEK,Reach-1,14427
   13648   24002   34172   23328   46546   92872   85386
River Rch & RM= TWELVEMILE CREEK,Reach-1,11540
   14069   24687   35101   23932   47750   95274   87332
River Rch & RM= TWELVEMILE CREEK,Reach-1,7630
   14103   24733   35154   23958   47803   95379   87358
River Rch & RM= TWELVEMILE CREEK,Reach-1,2420
   13916   24456   34803   23747   47381   94538   86825
Boundary for River Rch & Prof#=TWELVEMILE CREEK,Reach-1,1
Up Type=0
Dn Type=3
Dn Slope=0.001
Boundary for River Rch & Prof#=TWELVEMILE CREEK,Reach-1,2
Up Type=0
Dn Type=3
Dn Slope=0.001
Boundary for River Rch & Prof#=TWELVEMILE CREEK,Reach-1,3
Up Type=0
Dn Type=3
Dn Slope=0.001
Boundary for River Rch & Prof#=TWELVEMILE CREEK,Reach-1,4
Up Type=0
Dn Type=3
Dn Slope=0.001
Boundary for River Rch & Prof#=TWELVEMILE CREEK,Reach-1,5
Up Type=0
Dn Type=3
Dn Slope=0.001
Boundary for River Rch & Prof#=TWELVEMILE CREEK,Reach-1,6
Up Type=0
Dn Type=3
Dn Slope=0.001
Boundary for River Rch & Prof#=TWELVEMILE CREEK,Reach-1,7
Up Type=0
Dn Type=3
Dn Slope=0.001

--- TWELVEMILE CREEK.g01 (geometry) ---

Geom Title=Existing Conditions
Program Version=4.10

River Reach=TWELVEMILE CREEK,Reach-1
Reach XY= 30
        2457025.       13569075.      2462469.17      13565027.3
      2464728.54     13556176.47      2471941.64     13543758.32
      2474340.16     13541925.36      2478919.06     13543072.74
      2484876.55     13539078.75       2487634.7     13538864.23
      2489721.46     13536623.54       2489576.2      13533785.5
      2490847.86     13531551.43      2495366.86     13530781.06
      2497422.94     13526969.14      2497118.54     13524532.75
      2505519.06     13524672.74        2511950.     13520674.59
      2516545.03     13522124.94      2518227.45     13521180.47
      2519485.96       13525335.      2521304.97     13526024.93
      2524991.69     13524358.39      2526622.57     13521330.52
      2529242.05     13522058.51      2529822.94     13520180.85
      2528076.22      13517685.5      2531622.76     13514919.07
      2530075.39     13508940.16      2533166.04     13508831.71
      2531824.71     13504700.12        2532875.       13502725.

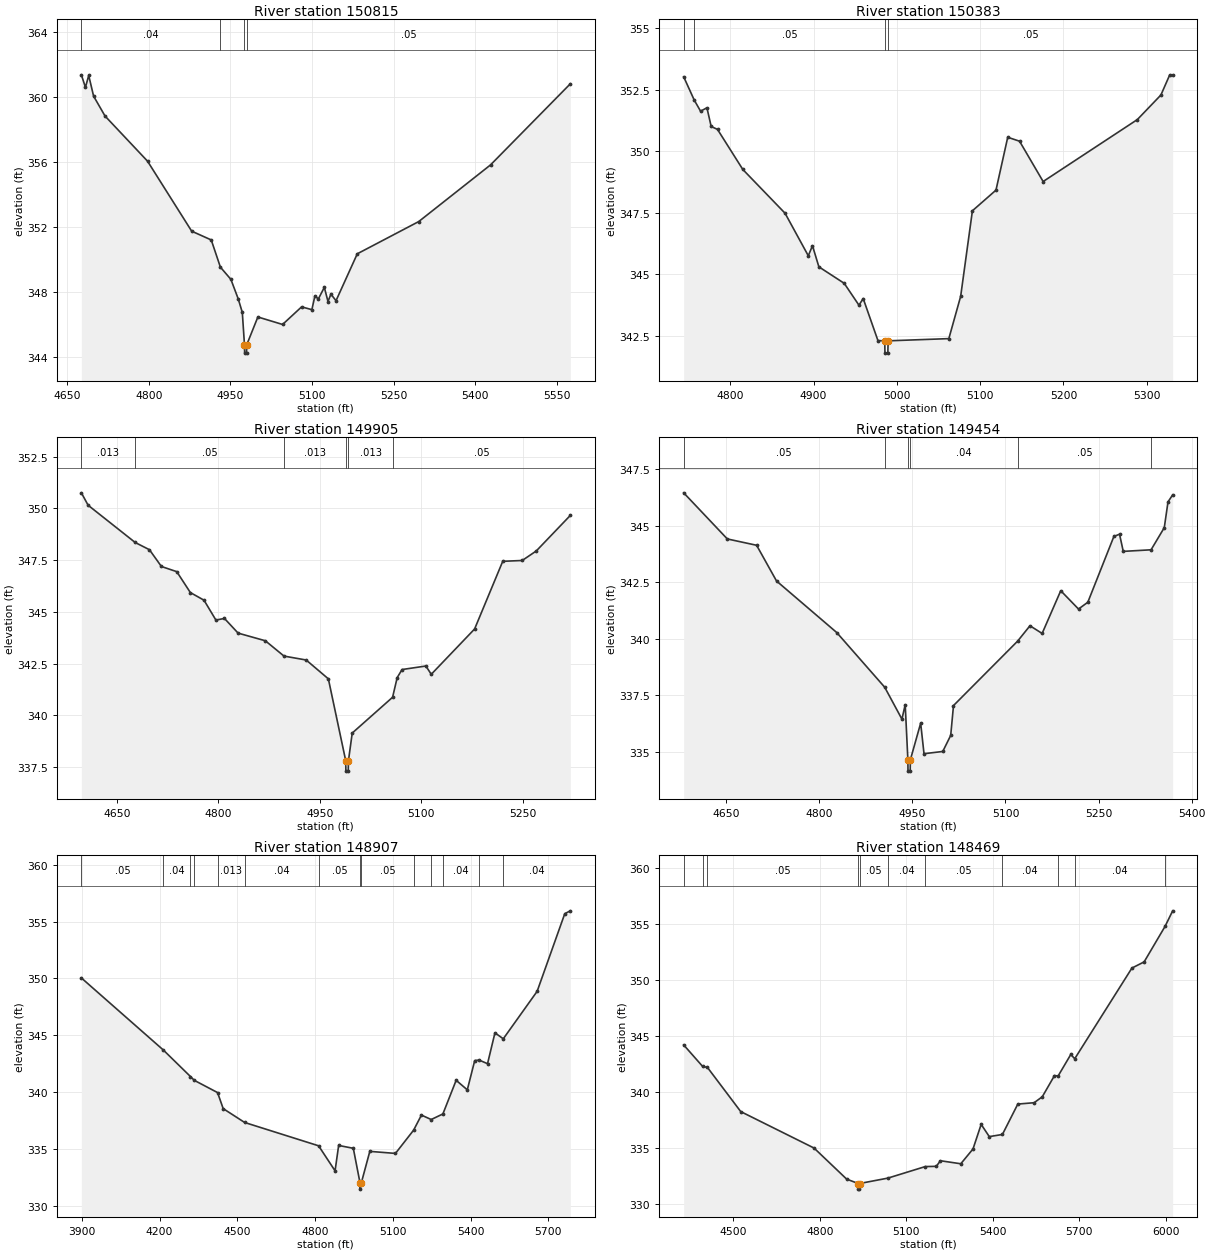
Type RM Length L Ch R = 1 ,150815  ,432,432,432
BEGIN DESCRIPTION:
COTTONWOOD CREEK 55.0
END DESCRIPTION:
XS GIS Cut Line= 3
      2457274.98     13569374.97        2457075.       13569075.
      2456875.01     13568575.03
#Sta/Elev= 30
  4675.9  361.34  4683.4  360.57  4689.4   361.3  4698.4  360.03  4719.4  358.81
  4797.5  356.04  4878.7  351.74  4914.7   351.2  4931.5  349.53  4950.8  348.78
  4964.3  347.58  4971.8  346.75  4975.8  344.75  4976.1  344.25  4979.6  344.25
  4979.8  344.75  5000.4  346.47  5045.8  346.01  5080.8  347.09  5099.7  346.92
  5105.1  347.74  5111.8  347.59  5122.6  348.29  5129.3  347.42  5134.7  347.87
  5144.1  347.47  5183.2  350.35  5296.2  352.33  5428.2  355.81  5574.9  360.79
#Mann= 4 ,-1 , 0
  4675.9     .04       0  4931.5     .05       0  4975.8     .05       0
  4979.8     .05       0
Bank Sta=4975.8,4979.8
XS Rating Curve= 0 ,0
Exp/Cntr=0.3,0.1

Type RM Length L Ch R = 1 ,150383  ,478,478,478
BEGIN DESCRIPTION:
COTTONWOOD CREEK 54.0
END DESCRIPTION:
XS GIS Cut Line= 3
      2457374.99     13569125.04        2457425.       13568825.
      2457225.02     13568625.02
#Sta/Elev= 30
  4744.1  353.03  4756.8  352.08  4764.4  351.63    4772  351.77  4777.1  351.01
  4784.7  350.89  4815.1  349.26  4865.8  347.48  4893.7  345.75  4898.7  346.16
  4906.4   345.3  4936.8  344.63  4954.5  343.74  4959.6  344.01  4977.3   342.3
  4985.5  342.29  4985.7  341.79  4989.2  341.79  4989.5  342.29  5062.4  342.38
  5076.6   344.1  5090.7  347.58    5119  348.42  5133.1  350.57  5147.3  350.41
  5175.6  348.77  5288.7  351.29    5317  352.29  5327.6  353.11  5331.1  353.11
#Mann= 4 ,-1 , 0
  4744.1    .013       0  4756.8     .05       0  4985.5     .05       0
  4989.5     .05       0
Bank Sta=4985.5,4989.5
XS Rating Curve= 0 ,0
Exp/Cntr=0.3,0.1

Type RM Length L Ch R = 1 ,149905  ,451,451,451
BEGIN DESCRIPTION:
COTTONWOOD CREEK 53.0
END DESCRIPTION:
XS GIS Cut Line= 3
        2457875.     13569074.96        2457825.       13568675.
      2457625.02     13568425.02
#Sta/Elev= 30
  4597.2  350.75  4607.2  350.15  4676.8  348.35  4697.9     348  4715.6  347.19
  4738.3  346.94  4758.4  345.93  4778.6  345.56  4796.2   344.6  4808.8  344.68
    4829  343.97  4869.3   343.6  4896.9  342.86  4929.7  342.67  4962.5  341.76
  4988.2   337.8  4988.4   337.3  4991.9   337.3  4992.2   337.8  4997.8  339.14
  5057.5  340.87  5064.3  341.82  5071.5  342.21  5106.7  342.38  5114.7  341.98
  5178.8  344.17  5220.4  347.44  5249.2  347.48    5270  347.94  5320.4  349.66
#Mann= 6 ,-1 , 0
  4597.2    .013       0  4676.8     .05       0  4896.9    .013       0
  4988.2     .03       0  4992.2    .013       0  5057.5     .05       0
Bank Sta=4988.2,4992.2
XS Rating Curve= 0 ,0
Exp/Cntr=0.3,0.1

Type RM Length L Ch R = 1 ,149454  ,547,547,547
BEGIN DESCRIPTION:
COTTONWOOD CREEK 52.0
END DESCRIPTION:
XS GIS Cut Line= 3
      2458074.99     13568925.03        2458225.       13568525.
      2458024.99     13568224.99
#Sta/Elev= 30
  4581.6  346.46  4651.9  344.42  4699.1  344.14  4731.2  342.56  4828.2  340.28
  4905.5  337.86  4933.2  336.45  4938.5  337.09  4942.8  334.65    4943  334.15
  4946.5  334.15  4946.8  334.65  4963.4  336.27  4968.8  334.92    4999  335.02
  5011.8  335.73  5016.3  337.05  5119.6   339.9  5139.5  340.58  5159.1  340.24
  5189.1  342.13  5217.7  341.32  5232.7  341.62  5274.7  344.53  5283.8  344.63
  5289.8  343.87  5334.6  343.94  5355.9  344.92  5361.9  346.06  5369.4  346.37
#Mann= 6 ,-1 , 0
  4581.6     .05       0  4905.5     .04       0  4942.8     .04       0
  4946.8     .04       0  5119.6     .05       0  5334.6    .013       0
Bank Sta=4942.8,4946.8
XS Rating Curve= 0 ,0
Exp/Cntr=0.3,0.1

Type RM Length L Ch R = 1 ,148907  ,438,438,438
BEGIN DESCRIPTION:
COTTONWOOD CREEK 51.0
END DESCRIPTION:
XS GIS Cut Line= 4
       2458260.2     13569337.27      2458632.43     13568382.43
        2458575.       13568325.      2457974.98     13567824.98
#Sta/Elev= 30
  3898.1  350.04  4214.5   343.7  4319.1  341.37  4333.5  341.04  4423.7  339.96
  4445.4  338.55  4528.3  337.33  4813.6  335.28  4877.2  333.08    4891  335.31
  4947.6  335.06  4973.9  331.97  4974.1  331.47  4977.9  331.97  5011.3  334.79
  5110.2  334.61  5180.5  336.66  5210.5  337.98  5248.2  337.59  5293.3  338.08
  5344.5  341.04  5387.5   340.2  5416.1  342.77  5432.8  342.82  5465.6   342.5
  5494.2  345.21  5526.4  344.69    5657  348.86  5763.7  355.69  5785.2  355.94
#Mann= 14 ,-1 , 0
  3898.1     .05       0  4214.5     .04       0  4319.1    .013       0
  4333.5     .04       0  4423.7    .013       0  4528.3     .04       0
  4813.6     .05       0  4973.9     .05       0  4977.9     .05       0
  5180.5     .04       0  5248.2     .05       0  5293.3     .04       0
  5432.8     .05       0  5526.4     .04       0
Bank Sta=4973.9,4977.9
XS Rating Curve= 0 ,0
Exp/Cntr=0.3,0.1

Type RM Length L Ch R = 1 ,148469  ,396,396,396
BEGIN DESCRIPTION:
COTTONWOOD CREEK 50.0
END DESCRIPTION:
XS GIS Cut Line= 3
      2459374.99     13568524.99        2458775.       13567925.
      2458175.03     13567325.03
#Sta/Elev= 30
  4327.8  344.21  4393.7  342.29  4410.1  342.21  4525.8  338.27  4780.3  335.02
  4893.5  332.25  4933.7  331.86    4934  331.36  4937.7  331.36    4938  331.86
  5036.3  332.34  5166.2  333.37  5204.6  333.39  5218.7  333.89  5289.5  333.62
  5331.9  334.94  5360.2  337.13  5388.4  336.04  5433.9  336.23  5487.4  338.94
    5544  339.06  5572.3  339.59  5614.7  341.48  5627.2  341.44  5671.3  343.36
  5684.9  342.98  5883.4  351.06  5925.8  351.61  5998.3  354.77  6024.8  356.16
#Mann= 11 ,-1 , 0
  4327.8     .05       0  4393.7    .013       0  4410.1     .05       0
  4933.7     .05       0    4938     .05       0  5036.3     .04       0
  5166.2     .05       0  5433.9     .04       0  5627.2    .013       0
  5684.9     .04       0  5998.3     .05       0
Bank Sta=4933.7,4938
XS Rating Curve= 0 ,0
Exp/Cntr=0.3,0.1

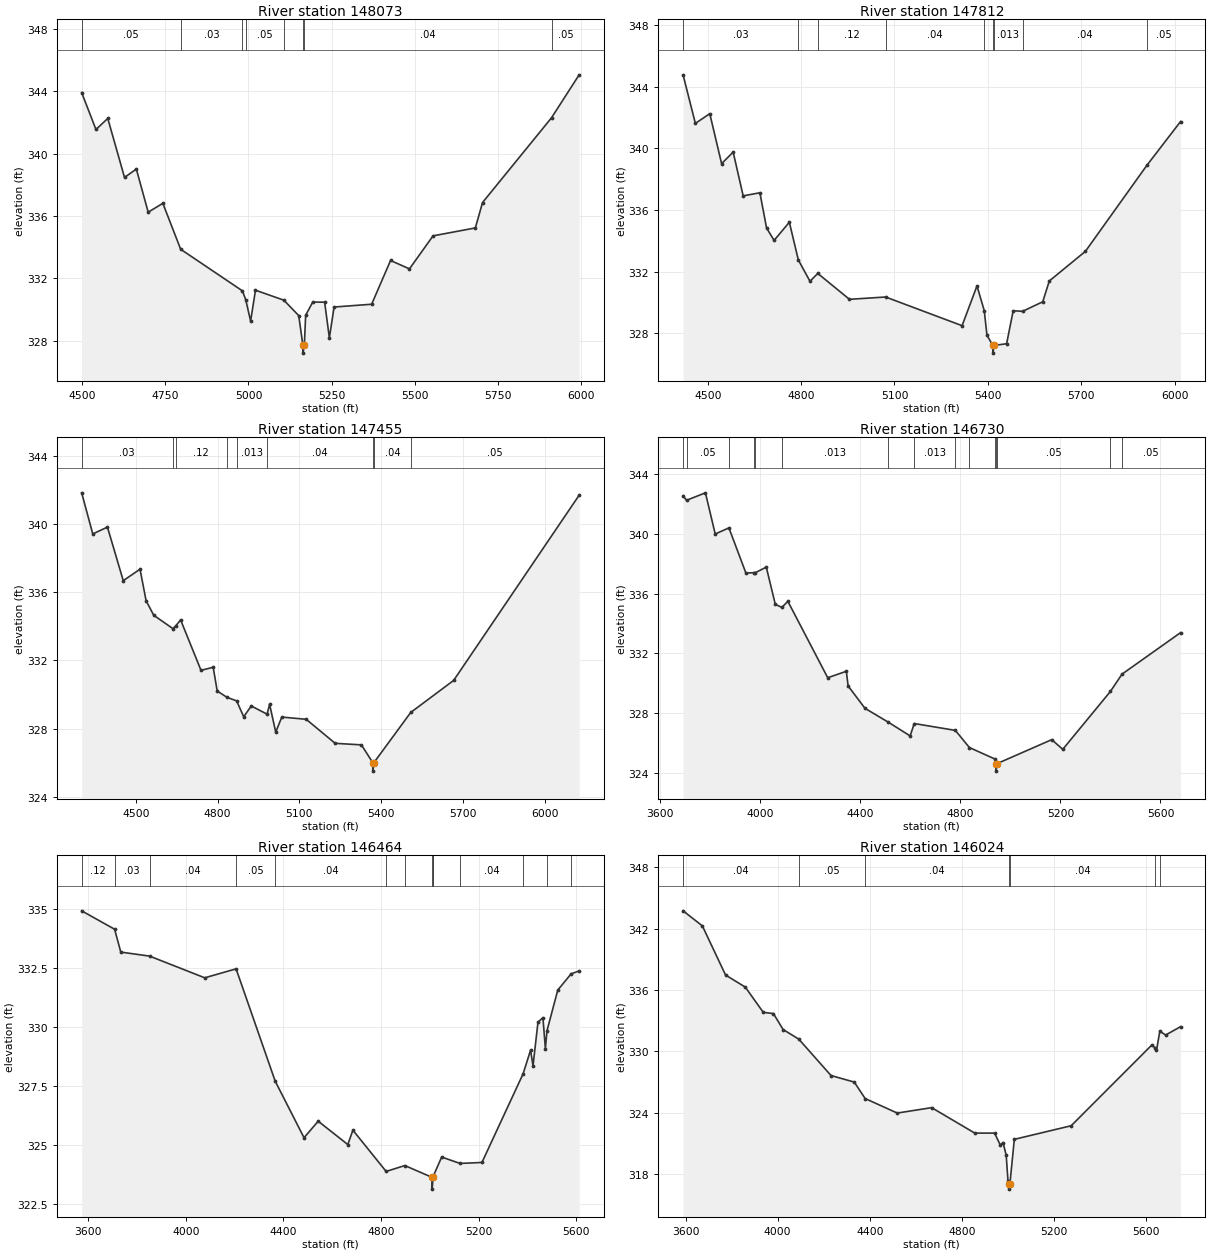
Type RM Length L Ch R = 1 ,148073  ,261,261,261
BEGIN DESCRIPTION:
COTTONWOOD CREEK 49.0
END DESCRIPTION:
XS GIS Cut Line= 3
        2459525.     13568275.01        2459125.       13567725.
      2458525.02     13567175.01
#Sta/Elev= 30
  4499.1  343.93    4542  341.56  4577.5  342.27  4627.8  338.48  4663.3  339.02
  4698.9  336.25  4742.9  336.82  4796.4  333.87  4981.8   331.2  4991.7  330.64
  5006.5  329.26  5021.1  331.24  5106.3   330.6    5151  329.61  5163.5   327.7
  5163.8   327.2  5167.8   327.7  5171.8  329.63  5193.1  330.48  5228.8  330.47
    5243  328.18  5257.2  330.16    5370  330.34  5426.8  333.15  5483.5  332.61
  5554.4  334.73  5681.4  335.24    5703  336.87  5910.1  342.31  5993.1  345.07
#Mann= 8 ,-1 , 0
  4499.1     .05       0  4796.4     .03       0  4981.8     .12       0
  4991.7     .05       0  5106.3     .04       0  5163.5     .05       0
  5167.8     .04       0  5910.1     .05       0
Bank Sta=5163.5,5167.8
XS Rating Curve= 0 ,0
Exp/Cntr=0.3,0.1

Type RM Length L Ch R = 1 ,147812  ,357,357,357
BEGIN DESCRIPTION:
COTTONWOOD CREEK 48.0
END DESCRIPTION:
XS GIS Cut Line= 3
      2459624.99     13568224.99        2459275.       13567325.
        2458675.       13567125.
#Sta/Elev= 30
  4420.8  344.76  4460.3  341.61  4506.6  342.24  4544.6     339  4581.7  339.75
  4613.9  336.91  4667.6  337.11    4689  334.83  4713.2  334.02  4762.2   335.2
  4791.1  332.75  4828.5  331.37  4853.5  331.88  4955.3   330.2  5071.4  330.35
  5317.1  328.49    5365  331.07  5388.4  329.46    5397  327.87  5415.9  327.21
  5416.2  326.71  5420.2  327.21  5460.2  327.32  5481.3  329.46  5511.4  329.42
  5576.2  330.04  5597.3  331.39  5713.2  333.31  5910.4  338.88  6018.9  341.73
#Mann= 9 ,-1 , 0
  4420.8     .03       0  4791.1     .05       0  4853.5     .12       0
  5071.4     .04       0  5388.4    .013       0  5415.9     .05       0
  5420.2    .013       0  5511.4     .04       0  5910.4     .05       0
Bank Sta=5415.9,5420.2
XS Rating Curve= 0 ,0
Exp/Cntr=0.3,0.1

Type RM Length L Ch R = 1 ,147455  ,725,725,725
BEGIN DESCRIPTION:
Mapping XS 95a106aa
END DESCRIPTION:
XS GIS Cut Line= 3
      2459876.63      13568009.5      2459438.27     13567132.79
      2458696.91      13566729.6
#Sta/Elev= 30
  4301.7  341.83  4342.4  339.42  4396.2  339.82  4454.2  336.68  4515.7  337.35
    4538   335.5    4566  334.65    4636  333.87  4646.3  334.02  4664.5  334.38
  4739.3  331.42    4784   331.6  4798.7  330.21  4834.3  329.84  4869.9  329.63
  4895.8   328.7  4923.7  329.33  4981.7  328.85  4990.8  329.43  5013.2   327.8
  5035.6  328.68    5125  328.55  5231.2  327.14  5327.5  327.05    5369  326.01
  5369.3  325.51  5373.4  326.01  5508.2  328.95  5665.7  330.83  6125.8  341.69
#Mann= 9 ,-1 , 0
  4301.7     .03       0    4636     .05       0  4646.3     .12       0
  4834.3     .05       0  4869.9    .013       0  4981.7     .04       0
    5369     .04       0  5373.4     .04       0  5508.2     .05       0
Bank Sta=5369,5373.4
XS Rating Curve= 0 ,0
Exp/Cntr=0.3,0.1

Type RM Length L Ch R = 1 ,146730  ,266,266,266
BEGIN DESCRIPTION:
Mapping XS b63610f7
END DESCRIPTION:
XS GIS Cut Line= 3
       2460024.2     13567979.11      2459655.67      13566956.2
      2459121.43     13566230.01
#Sta/Elev= 30
  3691.4  342.56  3705.2  342.26  3780.8  342.76  3819.9     340  3874.7  340.41
  3942.7  337.38  3974.1  337.41  3980.5  337.41  4024.1  337.78  4060.1  335.29
  4086.4  335.08  4110.3  335.49  4269.7  330.37  4344.1   330.8  4351.2  329.82
  4418.6  328.32  4511.8  327.39  4599.2  326.47  4615.6   327.3  4779.9  326.84
  4836.1  325.69  4939.7  324.91  4941.7  324.61    4942  324.11  4946.2  324.61
  5165.4  326.22  5209.3  325.57  5399.8  329.45  5446.3  330.61  5680.2  333.39
#Mann= 15 ,-1 , 0
  3691.4    .013       0  3705.2     .05       0  3874.7    .013       0
  3974.1     .03       0  3980.5     .05       0  4086.4    .013       0
  4511.8     .04       0  4615.6    .013       0  4779.9     .05       0
  4836.1    .013       0  4939.7     .05       0  4941.7     .05       0
  4946.2     .05       0  5399.8     .03       0  5446.3     .05       0
Bank Sta=4941.7,4946.2
XS Rating Curve= 0 ,0
Exp/Cntr=0.3,0.1

Type RM Length L Ch R = 1 ,146464  ,440,440,440
BEGIN DESCRIPTION:
Mapping XS 2f577128
END DESCRIPTION:
XS GIS Cut Line= 4
      2460501.64     13567783.84      2459742.09     13566759.53
      2459510.37       13566318.      2459248.51     13566275.01
#Sta/Elev= 30
  3573.2  334.94  3708.2  334.16  3733.6  333.19  3851.7  333.02  4077.8   332.1
  4206.2  332.48  4366.4  327.72  4484.7  325.32  4542.8  326.02  4664.2  325.03
    4685  325.64  4821.3  323.89    4898  324.14  5009.3  323.64  5009.7  323.14
  5013.9  323.64  5014.9   323.7  5048.9   324.5    5124  324.23    5214  324.27
  5382.7  328.03  5413.3  329.03  5423.4  328.37  5443.7  330.22    5464  330.41
  5474.1  329.09  5480.5  329.85  5524.8  331.58  5579.7  332.27  5612.4  332.39
#Mann= 14 ,-1 , 0
  3573.2     .12       0  3708.2     .03       0  3851.7     .04       0
  4206.2     .05       0  4366.4     .04       0  4821.3     .05       0
    4898     .04       0  5009.3     .04       0  5013.9     .04       0
  5014.9     .05       0    5124     .04       0  5382.7    .013       0
  5480.5     .04       0  5579.7     .05       0
Bank Sta=5009.3,5013.9
XS Rating Curve= 0 ,0
Exp/Cntr=0.3,0.1

Type RM Length L Ch R = 1 ,146024  ,278,278,278
BEGIN DESCRIPTION:
Mapping XS 350299e8
END DESCRIPTION:
XS GIS Cut Line= 4
      2460809.81     13567506.07      2460015.53     13566377.58
      2459703.14     13566185.76      2459291.35     13566237.56
#Sta/Elev= 30
    3589  343.75  3672.7  342.28  3773.7  337.47  3859.3  336.29  3937.5  333.82
  3981.6   333.7  4023.7  332.14  4091.8   331.2  4231.9  327.64  4332.9     327
  4380.2  325.39  4519.7  323.97  4669.2   324.5  4856.5  322.01  4942.7  322.01
  4967.5  320.83  4979.5  321.09  4993.1  319.83  5000.8  317.34  5004.2  317.03
  5004.5  316.53  5009.1  317.03  5028.3   321.4  5275.4  322.73    5626  330.63
  5640.5  330.33  5646.1   330.1  5660.6  331.98  5685.7   331.6  5750.6  332.42
#Mann= 7 ,-1 , 0
    3589     .04       0  4091.8     .05       0  4380.2     .04       0
  5004.2     .04       0  5009.1     .04       0  5640.5    .013       0
  5660.6     .04       0
Bank Sta=5004.2,5009.1
XS Rating Curve= 0 ,0
Exp/Cntr=0.3,0.1

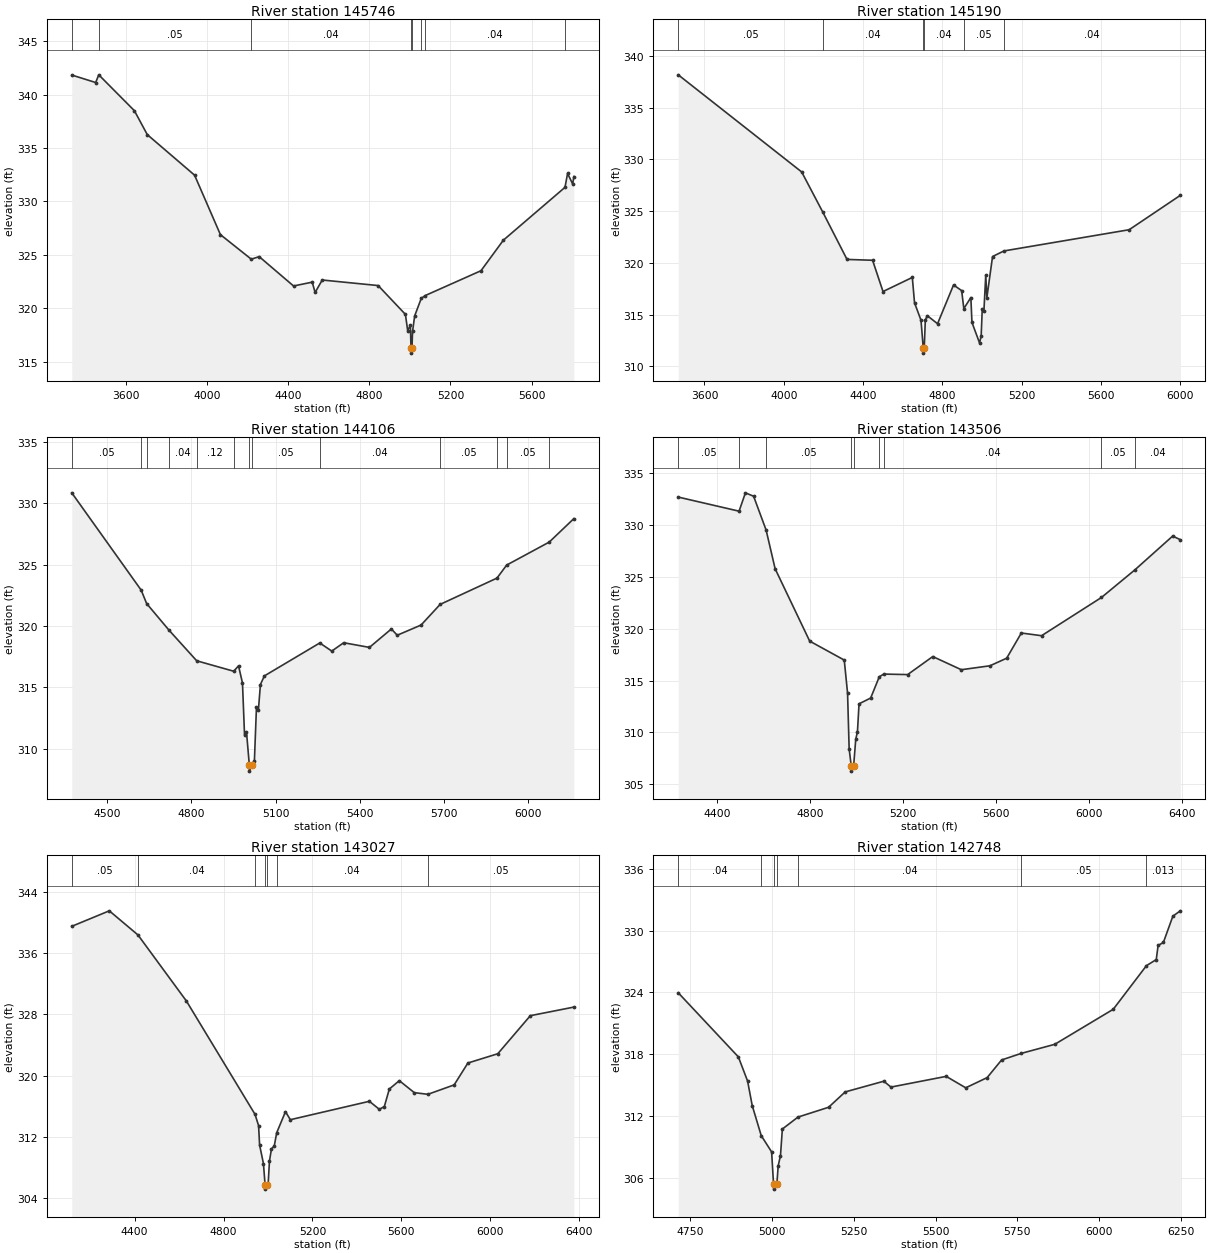
Type RM Length L Ch R = 1 ,145746  ,556,556,556
BEGIN DESCRIPTION:
Mapping XS d3e37707
END DESCRIPTION:
XS GIS Cut Line= 4
      2461321.94     13567284.69      2460124.03     13566134.53
      2459877.99     13566055.24      2459339.52     13566197.77
#Sta/Elev= 30
  3332.3  341.84  3450.2  341.14  3465.5  341.86  3641.1   338.5  3704.7  336.26
    3938  332.46  4065.4  326.89  4217.7  324.59  4256.6  324.83  4426.1  322.08
  4518.2  322.44  4532.4  321.47  4567.6  322.64  4843.4  322.12  4977.8  319.42
    4989   317.9  5002.5  318.42  5005.2  316.29  5005.6  315.79  5010.2  316.29
    5013  317.82  5023.5  319.28    5056  320.92  5075.2  321.18  5350.6  323.51
  5460.9  326.37  5764.8  331.32  5777.6  332.62  5802.8  331.63  5808.5  332.33
#Mann= 8 ,-1 , 0
  3332.3     .04       0  3465.5     .05       0  4217.7     .04       0
  5005.2     .04       0  5010.2     .04       0    5056     .05       0
  5075.2     .04       0  5764.8    .013       0
Bank Sta=5005.2,5010.2
XS Rating Curve= 0 ,0
Exp/Cntr=0.3,0.1

Type RM Length L Ch R = 1 ,145190  ,1084,1084,1084
BEGIN DESCRIPTION:
Mapping XS 48200aa8
END DESCRIPTION:
XS GIS Cut Line= 5
      2461374.02     13567093.68      2460922.65      13566034.7
      2460436.11     13565818.09       2460115.8     13565920.48
       2459632.3     13566094.86
#Sta/Elev= 30
  3467.5  338.16  4090.5  328.78    4196  324.94  4319.4  320.33  4448.4  320.25
    4501  317.23  4648.9  318.59  4660.1  316.14  4692.7  314.46  4704.1  311.78
  4704.4  311.28  4709.1  311.78  4714.6  314.48  4724.3   314.9  4776.3  314.12
  4856.9  317.86  4897.9  317.32  4908.9  315.58  4944.4  316.65  4949.9  314.25
  4988.3  312.26  4996.4  312.94  5001.9  315.55  5010.2  315.32  5019.6  318.82
  5025.1  316.63  5053.9  320.61  5111.4  321.15  5743.5   323.2  6001.5  326.52
#Mann= 6 ,-1 , 0
  3467.5     .05       0    4196     .04       0  4704.1     .05       0
  4709.1     .04       0  4908.9     .05       0  5111.4     .04       0
Bank Sta=4704.1,4709.1
XS Rating Curve= 0 ,0
Exp/Cntr=0.3,0.1

Type RM Length L Ch R = 1 ,144106  ,600,600,600
BEGIN DESCRIPTION:
COTTONWOOD CREEK 41.0
END DESCRIPTION:
XS GIS Cut Line= 3
        2461525.     13566325.03        2461575.       13565775.
      2460725.03     13564875.03
#Sta/Elev= 30
  4373.4  330.84  4620.9  322.92  4640.3  321.83  4720.2  319.66  4818.9  317.17
  4950.8  316.32    4968  316.76  4982.1  315.36  4989.4  311.14  4996.3   311.4
  5006.5  308.69    5007  308.19  5014.4  308.69  5024.6  309.03  5031.9  313.37
  5038.8  313.15  5046.1  315.24  5060.2  315.94  5257.7  318.62  5300.5  317.96
    5343  318.64  5434.8  318.26  5512.9  319.76  5533.9  319.25  5618.9  320.08
  5686.9  321.76  5889.5   323.9  5924.1  324.96  6075.8  326.83  6163.6  328.74
#Mann= 13 ,-1 , 0
  4373.4     .05       0  4620.9     .12       0  4640.3     .05       0
  4720.2     .04       0  4818.9     .12       0  4950.8     .05       0
  5006.5     .05       0  5014.4     .05       0  5257.7     .04       0
  5686.9     .05       0  5889.5     .04       0  5924.1     .05       0
  6075.8     .04       0
Bank Sta=5006.5,5014.4
XS Rating Curve= 0 ,0
Exp/Cntr=0.3,0.1

Type RM Length L Ch R = 1 ,143506  ,479,479,479
BEGIN DESCRIPTION:
Mapping XS a09edaf4
END DESCRIPTION:
XS GIS Cut Line= 3
      2462602.36     13565995.67      2462025.08     13565461.79
      2460888.95     13564694.25
#Sta/Elev= 30
  4234.6   332.7    4496  331.34  4523.3  333.11  4558.5  332.78  4612.2  329.52
  4650.9  325.79  4799.4  318.81    4948  316.98  4962.2  313.79    4969  308.42
    4978  306.77  4978.5  306.27  4988.3  306.77  4997.3  309.33  5004.7  310.08
  5011.5  312.76  5061.5  313.32  5098.5  315.37  5117.8  315.63  5220.4  315.58
  5328.3  317.32  5451.1  316.05    5574  316.43  5645.9  317.16  5708.9  319.59
  5795.8  319.33  6053.3  323.02  6196.8  325.68  6359.2  328.94    6392  328.59
#Mann= 9 ,-1 , 0
  4234.6     .05       0    4496     .12       0  4612.2     .05       0
    4978     .05       0  4988.3     .05       0  5098.5     .12       0
  5117.8     .04       0  6053.3     .05       0  6196.8     .04       0
Bank Sta=4978,4988.3
XS Rating Curve= 0 ,0
Exp/Cntr=0.3,0.1

Type RM Length L Ch R = 1 ,143027  ,279,279,279
BEGIN DESCRIPTION:
Mapping XS 299783a5
END DESCRIPTION:
XS GIS Cut Line= 4
      2462858.41     13565865.43      2462389.66     13565162.31
      2462051.12     13564936.61      2461149.62      13564490.2
#Sta/Elev= 30
  4117.5  339.48  4286.3   341.5    4415  338.36  4633.1  329.74  4941.6  314.97
  4957.6   313.5  4962.2  310.97  4979.5  308.55    4987  305.72  4987.5  305.22
  4997.3  305.72  5000.5   305.8  5006.5  308.87  5015.5  310.45  5028.2  310.86
  5039.1  312.57  5078.6  315.32  5100.4  314.27  5455.9  316.67  5500.8  315.62
  5523.2  315.99  5545.6  318.27  5590.5  319.36  5657.8   317.8  5719.1  317.58
  5837.2  318.81  5898.9  321.66  6033.4  322.87  6179.7  327.83  6375.4  328.95
#Mann= 7 ,-1 , 0
  4117.5     .05       0    4415     .04       0  4941.6     .05       0
    4987     .05       0  4997.3     .05       0  5039.1     .04       0
  5719.1     .05       0
Bank Sta=4987,4997.3
XS Rating Curve= 0 ,0
Exp/Cntr=0.3,0.1

Type RM Length L Ch R = 1 ,142748  ,497,497,497
BEGIN DESCRIPTION:
COTTONWOOD CREEK 38.0
END DESCRIPTION:
XS GIS Cut Line= 3
      2462725.02     13565125.02        2462525.       13564925.
      2461424.97     13564324.98
#Sta/Elev= 30
  4712.6  323.96  4896.5  317.74  4924.8  315.39  4938.9  313.02  4966.5   310.1
  4998.3  308.52  5004.1  305.41  5004.6  304.91  5014.4  305.41  5018.3  307.16
  5025.4  308.17  5031.1  310.74  5078.9   311.9  5172.5  312.85  5223.3  314.34
  5341.5  315.38  5363.3  314.81  5532.3  315.85  5592.1  314.74  5657.6  315.73
  5701.7  317.44    5762  318.08  5864.5  318.96  6043.4  322.36  6144.9  326.59
  6174.9  327.18  6180.6  328.55  6196.7  328.84  6225.7  331.39  6248.5  331.91
#Mann= 7 ,-1 , 0
  4712.6     .04       0  4966.5     .05       0  5004.1     .05       0
  5014.4     .05       0  5078.9     .04       0    5762     .05       0
  6144.9    .013       0
Bank Sta=5004.1,5014.4
XS Rating Curve= 0 ,0
Exp/Cntr=0.3,0.1

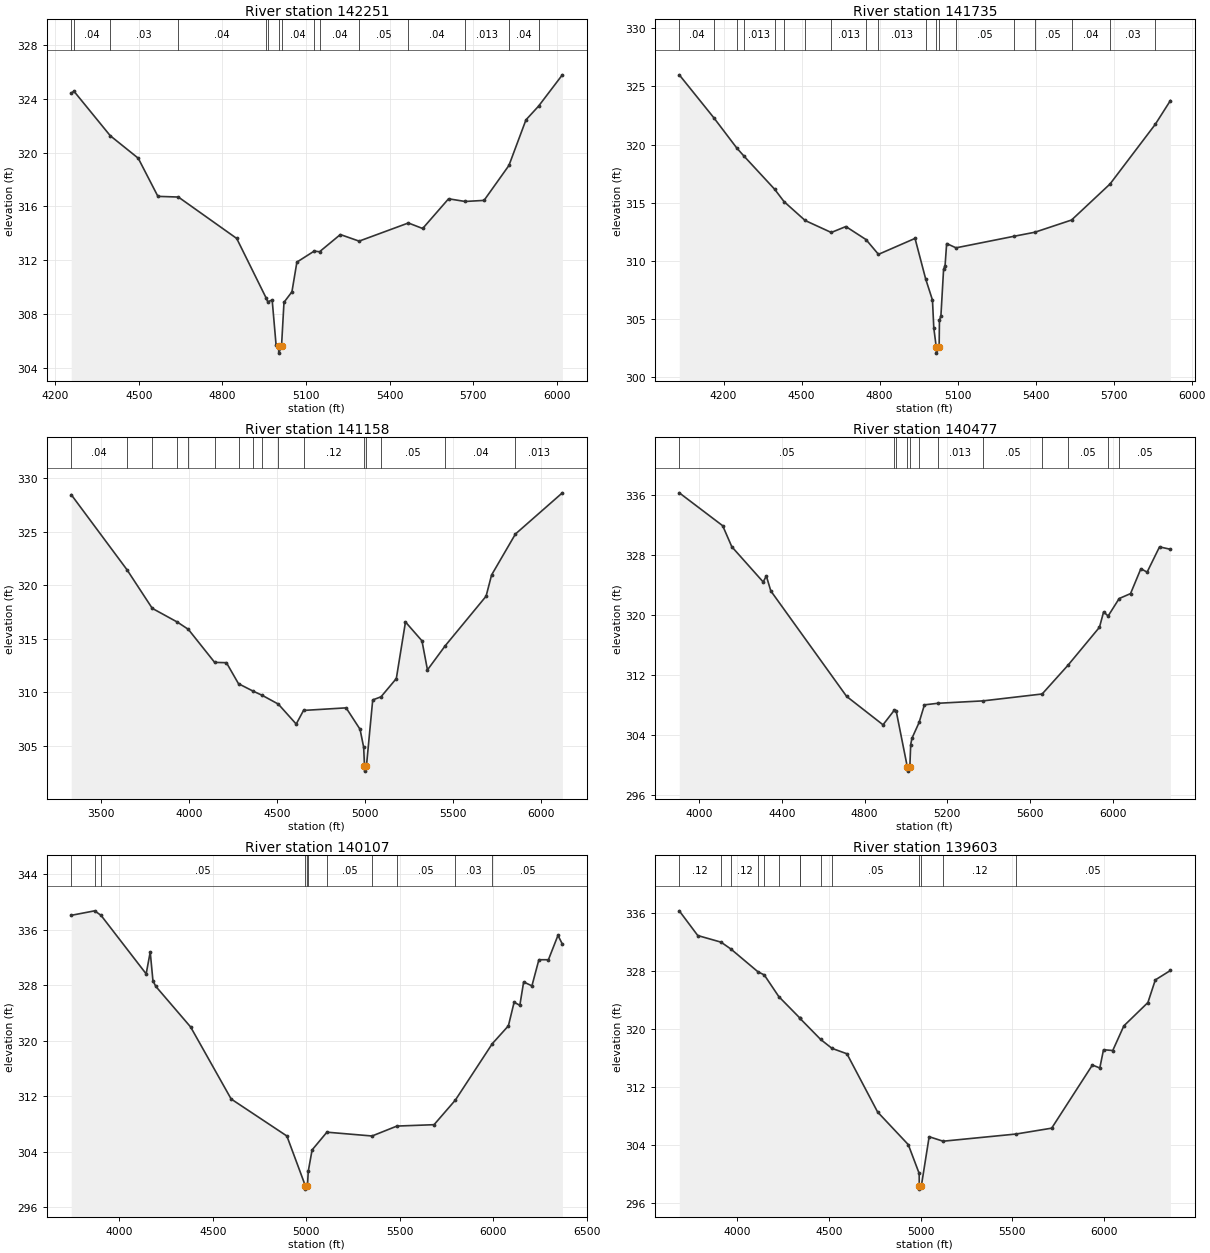
Type RM Length L Ch R = 1 ,142251  ,516,516,516
BEGIN DESCRIPTION:
COTTONWOOD CREEK 37.0
END DESCRIPTION:
XS GIS Cut Line= 3
      2463074.97     13565024.97        2462525.       13564475.
      2461624.96     13564074.98
#Sta/Elev= 30
  4257.6  324.43  4267.4  324.57  4397.7  321.26    4498  319.59  4568.7  316.75
  4642.1   316.7  4851.5  313.62  4956.7  309.21  4962.8  308.91  4978.8  309.04
  4992.9  305.67  5001.9  305.59  5002.4  305.09  5012.3  305.59  5021.2  308.87
  5049.7  309.65  5067.5  311.86  5129.7  312.68  5148.8  312.63  5223.5  313.91
  5290.8  313.42  5467.5  314.77  5518.9  314.36  5611.9  316.57  5671.2  316.37
  5739.2  316.45  5828.5  319.05  5889.6  322.44  5934.8  323.46  6020.3  325.79
#Mann= 15 ,-1 , 0
  4257.6     .03       0  4267.4     .04       0  4397.7     .03       0
  4642.1     .04       0  4956.7     .05       0  4962.8     .04       0
  5001.9     .04       0  5012.3     .04       0  5129.7     .05       0
  5148.8     .04       0  5290.8     .05       0  5467.5     .04       0
  5671.2    .013       0  5828.5     .04       0  5934.8     .12       0
Bank Sta=5001.9,5012.3
XS Rating Curve= 0 ,0
Exp/Cntr=0.3,0.1

Type RM Length L Ch R = 1 ,141735  ,577,577,577
BEGIN DESCRIPTION:
COTTONWOOD CREEK 36.0
END DESCRIPTION:
XS GIS Cut Line= 3
      2463375.03     13564575.02        2462575.       13564025.
      2461775.04     13563575.02
#Sta/Elev= 30
  4029.6     326  4162.5  322.31  4251.1   319.7  4279.5  318.99  4396.6  316.16
  4432.6   315.1  4513.6  313.48  4614.1  312.45  4670.3  312.96  4747.7  311.84
  4795.6  310.57  4936.2  311.94  4977.2  308.45  5003.3  306.64  5008.4  304.24
  5017.9  302.58  5018.4  302.08  5028.9  302.58  5030.1   304.9  5035.8   305.3
    5046  309.27  5051.8  309.61  5057.8   311.5  5093.9  311.13    5316  312.12
  5396.8  312.47  5538.1  313.52  5686.2  316.62  5859.9  321.74  5918.3  323.79
#Mann= 19 ,-1 , 0
  4029.6     .04       0  4162.5    .013       0  4251.1     .04       0
  4279.5    .013       0  4396.6     .04       0  4432.6    .013       0
  4513.6     .04       0  4614.1    .013       0  4747.7     .05       0
  4795.6    .013       0  4977.2     .12       0  5017.9     .05       0
  5028.9     .12       0  5093.9     .05       0    5316     .04       0
  5396.8     .05       0  5538.1     .04       0  5686.2     .03       0
  5859.9     .04       0
Bank Sta=5017.9,5028.9
XS Rating Curve= 0 ,0
Exp/Cntr=0.3,0.1

Type RM Length L Ch R = 1 ,141158  ,681,681,681
BEGIN DESCRIPTION:
Mapping XS 17707507
END DESCRIPTION:
XS GIS Cut Line= 4
      2463856.68     13564489.57      2462897.47     13563526.02
       2462459.1     13563421.85      2461518.61     13563153.14
#Sta/Elev= 30
  3330.3  328.44  3647.2  321.43  3790.3  317.84  3933.5  316.55  3995.2  315.88
  4144.5   312.8  4211.5  312.77    4280  310.81  4362.9  310.12  4415.5  309.72
    4506  308.91  4607.5  307.05  4649.1  308.32  4890.9  308.56    4970  306.56
  4990.5  304.89  4995.2  303.16  4995.7  302.66  5006.4  303.16  5041.9   309.3
    5089  309.59  5175.9  311.29  5227.9  316.57  5321.5  314.81  5352.7   312.1
  5453.5  314.35  5685.5  318.97  5716.7  320.95  5852.1  324.77  6118.6  328.61
#Mann= 16 ,-1 , 0
  3330.3     .04       0  3647.2    .013       0  3790.3     .05       0
  3933.5     .12       0  3995.2     .05       0  4144.5    .013       0
    4280     .12       0  4362.9    .013       0  4415.5     .12       0
    4506     .05       0  4649.1     .12       0  4995.2     .05       0
  5006.4     .12       0    5089     .05       0  5453.5     .04       0
  5852.1    .013       0
Bank Sta=4995.2,5006.4
XS Rating Curve= 0 ,0
Exp/Cntr=0.3,0.1

Type RM Length L Ch R = 1 ,140477  ,370,370,370
BEGIN DESCRIPTION:
Mapping XS f6533b4c
END DESCRIPTION:
XS GIS Cut Line= 4
      2464017.27     13563677.94      2463023.34     13563109.35
      2462875.77     13563035.57      2461812.41     13562983.49
#Sta/Elev= 30
  3904.3  336.24  4114.3  331.85  4158.3  329.05  4310.1  324.35  4325.2  325.16
  4346.8  323.16  4713.4  309.09  4889.4   305.3  4944.4  307.26  4952.9  307.16
  5007.4  299.62  5007.9  299.12    5019  299.62  5023.3  302.66  5029.1  303.49
  5063.9  305.61  5089.6  307.96  5154.8  308.17  5372.9  308.49  5658.9  309.41
  5783.3  313.23    5936  318.31    5956  320.36  5977.8  319.81  6031.2  322.14
  6086.2   322.8  6136.2  326.12  6166.3  325.66  6226.3  329.03    6279  328.71
#Mann= 12 ,-1 , 0
  3904.3     .05       0  4944.4     .12       0  4952.9    .013       0
  5007.4     .03       0    5019    .013       0  5063.9     .05       0
  5154.8    .013       0  5372.9     .05       0  5658.9     .03       0
  5783.3     .05       0  5977.8     .03       0  6031.2     .05       0
Bank Sta=5007.4,5019
XS Rating Curve= 0 ,0
Exp/Cntr=0.3,0.1

Type RM Length L Ch R = 1 ,140107  ,504,504,504
BEGIN DESCRIPTION:
Mapping XS 7349a29e
END DESCRIPTION:
XS GIS Cut Line= 3
      2464277.69     13563508.66      2463244.69     13562827.24
      2461881.81     13562558.13
#Sta/Elev= 30
  3742.8  338.08  3868.1  338.73  3902.1  338.08  4143.6  329.64  4165.3  332.79
  4179.8  328.66  4194.8  327.85  4381.5  321.98  4598.2   311.6  4896.1  306.27
  4994.6  299.11  4995.1  298.61  5006.2  299.11  5010.5  301.18    5031  304.26
  5110.2  306.82  5351.6  306.27  5484.6   307.7  5683.3   307.9  5797.3  311.45
  5994.5  319.57  6080.8  322.15  6111.4  325.55    6142  325.11  6162.4  328.48
  6206.6  327.91  6243.9  331.68  6294.9  331.68  6345.9  335.19  6369.5  333.93
#Mann= 11 ,-1 , 0
  3742.8     .05       0  3868.1     .12       0  3902.1     .05       0
  4994.6     .05       0  5006.2     .05       0  5010.5     .12       0
  5110.2     .05       0  5351.6     .12       0  5484.6     .05       0
  5797.3     .03       0  5994.5     .05       0
Bank Sta=4994.6,5006.2
XS Rating Curve= 0 ,0
Exp/Cntr=0.3,0.1

Type RM Length L Ch R = 1 ,139603  ,493,493,493
BEGIN DESCRIPTION:
Mapping XS 047794ee
END DESCRIPTION:
XS GIS Cut Line= 4
       2464464.3     13563044.24      2463392.26     13562375.85
      2463192.61     13562297.72      2462003.36     13562141.47
#Sta/Elev= 30
  3684.3  336.26  3785.2  332.85  3911.8  331.94  3965.3     331  4113.3  327.85
  4147.6  327.42  4227.1  324.42    4341  321.49  4342.8  321.41  4454.9  318.52
  4516.6  317.29  4598.2  316.54  4765.7   308.5  4932.6  304.01  4992.1  300.03
  4992.5  298.37    4993  297.87  5004.2  298.37  5046.4   305.1  5122.4  304.48
  5519.8  305.47  5714.3  306.28  5936.2  314.99  5976.6  314.58  5996.8   317.1
  6047.2  316.99  6107.7  320.39  6238.8  323.61  6279.2  326.73  6361.5  328.03
#Mann= 14 ,-1 , 0
  3684.3     .12       0  3911.8     .05       0  3965.3     .12       0
  4113.3     .05       0  4147.6     .12       0  4227.1     .05       0
    4341     .12       0  4342.8     .05       0  4454.9     .12       0
  4516.6     .05       0  4992.5     .05       0  5004.2     .05       0
  5122.4     .12       0  5519.8     .05       0
Bank Sta=4992.5,5004.2
XS Rating Curve= 0 ,0
Exp/Cntr=0.3,0.1