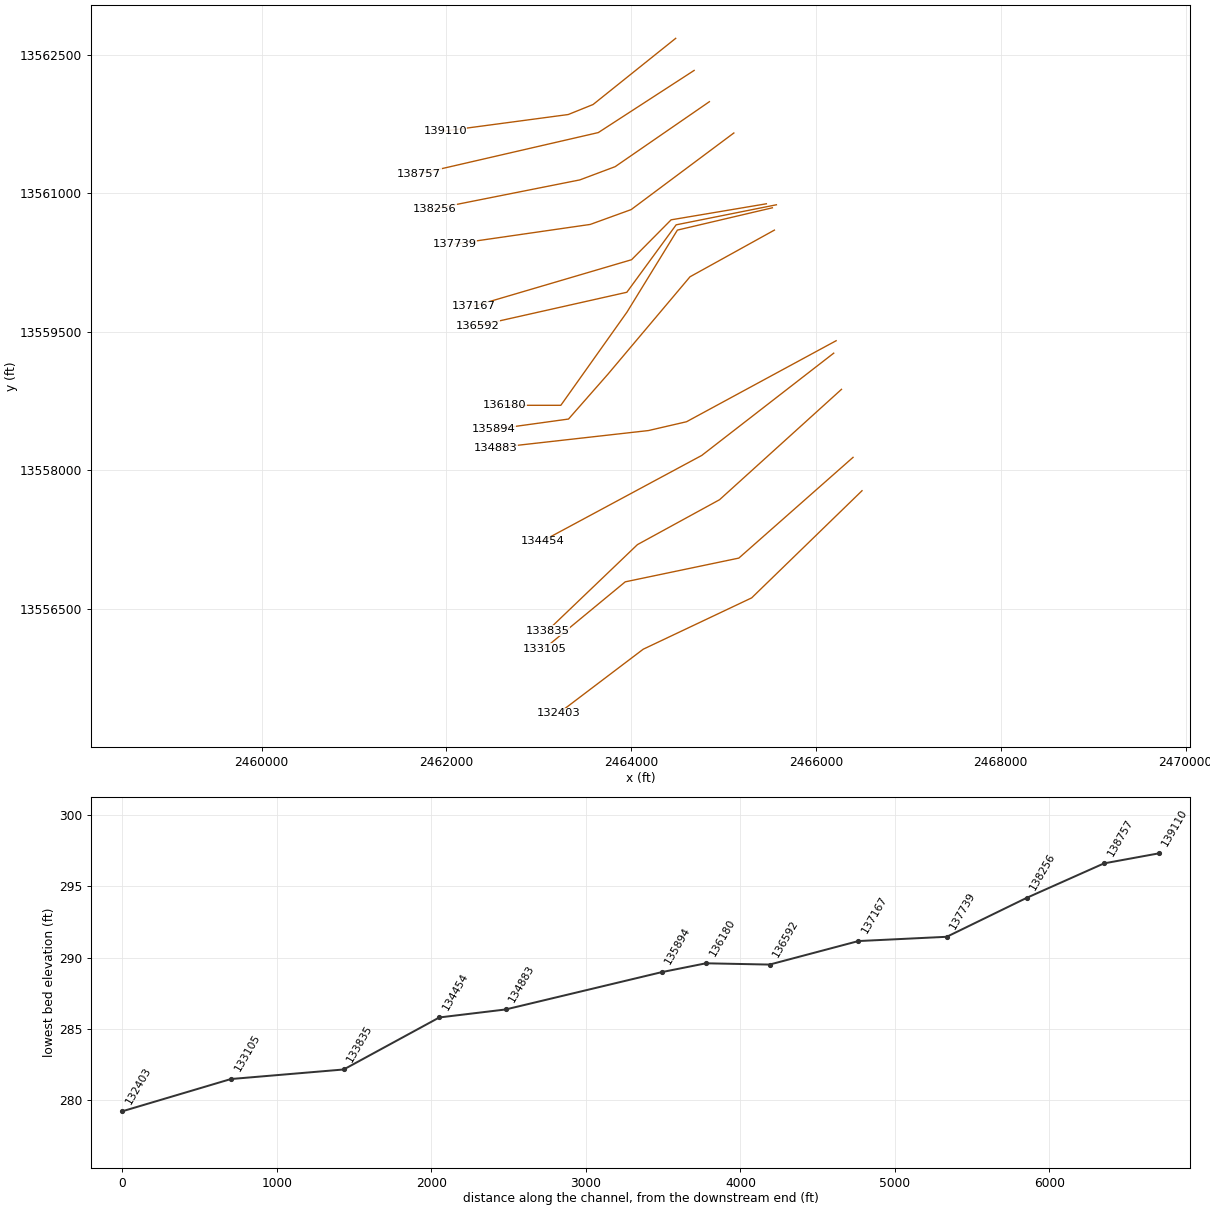
HEC-RAS study TWELVEMILE CREEK.prj: TWELVEMILE CREEK Base Level Engineering

--- TWELVEMILE CREEK.g01 (geometry) --- (continued)

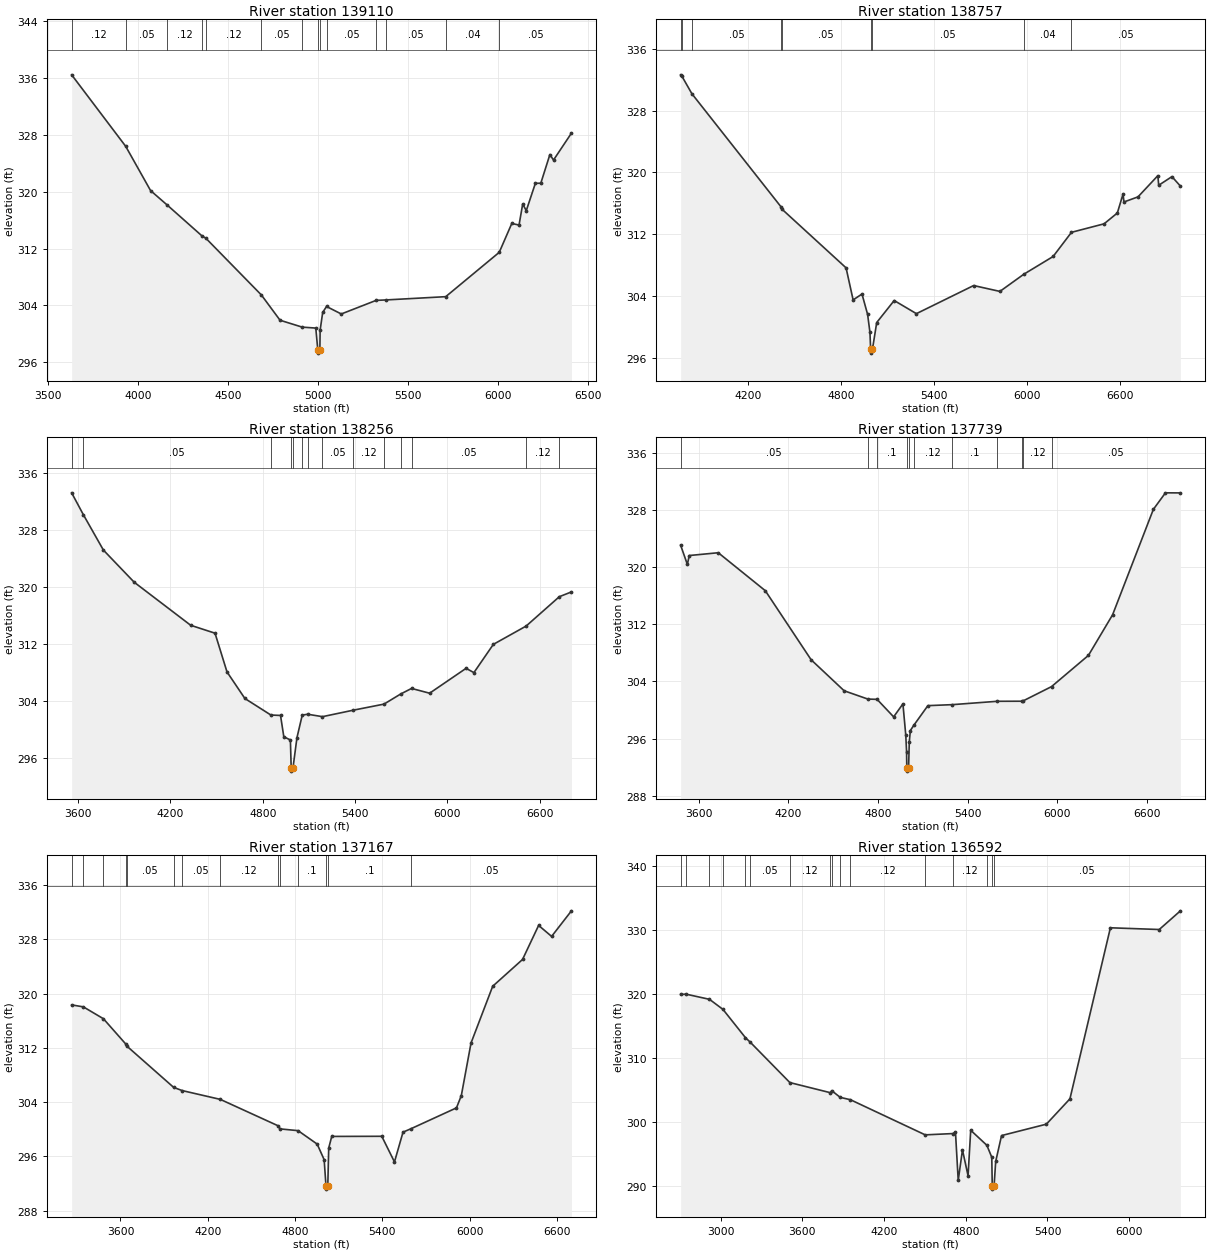
Type RM Length L Ch R = 1 ,139110  ,353,353,353
BEGIN DESCRIPTION:
Mapping XS 30a89d6a
END DESCRIPTION:
XS GIS Cut Line= 4
      2464481.64      13562675.3      2463587.58     13561959.18
      2463318.48     13561850.67      2461986.06     13561672.73
#Sta/Elev= 30
  3629.8   336.4  3930.6  326.35  4068.8  320.14  4161.7   318.1  4355.3  313.76
  4375.8  313.46    4685  305.48  4788.9  301.93  4912.4  300.96  4987.7  300.83
  4998.7  297.81  4999.2  297.31  5010.4  297.81  5011.8  300.53  5026.1  303.03
  5047.4  303.86  5129.5  302.81  5323.4  304.72  5377.3  304.78  5710.4  305.24
  6008.1  311.47  6077.8  315.52  6118.2   315.3  6138.4  318.24  6158.5  317.33
    6209  321.16  6239.3  321.18  6289.7   325.2  6309.9  324.43  6409.7  328.21
#Mann= 14 ,-1 , 0
  3629.8     .12       0  3930.6     .05       0  4161.7     .12       0
  4355.3     .05       0  4375.8     .12       0    4685     .05       0
  4912.4     .12       0  4998.7     .05       0  5010.4     .12       0
  5047.4     .05       0  5323.4     .12       0  5377.3     .05       0
  5710.4     .04       0  6008.1     .05       0
Bank Sta=4998.7,5010.4
XS Rating Curve= 0 ,0
Exp/Cntr=0.3,0.1

Type RM Length L Ch R = 1 ,138757  ,501,501,501
BEGIN DESCRIPTION:
Mapping XS f1cecdbf
END DESCRIPTION:
XS GIS Cut Line= 3
      2464681.29     13562328.08        2463644.     13561655.36
      2461703.87     13561208.31
#Sta/Elev= 30
  3764.7  332.64    3773  332.46  3837.5  330.19  4412.1  315.57  4418.4  315.26
    4833  307.65  4878.5   303.5  4935.8  304.26  4972.1  301.62  4987.2  299.29
  4991.6  297.11  4992.1  296.61  5003.4  297.11  5030.8  300.57  5143.7  303.42
  5287.2  301.72  5656.8  305.36  5826.3   304.6  5980.4  306.82  6169.9  309.12
  6288.5  312.25    6499  313.35  6584.6  314.75  6621.4   317.2  6627.4  316.18
  6718.1  316.84  6846.4  319.59  6851.6  318.34  6937.2  319.46    6992  318.23
#Mann= 9 ,-1 , 0
  3764.7     .05       0    3773     .12       0  3837.5     .05       0
  4412.1     .12       0  4418.4     .05       0  4991.6     .05       0
  5003.4     .05       0  5980.4     .04       0  6288.5     .05       0
Bank Sta=4991.6,5003.4
XS Rating Curve= 0 ,0
Exp/Cntr=0.3,0.1

Type RM Length L Ch R = 1 ,138256  ,517,517,517
BEGIN DESCRIPTION:
Mapping XS a3779c88
END DESCRIPTION:
XS GIS Cut Line= 4
       2464846.3     13561989.59      2463826.29     13561286.44
      2463444.35     13561143.21      2461873.12      13560830.7
#Sta/Elev= 30
  3558.2  333.23  3634.3  330.16  3764.5   325.2  3964.7  320.69  4331.9  314.65
  4490.1  313.54  4567.9  308.11  4684.2  304.38  4853.2  302.06  4915.9     302
  4937.3  299.01    4980  298.56  4985.2  294.69  4985.7  294.19  4997.2  294.69
  5022.7  298.88  5057.1  302.05  5092.3  302.17  5188.5  301.83    5389  302.74
  5588.4  303.59  5697.7  305.02  5767.7  305.79  5885.1  305.12    6122  308.61
  6172.9  308.01  6299.2  311.97  6512.4  314.54  6728.2  318.66    6807  319.33
#Mann= 14 ,-1 , 0
  3558.2     .12       0  3634.3     .05       0  4853.2     .12       0
  4985.2     .05       0  4997.2     .12       0  5057.1     .05       0
  5092.3     .12       0  5188.5     .05       0    5389     .12       0
  5588.4     .05       0  5697.7     .12       0  5767.7     .05       0
  6512.4     .12       0  6728.2     .05       0
Bank Sta=4985.2,4997.2
XS Rating Curve= 0 ,0
Exp/Cntr=0.3,0.1

Type RM Length L Ch R = 1 ,137739  ,572,572,572
BEGIN DESCRIPTION:
Mapping XS 5d849eb7
END DESCRIPTION:
XS GIS Cut Line= 4
      2465111.05     13561651.05       2463999.9     13560822.03
      2463557.19     13560661.44      2462085.86     13560448.77
#Sta/Elev= 30
  3479.5  323.06  3524.5  320.38  3537.3  321.62  3731.2  322.01    4046   316.7
  4352.5  307.04  4573.5   302.7  4732.2  301.54  4793.9   301.5  4904.7  299.05
  4966.8  300.87  4985.9  296.48  4991.2   294.2  4992.7  291.96  4993.2  291.46
  5004.7  291.96  5009.3  295.53  5016.5  297.14  5041.2  297.92  5133.7  300.62
  5297.9  300.76  5598.6  301.23  5761.5  301.24  5773.4  301.31  5960.9  303.28
  6207.9  307.65  6369.6  313.33  6642.4  328.08  6723.2  330.39  6823.4  330.38
#Mann= 11 ,-1 , 0
  3479.5     .05       0  4732.2     .12       0  4793.9      .1       0
  4992.7     .05       0  5004.7      .1       0  5041.2     .12       0
  5297.9      .1       0  5598.6     .12       0  5761.5     .05       0
  5773.4     .12       0  5960.9     .05       0
Bank Sta=4992.7,5004.7
XS Rating Curve= 0 ,0
Exp/Cntr=0.3,0.1

Type RM Length L Ch R = 1 ,137167  ,575,575,575
BEGIN DESCRIPTION:
Mapping XS 3a8f76bf
END DESCRIPTION:
XS GIS Cut Line= 4
        2465463.     13560884.79      2464432.17     13560711.18
      2464004.24     13560279.49       2462294.2     13559776.03
#Sta/Elev= 30
  3264.5  318.32    3345  318.03  3482.9  316.28    3639  312.49  3641.6  312.29
  3965.6  306.16  4024.2  305.69  4286.5  304.39  4682.5  300.51  4696.9  300.04
  4821.1  299.78  4952.3   297.8  5000.3   295.5  5012.8  291.66  5013.3  291.16
  5025.3  291.66  5031.6  297.21  5052.4  298.93  5396.4  298.95  5483.7  295.17
  5542.4  299.56  5596.6  300.06  5909.9  303.14  5943.2  304.95  6009.9   312.7
  6158.9  321.07  6364.1  325.02  6474.6  330.04  6563.9  328.42  6700.3  332.19
#Mann= 14 ,-1 , 0
  3264.5     .05       0    3345     .04       0  3482.9     .05       0
    3639     .04       0  3641.6     .05       0  3965.6     .12       0
  4024.2     .05       0  4286.5     .12       0  4682.5      .1       0
  4696.9     .12       0  4821.1      .1       0  5012.8     .05       0
  5025.3      .1       0  5596.6     .05       0
Bank Sta=5012.8,5025.3
XS Rating Curve= 0 ,0
Exp/Cntr=0.3,0.1

Type RM Length L Ch R = 1 ,136592  ,412,412,412
BEGIN DESCRIPTION:
Mapping XS aecd826f
END DESCRIPTION:
XS GIS Cut Line= 4
      2465571.49     13560873.94      2464486.43     13560656.92
      2463952.92     13559927.19      2462333.19     13559563.34
#Sta/Elev= 30
  2705.7  319.93  2745.2  319.98  2917.7  319.17  3016.5   317.6  3182.1  313.17
  3215.2  312.51    3508  306.16  3805.2  304.58  3815.5   304.9  3877.6  303.85
    3953  303.48    4502  297.99    4703  298.19  4724.3  298.39  4744.4  290.87
  4775.6  295.65  4816.6   291.6  4836.1  298.71  4954.8  296.36  4990.8  294.49
  4994.4  290.01  4994.9  289.51  5007.7  290.01  5019.6  293.83  5062.6  297.88
  5391.7  299.66  5564.8  303.62    5862  330.35  6220.7  330.08  6376.3     333
#Mann= 16 ,-1 , 0
  2705.7     .04       0  2745.2     .05       0  2917.7     .04       0
  3016.5     .05       0  3182.1     .04       0  3215.2     .05       0
    3508     .12       0  3805.2     .05       0  3815.5     .12       0
  3877.6     .05       0    3953     .12       0    4502      .1       0
    4703     .12       0  4954.8     .05       0  4994.4     .05       0
  5007.7     .05       0
Bank Sta=4994.4,5007.7
XS Rating Curve= 0 ,0
Exp/Cntr=0.3,0.1

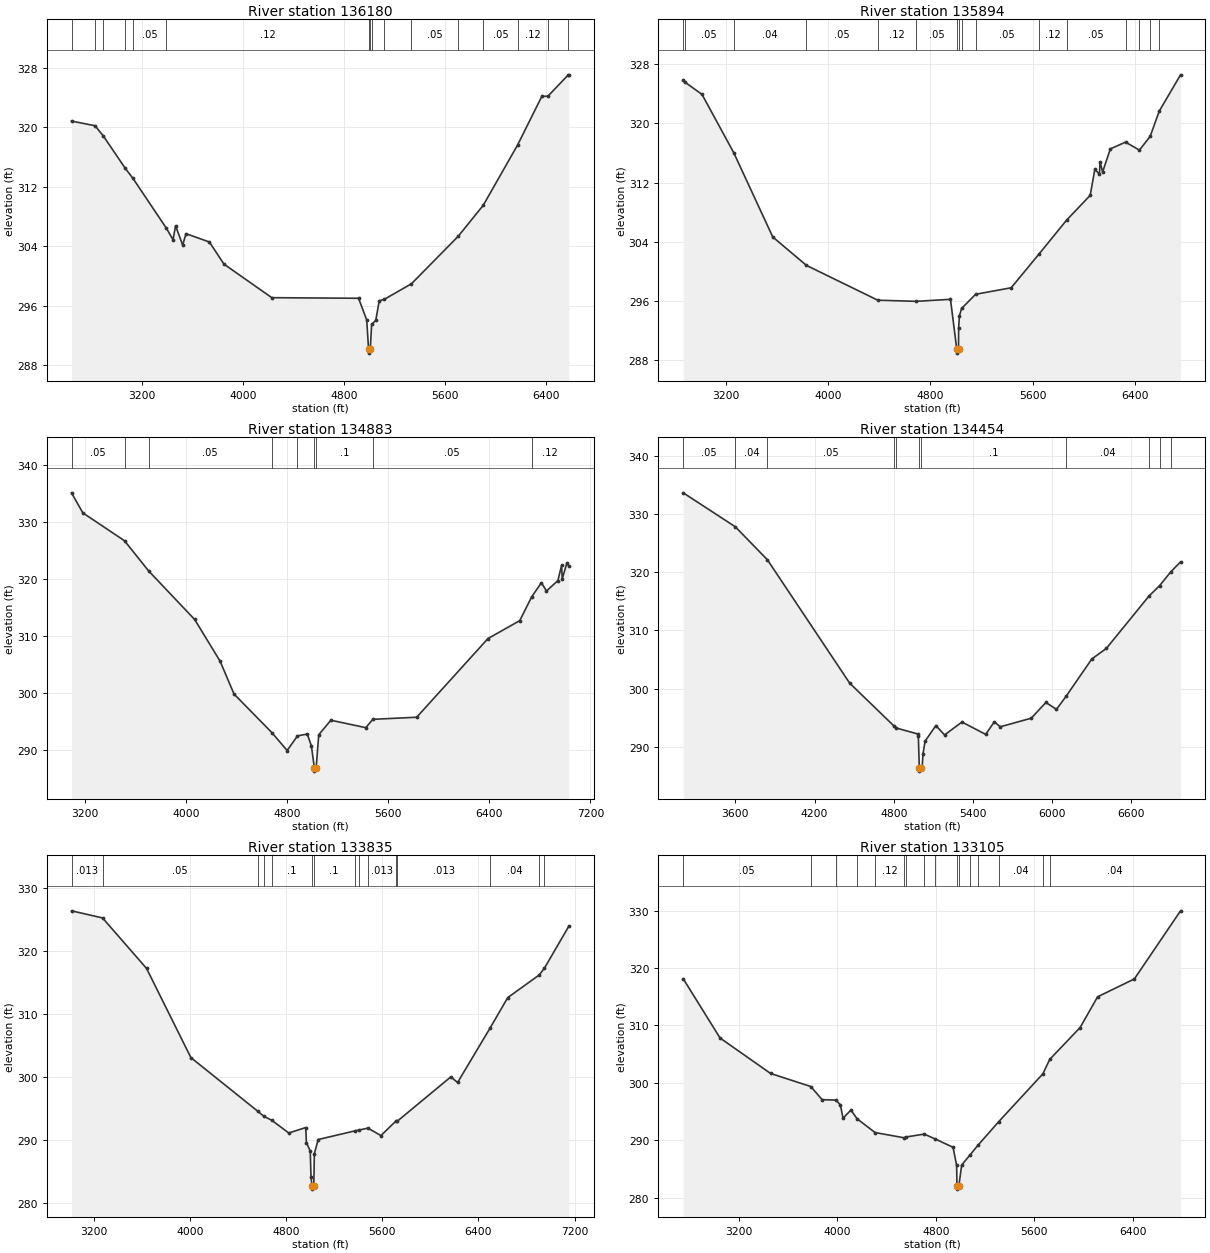
Type RM Length L Ch R = 1 ,136180  ,286,286,286
BEGIN DESCRIPTION:
Mapping XS 6dd37efa
END DESCRIPTION:
XS GIS Cut Line= 5
      2465528.06     13560841.38        2464500.       13560600.
      2463954.74     13559712.91       2463238.6      13558703.8
      2462630.98      13558703.8
#Sta/Elev= 30
  2639.1  320.82  2825.6  320.19  2891.4  318.81    3065  314.46  3125.7  313.12
  3390.4  306.42  3443.5  304.86    3464  306.73  3520.3  304.13  3546.2  305.67
  3731.8  304.55  3847.8  301.57  4226.6  297.06  4914.5  296.98  4979.1  294.06
  4993.9   290.1  4994.4   289.6  5007.3   290.1  5018.1  293.48    5051  294.01
  5078.1  296.63  5119.8  296.85  5333.6  298.93  5703.4   305.3  5902.9  309.49
  6175.1   317.6  6367.4  324.15  6415.3  324.16  6577.1  327.04  6581.4  327.04
#Mann= 16 ,-1 , 0
  2639.1     .05       0  2825.6     .04       0  2891.4     .05       0
    3065     .04       0  3125.7     .05       0  3390.4     .12       0
  4993.9     .05       0  5007.3     .12       0  5018.1     .05       0
  5119.8     .12       0  5333.6     .05       0  5703.4     .12       0
  5902.9     .05       0  6175.1     .12       0  6415.3     .05       0
  6577.1     .12       0
Bank Sta=4993.9,5007.3
XS Rating Curve= 0 ,0
Exp/Cntr=0.3,0.1

Type RM Length L Ch R = 1 ,135894  ,1011,1011,1011
BEGIN DESCRIPTION:
Mapping XS d53923d6
END DESCRIPTION:
XS GIS Cut Line= 5
      2465550.01       13560600.      2464636.69     13560094.85
      2463749.26     13559041.81      2463321.69     13558555.15
      2462511.58     13558443.38
#Sta/Elev= 30
  2869.7  325.78  2880.6  325.57  3016.3  323.89  3264.4  316.02  3569.5  304.65
  3832.5  300.82  4390.1  296.12  4690.6  295.97  4958.2  296.24  5007.5  289.48
    5008  288.98  5020.9  289.48  5021.9  292.42  5028.4  294.04  5045.1  295.01
  5154.5  296.92  5432.7   297.8  5649.5  302.34  5865.8  306.93  6050.1  310.27
  6086.4   313.8    6122  313.11  6127.1   314.8    6147  313.42  6207.5  316.54
  6326.4  317.45  6434.8  316.37  6518.8  318.23  6589.8  321.64  6756.1  326.53
#Mann= 16 ,-1 , 0
  2869.7     .03       0  2880.6     .05       0  3264.4     .04       0
  3832.5     .05       0  4390.1     .12       0  4690.6     .05       0
  5007.5     .05       0  5020.9     .05       0  5045.1     .12       0
  5154.5     .05       0  5649.5     .12       0  5865.8     .05       0
  6326.4     .12       0  6434.8     .05       0  6518.8     .12       0
  6589.8     .05       0
Bank Sta=5007.5,5020.9
XS Rating Curve= 0 ,0
Exp/Cntr=0.3,0.1

Type RM Length L Ch R = 1 ,134883  ,429,429,429
BEGIN DESCRIPTION:
Mapping XS b307d06a
END DESCRIPTION:
XS GIS Cut Line= 4
      2466217.77     13559402.75      2464598.86     13558526.02
      2464186.53     13558430.54      2462529.31     13558243.99
#Sta/Elev= 30
  3096.8  335.07  3185.9  331.57  3515.7  326.68  3707.2  321.38  4070.4   312.9
  4271.3  305.61  4381.4  299.86  4680.4  293.11  4801.8  289.97  4883.2  292.53
  4960.9  292.85  4993.2  290.79  5017.2  286.86  5017.7  286.36  5030.7  286.86
  5051.4  292.72  5147.1  295.27    5423  293.97  5479.7  295.43  5825.6  295.79
  6389.1  309.56  6640.7   312.7    6735  316.87  6811.7  319.34    6852  317.89
  6942.6  319.72  6971.4  322.39  6976.4     320    7013  322.77  7028.8  322.29
#Mann= 9 ,-1 , 0
  3096.8     .05       0  3515.7     .04       0  3707.2     .05       0
  4680.4     .12       0  4883.2      .1       0  5017.2     .05       0
  5030.7      .1       0  5479.7     .05       0    6735     .12       0
Bank Sta=5017.2,5030.7
XS Rating Curve= 0 ,0
Exp/Cntr=0.3,0.1

Type RM Length L Ch R = 1 ,134454  ,619,619,619
BEGIN DESCRIPTION:
Mapping XS bb7d15a7
END DESCRIPTION:
XS GIS Cut Line= 3
      2466191.71     13559268.19      2464763.79     13558161.44
      2463036.38     13557232.63
#Sta/Elev= 30
  3205.1  333.65  3599.3  327.82  3842.8  322.14  4466.1  300.93  4801.9  293.56
  4816.7  293.23    4980   292.2  4986.3  291.84  4993.9   286.3  4994.4   285.8
  5007.7   286.3  5015.4   286.5  5021.7  288.76  5037.3  290.94  5119.3  293.64
    5185  292.02  5316.9  294.24  5496.7  292.12  5562.4   294.3  5606.2  293.42
  5841.6   294.9  5952.7   297.6  6033.1  296.43  6105.2  298.65  6300.9  305.09
  6410.5  306.89  6734.2  315.91  6815.1  317.71  6900.3   320.1    6973  321.77
#Mann= 11 ,-1 , 0
  3205.1     .05       0  3599.3     .04       0  3842.8     .05       0
  4801.9     .12       0  4816.7      .1       0  4993.9     .05       0
  5007.7      .1       0  6105.2     .04       0  6734.2    .013       0
  6815.1     .05       0  6900.3     .04       0
Bank Sta=4993.9,5007.7
XS Rating Curve= 0 ,0
Exp/Cntr=0.3,0.1

Type RM Length L Ch R = 1 ,133835  ,730,730,730
BEGIN DESCRIPTION:
Mapping XS fd95f23d
END DESCRIPTION:
XS GIS Cut Line= 4
      2466275.95     13558876.72       2464956.5     13557682.27
      2464067.61     13557196.16       2463095.4     13556265.61
#Sta/Elev= 30
  3013.3  326.36  3271.5  325.23    3638   317.2  4006.4  303.05  4562.8  294.53
  4615.1   293.7  4679.2   293.1    4821  291.07  4962.3  291.93    4968  289.54
    5000   288.2    5006  284.14  5014.8  282.65  5015.3  282.15  5029.3  282.65
  5034.2  287.77  5065.7  290.03  5369.1  291.39  5405.7  291.54  5479.5  291.84
  5588.4  290.66  5716.2  293.03  5725.5  292.96  6169.7  299.98  6226.1  299.09
    6495  307.69  6643.4  312.57  6905.3  316.17  6948.7  317.25    7152  323.92
#Mann= 15 ,-1 , 0
  3013.3    .013       0  3271.5     .05       0  4562.8      .1       0
  4615.1     .05       0  4679.2      .1       0  5014.8     .05       0
  5029.3      .1       0  5369.1    .013       0  5405.7     .12       0
  5479.5    .013       0  5716.2     .12       0  5725.5    .013       0
    6495     .04       0  6905.3    .013       0  6948.7     .04       0
Bank Sta=5014.8,5029.3
XS Rating Curve= 0 ,0
Exp/Cntr=0.3,0.1

Type RM Length L Ch R = 1 ,133105  ,702,702,702
BEGIN DESCRIPTION:
Mapping XS c77be9ac
END DESCRIPTION:
XS GIS Cut Line= 4
      2466400.97     13558140.63      2465164.83     13557050.33
      2463935.67     13556793.38      2463060.64     13556071.14
#Sta/Elev= 30
  2748.8  318.13  3047.8  307.81  3458.5  301.63  3784.5  299.36  3876.8  297.07
  3989.7  296.99  4024.9  296.15  4046.7  293.83  4110.2  295.26    4161  293.73
  4306.7  291.34  4541.6  290.43  4557.8  290.56  4705.9  291.07  4791.9  290.25
  4939.9  288.77    4969  285.61  4971.9  281.98  4972.4  281.48  4986.5  281.98
  5009.9  285.67  5076.4  287.41  5143.6  289.16  5311.4  293.25  5669.4  301.57
  5725.2  304.09  5971.8  309.64  6113.8  314.99  6412.2   318.1  6787.4  329.97
#Mann= 16 ,-1 , 0
  2748.8     .05       0  3784.5      .1       0  3989.7     .12       0
    4161     .05       0  4306.7     .12       0  4541.6     .05       0
  4557.8     .12       0  4705.9     .05       0  4791.9      .1       0
  4971.9     .05       0  4986.5      .1       0  5076.4     .12       0
  5143.6      .1       0  5311.4     .04       0  5669.4    .013       0
  5725.2     .04       0
Bank Sta=4971.9,4986.5
XS Rating Curve= 0 ,0
Exp/Cntr=0.3,0.1

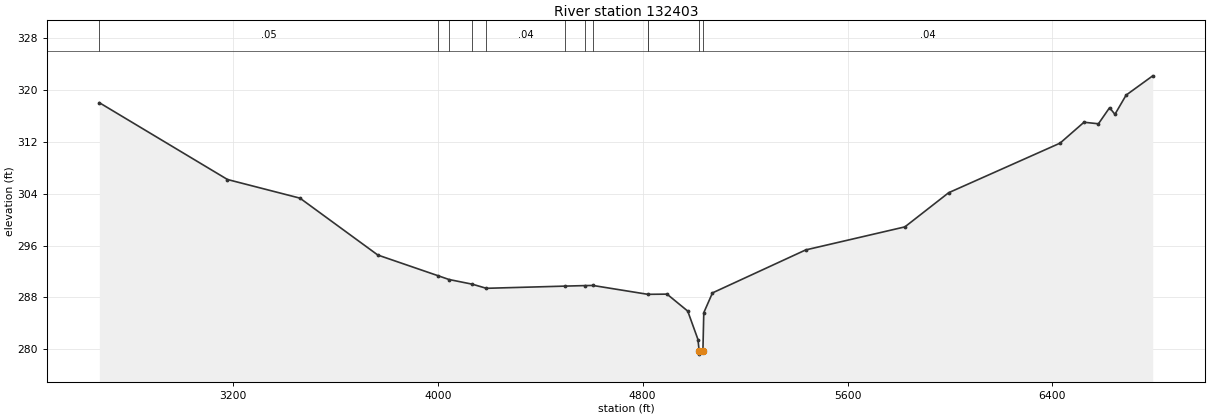
Type RM Length L Ch R = 1 ,132403  ,615,615,615
BEGIN DESCRIPTION:
Mapping XS b8ef2555
END DESCRIPTION:
XS GIS Cut Line= 4
      2466498.13     13557779.46      2465303.72     13556619.77
      2464130.11     13556064.22      2463213.57     13555369.87
#Sta/Elev= 30
  2678.7  318.07  3179.1   306.2  3462.1  303.32  3766.1  294.53  4002.3  291.32
    4044  290.75  4135.6  290.02  4189.8  289.39  4498.3  289.73  4575.3  289.81
  4605.6  289.83  4820.4  288.46  4895.3  288.49  4976.1  285.87  5016.1  281.48
  5020.7  279.72  5021.2  279.22  5035.4  279.72  5038.8  285.62  5072.7  288.68
  5436.7  295.32    5824  298.88    5995  304.16  6429.9  311.82  6523.4  315.05
  6579.7  314.81  6623.3   317.3  6644.1  316.27  6687.8  319.24  6791.8  322.22
#Mann= 12 ,-1 , 0
  2678.7     .05       0  4002.3      .1       0    4044     .05       0
  4135.6      .1       0  4189.8     .04       0  4498.3     .05       0
  4575.3     .04       0  4605.6     .05       0  4820.4      .1       0
  4820.4    .013       0  5020.7     .03       0  5035.4     .04       0
Bank Sta=5020.7,5035.4
XS Rating Curve= 0 ,0
Exp/Cntr=0.3,0.1