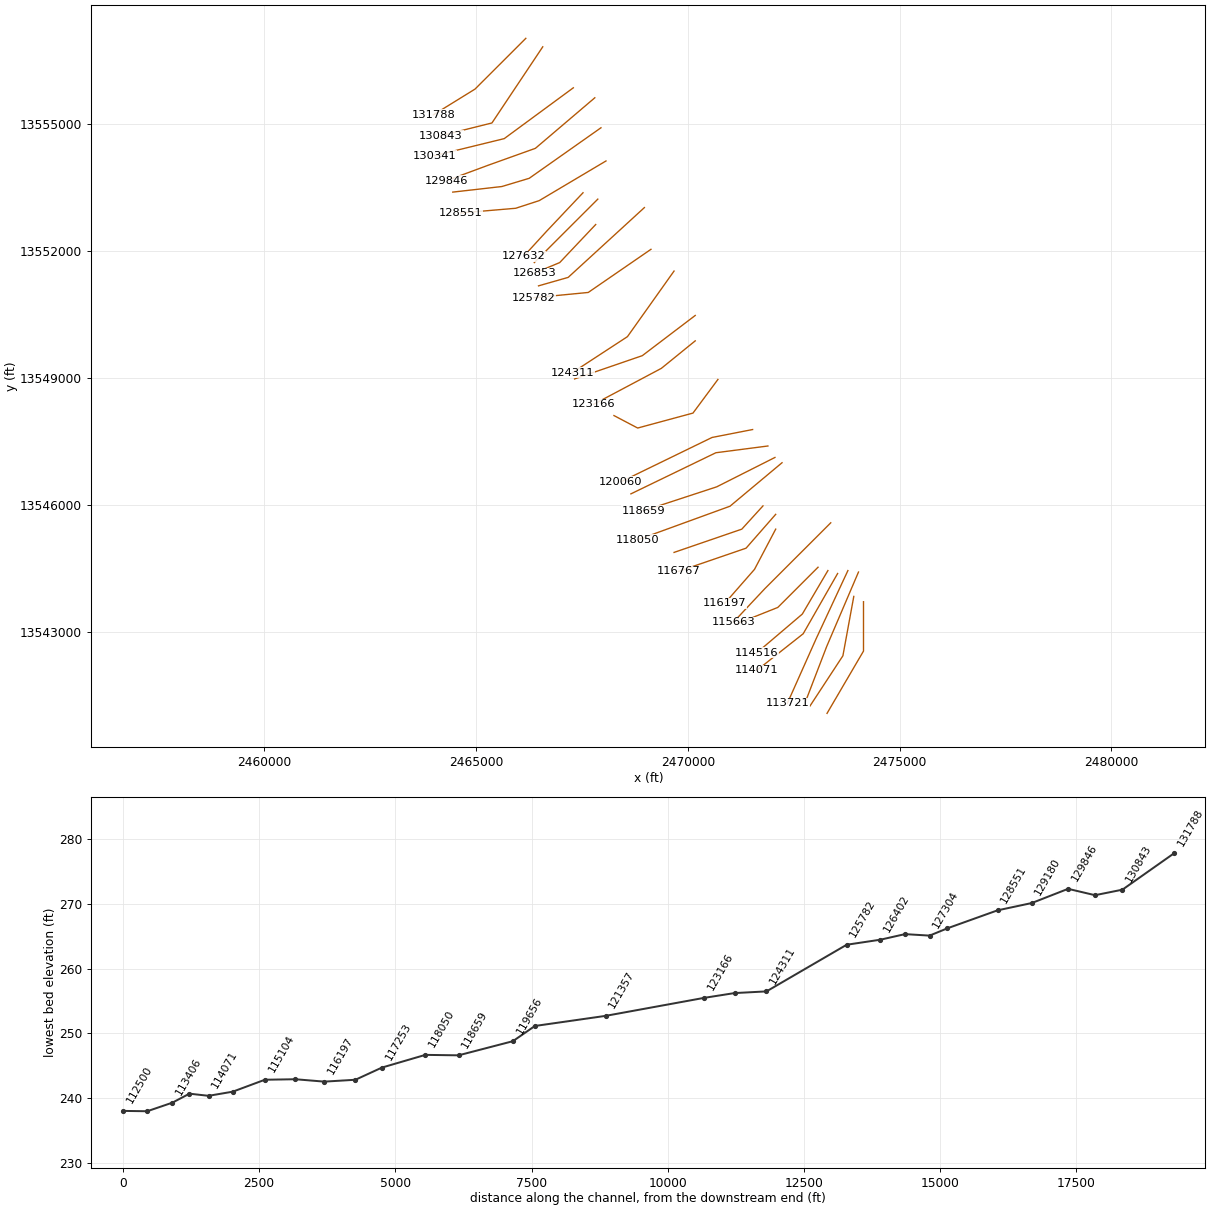
HEC-RAS study TWELVEMILE CREEK.prj: TWELVEMILE CREEK Base Level Engineering

--- TWELVEMILE CREEK.g01 (geometry) --- (continued)

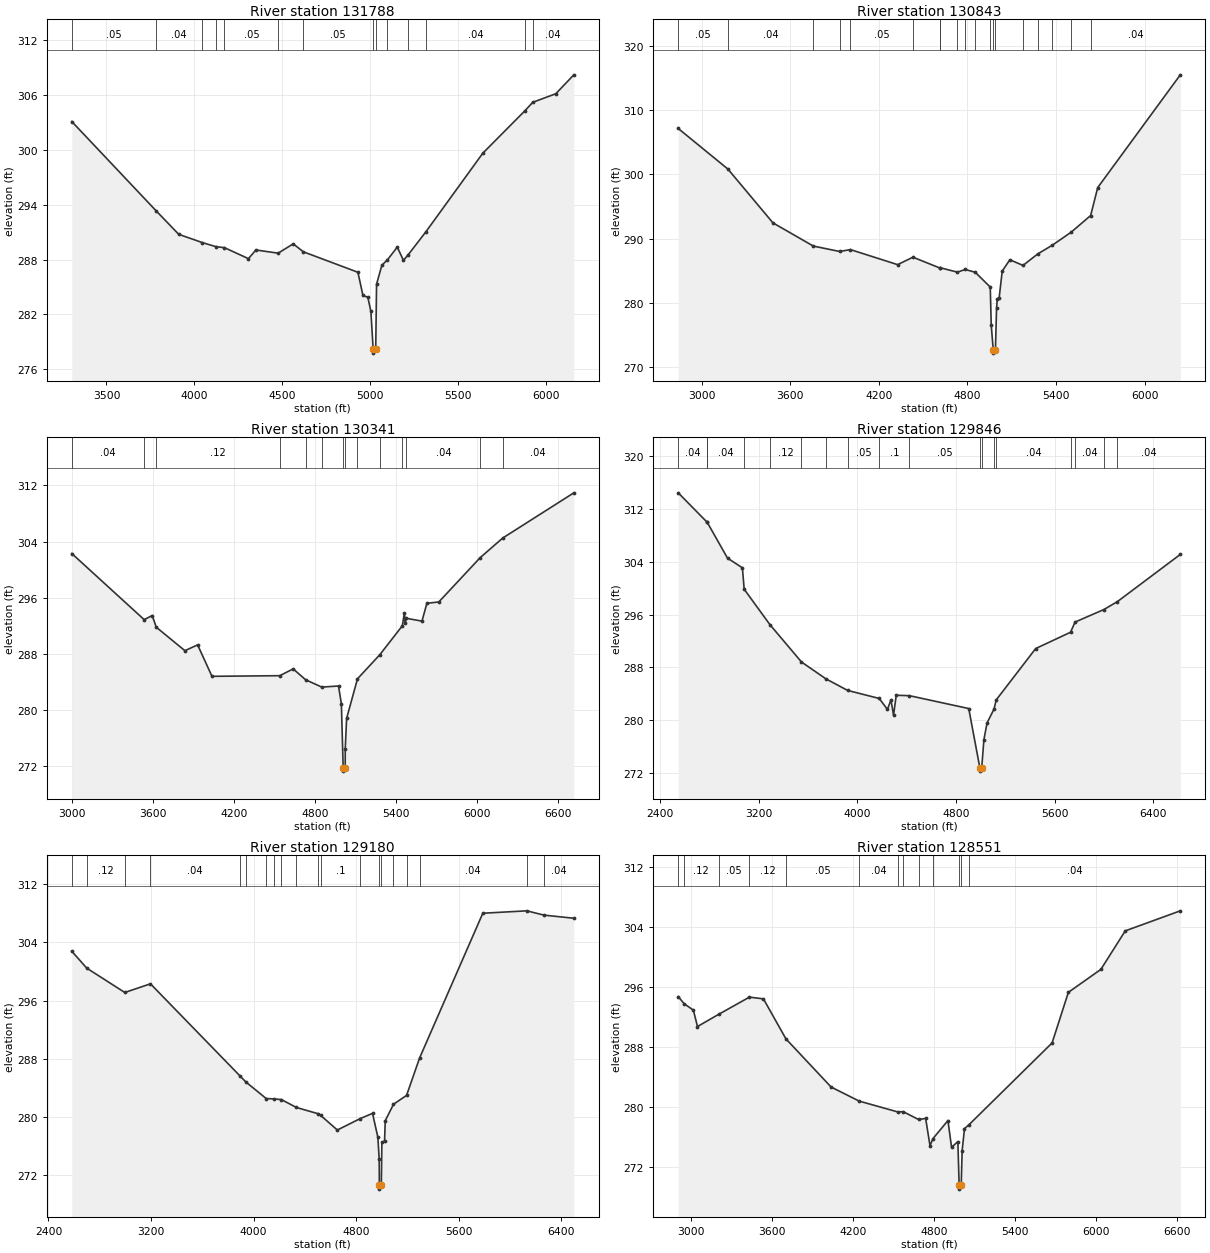
Type RM Length L Ch R = 1 ,131788  ,945,945,945
BEGIN DESCRIPTION:
COTTONWOOD CREEK 15.0
END DESCRIPTION:
XS GIS Cut Line= 3
      2466174.98     13557024.98        2464975.       13555825.
      2463991.25     13555217.01
#Sta/Elev= 30
  3302.7  303.12  3781.9  293.35  3910.8  290.77  4044.9  289.87  4120.7  289.43
  4170.7  289.31  4306.8  288.11  4349.2  289.06  4475.6  288.71  4561.3  289.73
    4619  288.86    4929  286.62  4957.3   284.1  4985.6  283.87  5002.7  282.33
  5015.4  278.27  5015.9  277.77  5030.2  278.27    5035  285.32  5065.3   287.4
  5095.5  287.95  5152.6  289.37  5187.8  287.93  5212.1  288.47  5316.5  291.08
  5638.7  299.65  5878.3   304.3  5922.5  305.22  6053.6  306.16  6156.2  308.23
#Mann= 14 ,-1 , 0
  3302.7     .05       0  3781.9     .04       0  4044.9     .05       0
  4120.7     .04       0  4170.7     .05       0  4475.6    .013       0
    4619     .05       0  5015.4     .05       0  5030.2     .05       0
  5095.5     .12       0  5212.1     .05       0  5316.5     .04       0
  5878.3     .05       0  5922.5     .04       0
Bank Sta=5015.4,5030.2
XS Rating Curve= 0 ,0
Exp/Cntr=0.3,0.1

Type RM Length L Ch R = 1 ,130843  ,502,502,502
BEGIN DESCRIPTION:
COTTONWOOD CREEK 13.0
END DESCRIPTION:
XS GIS Cut Line= 3
      2466574.99     13556824.98        2465375.       13555025.
      2464175.04     13554725.01
#Sta/Elev= 30
  2841.9  307.13  3178.5  300.81  3483.4  292.44  3756.8  288.83  3934.8  287.99
  4008.3  288.28  4327.7  285.94  4431.5   287.1  4612.1  285.43    4615  285.46
  4732.9  284.77    4785  285.19  4853.6  284.75    4955  282.45  4961.6  276.54
  4975.2  272.67  4975.7  272.17  4990.1  272.67  4997.7  279.16  5002.2  280.52
  5015.5  280.82  5036.1  284.94  5087.7   286.7  5176.8  285.82  5277.5  287.62
    5375  288.96  5503.4     291  5634.8  293.58  5682.9  297.94  6242.1  315.48
#Mann= 19 ,-1 , 0
  2841.9     .05       0  3178.5     .04       0  3756.8     .05       0
  3934.8    .013       0  4008.3     .05       0  4431.5    .013       0
  4612.1     .05       0    4615     .12       0  4732.9      .1       0
    4785     .05       0  4853.6      .1       0    4955     .05       0
  4975.2     .05       0  4990.1     .05       0  5176.8     .12       0
  5277.5     .05       0    5375     .04       0  5503.4     .05       0
  5634.8     .04       0
Bank Sta=4975.2,4990.1
XS Rating Curve= 0 ,0
Exp/Cntr=0.3,0.1

Type RM Length L Ch R = 1 ,130341  ,495,495,495
BEGIN DESCRIPTION:
Mapping XS 7864001b
END DESCRIPTION:
XS GIS Cut Line= 3
      2467296.75     13555855.87      2465664.83     13554654.49
      2464019.53     13554251.84
#Sta/Elev= 30
  2995.8  302.31  3532.4  292.89  3591.9  293.48  3621.6  291.82  3834.2  288.47
  3928.3   289.3  4034.7  284.82    4537  284.91  4636.4  285.88  4728.6  284.33
  4848.2  283.29  4972.4  283.44  4993.5   280.9  5006.9  271.82  5007.4  271.32
  5021.9  271.82  5022.2  274.49  5032.4  278.83    5113  284.47  5278.1  287.89
  5445.4  292.02  5460.7  293.87  5465.9  292.35  5475.9  293.08  5590.7  292.68
  5627.2  295.22  5715.6  295.41  6022.6  301.73    6189  304.51  6716.1  310.95
#Mann= 14 ,-1 , 0
  2995.8     .04       0  3532.4    .013       0  3621.6     .12       0
    4537     .05       0  4728.6    .013       0  4848.2      .1       0
  5006.9     .05       0  5021.9      .1       0    5113     .05       0
  5278.1     .04       0  5445.4     .05       0  5475.9     .04       0
  6022.6     .05       0    6189     .04       0
Bank Sta=5006.9,5021.9
XS Rating Curve= 0 ,0
Exp/Cntr=0.3,0.1

Type RM Length L Ch R = 1 ,129846  ,666,666,666
BEGIN DESCRIPTION:
Mapping XS 1184c564
END DESCRIPTION:
XS GIS Cut Line= 4
      2467803.71     13555619.76      2466400.94     13554425.33
      2465296.78     13554029.49      2464303.76     13553661.45
#Sta/Elev= 30
  2545.7  314.42  2780.7  309.96  2781.2  309.95  2945.5  304.54  3066.3  303.07
  3080.9  299.83  3289.4  294.48  3545.7  288.82    3744  286.27  3920.8  284.51
  4176.4   283.3  4243.5  281.64    4272  283.08  4292.9  280.76  4314.9  283.78
  4421.6  283.72  4903.3  281.77  4993.3   272.8  4993.8   272.3  5008.4   272.8
  5026.3  277.06  5051.8  279.59  5108.2  281.69  5126.6  283.09  5446.2  290.85
  5729.3  293.32    5766  294.86  6000.3  296.76    6110  297.96  6620.1   305.1
#Mann= 18 ,-1 , 0
  2545.7     .04       0  2780.7     .05       0  2781.2     .04       0
  3080.9    .013       0  3289.4     .12       0  3545.7     .05       0
    3744     .12       0  3920.8     .05       0  4176.4      .1       0
  4421.6     .05       0  4993.3     .05       0  5008.4     .05       0
  5108.2      .1       0  5126.6     .04       0  5729.3     .05       0
    5766     .04       0  6000.3     .05       0    6110     .04       0
Bank Sta=4993.3,5008.4
XS Rating Curve= 0 ,0
Exp/Cntr=0.3,0.1

Type RM Length L Ch R = 1 ,129180  ,629,629,629
BEGIN DESCRIPTION:
Mapping XS 5b08462f
END DESCRIPTION:
XS GIS Cut Line= 4
      2467949.52     13554911.41      2466255.11     13553716.99
      2465609.28     13553522.55       2464449.8     13553390.63
#Sta/Elev= 30
  2581.8   302.8  2698.3  300.48  2995.2  297.13  3195.3  298.32    3893  285.67
  3940.1  284.82  4097.6  282.56    4159   282.5  4215.5  282.42  4333.5  281.33
  4504.6  280.46  4521.8  280.25  4652.3  278.23  4830.3   279.8  4926.8  280.52
  4968.3  277.24  4978.7  274.19    4980  270.61  4980.5  270.11  4995.2  270.61
  4999.6  276.56  5020.5   276.7  5025.9  279.51  5090.2  281.77  5192.1  282.99
  5293.9  288.14  5786.6  308.02  6129.6  308.35  6263.4  307.76  6496.3  307.33
#Mann= 20 ,-1 , 0
  2581.8     .05       0  2698.3     .12       0  2995.2     .05       0
  3195.3     .04       0    3893    .013       0  3940.1     .04       0
  4097.6     .05       0    4159     .04       0  4215.5     .05       0
  4333.5      .1       0  4504.6     .05       0  4521.8      .1       0
  4830.3     .05       0    4980     .05       0  4995.2      .1       0
  5090.2    .013       0  5192.1      .1       0  5293.9     .04       0
  6129.6     .05       0  6263.4     .04       0
Bank Sta=4980,4995.2
XS Rating Curve= 0 ,0
Exp/Cntr=0.3,0.1

Type RM Length L Ch R = 1 ,128551  ,919,919,919
BEGIN DESCRIPTION:
Mapping XS 6a5dbb6b
END DESCRIPTION:
XS GIS Cut Line= 4
      2468067.59      13554126.7      2466491.22     13553189.22
      2465935.67     13553008.66      2464638.54     13552897.68
#Sta/Elev= 30
  2903.7  294.73  2946.9  293.78  3015.9  292.91  3046.3  290.72  3202.2  292.34
  3430.9  294.65    3535  294.42  3701.7  289.07  4036.5  282.63  4244.4  280.75
  4528.6  279.31  4571.6  279.33  4684.2  278.29    4737  278.43  4769.1  274.79
  4791.4  275.74  4902.1  278.15  4928.8  274.58  4975.6  275.33  4985.1  269.48
  4985.6  268.98  5000.4  269.48  5007.2  274.11  5024.7  277.07  5058.5   277.6
  5673.9  288.53  5794.3  295.29  6035.2  298.36  6215.9  303.51  6623.8  306.19
#Mann= 13 ,-1 , 0
  2903.7     .05       0  2946.9     .12       0  3202.2     .05       0
  3430.9     .12       0  3701.7     .05       0  4244.4     .04       0
  4528.6     .05       0  4571.6     .04       0  4684.2    .013       0
  4791.4      .1       0  4985.1     .05       0  5000.4      .1       0
  5058.5     .04       0
Bank Sta=4985.1,5000.4
XS Rating Curve= 0 ,0
Exp/Cntr=0.3,0.1

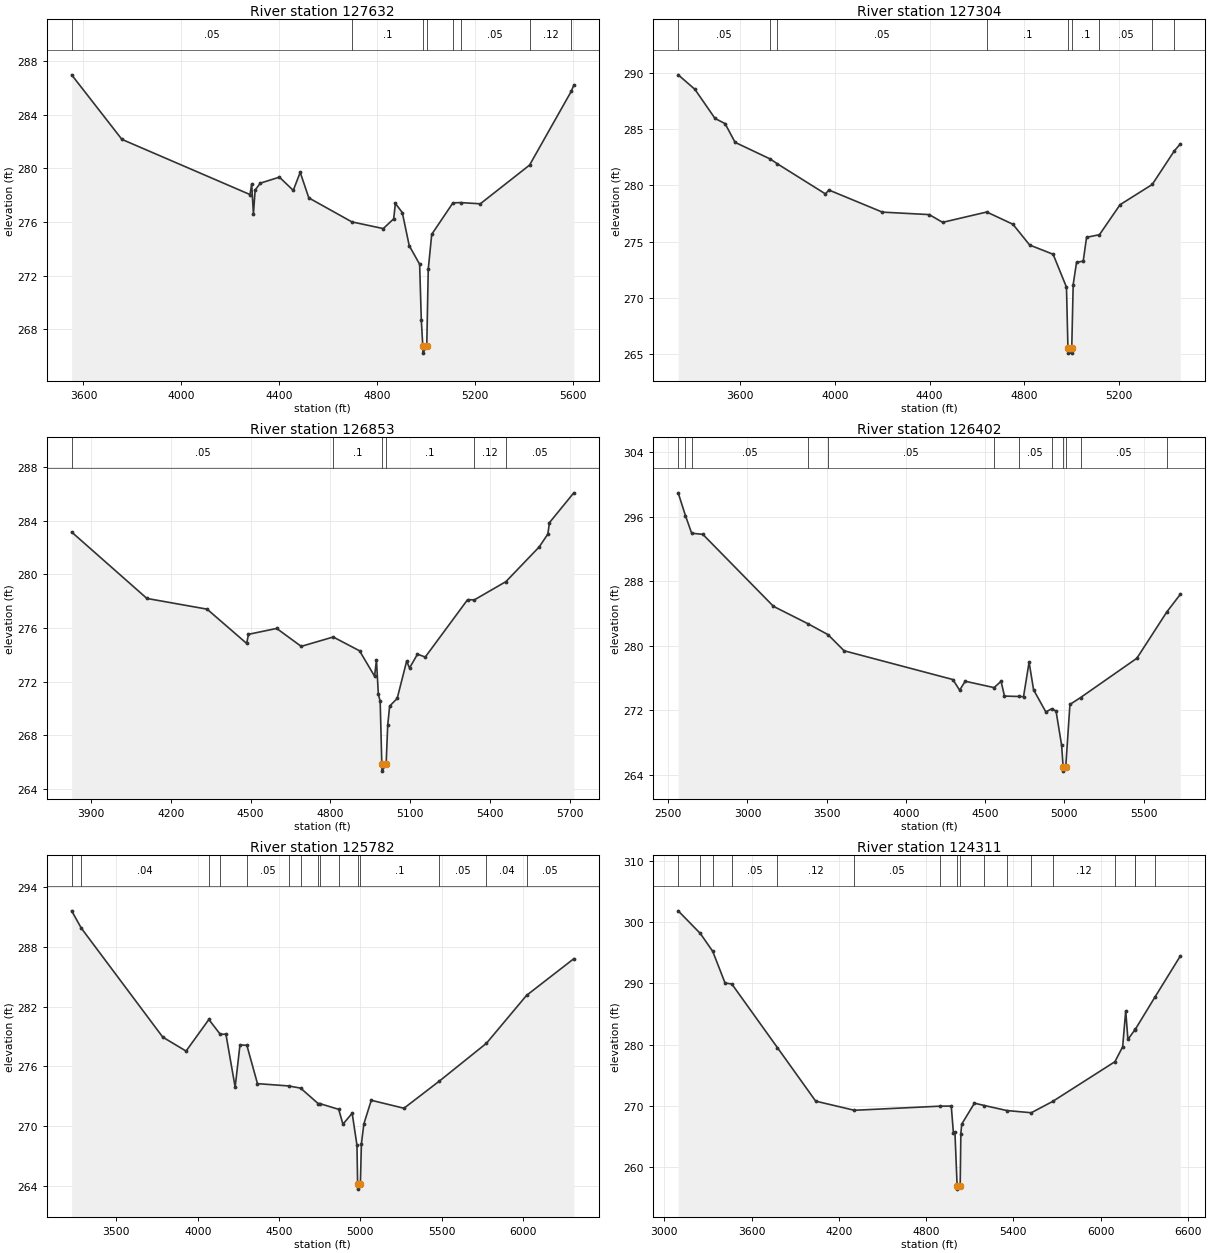
Type RM Length L Ch R = 1 ,127632  ,328,328,328
BEGIN DESCRIPTION:
COTTONWOOD CREEK 6.0
END DESCRIPTION:
XS GIS Cut Line= 3
      2467525.03     13553375.03        2466675.       13552475.
      2466125.02     13551875.02
#Sta/Elev= 30
  3551.7  286.99  3757.1  282.17  4280.6  278.05  4287.4  278.84  4294.5  276.59
  4301.6  278.39  4322.6   278.9  4400.7  279.35  4457.3  278.36  4485.7  279.71
  4520.9   277.8  4696.7  276.01  4825.1  275.51  4867.7  276.24  4874.5  277.39
  4902.8  276.71  4931.2  274.23  4973.7  272.85  4980.5  268.72  4986.7  266.71
  4987.2  266.21  5002.8  266.71  5008.9  272.47  5023.1  275.08  5109.8  277.43
  5142.1  277.45  5221.6  277.36  5422.9  280.25  5593.3  285.76  5603.6  286.22
#Mann= 8 ,-1 , 0
  3551.7     .05       0  4696.7      .1       0  4986.7     .05       0
  5002.8      .1       0  5109.8     .04       0  5142.1     .05       0
  5422.9     .12       0  5593.3     .05       0
Bank Sta=4986.7,5002.8
XS Rating Curve= 0 ,0
Exp/Cntr=0.3,0.1

Type RM Length L Ch R = 1 ,127304  ,451,451,451
BEGIN DESCRIPTION:
COTTONWOOD CREEK 5.0
END DESCRIPTION:
XS GIS Cut Line= 3
      2467875.03     13553225.03        2466675.       13552025.
      2466374.97     13551724.97
#Sta/Elev= 30
  3338.2  289.85  3408.9  288.56  3493.8  285.97  3536.2  285.51  3578.7  283.84
  3727.1  282.36  3757.3  281.93  3960.5  279.25  3974.6   279.6  4200.9  277.63
  4398.9  277.41  4455.5  276.72  4641.9  277.64  4752.5  276.55  4823.2   274.7
  4922.2  273.88  4978.7  270.95  4984.8  265.58  4985.3  265.08  5000.5  265.08
    5001  265.58    5007  271.18  5021.2  273.16  5049.4  273.27  5063.6  275.39
    5118  275.62    5205  278.29  5340.9  280.09    5434  283.07  5459.6   283.7
#Mann= 9 ,-1 , 0
  3338.2     .05       0  3727.1     .12       0  3757.3     .05       0
  4641.9      .1       0  4984.8     .05       0    5001      .1       0
    5118     .05       0  5340.9     .12       0    5434     .05       0
Bank Sta=4984.8,5001
XS Rating Curve= 0 ,0
Exp/Cntr=0.3,0.1

Type RM Length L Ch R = 1 ,126853  ,451,451,451
BEGIN DESCRIPTION:
COTTONWOOD CREEK 4.0
END DESCRIPTION:
XS GIS Cut Line= 3
      2467825.03     13552625.04        2466975.       13551725.
      2466374.99       13551475.
#Sta/Elev= 30
  3827.2  283.17  4110.2  278.21  4336.4  277.41  4485.3  274.85  4492.1  275.53
  4598.1  275.97  4690.4  274.63  4810.7  275.33  4909.6   274.3  4966.3   272.4
  4973.2  273.62  4980.4  271.05  4987.3  270.52  4993.4  265.81  4993.9  265.31
  5009.6  265.81  5015.6  268.75  5022.9  270.17  5051.2  270.74  5086.9  273.53
  5097.7  273.01  5127.5  274.05  5156.7  273.83    5316  278.12  5341.1   278.1
  5460.2  279.47  5585.2  282.06  5617.7  283.02  5623.6  283.87  5715.2   286.1
#Mann= 6 ,-1 , 0
  3827.2     .05       0  4810.7      .1       0  4993.4     .05       0
  5009.6      .1       0  5341.1     .12       0  5460.2     .05       0
Bank Sta=4993.4,5009.6
XS Rating Curve= 0 ,0
Exp/Cntr=0.3,0.1

Type RM Length L Ch R = 1 ,126402  ,620,620,620
BEGIN DESCRIPTION:
COTTONWOOD CREEK 3.0
END DESCRIPTION:
XS GIS Cut Line= 3
      2468975.03     13553025.03        2467175.       13551375.
      2466474.98     13551174.99
#Sta/Elev= 30
  2562.4  298.97  2608.4  296.14  2647.5  293.96  2718.1  293.82    3164  284.89
  3381.1  282.74  3508.3  281.38  3609.8  279.38  4296.7  275.81  4339.2  274.49
  4374.4   275.6  4556.6  274.81  4600.7  275.59  4622.3  273.76  4712.7  273.71
  4742.5  273.68  4777.7  277.97    4806  274.54  4883.7  271.78  4919.2  272.18
  4947.8  271.91    4983  267.66  4992.7  264.95  4993.2  264.45    5009  264.95
  5035.5  272.72    5103  273.58    5458  278.45  5647.6  284.21  5732.3  286.38
#Mann= 12 ,-1 , 0
  2562.4     .05       0  2608.4     .04       0  2647.5     .05       0
  3381.1     .12       0  3508.3     .05       0  4556.6      .1       0
  4712.7     .05       0  4919.2      .1       0  4992.7     .05       0
    5009      .1       0    5103     .05       0  5647.6     .04       0
Bank Sta=4992.7,5009
XS Rating Curve= 0 ,0
Exp/Cntr=0.3,0.1

Type RM Length L Ch R = 1 ,125782  ,1471,1471,1471
BEGIN DESCRIPTION:
COTTONWOOD CREEK 2.0
END DESCRIPTION:
XS GIS Cut Line= 3
      2469129.98     13552038.74      2467648.78      13551018.9
       2466365.6     13550894.85
#Sta/Elev= 30
  3224.9  291.61  3284.3  289.87  3785.2  278.93  3928.5  277.53  4068.6   280.7
  4139.3   279.2  4173.4  279.24  4230.2  273.91    4260  278.16  4302.4   278.1
  4367.5  274.26  4559.3  274.03  4632.8  273.81  4740.6  272.26  4749.9  272.26
    4867  271.68    4893  270.19  4949.8  271.29  4979.3  268.07  4983.3  264.17
  4983.8  263.67  5000.2  264.17  5006.6  268.21  5021.5  270.21  5067.2  272.59
  5268.2  271.79  5486.1  274.52  5775.2  278.31  6021.9  283.12  6312.4   286.8
#Mann= 15 ,-1 , 0
  3224.9     .05       0  3284.3     .04       0  4068.6     .05       0
  4139.3     .04       0  4302.4     .05       0  4559.3    .013       0
  4632.8     .05       0  4740.6    .013       0  4749.9     .05       0
    4867      .1       0  4983.3     .05       0  5000.2      .1       0
  5486.1     .05       0  5775.2     .04       0  6021.9     .05       0
Bank Sta=4983.3,5000.2
XS Rating Curve= 0 ,0
Exp/Cntr=0.3,0.1

Type RM Length L Ch R = 1 ,124311  ,586,586,586
BEGIN DESCRIPTION:
WOODS CREEK 3.0
END DESCRIPTION:
XS GIS Cut Line= 3
      2469674.99     13551524.99        2468575.       13549975.
      2467274.97     13549124.98
#Sta/Elev= 30
  3094.9  301.83  3247.2  298.14  3332.7  295.22  3417.2  290.07  3463.7  289.91
  3777.6  279.53  4040.9  270.81  4306.9  269.32  4893.3  269.99  4973.4  270.01
  4988.2   265.6  4998.5  265.77  5013.7  256.97  5014.2  256.47  5034.7  256.97
  5039.3  265.53  5045.3  267.07  5132.8  270.48  5201.1   270.1  5355.2  269.28
  5523.7  268.92  5671.3  270.77  6099.1  277.24  6152.2  279.67  6173.3  285.54
  6188.4  280.87  6236.8  282.45  6239.3  282.52  6375.6  287.82  6548.8  294.46
#Mann= 17 ,-1 , 0
  3094.9     .04       0  3247.2     .05       0  3332.7    .013       0
  3463.7     .05       0  3777.6     .12       0  4306.9     .05       0
  4893.3      .1       0  5013.7     .05       0  5034.7      .1       0
  5201.1     .05       0  5355.2     .12       0  5523.7     .05       0
  5671.3     .12       0  6099.1     .05       0  6236.8     .12       0
  6239.3     .05       0  6375.6     .12       0
Bank Sta=5013.7,5034.7
XS Rating Curve= 0 ,0
Exp/Cntr=0.3,0.1

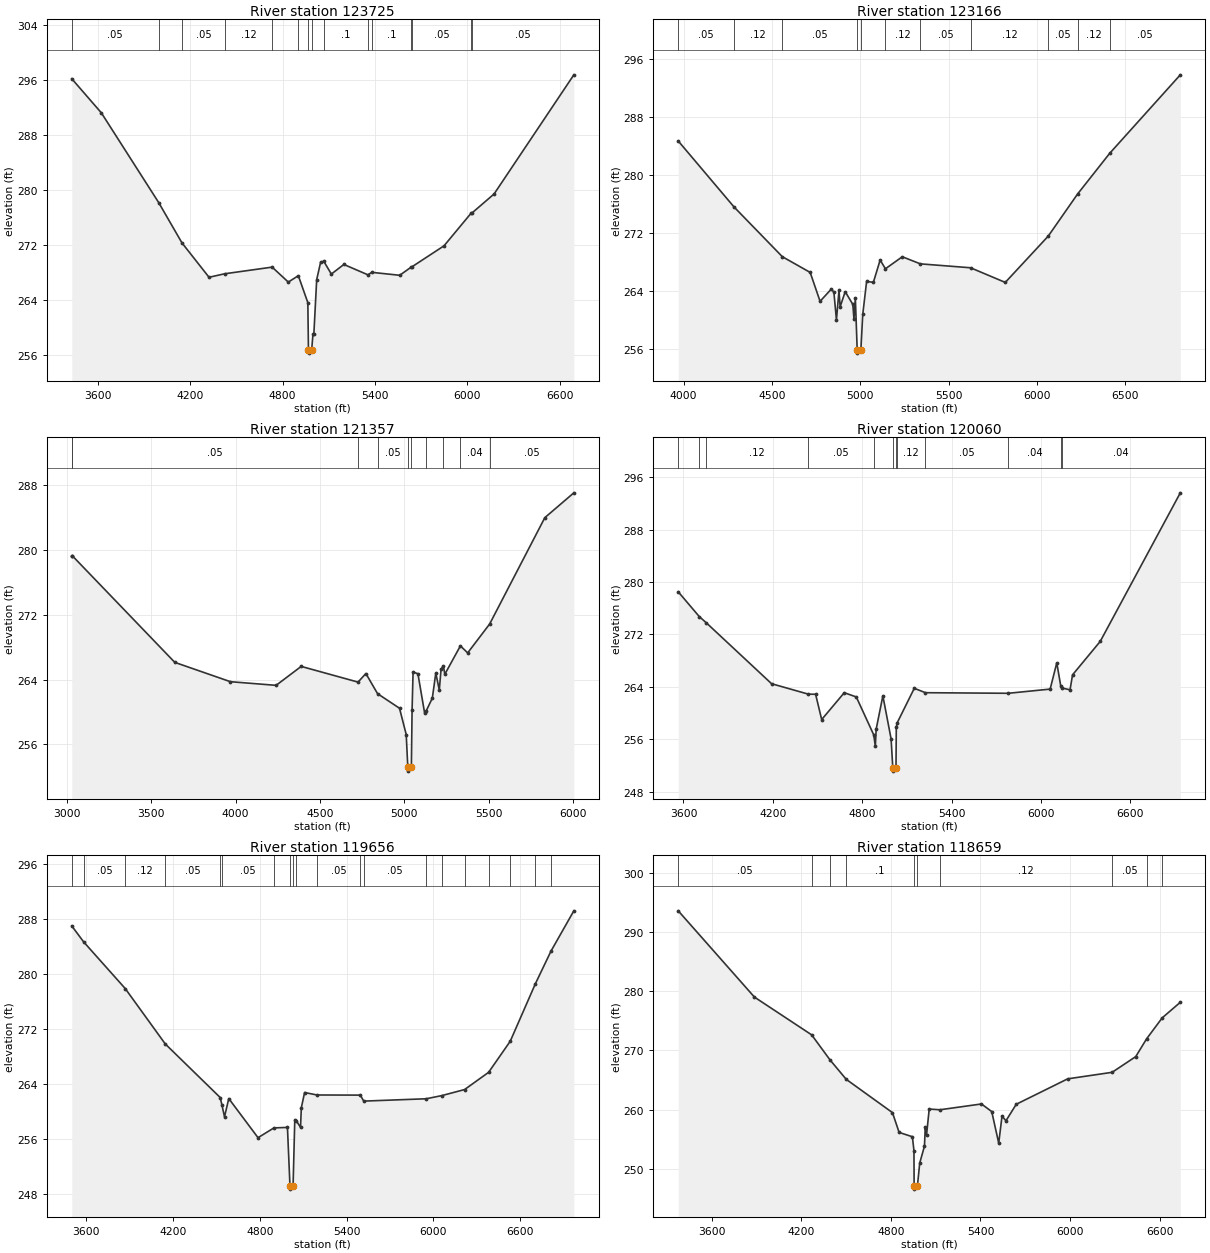
Type RM Length L Ch R = 1 ,123725  ,559,559,559
BEGIN DESCRIPTION:
WOODS CREEK 2.0
END DESCRIPTION:
XS GIS Cut Line= 3
      2470175.02     13550475.02        2468925.       13549525.
      2467325.05     13548975.02
#Sta/Elev= 30
  3429.9  296.22  3622.3  291.24  3994.4  278.17    4146  272.28  4321.7  267.27
  4423.1  267.78  4731.7  268.75  4836.7  266.57  4901.9   267.5  4963.6  263.57
  4967.6  256.71  4968.1  256.21  4988.6  256.71  4996.8  258.95  5002.6  258.95
  5021.1  266.93  5046.8  269.48  5067.2   269.6  5116.3  267.74  5197.7  269.14
  5353.8  267.63  5379.2  267.99  5560.4  267.56  5633.2  268.72  5639.6  268.79
  5848.5  271.86  6025.7  276.65    6033   276.7  6173.7  279.42  6691.8  296.79
#Mann= 15 ,-1 , 0
  3429.9     .05       0  3994.4     .12       0    4146     .05       0
  4423.1     .12       0  4731.7     .05       0  4901.9     .12       0
  4967.6     .05       0  4988.6     .12       0  5067.2      .1       0
  5353.8     .05       0  5379.2      .1       0  5633.2     .12       0
  5639.6     .05       0  6025.7     .12       0    6033     .05       0
Bank Sta=4967.6,4988.6
XS Rating Curve= 0 ,0
Exp/Cntr=0.3,0.1

Type RM Length L Ch R = 1 ,123166  ,1809,1809,1809
BEGIN DESCRIPTION:
WOODS CREEK 1.0
END DESCRIPTION:
XS GIS Cut Line= 3
      2470174.97     13549874.97        2469375.       13549225.
        2467775.       13548375.
#Sta/Elev= 30
  3969.7  284.75    4285  275.66    4559  268.78  4716.7  266.61  4772.7  262.62
  4836.7  264.32    4851  263.86  4865.4  260.05  4879.8  264.14  4886.2  261.86
    4915  263.95  4958.1   262.2  4964.5   260.2  4972.4  263.07  4982.8  255.97
  4983.3  255.47  5003.8  255.97  5014.3  260.81  5036.2  265.37  5074.5  265.24
  5112.8  268.32  5142.7  267.11  5238.2  268.77  5340.6  267.79  5624.6  267.25
  5821.2  265.23  6064.5  271.62  6230.6  277.43  6412.2  283.04  6812.2  293.88
#Mann= 11 ,-1 , 0
  3969.7     .05       0    4285     .12       0    4559     .05       0
  4982.8     .05       0  5003.8     .05       0  5142.7     .12       0
  5340.6     .05       0  5624.6     .12       0  6064.5     .05       0
  6230.6     .12       0  6412.2     .05       0
Bank Sta=4982.8,5003.8
XS Rating Curve= 0 ,0
Exp/Cntr=0.3,0.1

Type RM Length L Ch R = 1 ,121357  ,1297,1297,1297
BEGIN DESCRIPTION:
4917
END DESCRIPTION:
XS GIS Cut Line= 4
      2470711.18     13548963.53      2470121.99     13548168.12
      2468815.89     13547814.59      2468256.15     13548109.19
#Sta/Elev= 30
  3028.6  279.24  3031.9   279.3  3639.1  266.13  3968.9  263.74  4239.5  263.29
  4388.3  265.63  4725.2  263.69  4771.6  264.75  4840.9  262.26  4970.9  260.46
  5010.7  257.21    5020  253.19  5020.5  252.69  5041.2  253.19  5045.4  260.24
  5051.3  264.94  5080.1  264.72  5119.9  259.85  5129.6  260.16  5165.3   261.7
    5186  264.81  5206.7  262.71  5217.1  265.26  5230.7  265.71  5239.5  264.66
  5331.8  268.17  5374.9   267.3  5505.1  270.87  5832.1  284.01  6004.1  287.08
#Mann= 10 ,-1 , 0
  3028.6     .12       0  3031.9     .05       0  4725.2     .12       0
  4840.9     .05       0    5020     .05       0  5041.2     .05       0
  5129.6     .05       0  5230.7     .12       0  5331.8     .04       0
  5505.1     .05       0
Bank Sta=5020,5041.2
XS Rating Curve= 0 ,0
Exp/Cntr=0.3,0.1

Type RM Length L Ch R = 1 ,120060  ,404,404,404
BEGIN DESCRIPTION:
Mapping XS 99a400bc
END DESCRIPTION:
XS GIS Cut Line= 3
      2471530.05     13547779.19      2470571.69     13547591.69
      2468419.46     13546543.35
#Sta/Elev= 30
  3564.7  278.52  3705.9  274.74  3753.4  273.78  4191.4  264.48  4437.9  262.89
  4486.9  262.87  4527.7  259.01  4679.3  263.11    4760  262.46  4877.3  256.66
  4887.8  254.92  4893.5  257.54  4938.4  262.63  4993.6  256.07  5005.1  251.63
  5005.6  251.13  5026.5  251.63  5028.6  257.82    5035  258.53  5149.3  263.78
  5224.3  263.11  5780.3  263.02  6061.4  263.66  6105.9  267.67  6132.4  264.16
  6140.4  263.83  6194.9  263.55  6211.8  265.84  6397.7  270.95  6935.2  293.64
#Mann= 12 ,-1 , 0
  3564.7     .12       0  3705.9     .05       0  3753.4     .12       0
  4437.9     .05       0  4877.3      .1       0  5005.1     .05       0
  5026.5      .1       0    5035     .12       0  5224.3     .05       0
  5780.3     .04       0  6132.4      .1       0  6140.4     .04       0
Bank Sta=5005.1,5026.5
XS Rating Curve= 0 ,0
Exp/Cntr=0.3,0.1

Type RM Length L Ch R = 1 ,119656  ,997,997,997
BEGIN DESCRIPTION:
Mapping XS 3b72cc0b
END DESCRIPTION:
XS GIS Cut Line= 3
      2471891.11     13547390.29      2470661.97     13547230.58
      2468656.74     13546259.19
#Sta/Elev= 30
    3502     287  3583.6  284.69  3871.4   277.9  4147.8  269.86  4527.2  262.08
  4538.4  261.06  4556.9  259.28  4586.4  261.93  4788.4  256.25  4898.2  257.67
  4991.6  257.74    5009  249.28  5009.5  248.78  5030.5  249.28  5042.3  258.86
  5052.7  258.71  5081.9  257.75  5087.5   260.6  5110.1  262.81  5195.3  262.45
  5494.5  262.43  5518.6  261.56  5949.8   261.9  6057.6  262.36  6215.2  263.24
  6380.9  265.74  6530.2  270.25  6704.3  278.62    6812  283.35  6969.6  289.19
#Mann= 20 ,-1 , 0
    3502     .12       0  3583.6     .05       0  3871.4     .12       0
  4147.8     .05       0  4527.2     .12       0  4538.4     .05       0
  4898.2      .1       0    5009     .05       0  5030.5      .1       0
  5052.7     .12       0  5195.3     .05       0  5494.5     .12       0
  5518.6     .05       0  5949.8     .12       0  6057.6      .1       0
  6215.2     .05       0  6380.9     .12       0  6530.2     .05       0
  6704.3     .12       0    6812     .04       0
Bank Sta=5009,5030.5
XS Rating Curve= 0 ,0
Exp/Cntr=0.3,0.1

Type RM Length L Ch R = 1 ,118659  ,609,609,609
BEGIN DESCRIPTION:
Mapping XS e8ebe740
END DESCRIPTION:
XS GIS Cut Line= 3
      2472057.82     13547119.47       2470682.8     13546425.02
      2468948.35     13545856.12
#Sta/Elev= 30
  3373.7  293.56  3884.7     279  4268.2  272.63  4391.6  268.39  4500.2  265.12
  4809.8  259.51  4854.4  256.17  4943.4  255.44  4953.9   253.1  4955.1   247.1
  4955.6   246.6    4977   247.1  4992.6  251.01  5024.4  253.85  5029.7  257.08
  5038.1  255.71  5056.2  260.11  5127.6  259.99  5406.4  260.97  5475.3  259.69
  5522.2  254.36  5544.2  258.92  5570.8  258.14  5639.7  260.92  5984.6  265.21
  6282.3  266.31  6440.7  268.96  6513.5  271.96  6618.1   275.5  6739.5  278.13
#Mann= 10 ,-1 , 0
  3373.7     .05       0  4268.2     .12       0  4391.6     .05       0
  4500.2      .1       0  4955.1     .05       0    4977      .1       0
  5127.6     .12       0  6282.3     .05       0  6513.5     .12       0
  6618.1     .05       0
Bank Sta=4955.1,4977
XS Rating Curve= 0 ,0
Exp/Cntr=0.3,0.1

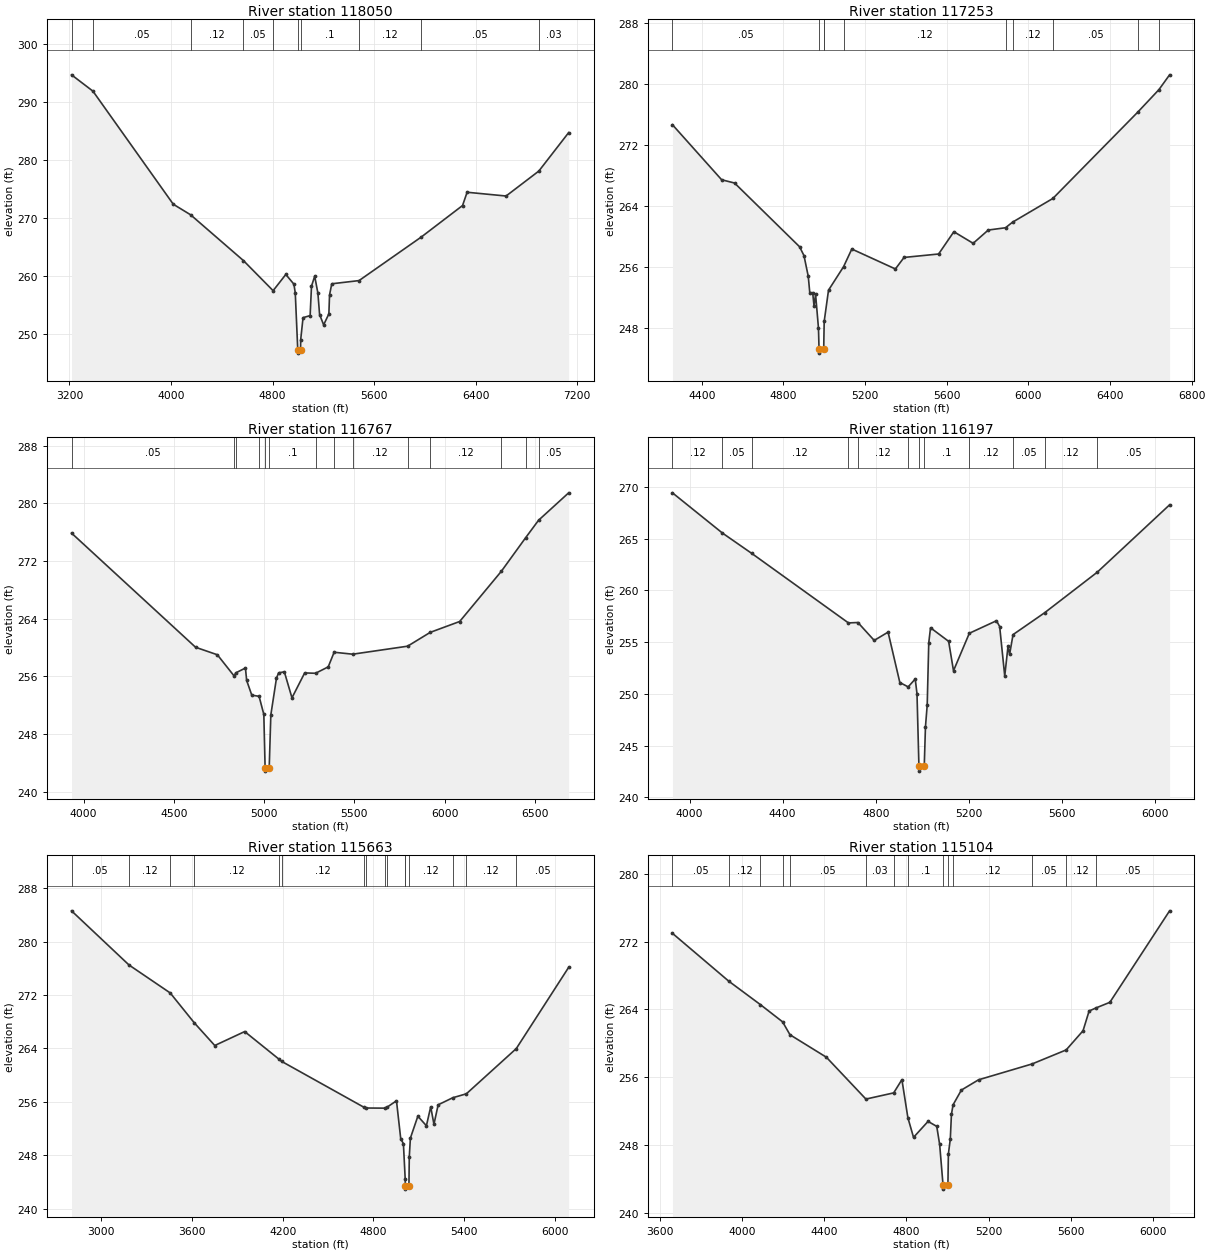
Type RM Length L Ch R = 1 ,118050  ,797,797,797
BEGIN DESCRIPTION:
Mapping XS 4a11209a
END DESCRIPTION:
XS GIS Cut Line= 3
      2472224.47     13546994.47       2470995.3     13545966.69
      2468821.73     13545175.04
#Sta/Elev= 30
  3216.5  294.71  3385.2  291.89    4018  272.37  4154.3  270.55  4570.7  262.64
  4804.2  257.45  4904.2  260.25  4968.1  258.57  4978.7  257.06  4998.5  247.17
    4999  246.67  5020.5  247.17  5021.3  248.97    5040  252.79  5095.8  253.15
  5106.5  258.23  5131.8  259.95    5157  257.01  5170.3  253.33  5202.2  251.55
  5243.4  253.45  5248.7  256.72  5266.1  258.64  5480.8  259.19  5971.1  266.71
  6296.2  272.15  6332.1  274.44    6639  273.79  6897.1   278.1    7132  284.74
#Mann= 10 ,-1 , 0
  3216.5     .12       0  3385.2     .05       0  4154.3     .12       0
  4570.7     .05       0  4804.2      .1       0  4998.5     .05       0
  5020.5      .1       0  5480.8     .12       0  5971.1     .05       0
  6897.1     .03       0
Bank Sta=4998.5,5020.5
XS Rating Curve= 0 ,0
Exp/Cntr=0.3,0.1

Type RM Length L Ch R = 1 ,117253  ,486,486,486
BEGIN DESCRIPTION:
TWELVEMILE CREEK 180.0
END DESCRIPTION:
XS GIS Cut Line= 3
      2471775.02     13545975.02        2471275.       13545425.
      2469675.02     13544875.01
#Sta/Elev= 30
  4256.7  274.64  4497.6  267.43  4561.1     267  4879.4  258.65    4901  257.49
    4922  254.77  4929.4  252.63  4943.6  252.63  4950.4  250.86  4957.8  252.42
    4972  247.99  4974.8  245.21  4975.3  244.71  4997.6  245.21    5000  248.86
  5021.2  252.96    5095  256.04  5135.3  258.35  5348.7  255.74  5391.3  257.25
  5560.5   257.7  5635.2  260.62  5729.7   259.1  5803.7  260.84  5888.2  261.14
  5922.6  261.87  6120.2  264.98  6536.3   276.3  6639.7  279.24  6691.9  281.18
#Mann= 10 ,-1 , 0
  4256.7     .05       0  4974.8     .05       0  4997.6     .05       0
    5000      .1       0    5095     .12       0  5888.2      .1       0
  5922.6     .12       0  6120.2     .05       0  6536.3     .04       0
  6639.7     .03       0
Bank Sta=4974.8,4997.6
XS Rating Curve= 0 ,0
Exp/Cntr=0.3,0.1

Type RM Length L Ch R = 1 ,116767  ,570,570,570
BEGIN DESCRIPTION:
TWELVEMILE CREEK 179.0
END DESCRIPTION:
XS GIS Cut Line= 3
      2472074.97     13545774.97        2471375.       13544975.
      2469774.97     13544424.99
#Sta/Elev= 30
  3932.9  275.89  4620.5  260.03    4741  258.99  4834.4  256.03  4842.5  256.47
  4896.7  257.15  4903.3  255.43  4931.8  253.38  4972.2  253.22  4998.5  250.71
  5005.6  243.33  5006.1  242.83  5028.4  243.33  5037.4  250.65  5068.7  255.75
  5080.5  256.48  5112.2  256.62  5154.5  253.01  5224.9  256.47  5285.1  256.42
  5355.4  257.31  5388.1  259.34  5491.1  259.07  5795.1  260.18  5920.6   262.1
  6083.8  263.61  6314.9  270.59  6448.9  275.23  6520.9  277.67  6687.8  281.48
#Mann= 14 ,-1 , 0
  3932.9     .05       0  4834.4     .12       0  4842.5     .05       0
  4972.2      .1       0  5005.6     .05       0  5028.4      .1       0
  5285.1     .12       0  5388.1     .05       0  5491.1     .12       0
  5795.1      .1       0  5920.6     .12       0  6314.9     .05       0
  6448.9     .04       0  6520.9     .05       0
Bank Sta=5005.6,5028.4
XS Rating Curve= 0 ,0
Exp/Cntr=0.3,0.1

Type RM Length L Ch R = 1 ,116197  ,534,534,534
BEGIN DESCRIPTION:
TWELVEMILE CREEK 178.0
END DESCRIPTION:
XS GIS Cut Line= 3
      2472075.02     13545425.04        2471575.       13544475.
      2470875.01     13543675.01
#Sta/Elev= 30
  3926.4  269.43  4140.8  265.55  4267.7  263.57  4682.8  256.86  4723.5   256.9
  4793.5  255.17  4853.1  255.97  4903.7   251.1  4939.5  250.68  4969.8  251.44
  4977.4  250.02  4985.7  243.04  4986.2  242.54  5008.6  243.04  5013.8  246.82
  5021.3  248.93    5028  254.95  5035.6  256.39  5113.4  255.08  5134.3  252.24
  5202.3  255.86  5318.9  257.07  5332.7  256.51  5354.5  251.73  5368.7  254.63
  5375.4  253.82  5390.2  255.73  5525.8  257.84  5752.1  261.76    6063  268.27
#Mann= 12 ,-1 , 0
  3926.4     .12       0  4140.8     .05       0  4267.7     .12       0
  4682.8     .05       0  4723.5     .12       0  4939.5      .1       0
  4985.7     .05       0  5008.6      .1       0  5202.3     .12       0
  5390.2     .05       0  5525.8     .12       0  5752.1     .05       0
Bank Sta=4985.7,5008.6
XS Rating Curve= 0 ,0
Exp/Cntr=0.3,0.1

Type RM Length L Ch R = 1 ,115663  ,559,559,559
BEGIN DESCRIPTION:
TWELVEMILE CREEK 177.0
END DESCRIPTION:
XS GIS Cut Line= 3
      2473374.98     13545574.98        2471825.       13544025.
      2471074.99     13543224.99
#Sta/Elev= 30
  2802.9  284.63  3183.2  276.51  3455.7  272.32  3613.9  267.87  3750.4  264.44
  3948.4  266.53  4173.7  262.42    4192  262.07  4737.4  255.18  4747.7  255.07
  4874.5  255.05  4891.1  255.21  4952.5  256.15  4980.8  250.42  4998.3  249.74
  5010.2   244.4  5011.2  243.41  5011.7  242.91  5034.8  243.41  5037.2  247.76
  5044.5  250.56  5093.8  253.84  5150.5  252.41  5178.8  255.25  5200.3  252.64
  5228.2  255.55  5324.7  256.61  5414.8   257.2    5745  263.98  6091.5  276.16
#Mann= 16 ,-1 , 0
  2802.9     .05       0  3183.2     .12       0  3455.7     .05       0
  3613.9     .12       0  4173.7     .05       0    4192     .12       0
  4737.4     .05       0  4747.7     .03       0  4874.5     .05       0
  4891.1      .1       0  5010.2     .12       0  5011.2     .05       0
  5034.8     .12       0  5324.7     .05       0  5414.8     .12       0
    5745     .05       0
Bank Sta=5011.2,5034.8
XS Rating Curve= 0 ,0
Exp/Cntr=0.3,0.1

Type RM Length L Ch R = 1 ,115104  ,588,588,588
BEGIN DESCRIPTION:
TWELVEMILE CREEK 176.0
END DESCRIPTION:
XS GIS Cut Line= 3
      2473074.98     13544524.98        2472125.       13543575.
        2471125.       13543175.
#Sta/Elev= 30
  3660.8  272.97  3935.1  267.33  4089.5  264.56  4197.1  262.54    4233  261.02
  4410.3  258.37  4602.7  253.44    4738  254.17    4778  255.73    4807  251.25
  4834.6  248.93  4905.3  250.81  4947.7  250.22  4961.8  248.09  4978.2  243.33
  4978.7  242.83    5002  243.33  5004.3  246.97  5013.7  248.75  5019.1  251.63
    5027  252.76  5067.5   254.5    5151  255.71    5412  257.58  5577.7  259.23
  5659.9  261.49  5689.5  263.82  5725.1   264.2  5790.5  264.84  6081.3  275.62
#Mann= 14 ,-1 , 0
  3660.8     .05       0  3935.1     .12       0  4089.5     .04       0
  4197.1     .12       0    4233     .05       0  4602.7     .03       0
    4738     .05       0    4807      .1       0  4978.2     .05       0
    5002      .1       0    5027     .12       0    5412     .05       0
  5577.7     .12       0  5725.1     .05       0
Bank Sta=4978.2,5002
XS Rating Curve= 0 ,0
Exp/Cntr=0.3,0.1

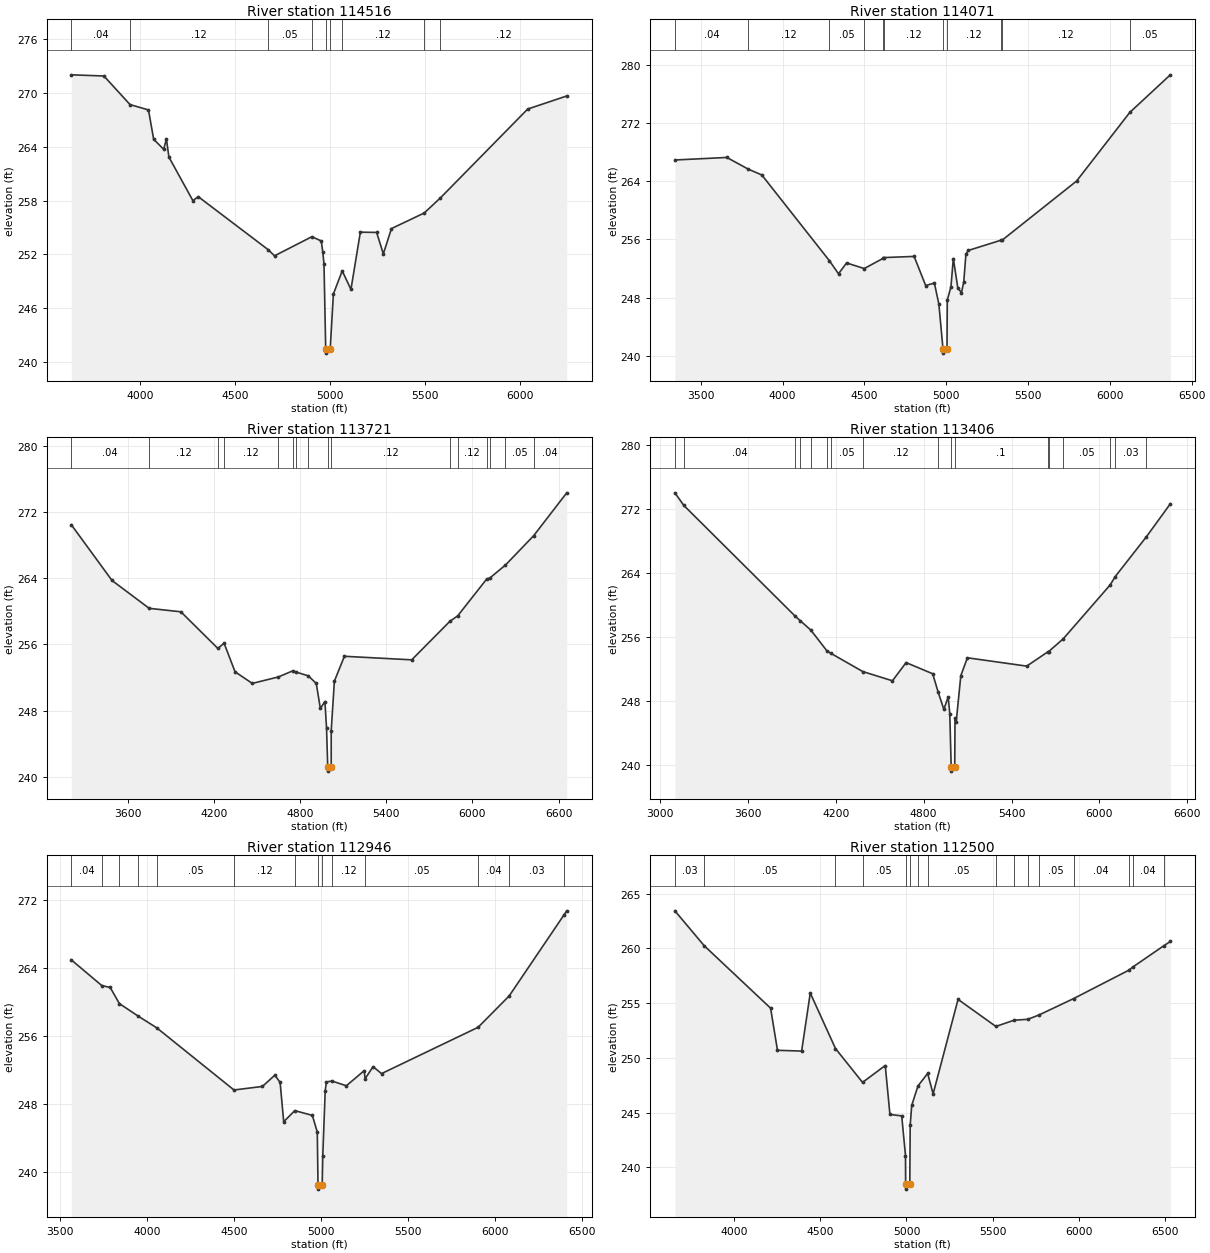
Type RM Length L Ch R = 1 ,114516  ,445,445,445
BEGIN DESCRIPTION:
Mapping XS db630a3e
END DESCRIPTION:
XS GIS Cut Line= 3
      2473307.82     13544445.88      2472703.63     13543418.08
      2471628.66     13542502.61
#Sta/Elev= 30
  3639.6  272.05  3810.9  271.92  3948.3  268.73  4045.2  268.13  4072.5  264.86
  4125.3  263.73  4139.4   264.9  4152.6  262.87  4278.6  258.01  4306.9  258.45
  4675.3  252.52  4707.8  251.85  4903.7  253.98  4953.5  253.51  4961.2   252.3
  4967.8  250.96  4976.8  241.49  4977.3  240.99  5000.6  241.49  5017.2  247.59
  5063.6  250.17  5109.5   248.1  5158.9  254.49  5244.5  254.46  5279.7  252.07
  5322.5  254.89  5494.7  256.63  5579.5  258.31  6038.5  268.23  6243.8  269.69
#Mann= 9 ,-1 , 0
  3639.6     .04       0  3948.3     .12       0  4675.3     .05       0
  4903.7      .1       0  4976.8     .05       0  5000.6      .1       0
  5063.6     .12       0  5494.7     .05       0  5579.5     .12       0
Bank Sta=4976.8,5000.6
XS Rating Curve= 0 ,0
Exp/Cntr=0.3,0.1

Type RM Length L Ch R = 1 ,114071  ,350,350,350
BEGIN DESCRIPTION:
Mapping XS c5780464
END DESCRIPTION:
XS GIS Cut Line= 3
      2473536.98     13544376.44      2472724.47      13542952.8
      2471634.19     13542091.69
#Sta/Elev= 30
  3341.1  266.95  3658.6   267.3  3788.8   265.7  3872.4  264.89  4285.8  253.07
  4341.2  251.28  4390.5  252.77  4498.6     252  4613.5   253.4  4617.7  253.51
  4803.5  253.67  4874.1  249.66  4927.4     250  4954.7   247.1  4980.3  240.85
  4980.8  240.35  5004.4  240.85  5006.2  247.63  5028.7  249.51  5043.1  253.38
  5070.3  249.38  5092.8  248.65    5107  250.18    5120  253.97  5134.4  254.49
  5335.5  255.91    5340  255.88  5796.5  264.05  6121.8   273.5  6369.6  278.68
#Mann= 11 ,-1 , 0
  3341.1     .04       0  3788.8     .12       0  4285.8     .05       0
  4498.6     .12       0  4613.5     .05       0  4617.7     .12       0
  4980.3     .05       0  5004.4     .12       0  5335.5     .05       0
    5340     .12       0  6121.8     .05       0
Bank Sta=4980.3,5004.4
XS Rating Curve= 0 ,0
Exp/Cntr=0.3,0.1

Type RM Length L Ch R = 1 ,113721  ,315,315,315
BEGIN DESCRIPTION:
Mapping XS 02072062
END DESCRIPTION:
XS GIS Cut Line= 3
      2473780.01     13544445.83      2473030.02     13542834.74
      2472349.46     13541306.96
#Sta/Elev= 30
  3207.8  270.48  3491.1  263.74    3750  260.37  3970.7  259.95  4228.3  255.52
  4271.6  256.15  4347.8   252.7  4467.7  251.29  4649.6  252.07  4748.3   252.8
  4769.6  252.68  4858.5   252.2  4913.4  251.28  4941.8  248.26  4973.6   249.1
  4984.9   245.9  4993.2  241.18  4993.7  240.68  5017.3  241.18  5017.5  245.59
  5039.5  251.56  5109.2  254.57    5578  254.14  5843.2  258.79  5898.1  259.46
  6099.4   263.9  6122.8  264.05  6230.9  265.61  6426.9  269.15  6657.4  274.34
#Mann= 16 ,-1 , 0
  3207.8     .04       0    3750     .12       0  4228.3     .05       0
  4271.6     .12       0  4649.6     .05       0  4748.3     .12       0
  4769.6     .05       0  4858.5     .12       0  4993.2     .05       0
  5017.3     .12       0  5843.2     .05       0  5898.1     .12       0
  6099.4     .05       0  6122.8     .12       0  6230.9     .05       0
  6426.9     .04       0
Bank Sta=4993.2,5017.3
XS Rating Curve= 0 ,0
Exp/Cntr=0.3,0.1

Type RM Length L Ch R = 1 ,113406  ,460,460,460
BEGIN DESCRIPTION:
Mapping XS d752d55a
END DESCRIPTION:
XS GIS Cut Line= 3
      2474030.03     13544411.14      2473280.02     13542654.19
      2472752.41     13541279.61
#Sta/Elev= 30
  3101.5  274.01  3161.9  272.45  3921.4  258.65  3957.4  258.06  4029.9  256.88
  4138.4  254.32  4164.1  254.01  4384.6  251.71  4586.9  250.56  4680.1  252.83
  4861.6  251.44  4897.8  249.22  4937.9  246.99  4967.5  248.54  4978.3  246.47
    4988  239.79  4988.5  239.29  5012.1  239.79  5014.1  245.93  5021.7  245.36
  5053.8  251.21  5098.8  253.43  5503.7  252.39  5646.9  254.16  5653.1   254.2
  5753.7  255.81  6073.9  262.53  6107.9  263.56  6320.5  268.52  6484.2  272.64
#Mann= 17 ,-1 , 0
  3101.5    .013       0  3161.9     .04       0  3921.4     .05       0
  3957.4     .04       0  4029.9     .05       0  4138.4     .12       0
  4164.1     .05       0  4384.6     .12       0  4897.8      .1       0
    4988     .05       0  5012.1      .1       0  5646.9     .05       0
  5653.1     .12       0  5753.7     .05       0  6073.9     .04       0
  6107.9     .03       0  6320.5     .04       0
Bank Sta=4988,5012.1
XS Rating Curve= 0 ,0
Exp/Cntr=0.3,0.1

Type RM Length L Ch R = 1 ,112946  ,446,446,446
BEGIN DESCRIPTION:
Mapping XS 007c9bdd
END DESCRIPTION:
XS GIS Cut Line= 3
       2473918.9     13543834.71      2473661.97     13542431.96
       2472884.2     13541244.49
#Sta/Elev= 30
  3565.1  264.98  3740.5  261.95  3788.5  261.73  3841.2  259.83  3949.5  258.35
  4056.1  256.97  4499.5  249.65  4662.8  250.07  4733.9  251.39  4764.4  250.55
    4785  245.91  4848.6  247.22  4949.6  246.66  4977.9  244.69  4982.1  238.47
  4982.6  237.97  5006.2  238.47  5009.3  241.83  5023.4  249.57  5030.3  250.59
  5061.3  250.71  5144.9  250.15  5247.4  251.93  5252.4  250.97  5298.4   252.4
  5346.8  251.58  5901.8  257.04  6080.3  260.74  6394.2  270.26  6410.7  270.76
#Mann= 14 ,-1 , 0
  3565.1     .04       0  3740.5     .12       0  3841.2     .05       0
  3949.5     .12       0  4056.1     .05       0  4499.5     .12       0
  4848.6      .1       0  4982.1     .05       0  5006.2      .1       0
  5061.3     .12       0  5252.4     .05       0  5901.8     .04       0
  6080.3     .03       0  6394.2     .04       0
Bank Sta=4982.1,5006.2
XS Rating Curve= 0 ,0
Exp/Cntr=0.3,0.1

Type RM Length L Ch R = 1 ,112500  ,431,431,431
BEGIN DESCRIPTION:
Mapping XS d5069431
END DESCRIPTION:
XS GIS Cut Line= 3
      2474148.08     13543709.77      2474148.08     13542543.08
      2473286.95     13541070.82
#Sta/Elev= 30
  3657.5  263.44    3827  260.26  4212.3  254.55  4252.3   250.7  4392.3  250.63
  4442.3  255.93  4588.6  250.86  4745.4  247.77    4877  249.31  4904.2  244.84
  4972.6  244.71  4994.3  241.09  4995.2  238.52  4995.7  238.02  5019.4  238.52
  5021.6  243.85  5030.5  245.66  5066.6  247.44  5122.8  248.59  5154.6  246.72
  5299.2  255.35  5518.4  252.88  5623.9  253.45  5703.4  253.53  5768.8  253.93
  5968.6  255.42  6289.5  258.02  6310.8  258.29    6491  260.24  6529.8  260.64
#Mann= 16 ,-1 , 0
  3657.5     .03       0    3827     .05       0  4588.6     .12       0
  4745.4     .05       0  4995.2     .05       0  5019.4     .05       0
  5066.6      .1       0  5122.8     .05       0  5518.4     .12       0
  5623.9     .05       0  5703.4     .12       0  5768.8     .05       0
  5968.6     .04       0  6289.5     .12       0  6310.8     .04       0
    6491     .12       0
Bank Sta=4995.2,5019.4
XS Rating Curve= 0 ,0
Exp/Cntr=0.3,0.1