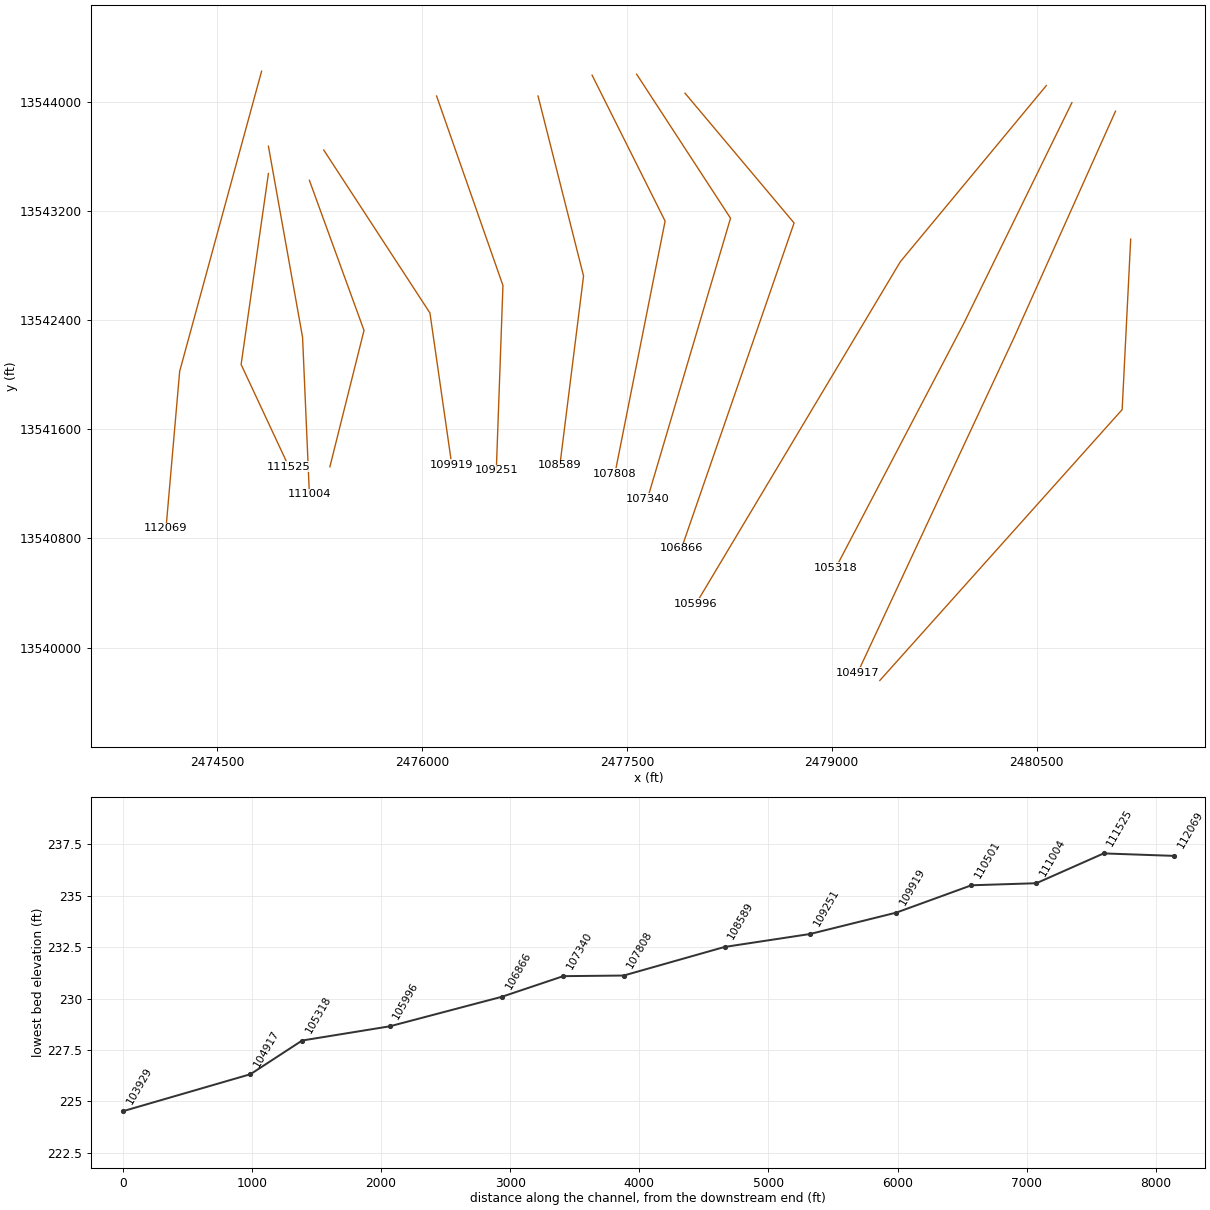
HEC-RAS study TWELVEMILE CREEK.prj: TWELVEMILE CREEK Base Level Engineering

--- TWELVEMILE CREEK.g01 (geometry) --- (continued)

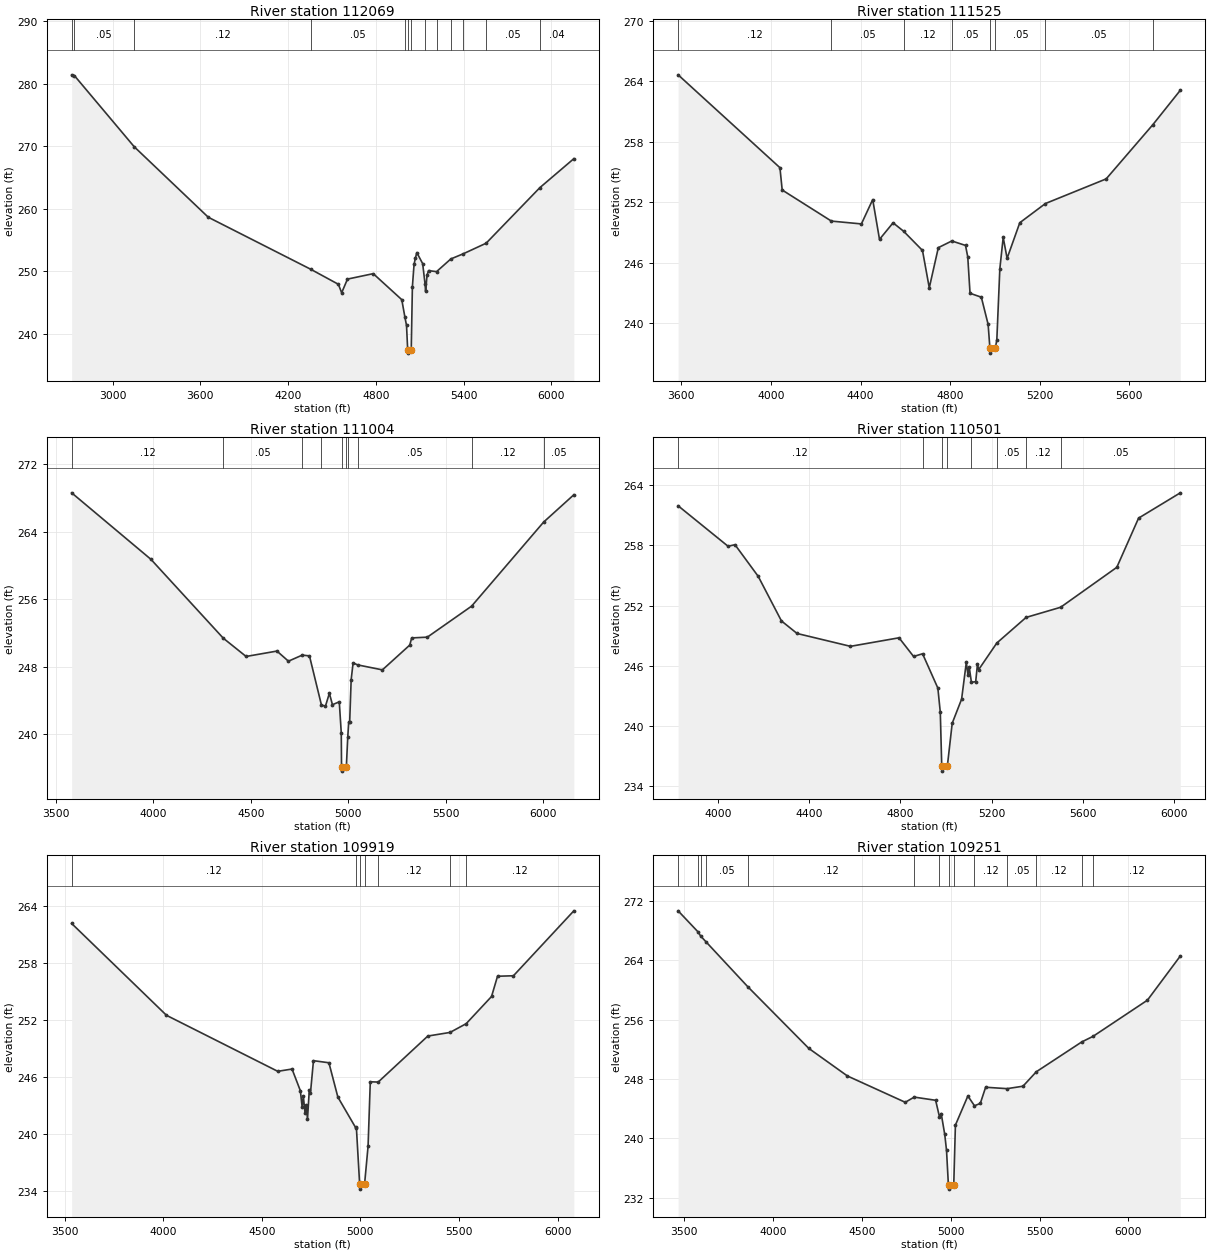
Type RM Length L Ch R = 1 ,112069  ,544,544,544
BEGIN DESCRIPTION:
TWELVEMILE CREEK 170.0
END DESCRIPTION:
XS GIS Cut Line= 3
        2474825.     13544225.01        2474225.       13542025.
        2474125.       13540875.
#Sta/Elev= 30
  2719.3  281.45  2737.5  281.34  3147.1  269.95  3653.9  258.67  4353.9  250.36
  4543.6  247.95    4566  246.59  4605.8  248.78    4782  249.65  4977.2  245.49
    4999  242.64  5009.7  241.37  5017.6  237.44  5018.1  236.94  5041.9  237.44
  5049.8  247.56  5061.1  251.12  5069.9  252.11    5080  253.02  5120.1  251.25
  5136.5  247.97  5140.2  246.82  5150.2  249.45  5160.3  250.14  5214.9  249.97
  5312.5     252  5398.9  252.84  5554.2  254.52  5921.4   263.4    6154  268.04
#Mann= 13 ,-1 , 0
  2719.3     .12       0  2737.5     .05       0  3147.1     .12       0
  4353.9     .05       0    4999      .1       0  5017.6     .05       0
  5041.9      .1       0  5136.5     .05       0  5214.9     .12       0
  5312.5     .05       0  5398.9     .12       0  5554.2     .05       0
  5921.4     .04       0
Bank Sta=5017.6,5041.9
XS Rating Curve= 0 ,0
Exp/Cntr=0.3,0.1

Type RM Length L Ch R = 1 ,111525  ,521,521,521
BEGIN DESCRIPTION:
TWELVEMILE CREEK 169.0
END DESCRIPTION:
XS GIS Cut Line= 3
      2474874.99     13543474.96        2474675.       13542075.
      2475024.99     13541325.02
#Sta/Elev= 30
  3585.6  264.63  4040.1  255.43  4050.2  253.22  4269.8  250.14  4403.8  249.86
  4454.3  252.27  4484.6  248.33  4545.2  249.97  4592.4  249.13  4676.5  247.23
  4706.8  243.53  4747.2  247.51  4807.4  248.17  4868.5  247.73  4878.6  246.59
  4888.7  242.99  4939.2   242.6  4969.5  239.91  4977.4  237.56  4977.9  237.06
  5001.9  237.56  5008.4  238.41  5021.8  245.42  5036.8  248.52  5054.2  246.45
  5110.9  249.98  5225.3  251.88  5496.4  254.32  5704.8  259.69  5827.4   263.1
#Mann= 8 ,-1 , 0
  3585.6     .12       0  4269.8     .05       0  4592.4     .12       0
  4807.4     .05       0  4977.4     .05       0  5001.9     .05       0
  5225.3     .05       0  5704.8     .12       0
Bank Sta=4977.4,5001.9
XS Rating Curve= 0 ,0
Exp/Cntr=0.3,0.1

Type RM Length L Ch R = 1 ,111004  ,503,503,503
BEGIN DESCRIPTION:
TWELVEMILE CREEK 168.0
END DESCRIPTION:
XS GIS Cut Line= 3
        2474875.     13543674.99        2475125.       13542275.
        2475175.     13541125.03
#Sta/Elev= 30
  3582.3  268.62  3988.6  260.73  4359.1  251.38  4476.2  249.21  4634.2  249.85
  4693.1  248.65  4763.6  249.37  4800.8  249.28  4861.9  243.48  4882.5   243.3
  4902.9  244.84  4918.6  243.49  4953.6  243.83  4963.8  240.15  4965.2  236.11
  4965.7  235.61  4989.8  236.11    4997  239.62  5001.9  241.42  5006.9  241.42
  5014.5  246.46  5024.5  248.45  5047.7  248.21  5174.6  247.62  5314.7  250.56
  5324.7  251.41  5404.8   251.5  5631.7  255.18  6000.7  265.15  6155.5  268.39
#Mann= 10 ,-1 , 0
  3582.3     .12       0  4359.1     .05       0  4763.6     .12       0
  4861.9     .05       0  4965.2     .05       0  4989.8     .05       0
    4997      .1       0  5047.7     .05       0  5631.7     .12       0
  6000.7     .05       0
Bank Sta=4965.2,4989.8
XS Rating Curve= 0 ,0
Exp/Cntr=0.3,0.1

Type RM Length L Ch R = 1 ,110501  ,582,582,582
BEGIN DESCRIPTION:
TWELVEMILE CREEK 167.0
END DESCRIPTION:
XS GIS Cut Line= 3
      2475175.01     13543424.97        2475575.       13542325.
        2475325.     13541325.01
#Sta/Elev= 30
  3825.3  261.94  4044.1  257.91  4074.7  258.06  4176.4  254.91  4278.2  250.47
  4346.7  249.22  4580.8  247.94  4793.6  248.79  4857.4  246.93  4896.8   247.2
  4963.8  243.78  4974.5  241.37  4980.8  236.01  4981.3  235.51  5005.4  236.01
  5026.7  240.28  5067.9  242.68  5088.5  246.34  5096.2  245.05  5101.4  245.86
  5110.9  244.35  5129.7  244.43  5137.5  246.18  5142.6  245.62  5222.2  248.27
  5350.5  250.82  5501.9  251.83  5748.2  255.81  5843.6  260.71  6026.5  263.23
#Mann= 8 ,-1 , 0
  3825.3     .12       0  4896.8      .1       0  4980.8     .05       0
  5005.4      .1       0  5110.9     .12       0  5222.2     .05       0
  5350.5     .12       0  5501.9     .05       0
Bank Sta=4980.8,5005.4
XS Rating Curve= 0 ,0
Exp/Cntr=0.3,0.1

Type RM Length L Ch R = 1 ,109919  ,668,668,668
BEGIN DESCRIPTION:
Mapping XS 68f1e390
END DESCRIPTION:
XS GIS Cut Line= 3
      2475280.05      13543647.2       2476057.8      13542452.8
      2476217.52     13541341.73
#Sta/Elev= 30
  3535.1  262.12  4016.3  252.46  4580.7  246.57  4653.2  246.81  4695.4  244.53
  4704.5  242.82  4710.5  243.94  4719.1  242.21  4725.6  242.99  4731.6  241.54
  4740.8  244.61  4746.7  244.29  4761.9  247.69  4840.3  247.47  4885.7  243.86
  4975.3  240.67  4979.7  240.64  4996.3  234.68  4996.8  234.18  5021.1  234.68
    5039   238.7  5050.2  245.47  5090.3  245.44  5342.1  250.28  5454.6  250.66
  5536.6  251.58  5665.4  254.44  5695.7  256.57  5776.5  256.62  6082.9  263.45
#Mann= 7 ,-1 , 0
  3535.1     .12       0  4975.3      .1       0  4996.3     .05       0
  5021.1      .1       0  5090.3     .12       0  5454.6     .05       0
  5536.6     .12       0
Bank Sta=4996.3,5021.1
XS Rating Curve= 0 ,0
Exp/Cntr=0.3,0.1

Type RM Length L Ch R = 1 ,109251  ,662,662,662
BEGIN DESCRIPTION:
Mapping XS b64c6cac
END DESCRIPTION:
XS GIS Cut Line= 3
      2476106.41     13544043.06      2476592.52     13542654.19
      2476543.91     13541300.04
#Sta/Elev= 30
  3465.1   270.7  3577.5  267.85  3591.1  267.32    3622  266.52  3856.7  260.47
  4200.9  252.13  4418.1  248.41  4743.5  244.86    4794  245.56  4914.5  245.13
  4935.7  242.94  4945.8  243.34  4965.8  240.52  4975.8  238.37  4985.8  233.94
  4991.3  233.64  4991.8  233.14  5016.4  233.64  5025.8  241.78  5095.9  245.71
  5133.2  244.39  5165.9  244.71  5195.9  246.89  5316.7   246.7  5406.1  247.03
  5481.2  248.98  5737.2  253.01  5800.6  253.76  6106.5  258.64  6291.6   264.6
#Mann= 14 ,-1 , 0
  3465.1     .12       0  3577.5     .05       0  3591.1     .12       0
    3622     .05       0  3856.7     .12       0    4794     .05       0
  4935.7      .1       0  4991.3     .05       0  5016.4      .1       0
  5133.2     .12       0  5316.7     .05       0  5481.2     .12       0
  5737.2     .05       0  5800.6     .12       0
Bank Sta=4991.3,5016.4
XS Rating Curve= 0 ,0
Exp/Cntr=0.3,0.1

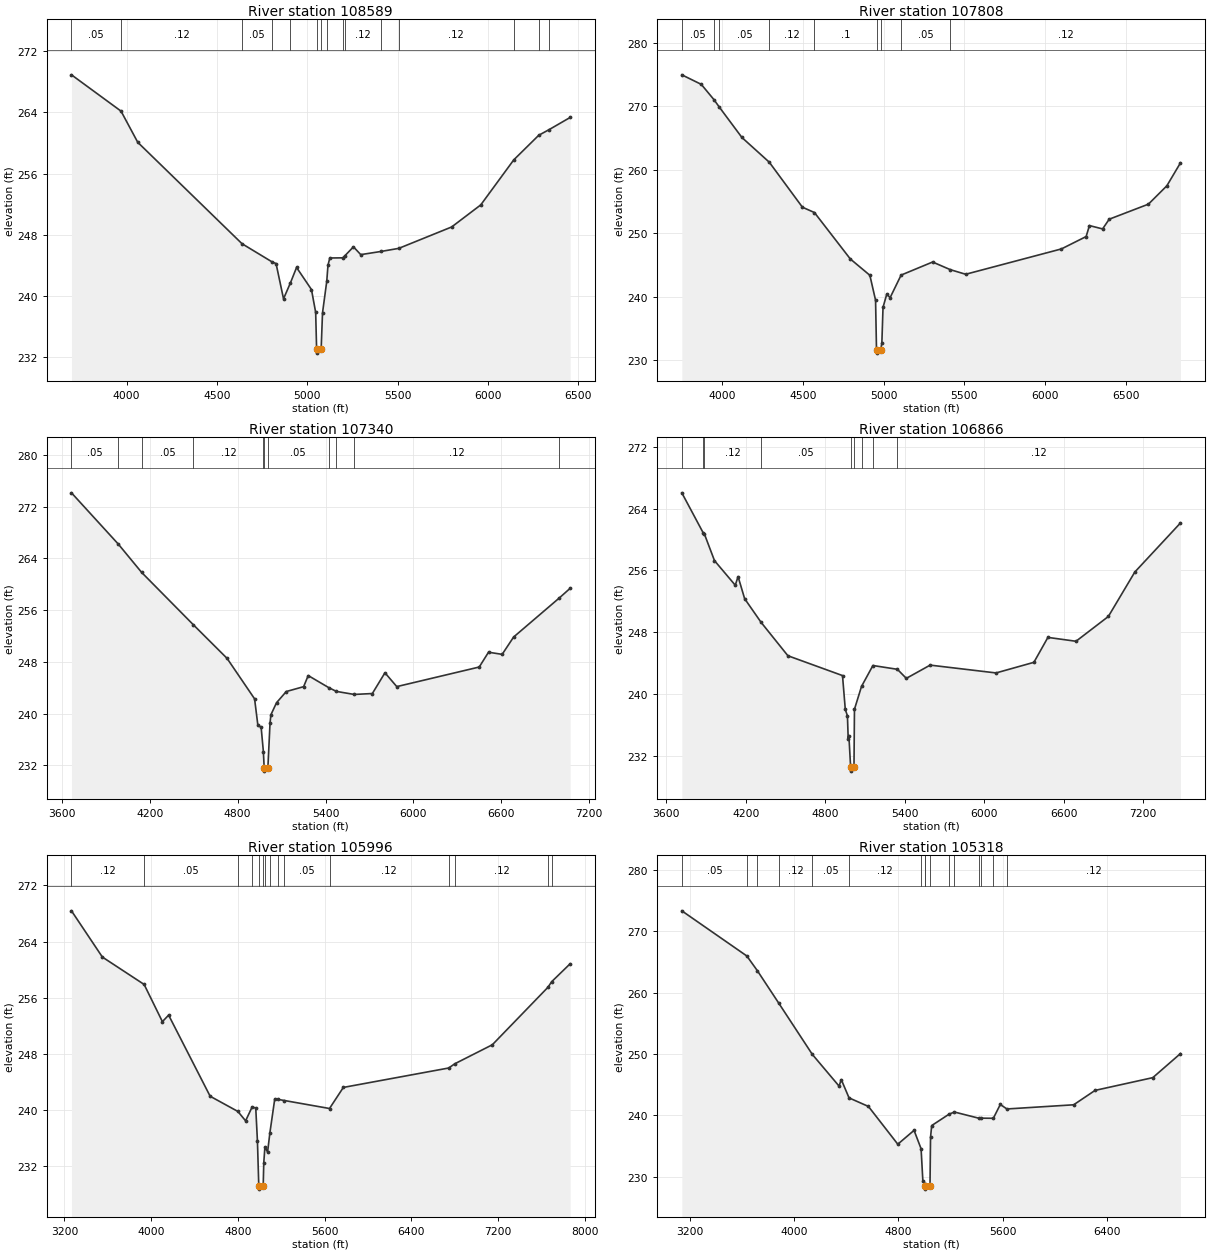
Type RM Length L Ch R = 1 ,108589  ,781,781,781
BEGIN DESCRIPTION:
Mapping XS 7691dc3c
END DESCRIPTION:
XS GIS Cut Line= 3
      2476849.46     13544043.11       2477182.8     13542723.63
      2477009.19     13541334.77
#Sta/Elev= 30
  3694.7  268.93    3969  264.18  4061.6   260.1  4638.7  246.83  4805.9  244.44
  4827.3  244.23  4868.6  239.62  4906.8   241.7  4940.8  243.72  5023.3  240.83
  5046.6  237.84  5051.8  233.01  5052.3  232.51  5076.9  233.01  5084.5  237.78
    5108  241.92  5114.7     244  5124.8  244.96  5196.3  244.98  5208.2  245.25
  5255.8  246.42  5296.1   245.4  5407.1  245.81  5506.8  246.22  5799.4  249.02
  5960.6  251.91  6143.2   257.8  6281.5  261.02    6339  261.76  6455.3  263.35
#Mann= 15 ,-1 , 0
  3694.7     .05       0    3969     .12       0  4638.7     .05       0
  4805.9     .12       0  4906.8      .1       0  5051.8     .05       0
  5076.9      .1       0    5108     .12       0  5196.3      .1       0
  5208.2     .12       0  5407.1     .05       0  5506.8     .12       0
  6143.2     .05       0  6281.5     .12       0    6339     .05       0
Bank Sta=5051.8,5076.9
XS Rating Curve= 0 ,0
Exp/Cntr=0.3,0.1

Type RM Length L Ch R = 1 ,107808  ,468,468,468
BEGIN DESCRIPTION:
Mapping XS acb50270
END DESCRIPTION:
XS GIS Cut Line= 3
       2477245.3     13544195.84      2477780.02     13543126.41
      2477411.97     13541272.25
#Sta/Elev= 30
  3751.5  274.95  3871.8  273.45    3950  271.05    3984  269.85  4123.4  265.08
  4292.7  261.19  4497.9   254.1  4572.2  253.26  4794.2  245.95  4915.2  243.38
  4950.5  239.45  4956.3  231.62  4956.8  231.12  4981.6  231.62  4989.4  232.67
  4996.6  238.33    5020  240.42  5040.4  239.85  5108.5  243.41  5303.6  245.47
  5413.5  244.26  5508.2  243.54  6100.6  247.53  6253.6  249.48    6274  251.21
  6355.5  250.68  6396.3  252.21    6639  254.58  6753.1  257.47  6837.5  261.09
#Mann= 9 ,-1 , 0
  3751.5     .05       0    3950     .12       0    3984     .05       0
  4292.7     .12       0  4572.2      .1       0  4956.3     .05       0
  4981.6      .1       0  5108.5     .05       0  5413.5     .12       0
Bank Sta=4956.3,4981.6
XS Rating Curve= 0 ,0
Exp/Cntr=0.3,0.1

Type RM Length L Ch R = 1 ,107340  ,474,474,474
BEGIN DESCRIPTION:
Mapping XS e13a7a38
END DESCRIPTION:
XS GIS Cut Line= 3
      2477571.71     13544202.76      2478259.19     13543147.24
      2477650.64     13541089.82
#Sta/Elev= 30
    3665  274.13  3984.8   266.2  4144.2  261.82  4497.5  253.72  4727.5  248.53
  4915.4  242.27  4937.4  238.27  4960.3  237.84  4975.5   234.1  4980.9  231.59
  4981.4  231.09  5006.2  231.59  5020.9  238.53  5026.8   239.8  5065.3  241.67
  5131.8   243.4  5250.3  244.15  5281.6  245.87  5421.4  244.01  5473.9  243.42
  5595.5  242.95  5719.5  243.09  5805.7   246.3  5886.4  244.16  6449.5  247.19
  6512.8  249.48    6606  249.15  6684.4  251.83  6992.7   257.8  7070.2  259.36
#Mann= 11 ,-1 , 0
    3665     .05       0  3984.8     .12       0  4144.2     .05       0
  4497.5     .12       0  4975.5     .05       0  4980.9     .05       0
  5006.2     .05       0  5421.4     .12       0  5473.9     .05       0
  5595.5     .12       0  6992.7     .05       0
Bank Sta=4980.9,5006.2
XS Rating Curve= 0 ,0
Exp/Cntr=0.3,0.1

Type RM Length L Ch R = 1 ,106866  ,870,870,870
BEGIN DESCRIPTION:
Mapping XS 886fb6f7
END DESCRIPTION:
XS GIS Cut Line= 3
      2477925.87     13544063.89      2478724.47     13543112.52
      2477900.83     13540729.24
#Sta/Elev= 30
  3718.2  266.03  3880.8  260.82  3887.5  260.76  3964.8  257.27  4121.5   254.1
  4142.8  255.21  4192.3  252.36  4316.2  249.31  4518.8  244.99    4931  242.43
    4952  238.06  4968.3  237.22  4973.8   234.3  4979.1  234.67  4992.3  230.59
  4992.8  230.09  5017.6  230.59  5021.2  238.08  5074.5  241.03  5160.5  243.73
  5345.1  243.24  5412.6  242.07  5592.5  243.78  6089.8  242.77  6375.5  244.14
  6481.3  247.36  6693.3  246.86  6937.4  250.06  7137.2   255.8  7481.9  262.14
#Mann= 9 ,-1 , 0
  3718.2     .12       0  3880.8     .05       0  3887.5     .12       0
  4316.2     .05       0  4992.3     .05       0  5017.6     .05       0
  5074.5     .03       0  5160.5     .05       0  5345.1     .12       0
Bank Sta=4992.3,5017.6
XS Rating Curve= 0 ,0
Exp/Cntr=0.3,0.1

Type RM Length L Ch R = 1 ,105996  ,678,678,678
BEGIN DESCRIPTION:
Mapping XS cfb8d48a
END DESCRIPTION:
XS GIS Cut Line= 3
      2480571.68     13544119.46      2479502.24      13542827.8
      2478005.12     13540319.44
#Sta/Elev= 30
  3264.9  268.38  3549.8  261.78  3934.9  257.87  4103.3  252.56  4160.7  253.49
  4543.6  241.91  4799.3  239.74  4870.5   238.4  4930.4  240.37  4964.1  240.24
  4979.7   235.5  4991.7  229.31  4997.1  229.15  4997.9  228.65  5032.9  229.15
  5038.1  232.41  5048.4  234.65  5073.2  233.95  5094.7  236.71  5139.3  241.52
  5165.2  241.47  5228.3   241.3  5644.2  240.16  5771.9  243.17  6743.1  245.94
  6800.1  246.55  7145.7  249.26  7658.7  257.47  7692.6  258.26    7863  260.82
#Mann= 15 ,-1 , 0
  3264.9     .12       0  3934.9     .05       0  4799.3     .12       0
  4930.4     .05       0  4997.1     .05       0  5032.9     .05       0
  5048.4      .1       0  5094.7     .05       0  5165.2      .1       0
  5228.3     .05       0  5644.2     .12       0  6743.1     .05       0
  6800.1     .12       0  7658.7     .05       0  7692.6     .12       0
Bank Sta=4997.1,5032.9
XS Rating Curve= 0 ,0
Exp/Cntr=0.3,0.1

Type RM Length L Ch R = 1 ,105318  ,401,401,401
BEGIN DESCRIPTION:
Mapping XS e021ba3a
END DESCRIPTION:
XS GIS Cut Line= 3
      2480759.18     13543994.44      2479967.52     13542376.41
      2479030.04     13540584.78
#Sta/Elev= 30
  3140.8  273.37  3639.4     266  3719.7  263.61  3882.6  258.35  4141.5  249.94
  4346.5  244.77  4363.4  245.83  4422.9  242.85  4571.6  241.45  4796.7  235.29
  4921.4  237.55  4975.3  234.55  4988.9  229.31  5005.4  228.84  5007.8  228.46
  5008.6  227.96  5043.6  228.46  5047.8  236.41  5056.6  238.33  5190.5   240.2
    5231  240.54  5416.3  239.54  5432.2  239.54  5529.3  239.52  5582.6  241.77
  5633.4  241.04  6145.2  241.72  6309.3  244.07  6751.9  246.15  6964.2  250.08
#Mann= 16 ,-1 , 0
  3140.8     .05       0  3639.4     .12       0  3719.7     .05       0
  3882.6     .12       0  4141.5     .05       0  4422.9     .12       0
  4975.3      .1       0  5005.4     .12       0  5007.8     .05       0
  5043.6     .12       0  5190.5     .05       0    5231     .12       0
  5416.3     .05       0  5432.2     .12       0  5529.3     .05       0
  5633.4     .12       0
Bank Sta=5007.8,5043.6
XS Rating Curve= 0 ,0
Exp/Cntr=0.3,0.1

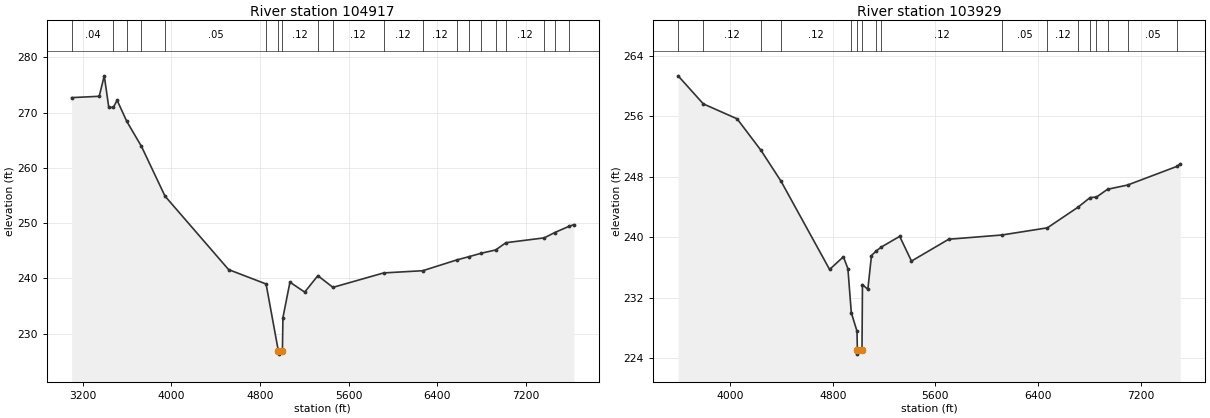
Type RM Length L Ch R = 1 ,104917  ,988,988,988
BEGIN DESCRIPTION:
Mapping XS f79ef05f
END DESCRIPTION:
XS GIS Cut Line= 3
      2481078.61     13543931.92      2480335.58     13542272.24
      2479189.75     13539814.98
#Sta/Elev= 30
  3100.5  272.69  3349.1  272.93  3394.6  276.63  3435.5  270.92  3476.4  270.92
  3510.6  272.21  3597.4  268.41  3730.2  263.87  3942.4  254.89  4516.3   241.6
  4854.3     239  4965.6  226.82  4966.4  226.32  5001.5  226.82  5006.4  232.94
  5069.5  239.33  5202.7  237.53  5321.1   240.5  5457.4  238.39  5914.9     241
  6267.5   241.4  6576.2  243.36  6686.5  243.95  6796.7  244.57  6925.5  245.15
  7017.1  246.46  7364.2  247.34    7458   248.3  7583.5   249.4  7630.2  249.72
#Mann= 20 ,-1 , 0
  3100.5     .04       0  3476.4     .05       0  3597.4     .04       0
  3730.2     .05       0  3942.4     .05       0  4854.3     .12       0
  4965.6     .05       0  5001.5     .12       0  5321.1     .05       0
  5457.4     .12       0  5914.9     .12       0  6267.5     .12       0
  6576.2     .05       0  6686.5     .12       0  6796.7     .05       0
  6925.5     .05       0  7017.1     .12       0  7364.2     .05       0
    7458     .12       0  7583.5     .05       0
Bank Sta=4965.6,5001.5
XS Rating Curve= 0 ,0
Exp/Cntr=0.3,0.1

Type RM Length L Ch R = 1 ,103929  ,899,899,899
BEGIN DESCRIPTION:
Mapping XS 3e158304
END DESCRIPTION:
XS GIS Cut Line= 3
      2481189.74     13542994.49      2481127.24     13541744.46
      2479352.23     13539758.61
#Sta/Elev= 30
  3594.5  261.34  3790.8  257.63  4054.6  255.65  4240.5  251.48  4396.7   247.4
  4775.5  235.72  4882.9   237.4  4918.1  235.83  4944.7     230  4989.1  227.55
    4992  225.02  4992.9  224.52    5028  225.02  5031.7  233.72  5073.6  233.09
    5102  237.56  5138.8  238.17  5178.9  238.69  5321.8   240.1  5413.8  236.83
  5703.9  239.72  6118.1  240.28  6473.3  241.23    6712  243.96  6806.8  245.24
    6855  245.29  6942.4  246.33  7098.5  246.89  7485.1  249.37  7509.6   249.7
#Mann= 17 ,-1 , 0
  3594.5     .05       0  3790.8     .12       0  4240.5     .05       0
  4396.7     .12       0  4944.7      .1       0    4992     .05       0
    5028      .1       0  5138.8     .05       0  5178.9     .12       0
  6118.1     .05       0  6473.3     .12       0    6712     .05       0
  6806.8     .12       0    6855     .05       0  6942.4     .12       0
  7098.5     .05       0  7485.1     .12       0
Bank Sta=4992,5028
XS Rating Curve= 0 ,0
Exp/Cntr=0.3,0.1