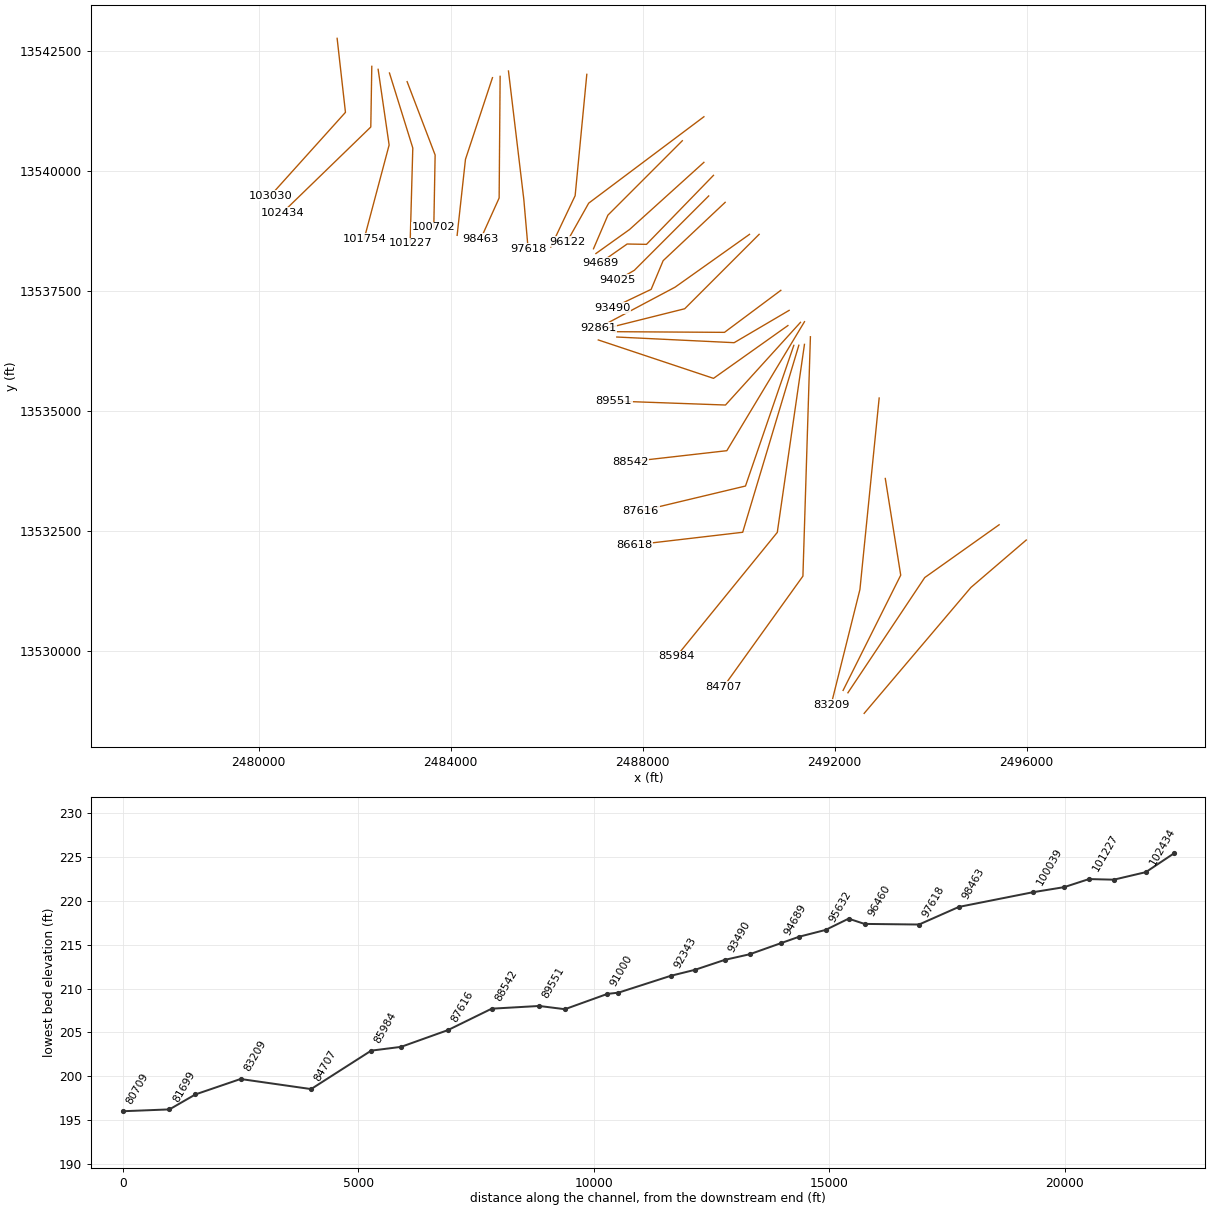
HEC-RAS study TWELVEMILE CREEK.prj: TWELVEMILE CREEK Base Level Engineering

--- TWELVEMILE CREEK.g01 (geometry) --- (continued)

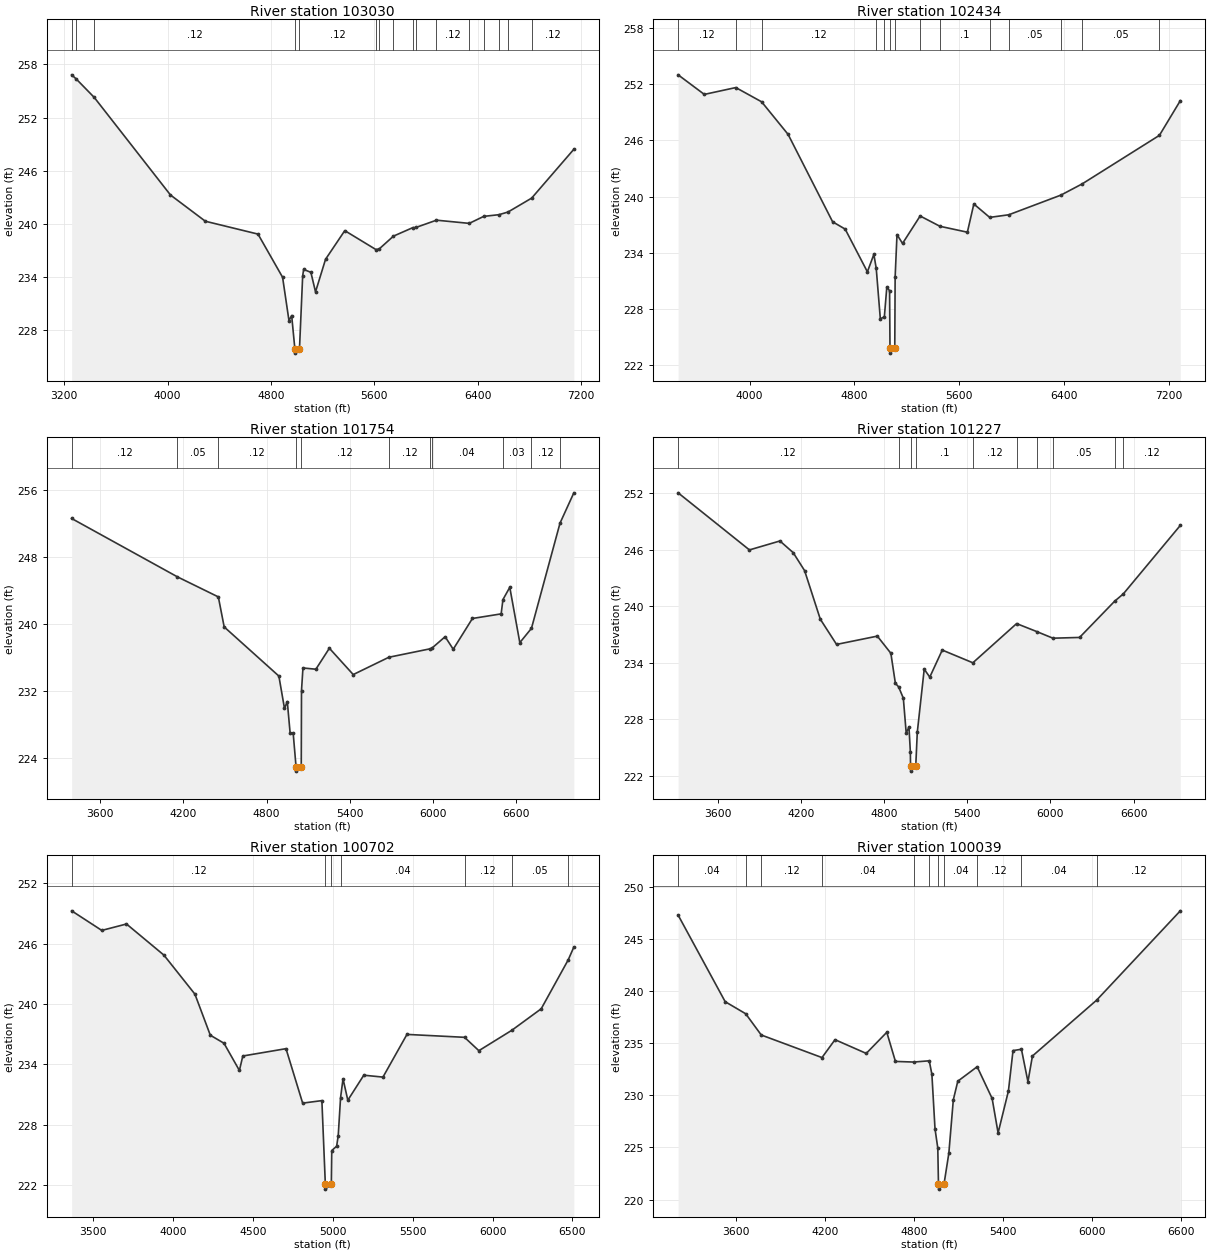
Type RM Length L Ch R = 1 ,103030  ,596,596,596
BEGIN DESCRIPTION:
Mapping XS 38f0748f
END DESCRIPTION:
XS GIS Cut Line= 3
      2481634.19     13542758.34       2481807.8     13541216.69
       2480245.3     13539480.58
#Sta/Elev= 30
  3258.1  256.83  3292.9  256.37    3433  254.28  4023.1  243.27    4293  240.31
  4700.5  238.86  4890.8  233.99  4940.2   229.1  4961.1  229.67  4985.7  225.93
  4986.5  225.43  5021.7  225.93  5046.3  234.15  5053.8  234.87  5109.8  234.55
  5145.7  232.34  5223.4  236.02  5372.2  239.25  5612.8  237.12  5638.2  237.18
  5748.9  238.63  5897.4  239.58  5923.2  239.61  6081.9  240.43  6335.6  240.07
  6447.8  240.86  6565.5  241.05  6635.7  241.35  6818.7  242.92  7145.2  248.43
#Mann= 16 ,-1 , 0
  3258.1     .12       0  3292.9     .05       0    3433     .12       0
  4985.7     .05       0  5021.7     .12       0  5612.8      .1       0
  5638.2     .12       0  5748.9     .05       0  5897.4     .12       0
  5923.2     .05       0  6081.9     .12       0  6335.6     .05       0
  6447.8     .12       0  6565.5    .013       0  6635.7     .05       0
  6818.7     .12       0
Bank Sta=4985.7,5021.7
XS Rating Curve= 0 ,0
Exp/Cntr=0.3,0.1

Type RM Length L Ch R = 1 ,102434  ,680,680,680
BEGIN DESCRIPTION:
Mapping XS 1c5041f2
END DESCRIPTION:
XS GIS Cut Line= 3
      2482356.41     13542175.07      2482335.58     13540911.13
      2480489.42      13539120.5
#Sta/Elev= 30
    3454     253  3654.1  250.91  3894.6  251.64  4091.8  250.12  4294.2  246.64
  4634.2  237.31    4730  236.53  4899.8  231.97  4949.2  233.83  4967.3  232.34
  4998.6  226.95  5029.4  227.17  5048.2  230.35  5069.3  229.95  5072.4  223.79
  5073.3  223.29  5108.9  223.79  5111.7  231.39  5125.9  235.94  5168.3     235
  5302.8  237.93  5454.1  236.83  5663.5   236.2  5712.9  239.21    5834  237.78
  5979.8  238.06    6378  240.16  6540.8  241.36  7130.5  246.54    7290  250.24
#Mann= 14 ,-1 , 0
    3454     .12       0  3894.6     .05       0  4091.8     .12       0
  4967.3      .1       0  5029.4     .12       0  5072.4     .05       0
  5108.9     .12       0  5302.8     .05       0  5454.1      .1       0
    5834     .12       0  5979.8     .05       0    6378    .013       0
  6540.8     .05       0  7130.5     .12       0
Bank Sta=5072.4,5108.9
XS Rating Curve= 0 ,0
Exp/Cntr=0.3,0.1

Type RM Length L Ch R = 1 ,101754  ,527,527,527
BEGIN DESCRIPTION:
Mapping XS 67cc1471
END DESCRIPTION:
XS GIS Cut Line= 3
      2482488.35     13542112.57      2482717.52     13540536.13
      2482196.97     13538578.88
#Sta/Elev= 30
  3395.8  252.65  4157.8  245.67  4452.7  243.27  4494.8  239.68  4888.9   233.8
  4929.3  229.93  4949.5  230.75  4969.7  227.02    4992  226.96  5012.7  222.93
  5013.6  222.43  5050.1  222.93  5051.9  232.07  5062.4  234.77  5155.5  234.62
  5252.7  237.13  5424.6  233.98  5681.1  236.05  5981.1  237.07  5989.4  237.11
  6086.8  238.51  6145.1  237.01  6283.4  240.69  6490.4  241.24  6503.3  242.95
  6552.5  244.42  6624.9   237.8  6708.8  239.51  6914.4  252.09  7014.1  255.72
#Mann= 11 ,-1 , 0
  3395.8     .12       0  4157.8     .05       0  4452.7     .12       0
  5012.7     .05       0  5050.1     .12       0  5681.1     .12       0
  5981.1    .013       0  5989.4     .04       0  6503.3     .03       0
  6708.8     .12       0  6914.4     .05       0
Bank Sta=5012.7,5050.1
XS Rating Curve= 0 ,0
Exp/Cntr=0.3,0.1

Type RM Length L Ch R = 1 ,101227  ,525,525,525
BEGIN DESCRIPTION:
Mapping XS 61220494
END DESCRIPTION:
XS GIS Cut Line= 3
      2482724.47     13542036.11      2483210.58     13540473.63
      2483155.06     13538488.76
#Sta/Elev= 30
  3314.5  252.04  3828.8  245.98  4048.8  246.93  4144.6  245.69  4226.8  243.78
  4339.9  238.63  4457.2  235.95  4751.3  236.83  4848.9  235.01  4881.5  231.82
  4904.6  231.45  4938.9  230.24  4959.5  226.54  4979.5  227.18  4989.5  224.54
  4990.8     223  4991.8   222.5  5028.3     223  5039.5  226.62  5089.5  233.32
  5129.6  232.48  5219.6  235.35  5440.3     234  5755.8  238.16  5899.9  237.32
  6017.9  236.61    6210  236.69  6463.2  240.54  6525.3  241.31  6936.5  248.58
#Mann= 10 ,-1 , 0
  3314.5     .12       0  4904.6      .1       0  4990.8     .05       0
  5028.3      .1       0  5440.3     .12       0  5755.8     .05       0
  5899.9     .12       0  6017.9     .05       0  6463.2     .04       0
  6525.3     .12       0
Bank Sta=4990.8,5028.3
XS Rating Curve= 0 ,0
Exp/Cntr=0.3,0.1

Type RM Length L Ch R = 1 ,100702  ,663,663,663
BEGIN DESCRIPTION:
Mapping XS 749c436a
END DESCRIPTION:
XS GIS Cut Line= 3
      2483092.51     13541855.61      2483675.85      13540327.8
      2483648.08     13538820.84
#Sta/Elev= 30
  3366.4  249.28    3555  247.33  3709.6  247.97  3943.9  244.87  4137.7  240.99
  4234.1   236.9  4319.7   236.1  4416.1  233.39  4437.5  234.83  4707.7  235.56
    4812  230.14  4932.3  230.39  4953.9  222.08  4954.9  221.58  4991.4  222.08
  4994.1  225.42  5024.6  225.85  5034.6  226.91  5049.2  230.68  5064.6  232.56
  5094.6  230.43  5194.6  232.92  5314.5  232.73  5464.7  236.98    5825  236.69
  5914.7  235.36  6120.9  237.39  6304.8  239.53  6473.5  244.39    6509  245.67
#Mann= 7 ,-1 , 0
  3366.4     .12       0  4953.9     .05       0  4991.4     .12       0
  5049.2     .04       0    5825     .12       0  6120.9     .05       0
  6473.5     .12       0
Bank Sta=4953.9,4991.4
XS Rating Curve= 0 ,0
Exp/Cntr=0.3,0.1

Type RM Length L Ch R = 1 ,100039  ,1576,1576,1576
BEGIN DESCRIPTION:
Mapping XS 9601678f
END DESCRIPTION:
XS GIS Cut Line= 3
      2484870.31     13541938.95       2484307.8     13540237.52
      2484134.19     13538654.22
#Sta/Elev= 30
    3212  247.33  3529.2  239.01  3667.5  237.85  3772.3  235.81  4181.7  233.64
  4269.5  235.36    4480  234.04  4618.5  236.07  4676.7  233.27  4799.7  233.21
  4904.6  233.33  4922.4  232.04  4943.5  226.79  4962.2  224.95  4966.8   221.5
  4967.8     221  5004.4   221.5  5036.7  224.45  5066.9  229.58  5097.1  231.37
  5227.6  232.76  5328.5  229.71  5368.7   226.4  5438.3  230.43  5469.3  234.31
    5526  234.44  5569.9  231.32  5600.1  233.79    6033  239.16  6596.8  247.74
#Mann= 11 ,-1 , 0
    3212     .04       0  3667.5     .05       0  3772.3     .12       0
  4181.7     .04       0  4799.7     .03       0  4904.6     .04       0
  4966.8     .04       0  5004.4     .04       0  5227.6     .12       0
    5526     .04       0    6033     .12       0
Bank Sta=4966.8,5004.4
XS Rating Curve= 0 ,0
Exp/Cntr=0.3,0.1

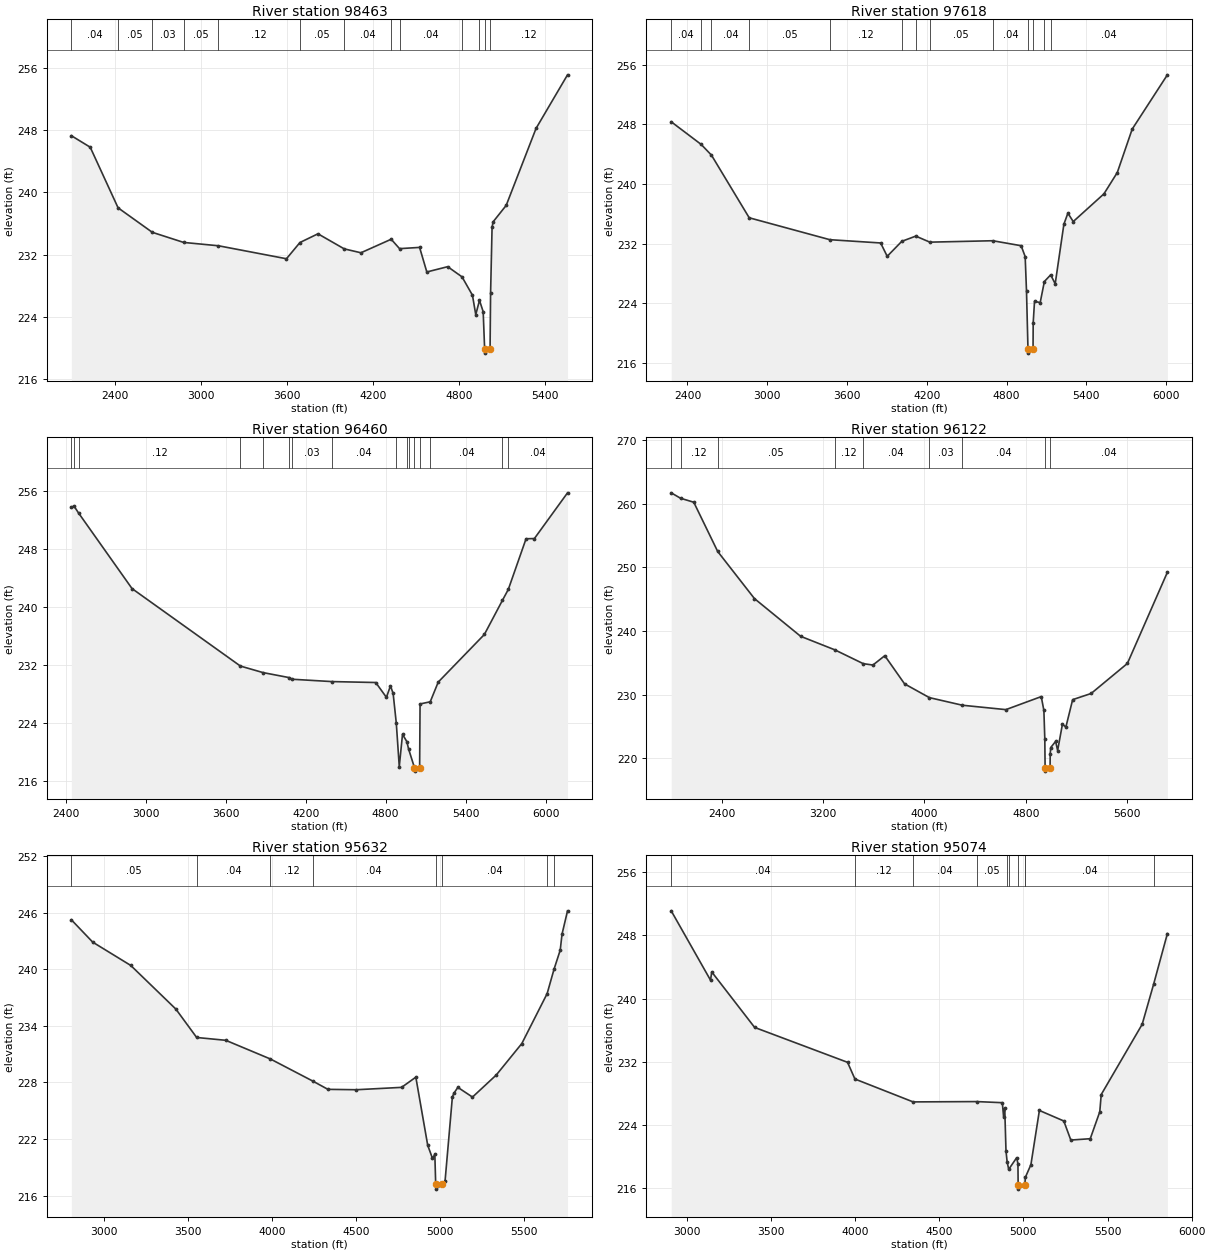
Type RM Length L Ch R = 1 ,98463   ,845,845,845
BEGIN DESCRIPTION:
Mapping XS 080ad2cf
END DESCRIPTION:
XS GIS Cut Line= 3
      2485030.02     13541966.72      2485009.19     13539431.96
      2484627.23     13538584.72
#Sta/Elev= 30
  2093.9  247.29  2225.6  245.81  2420.2  238.01  2659.2  234.86    2878  233.56
  3121.1  233.13  3595.7  231.46    3690  233.55  3815.7  234.67  3999.2  232.73
  4115.7  232.23  4326.9  233.97  4385.3  232.76  4525.3  232.92  4575.7  229.76
  4721.4  230.44  4821.5  229.13  4894.3  226.77  4917.4  224.27  4943.4  226.11
  4969.2  224.65  4979.4  219.82  4980.4  219.32  5017.3  219.82  5020.9     227
  5031.3  235.53  5038.6  236.21    5130  238.33  5338.4  248.23  5558.1  255.12
#Mann= 13 ,-1 , 0
  2093.9     .04       0  2420.2     .05       0  2659.2     .03       0
    2878     .05       0  3121.1     .12       0    3690     .05       0
  3999.2     .04       0  4326.9     .05       0  4385.3     .04       0
  4821.5     .03       0  4943.4     .12       0  4979.4     .05       0
  5017.3     .12       0
Bank Sta=4979.4,5017.3
XS Rating Curve= 0 ,0
Exp/Cntr=0.3,0.1

Type RM Length L Ch R = 1 ,97618   ,1158,1158,1158
BEGIN DESCRIPTION:
Mapping XS e45d2a94
END DESCRIPTION:
XS GIS Cut Line= 3
      2485203.63     13542077.77      2485523.08     13539404.19
      2485613.33     13538369.72
#Sta/Elev= 30
  2277.7  248.35  2503.2  245.31  2580.5  243.87  2864.2  235.47  3470.4  232.53
  3852.6  232.09  3901.9   230.3  4011.6  232.31  4116.7  233.01  4222.6   232.2
  4695.6  232.39  4909.1  231.72  4939.3  230.26  4949.4   225.6  4960.5  217.81
  4961.5  217.31  4998.5  217.81  4999.6  221.35  5009.6  224.24  5052.4   224.1
  5083.7  226.92  5131.1  227.81  5165.1  226.61  5230.5  234.61  5260.6  236.09
  5300.7  234.96  5531.6  238.68    5632  241.54  5743.9  247.36  6008.7  254.65
#Mann= 13 ,-1 , 0
  2277.7     .04       0  2503.2     .05       0  2580.5     .04       0
  2864.2     .05       0  3470.4     .12       0  4011.6      .1       0
  4116.7     .12       0  4222.6     .05       0  4695.6     .04       0
  4960.5     .04       0  4998.5     .04       0  5083.7     .05       0
  5131.1     .04       0
Bank Sta=4960.5,4998.5
XS Rating Curve= 0 ,0
Exp/Cntr=0.3,0.1

Type RM Length L Ch R = 1 ,96460   ,338,338,338
BEGIN DESCRIPTION:
Mapping XS fbac9f40
END DESCRIPTION:
XS GIS Cut Line= 3
      2486835.58     13542008.38      2486592.52     13539480.58
      2486085.57     13538411.11
#Sta/Elev= 30
    2442  253.84  2462.7  253.94  2496.3     253  2897.5  242.57  3710.5  231.88
  3880.2  230.98  4078.8  230.28  4099.8  230.06  4395.1  229.74  4725.9  229.61
  4806.2  227.56  4836.4  229.15  4856.5   228.1  4880.3  223.97  4902.5     218
  4926.8  222.46  4959.2  221.46  4972.5  220.43  5016.2  217.88  5017.2  217.38
  5055.3  217.88  5058.5  226.65  5134.8  226.95  5194.9  229.67    5541  236.24
  5676.5  240.95  5720.7  242.46  5853.8  249.45  5916.4  249.48    6165  255.79
#Mann= 16 ,-1 , 0
    2442     .12       0  2462.7     .05       0  2496.3     .12       0
  3710.5     .03       0  3880.2     .05       0  4078.8     .04       0
  4099.8     .03       0  4395.1     .04       0  4880.3     .05       0
  4959.2     .12       0  4972.5     .05       0  5016.2     .05       0
  5055.3     .05       0  5134.8     .04       0  5676.5     .05       0
  5720.7     .04       0
Bank Sta=5016.2,5055.3
XS Rating Curve= 0 ,0
Exp/Cntr=0.3,0.1

Type RM Length L Ch R = 1 ,96122   ,490,490,490
BEGIN DESCRIPTION:
TWELVEMILE CREEK 143.0
END DESCRIPTION:
XS GIS Cut Line= 3
      2489275.02     13541125.02        2486875.       13539325.
        2486425.     13538525.01
#Sta/Elev= 30
  2000.2  261.74  2073.7  260.89  2178.4  260.26  2367.2  252.52  2657.5  245.11
  3022.1  239.18  3291.1  237.06  3516.5  234.88  3592.9  234.66  3686.7  236.13
  3842.9   231.7  4038.4  229.54  4299.5  228.34  4642.9  227.65  4922.1   229.7
  4942.9  227.52  4950.2  223.04  4952.6  218.48  4953.6  217.98  4991.7  218.48
  4992.9  220.74  4997.1  221.69  5035.6  222.66  5051.5  221.22  5089.2  225.35
  5116.6  224.91  5170.1  229.22  5316.1  230.19  5602.3  234.91  5918.1  249.25
#Mann= 9 ,-1 , 0
  2000.2     .05       0  2073.7     .12       0  2367.2     .05       0
  3291.1     .12       0  3516.5     .04       0  4038.4     .03       0
  4299.5     .04       0  4952.6     .04       0  4991.7     .04       0
Bank Sta=4952.6,4991.7
XS Rating Curve= 0 ,0
Exp/Cntr=0.3,0.1

Type RM Length L Ch R = 1 ,95632   ,558,558,558
BEGIN DESCRIPTION:
TWELVEMILE CREEK 142.0
END DESCRIPTION:
XS GIS Cut Line= 3
      2488824.97     13540624.97        2487275.       13539075.
      2486974.99     13538374.97
#Sta/Elev= 30
  2803.5  245.25  2930.7  242.88    3157  240.41  3425.7  235.78  3549.4  232.77
  3722.7  232.47  3988.4  230.49  4240.4  228.15  4330.8  227.27  4500.5  227.23
  4769.2  227.48  4854.1  228.56  4924.8  221.34  4953.1  219.95  4967.2  220.37
  4972.4  217.19  4973.4  216.69  5011.6  217.19  5028.1  217.55  5071.6  226.45
  5080.7  226.86  5104.3  227.48  5191.3  226.45  5332.8  228.79  5485.1  232.13
  5635.7  237.42  5676.6     240  5713.6  242.03  5724.4  243.73  5757.1   246.2
#Mann= 8 ,-1 , 0
  2803.5     .05       0  3549.4     .04       0  3988.4     .12       0
  4240.4     .04       0  4972.4     .04       0  5011.6     .04       0
  5635.7     .03       0  5676.6     .04       0
Bank Sta=4972.4,5011.6
XS Rating Curve= 0 ,0
Exp/Cntr=0.3,0.1

Type RM Length L Ch R = 1 ,95074   ,385,385,385
BEGIN DESCRIPTION:
TWELVEMILE CREEK 141.0
END DESCRIPTION:
XS GIS Cut Line= 3
      2489275.02     13540175.02        2487725.       13538775.
      2487025.02     13538275.01
#Sta/Elev= 30
  2906.8  251.08  3140.4  242.32  3147.8  243.36  3402.6  236.35  3954.9  231.94
  3998.7  229.83  4344.5  226.94  4723.1  226.98  4874.8  226.84  4882.3  225.07
    4889  226.16  4896.5  220.75  4903.1   219.4  4912.6  218.42    4960  219.89
  4967.5  219.13  4968.8  216.42  4969.8  215.92    5008  216.42  5011.8  217.42
  5044.6  219.01    5095  225.86    5240  224.53  5281.8  222.12  5397.3  222.29
  5453.9  225.69  5462.5  227.87  5705.8  236.74  5773.8   241.8  5855.7   248.2
#Mann= 10 ,-1 , 0
  2906.8     .04       0  3998.7     .12       0  4344.5     .04       0
  4723.1     .05       0  4903.1     .04       0  4912.6     .05       0
  4968.8     .05       0    5008     .05       0  5011.8     .04       0
  5773.8    .013       0
Bank Sta=4968.8,5008
XS Rating Curve= 0 ,0
Exp/Cntr=0.3,0.1

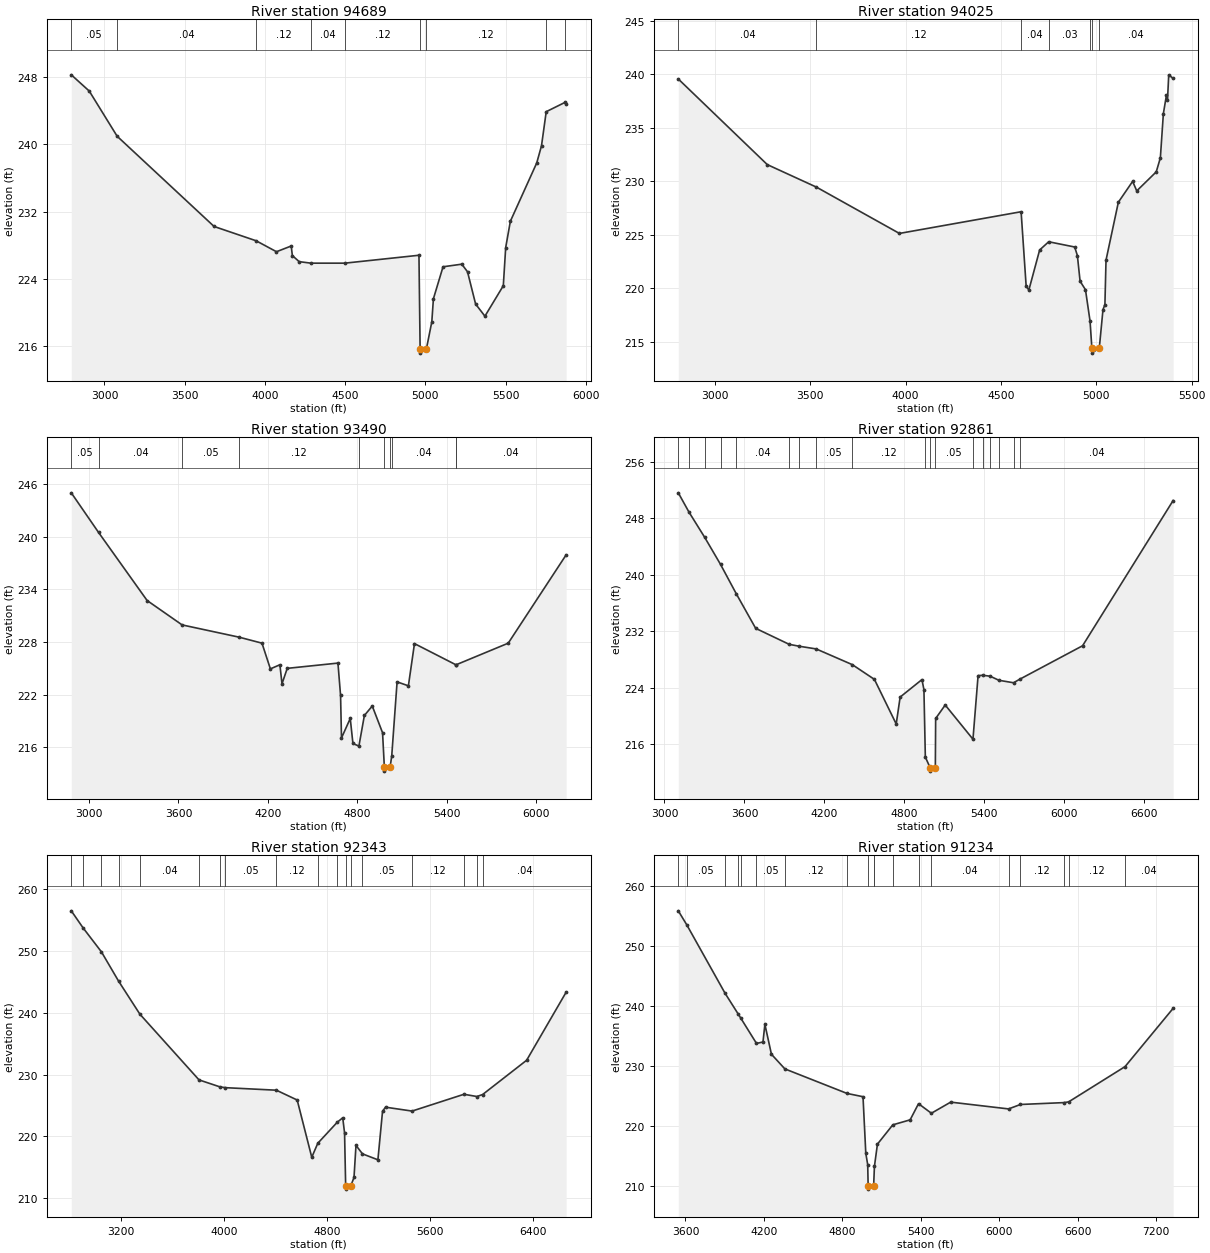
Type RM Length L Ch R = 1 ,94689   ,664,664,664
BEGIN DESCRIPTION:
Mapping XS a80e2ecb
END DESCRIPTION:
XS GIS Cut Line= 4
      2489474.46     13539904.19      2488078.63     13538466.69
      2487675.85     13538473.63      2487120.27     13538084.72
#Sta/Elev= 30
  2793.1  248.26  2905.2  246.33  3079.1  240.96  3683.3  230.24  3945.4  228.54
  4072.2  227.24  4164.1  227.92  4171.2  226.78  4213.7  226.06  4287.4  225.88
  4497.9  225.88  4960.4  226.82  4967.6  215.69  4968.6  215.19  5006.8  215.69
  5040.5  218.91  5050.5  221.65  5110.5  225.45  5227.3  225.76    5263  224.86
  5313.6  221.02  5371.6  219.58  5486.2   223.2  5501.1  227.74  5530.2  230.86
  5694.6  237.79  5724.3  239.83  5753.7  243.88  5870.3  244.98  5877.8  244.74
#Mann= 9 ,-1 , 0
  2793.1     .05       0  3079.1     .04       0  3945.4     .12       0
  4287.4     .04       0  4497.9     .12       0  4967.6     .04       0
  5006.8     .12       0  5753.7    .013       0  5870.3     .04       0
Bank Sta=4967.6,5006.8
XS Rating Curve= 0 ,0
Exp/Cntr=0.3,0.1

Type RM Length L Ch R = 1 ,94025   ,535,535,535
BEGIN DESCRIPTION:
TWELVEMILE CREEK 139.0
END DESCRIPTION:
XS GIS Cut Line= 3
      2489375.01     13539475.01        2487825.       13537925.
      2487474.96     13537724.98
#Sta/Elev= 30
  2807.7  239.57  3274.4  231.56  3532.5  229.45  3967.4  225.12  4605.6  227.15
    4632   220.2  4646.2  219.82  4702.8  223.57  4750.3  224.34  4886.6  223.85
  4900.7  223.05  4914.9  220.65  4943.2  219.85  4967.2  216.91  4976.6  214.42
  4977.6  213.92  5015.8  214.42    5035  217.99  5045.1  218.46  5050.9  222.62
  5115.6  228.04  5190.5  229.99  5212.1   229.1  5314.3  230.88  5335.9  232.19
  5351.7  236.33  5367.6  238.03  5373.3  237.58  5379.8  239.96  5402.9  239.62
#Mann= 7 ,-1 , 0
  2807.7     .04       0  3532.5     .12       0  4605.6     .04       0
  4750.3     .03       0  4967.2     .04       0  4976.6     .04       0
  5015.8     .04       0
Bank Sta=4976.6,5015.8
XS Rating Curve= 0 ,0
Exp/Cntr=0.3,0.1

Type RM Length L Ch R = 1 ,93490   ,629,629,629
BEGIN DESCRIPTION:
Mapping XS 56a12009
END DESCRIPTION:
XS GIS Cut Line= 4
      2489717.55     13539341.71      2488425.85     13538126.41
      2488175.85     13537529.19       2487363.4     13537140.32
#Sta/Elev= 30
  2880.6  244.98  3063.6  240.47  3389.6  232.71  3624.5  229.93    4008  228.53
  4160.7  227.85    4217  224.92  4280.9  225.39  4295.1  223.22  4330.2  224.98
  4670.6  225.58  4688.2  221.89  4694.4  217.05  4753.2  219.27  4771.2  216.42
  4811.3  216.12    4848  219.61    4901  220.69  4970.1  217.64    4982  213.77
    4983  213.27  5021.2  213.77  5031.8  215.03  5067.6  223.44  5143.5  222.99
  5184.3   227.8    5461   225.4  5464.1  225.39  5813.7  227.85  6202.3  237.91
#Mann= 10 ,-1 , 0
  2880.6     .05       0  3063.6     .04       0  3624.5     .05       0
    4008     .12       0  4811.3     .04       0    4982     .05       0
  5021.2     .04       0  5031.8     .04       0    5461     .05       0
  5464.1     .04       0
Bank Sta=4982,5021.2
XS Rating Curve= 0 ,0
Exp/Cntr=0.3,0.1

Type RM Length L Ch R = 1 ,92861   ,518,518,518
BEGIN DESCRIPTION:
TWELVEMILE CREEK 137.0
END DESCRIPTION:
XS GIS Cut Line= 3
      2490224.96     13538674.97        2488675.       13537575.
      2487074.98     13536724.99
#Sta/Elev= 30
  3103.7  251.63    3184  248.89  3302.2   245.3  3420.4  241.48  3538.6  237.31
  3684.3   232.4  3935.9  230.13  4011.4  229.86    4138  229.48  4409.2  227.25
    4575  225.16  4738.6  218.83  4768.1  222.65  4931.7  225.13  4946.5   223.7
  4957.1  214.13  4992.8  212.64  4993.8  212.14  5032.1  212.64  5034.5  219.61
  5106.2  221.52  5314.4  216.67  5352.8  225.69  5388.7  225.74  5443.3  225.61
    5509  225.03  5618.7  224.68  5665.3  225.18  6136.7  229.93  6816.1  250.54
#Mann= 18 ,-1 , 0
  3103.7     .03       0    3184    .013       0  3302.2     .04       0
  3420.4     .05       0  3538.6     .04       0  3935.9     .05       0
  4011.4     .12       0    4138     .05       0  4409.2     .12       0
  4957.1     .05       0  4992.8     .05       0  5032.1     .05       0
  5314.4     .05       0  5388.7     .04       0  5443.3     .05       0
    5509     .04       0  5618.7     .05       0  5665.3     .04       0
Bank Sta=4992.8,5032.1
XS Rating Curve= 0 ,0
Exp/Cntr=0.3,0.1

Type RM Length L Ch R = 1 ,92343   ,1109,1109,1109
BEGIN DESCRIPTION:
TWELVEMILE CREEK 136.0
END DESCRIPTION:
XS GIS Cut Line= 3
      2490424.97     13538674.97        2488875.       13537125.
      2487275.03     13536725.01
#Sta/Elev= 30
  2812.4  256.52  2903.2  253.78  3046.6  249.87  3179.4  245.14  3345.1  239.78
    3804  229.14  3967.7     228  4009.4  227.88  4404.5  227.47    4566  225.88
  4679.1  216.61    4726  218.88  4877.8   222.3  4919.5     223  4933.7  220.56
  4942.3  211.95  4943.3  211.45  4981.6  211.95    5007  213.34  5022.4  218.53
  5072.9  217.16  5192.5   216.2  5228.6  224.07  5251.8  224.72  5457.8  224.09
  5860.3  226.81    5961  226.45  6005.4  226.77    6347  232.32  6653.6  243.34
#Mann= 18 ,-1 , 0
  2812.4     .04       0  2903.2     .03       0  3046.6    .013       0
  3179.4     .05       0  3345.1     .04       0    3804     .05       0
  3967.7     .04       0  4009.4     .05       0  4404.5     .12       0
    4726     .05       0  4877.8      .1       0  4942.3     .05       0
  4981.6      .1       0  5072.9     .05       0  5457.8     .12       0
  5860.3     .04       0    5961     .12       0  6005.4     .04       0
Bank Sta=4942.3,4981.6
XS Rating Curve= 0 ,0
Exp/Cntr=0.3,0.1

Type RM Length L Ch R = 1 ,91234   ,234,234,234
BEGIN DESCRIPTION:
Mapping XS 9e34f1d3
END DESCRIPTION:
XS GIS Cut Line= 3
      2490877.28     13537508.38      2489703.63     13536633.35
      2487384.21     13536647.24
#Sta/Elev= 30
  3545.4  255.85  3610.7   253.5    3903  242.13  4002.7   238.7  4023.1  237.99
  4143.3  233.78  4192.9  234.02  4207.5  236.96  4257.5  231.98  4360.3  229.54
  4835.2  225.46  4957.7  224.91    4979  215.48  4993.6  213.61    4997  210.03
    4998  209.53  5038.9  210.03    5045  213.31    5068  217.02  5185.4  220.23
    5318  221.06  5382.1  223.75  5480.4  222.16    5628  224.01  6070.5  222.88
  6161.7  223.62  6493.8  223.93  6529.6  224.05    6961  229.92  7328.8  239.62
#Mann= 19 ,-1 , 0
  3545.4     .12       0  3610.7     .05       0    3903    .013       0
  4002.7     .05       0  4023.1    .013       0  4143.3     .05       0
  4360.3     .12       0  4835.2     .05       0    4997     .05       0
  5038.9     .05       0    5045     .03       0  5185.4     .04       0
  5382.1     .05       0  5480.4     .04       0  6070.5     .05       0
  6161.7     .12       0  6493.8     .05       0  6529.6     .12       0
    6961     .04       0
Bank Sta=4997,5038.9
XS Rating Curve= 0 ,0
Exp/Cntr=0.3,0.1

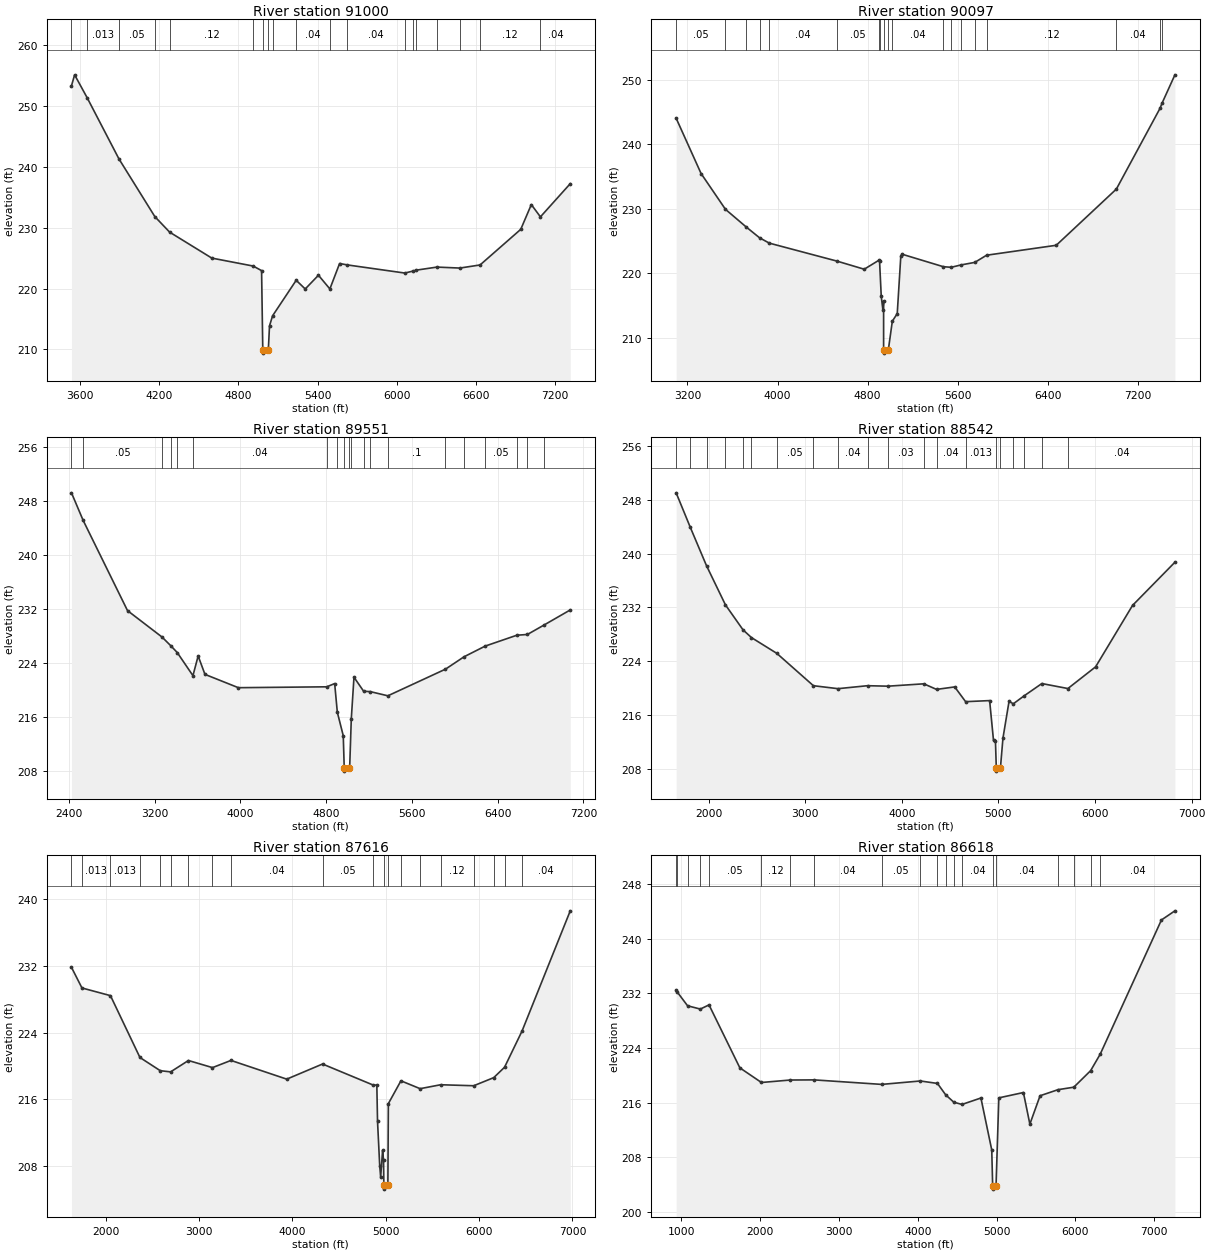
Type RM Length L Ch R = 1 ,91000   ,903,903,903
BEGIN DESCRIPTION:
Mapping XS 386d8335
END DESCRIPTION:
XS GIS Cut Line= 3
       2491050.9     13537091.71      2489905.02     13536418.08
      2487460.59     13536536.13
#Sta/Elev= 30
  3536.6  253.35  3560.3  255.16  3656.3  251.35  3896.1  241.33  4167.5  231.85
  4279.7  229.29    4599  225.02  4912.4  223.71    4976  222.96  4985.1  209.89
  4986.1  209.39    5027  209.89    5036  213.88  5059.3  215.53    5238  221.37
  5306.4  219.94  5406.5   222.2    5493  219.95  5566.7  224.13  5624.2   223.9
  6060.4  222.56  6121.5  222.88    6148  223.04  6303.9  223.54    6477  223.38
  6630.3  223.89  6938.3  229.75  7018.3  233.82  7087.2   231.8  7313.1  237.26
#Mann= 19 ,-1 , 0
  3536.6     .05       0  3656.3    .013       0  3896.1     .05       0
  4167.5    .013       0  4279.7     .12       0  4912.4     .05       0
  4985.1     .05       0    5027     .05       0  5059.3     .03       0
    5238     .04       0    5493     .12       0  5624.2     .04       0
  6060.4     .05       0  6121.5     .04       0    6148     .05       0
  6303.9     .12       0    6477     .05       0  6630.3     .12       0
  7087.2     .04       0
Bank Sta=4985.1,5027
XS Rating Curve= 0 ,0
Exp/Cntr=0.3,0.1

Type RM Length L Ch R = 1 ,90097   ,546,546,546
BEGIN DESCRIPTION:
TWELVEMILE CREEK 133.0
END DESCRIPTION:
XS GIS Cut Line= 3
      2491024.96     13536774.97        2489475.       13535675.
      2487075.03     13536474.99
#Sta/Elev= 30
  3099.4  244.04  3320.8  235.47  3537.5  229.92  3722.1  227.18  3840.3  225.51
  3927.3  224.68  4529.4  221.89    4770  220.64  4904.1  222.07  4906.4  221.84
  4921.3  216.42  4936.1  214.32  4942.2  215.74  4942.3  208.14  4943.3  207.64
  4984.2  208.14  5019.7  212.59  5063.3  213.76  5094.9  222.64  5105.4  222.97
  5472.8  221.03  5542.9  220.94  5631.3  221.31  5752.2   221.7  5856.9  222.81
  6475.7  224.35  7009.8  233.06  7397.5  245.57  7415.8  246.38  7529.8  250.76
#Mann= 19 ,-1 , 0
  3099.4     .05       0  3537.5     .12       0  3722.1    .013       0
  3840.3     .12       0  3927.3     .04       0  4529.4     .05       0
  4904.1     .04       0  4906.4     .12       0  4942.3     .05       0
  4984.2     .12       0  5019.7     .04       0  5472.8     .05       0
  5542.9     .04       0  5631.3     .05       0  5752.2     .04       0
  5856.9     .12       0  7009.8     .04       0  7397.5     .05       0
  7415.8     .04       0
Bank Sta=4942.3,4984.2
XS Rating Curve= 0 ,0
Exp/Cntr=0.3,0.1

Type RM Length L Ch R = 1 ,89551   ,1009,1009,1009
BEGIN DESCRIPTION:
Mapping XS a68aa2cc
END DESCRIPTION:
XS GIS Cut Line= 3
      2491286.95     13536841.67      2489724.47     13535119.46
      2487399.02     13535202.76
#Sta/Elev= 30
    2425  249.17  2533.4  245.11  2947.6  231.75  3269.6  227.84  3352.1  226.54
  3411.5  225.55  3557.9  222.13  3606.5  225.04    3670  222.32  3981.6  220.35
  4806.1  220.48  4879.9  220.96  4904.6  216.72    4960  213.25    4969  208.51
    4970  208.01  5010.9  208.51    5020   208.6  5034.9  215.72    5060   221.9
  5150.1  219.82  5211.8  219.77  5376.1  219.15  5913.4  223.09  6086.5  224.92
  6283.5   226.5    6579  228.11  6677.5  228.22  6830.8   229.6  7077.3  231.85
#Mann= 20 ,-1 , 0
    2425    .013       0  2533.4     .05       0  3269.6     .12       0
  3352.1     .05       0  3411.5    .013       0  3557.9     .04       0
  4806.1     .05       0  4904.6      .1       0    4969     .05       0
  5010.9      .1       0  5034.9     .12       0  5150.1     .05       0
  5211.8     .12       0  5376.1      .1       0  5913.4     .05       0
  6086.5     .12       0  6283.5     .05       0    6579     .12       0
  6677.5     .05       0  6830.8     .12       0
Bank Sta=4969,5010.9
XS Rating Curve= 0 ,0
Exp/Cntr=0.3,0.1

Type RM Length L Ch R = 1 ,88542   ,926,926,926
BEGIN DESCRIPTION:
Mapping XS 1dd50609
END DESCRIPTION:
XS GIS Cut Line= 3
      2491370.28     13536855.55      2489752.24     13534168.08
       2487739.2     13533939.01
#Sta/Elev= 30
    1664  249.01  1810.2   243.9  1978.4  238.19  2174.3  232.38  2356.4  228.67
  2443.9  227.52  2706.2  225.18  3084.7  220.38  3339.1  219.94    3645  220.38
  3856.4  220.31    4228  220.66  4359.3  219.83  4547.6   220.2  4660.3  218.01
  4908.9  218.17  4949.2  212.25  4969.3  212.16    4978   208.2    4979   207.7
  5020.9   208.2    5047   212.6  5110.2  218.08  5153.5  217.69  5264.7  218.86
  5449.5   220.7  5719.2  219.96  6005.9  223.18  6388.4   232.3    6827  238.71
#Mann= 20 ,-1 , 0
    1664     .05       0  1810.2    .013       0  1978.4     .05       0
  2174.3     .05       0  2356.4     .05       0  2443.9     .12       0
  2706.2     .05       0  3084.7    .013       0  3339.1     .04       0
    3645    .013       0  3856.4     .03       0    4228     .04       0
  4359.3     .04       0  4660.3    .013       0    4978     .04       0
  5020.9     .04       0  5153.5     .04       0  5264.7     .12       0
  5449.5     .05       0  5719.2     .04       0
Bank Sta=4978,5020.9
XS Rating Curve= 0 ,0
Exp/Cntr=0.3,0.1

Type RM Length L Ch R = 1 ,87616   ,998,998,998
BEGIN DESCRIPTION:
Mapping XS f18b8d84
END DESCRIPTION:
XS GIS Cut Line= 3
      2491148.07     13536362.51      2490141.13     13533431.96
      2487960.58     13532911.13
#Sta/Elev= 30
  1635.6   231.8  1747.7  229.33    2053  228.41  2368.7  221.01  2586.4  219.43
    2697  219.29  2887.9  220.65  3145.5   219.8  3343.5  220.66  3940.5  218.42
  4323.9  220.23  4866.5  217.71  4905.1  217.71  4912.6  213.37    4936  208.06
  4946.2   206.7  4966.8  209.89  4977.1  208.71  4980.4  205.76  4981.4  205.26
  5023.4  205.76  5028.5  215.49  5163.2  218.22  5368.6  217.28  5588.8  217.75
  5942.5  217.63  6156.8   218.6  6272.4  219.84  6460.1  224.18  6976.2  238.56
#Mann= 20 ,-1 , 0
  1635.6    .013       0  1747.7    .013       0    2053    .013       0
  2368.7    .013       0  2586.4    .013       0    2697     .12       0
  2887.9    .013       0  3145.5     .03       0  3343.5     .04       0
  4323.9     .05       0  4866.5      .1       0  4980.4     .05       0
  5023.4      .1       0  5163.2     .04       0  5368.6     .04       0
  5588.8     .12       0  5942.5     .12       0  6156.8     .12       0
  6272.4     .05       0  6460.1     .04       0
Bank Sta=4980.4,5023.4
XS Rating Curve= 0 ,0
Exp/Cntr=0.3,0.1

Type RM Length L Ch R = 1 ,86618   ,634,634,634
BEGIN DESCRIPTION:
TWELVEMILE CREEK 128.0
END DESCRIPTION:
XS GIS Cut Line= 3
      2491252.57     13536364.49      2490083.02     13532468.66
      2487834.85     13532205.65
#Sta/Elev= 30
   932.4  232.44   947.8  232.15  1077.5  230.16  1239.2  229.68  1349.7  230.29
  1741.2  221.08  2015.1  218.94    2381   219.3    2685  219.32  3541.4  218.66
  4032.4  219.16  4249.5   218.8  4353.3  217.14  4457.1  216.05    4561  215.73
    4801  216.67  4938.5  209.07    4950  203.84    4951  203.34    4993  203.84
  5028.2  216.69  5340.3  217.47  5422.3  212.85  5551.8     217  5780.1  217.89
    5980  218.25  6193.7  220.67  6315.1  223.08  7092.2  242.71  7263.5  244.05
#Mann= 20 ,-1 , 0
   932.4     .05       0   947.8     .12       0  1077.5     .05       0
  1239.2     .12       0  1349.7     .05       0  2015.1     .12       0
    2381     .03       0    2685     .04       0  3541.4     .05       0
  4032.4    .013       0  4249.5     .03       0  4353.3     .04       0
  4457.1     .03       0    4561     .04       0    4950     .04       0
    4993     .04       0  5780.1     .04       0    5980     .12       0
  6193.7    .013       0  6315.1     .04       0
Bank Sta=4950,4993
XS Rating Curve= 0 ,0
Exp/Cntr=0.3,0.1

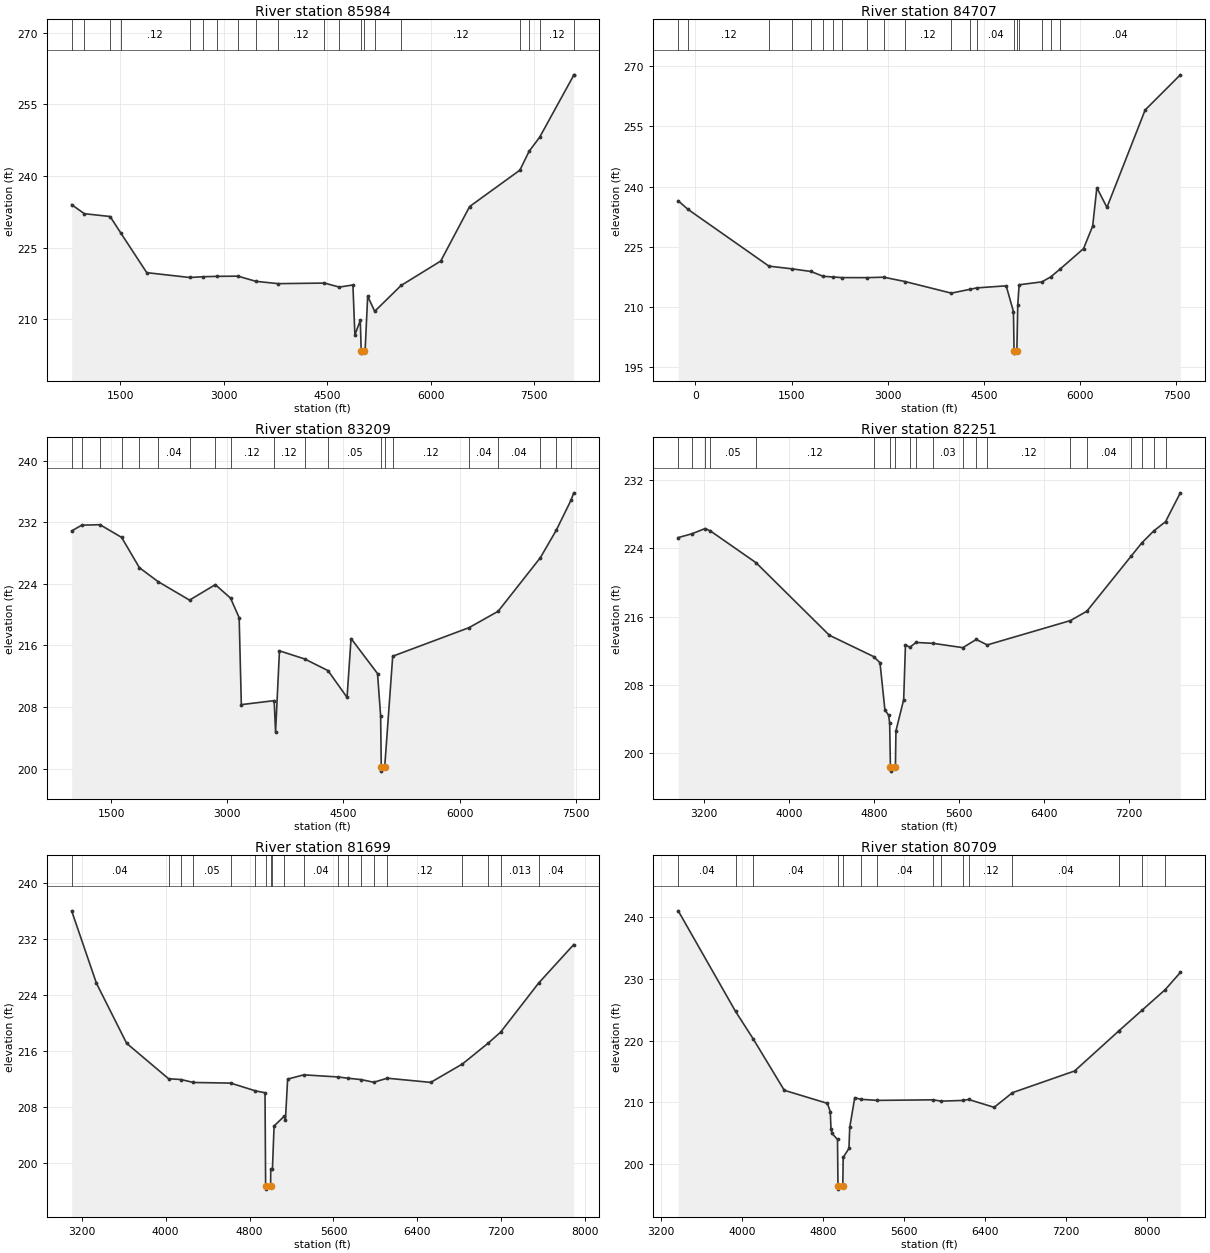
Type RM Length L Ch R = 1 ,85984   ,1277,1277,1277
BEGIN DESCRIPTION:
Mapping XS a3f8e5e6
END DESCRIPTION:
XS GIS Cut Line= 3
      2491369.76     13536382.72      2490803.62     13532466.07
      2488708.09     13529888.97
#Sta/Elev= 30
   796.8  233.98   980.7  232.09  1354.5   231.5  1507.5  228.09  1885.7  219.75
  2507.6  218.74  2707.6   218.9  2907.6  218.98  3207.7  219.02    3467  217.94
  3792.3  217.45  4461.7  217.57  4677.2  216.73  4874.4  217.18  4903.1  206.72
  4981.4  209.75  4994.7  203.41  4995.7  202.91  5038.5  203.41    5052  203.69
  5088.5  214.83  5190.1  211.66  5572.9  217.07  6147.5  222.18  6566.6  233.59
    7295   241.2  7428.3  245.14    7582   248.1  8075.4  261.06  8075.7  261.15
#Mann= 20 ,-1 , 0
   796.8     .05       0   980.7     .12       0  1354.5     .05       0
  1507.5     .12       0  2507.6    .013       0  2707.6     .05       0
  2907.6     .05       0  3207.7    .013       0    3467     .12       0
  3792.3     .12       0  4461.7     .04       0  4677.2     .04       0
  4994.7     .03       0  5038.5     .03       0  5190.1     .12       0
  5572.9     .12       0    7295     .05       0  7428.3     .05       0
    7582     .12       0  8075.4     .05       0
Bank Sta=4994.7,5038.5
XS Rating Curve= 0 ,0
Exp/Cntr=0.3,0.1

Type RM Length L Ch R = 1 ,84707   ,1498,1498,1498
BEGIN DESCRIPTION:
Mapping XS c4ba3441
END DESCRIPTION:
XS GIS Cut Line= 3
      2491493.72     13536541.63      2491337.47     13531554.61
      2489683.85     13529249.96
#Sta/Elev= 30
  -266.5  236.48  -116.3  234.37  1147.2   220.2  1504.1  219.53  1800.7  218.87
  1991.6  217.67  2150.8  217.49  2282.7  217.34  2674.9  217.33    2936  217.44
  3268.5  216.36  3990.2  213.47  4276.9  214.41  4388.6  214.78  4845.6  215.29
  4958.8  208.86  4968.1  199.02  4969.1  198.52    5012  199.02  5025.7  210.49
  5046.9  215.55    5403  216.28  5539.2  217.51  5687.3  219.49  6051.1  224.56
  6193.6  230.19  6258.6  239.74  6415.8  234.83  7011.4  259.11  7559.5  267.87
#Mann= 20 ,-1 , 0
  -266.5     .12       0  -116.3     .12       0  1147.2     .12       0
  1504.1     .05       0  1800.7     .12       0  1991.6     .05       0
  2150.8     .05       0  2282.7     .04       0  2674.9     .05       0
    2936     .12       0  3268.5     .12       0  3990.2     .04       0
  4276.9     .05       0  4388.6     .04       0  4968.1     .03       0
    5012     .03       0  5046.9     .12       0    5403    .013       0
  5539.2     .12       0  5687.3     .04       0
Bank Sta=4968.1,5012
XS Rating Curve= 0 ,0
Exp/Cntr=0.3,0.1

Type RM Length L Ch R = 1 ,83209   ,958,958,958
BEGIN DESCRIPTION:
TWELVEMILE CREEK 124.0
END DESCRIPTION:
XS GIS Cut Line= 3
      2492926.01     13535265.51        2492525.       13531275.
      2491924.99     13528874.97
#Sta/Elev= 30
   989.8  230.88  1120.6  231.63  1355.9  231.69  1635.2  230.04    1865   226.1
  2106.9  224.29  2512.4  221.89  2845.3   223.9  3041.9  222.15  3153.2  219.61
  3181.3  208.31  3605.3  208.83  3623.5  204.74  3673.8   215.3  3997.8  214.25
  4300.8  212.73  4546.7  209.25  4598.4   216.9  4940.1  212.35  4980.3  206.89
  4988.7  200.17  4989.7  199.67  5032.7  200.17  5136.4   214.6  6121.9  218.31
  6498.2  220.44  7042.9   227.4  7247.6  230.95  7439.8  234.89  7474.3  235.83
#Mann= 20 ,-1 , 0
   989.8     .04       0  1120.6     .05       0  1355.9     .04       0
  1635.2     .05       0    1865     .04       0  2106.9     .04       0
  2512.4     .12       0  2845.3     .05       0  3041.9     .12       0
  3605.3     .12       0  3997.8     .05       0  4300.8     .05       0
  4988.7     .05       0  5032.7      .1       0  5136.4     .12       0
  6121.9     .04       0  6498.2     .04       0  7042.9     .12       0
  7247.6     .05       0  7439.8     .04       0
Bank Sta=4988.7,5032.7
XS Rating Curve= 0 ,0
Exp/Cntr=0.3,0.1

Type RM Length L Ch R = 1 ,82251   ,552,552,552
BEGIN DESCRIPTION:
TWELVEMILE CREEK 122.0
END DESCRIPTION:
XS GIS Cut Line= 3
      2493053.53     13533589.26        2493375.       13531575.
      2492175.02     13529175.03
#Sta/Elev= 30
  2960.6  225.26  3088.1   225.7  3214.1  226.32  3262.8  226.04  3692.2  222.32
  4382.6  213.82  4797.9  211.33  4858.6  210.61  4904.7  205.09  4939.6  204.45
  4949.7  203.52  4956.6  198.41  4957.6  197.91  5003.7  198.41  5008.7  202.63
  5081.4  206.28  5098.2   212.7  5139.8  212.41  5196.8  212.98  5361.1  212.87
    5638  212.37    5764  213.33  5867.6  212.69  6650.2  215.54  6804.5  216.64
  7220.7  223.08    7321  224.63    7433  226.03  7544.6  227.12  7683.6   230.5
#Mann= 20 ,-1 , 0
  2960.6     .12       0  3088.1     .05       0  3214.1     .04       0
  3262.8     .05       0  3692.2     .12       0  4797.9     .04       0
  4956.6     .04       0  5003.7     .04       0  5139.8     .03       0
  5196.8     .04       0  5361.1     .03       0    5638     .04       0
    5764     .05       0  5867.6     .12       0  6650.2     .04       0
  6804.5     .04       0  7220.7     .04       0    7321     .12       0
    7433    .013       0  7544.6     .12       0
Bank Sta=4956.6,5003.7
XS Rating Curve= 0 ,0
Exp/Cntr=0.3,0.1

Type RM Length L Ch R = 1 ,81699   ,990,990,990
BEGIN DESCRIPTION:
TWELVEMILE CREEK 121.0
END DESCRIPTION:
XS GIS Cut Line= 3
      2495425.03     13532625.02        2493875.       13531525.
      2492275.02     13529125.03
#Sta/Elev= 30
  3104.9  235.99  3341.1  225.64    3629  217.05  4029.3  211.98  4147.5  211.87
  4265.7  211.45  4620.3  211.36  4856.7  210.25  4947.8  209.98  4953.6   196.7
  4954.6   196.2    5001   196.7  5002.5  199.11  5018.4  199.03  5034.1  205.23
  5131.5  206.63  5142.3  206.07  5163.3  211.93  5316.9  212.54  5641.7  212.24
  5742.9  212.05  5863.7  211.86  5984.5  211.48  6112.4  212.06  6527.4  211.46
  6829.8   214.1  7071.3  217.03  7192.1  218.63  7554.4  225.64    7890  231.17
#Mann= 20 ,-1 , 0
  3104.9     .04       0  4029.3     .12       0  4147.5     .12       0
  4265.7     .05       0  4620.3     .12       0  4856.7     .05       0
  4953.6     .04       0    5001     .05       0  5018.4     .05       0
  5131.5     .04       0  5316.9     .04       0  5641.7     .04       0
  5742.9     .03       0  5863.7     .04       0  5984.5     .04       0
  6112.4     .12       0  6829.8     .04       0  7071.3    .013       0
  7192.1    .013       0  7554.4     .04       0
Bank Sta=4953.6,5001
XS Rating Curve= 0 ,0
Exp/Cntr=0.3,0.1

Type RM Length L Ch R = 1 ,80709   ,713,713,713
BEGIN DESCRIPTION:
Mapping XS 9a3b2b2b
END DESCRIPTION:
XS GIS Cut Line= 3
      2495990.11     13532306.98      2494835.58     13531317.38
      2492613.34     13528695.83
#Sta/Elev= 30
  3372.1  240.96    3938  224.71    4113  220.25  4419.3  211.96    4845  209.85
  4873.5  208.49  4880.3  205.76  4890.7  204.99  4944.7  204.01  4949.5  196.49
  4950.5  195.99    4997  196.49  5000.7  201.11  5057.8  202.57  5065.6  205.99
    5115  210.77  5172.2  210.51  5338.3  210.33  5887.5  210.42  5968.9  210.21
  6180.2  210.32  6238.5  210.48  6491.4  209.21  6672.3  211.58  7285.6  215.08
  7723.2  221.57  7724.3  221.59  7954.9  224.95  8180.1  228.22  8329.4     231
#Mann= 16 ,-1 , 0
  3372.1     .04       0    3938    .013       0    4113     .04       0
  4949.5     .04       0    4997     .04       0  5172.2     .05       0
  5338.3     .04       0  5887.5     .05       0  5968.9     .04       0
  6180.2     .05       0  6238.5     .12       0  6672.3     .04       0
  7723.2     .03       0  7724.3     .04       0  7954.9     .03       0
  8180.1     .04       0
Bank Sta=4949.5,4997
XS Rating Curve= 0 ,0
Exp/Cntr=0.3,0.1