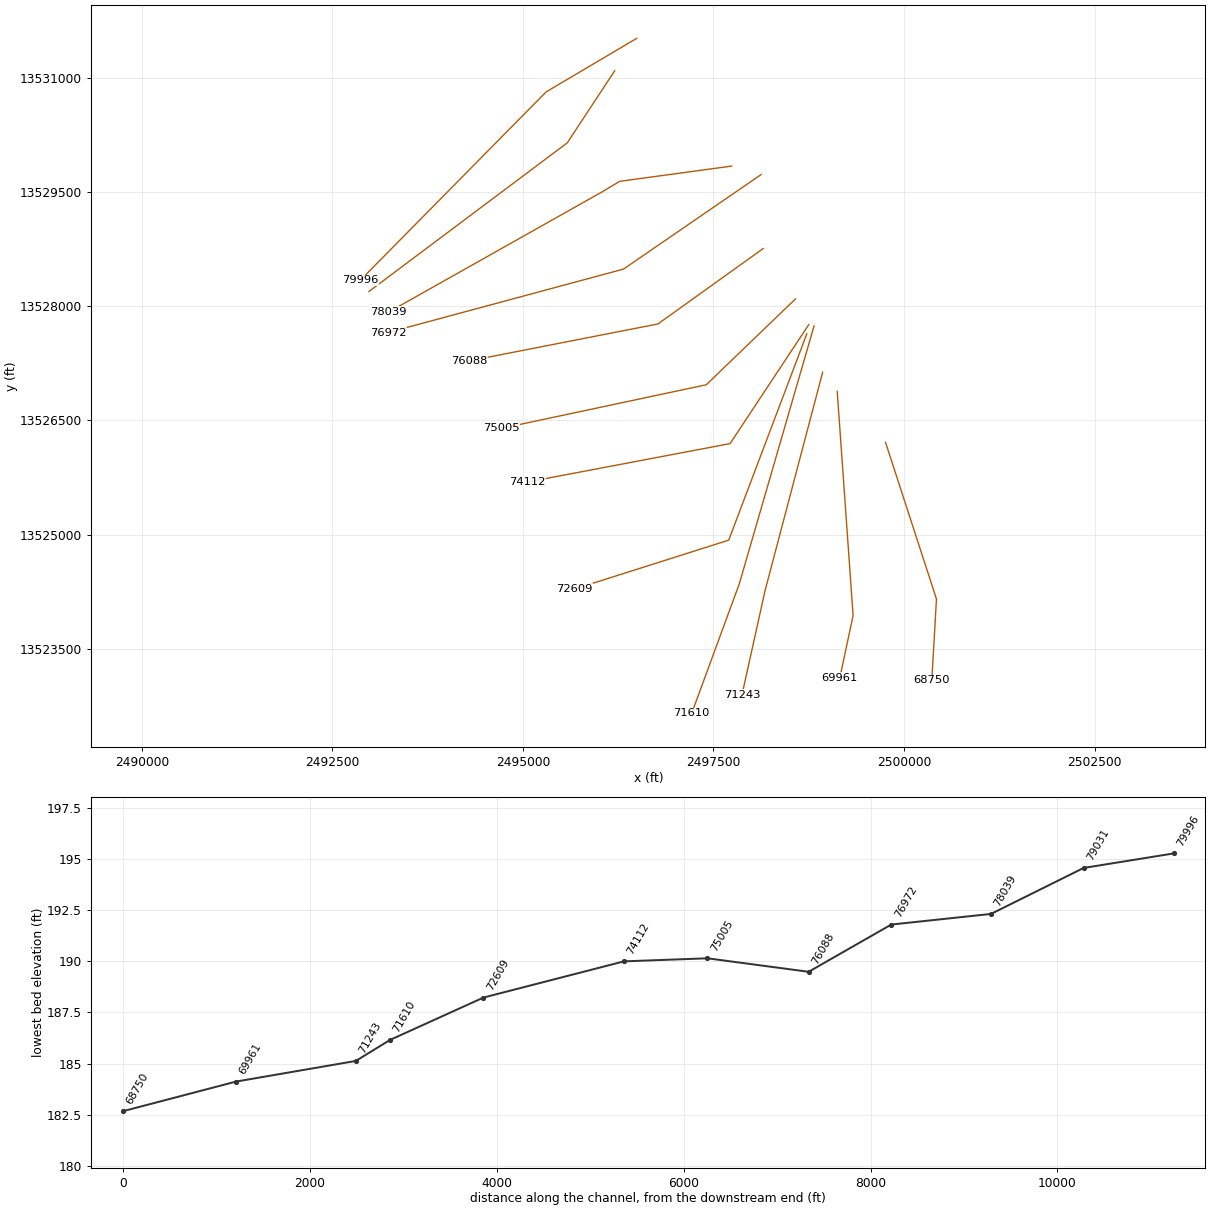
HEC-RAS study TWELVEMILE CREEK.prj: TWELVEMILE CREEK Base Level Engineering

--- TWELVEMILE CREEK.g01 (geometry) --- (continued)

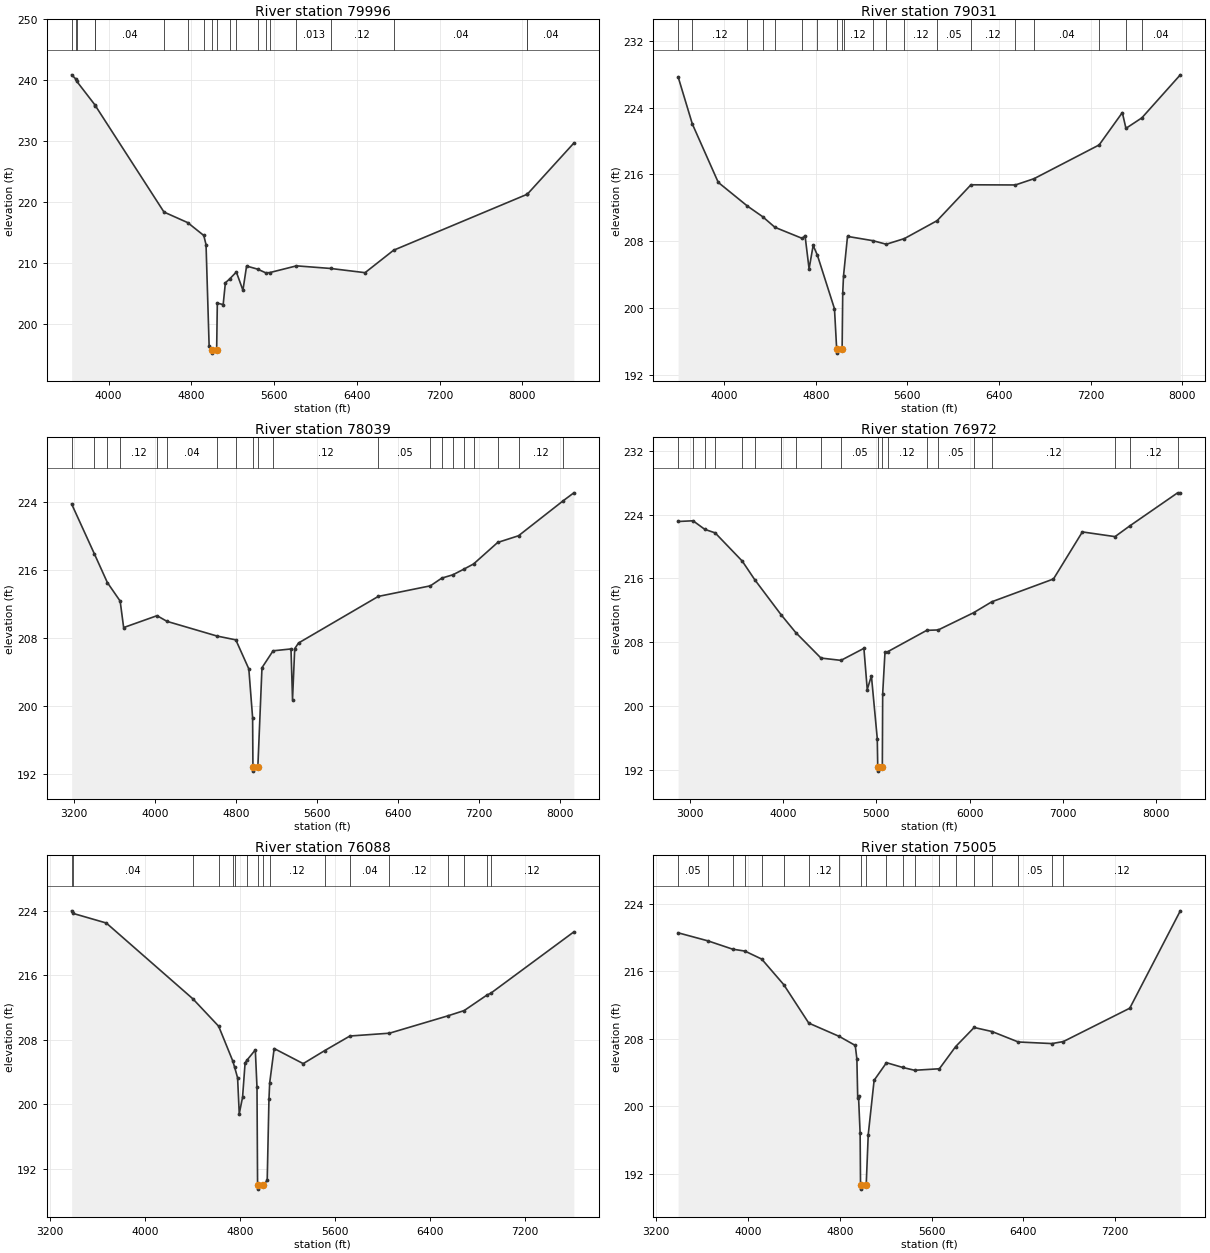
Type RM Length L Ch R = 1 ,79996   ,965,965,965
BEGIN DESCRIPTION:
Mapping XS 5c6a3b5c
END DESCRIPTION:
XS GIS Cut Line= 3
      2496493.55     13531517.03      2495304.33     13530813.91
      2492865.14       13528340.
#Sta/Elev= 30
  3641.9  240.91  3685.2  240.17  3692.5  239.82  3864.7  236.03    3872  235.83
  4534.7  218.41  4763.8  216.68  4919.5  214.57  4941.3  213.06  4971.3  196.42
  4996.3  195.78  4997.3  195.28  5043.9  195.78  5050.4  203.47    5107  203.24
  5128.3  206.81  5169.4  207.44  5234.4  208.58    5298  205.59  5333.3  209.56
  5441.7  209.04  5519.2  208.44  5558.7  208.49  5815.9  209.59  6146.5  209.16
  6478.9  208.47  6754.6  212.15  8045.6  221.32  8049.1  221.36  8497.6  229.72
#Mann= 20 ,-1 , 0
  3641.9     .04       0  3685.2     .05       0  3692.5     .04       0
  3864.7     .05       0    3872     .04       0  4534.7     .12       0
  4763.8     .04       0  4919.5     .03       0  4996.3     .03       0
  5043.9     .03       0  5169.4     .03       0  5234.4     .05       0
  5441.7     .03       0  5519.2     .05       0  5558.7     .12       0
  5815.9    .013       0  6146.5     .12       0  6754.6     .04       0
  8045.6     .05       0  8049.1     .04       0
Bank Sta=4996.3,5043.9
XS Rating Curve= 0 ,0
Exp/Cntr=0.3,0.1

Type RM Length L Ch R = 1 ,79031   ,992,992,992
BEGIN DESCRIPTION:
Mapping XS d215ba53
END DESCRIPTION:
XS GIS Cut Line= 3
       2496203.8     13531091.05       2495582.1     13530145.51
        2492979.     13528193.18
#Sta/Elev= 30
  3598.3  227.71  3722.6  222.05  3948.8  215.05  4203.4  212.21    4336  210.94
  4443.9  209.66  4684.3  208.32  4706.6  208.67  4742.1  204.67  4777.5  207.49
  4814.7  206.31  4963.8  199.89  4982.9  195.07  4983.9  194.57  5030.5  195.07
  5035.8  201.75  5042.7  203.83  5077.5  208.57    5298  208.06  5416.5  207.63
  5574.6  208.31  5860.4  210.46  6155.4  214.76  6543.5  214.74    6706  215.49
  7274.9  219.54  7477.5  223.42  7509.1  221.53  7648.1  222.79  7983.8  227.95
#Mann= 20 ,-1 , 0
  3598.3     .05       0  3722.6     .12       0  4203.4     .05       0
    4336     .12       0  4443.9     .04       0  4684.3     .04       0
  4814.7     .03       0  4982.9     .03       0  5030.5     .03       0
  5042.7     .12       0    5298     .05       0  5416.5    .013       0
  5574.6     .12       0  5860.4     .05       0  6155.4     .12       0
  6543.5     .12       0    6706     .04       0  7274.9     .05       0
  7509.1     .05       0  7648.1     .04       0
Bank Sta=4982.9,5030.5
XS Rating Curve= 0 ,0
Exp/Cntr=0.3,0.1

Type RM Length L Ch R = 1 ,78039   ,1067,1067,1067
BEGIN DESCRIPTION:
Mapping XS efbde3fc
END DESCRIPTION:
XS GIS Cut Line= 4
      2497737.62     13529839.62      2496268.93     13529639.52
      2496042.17     13529503.15      2493239.18     13527923.75
#Sta/Elev= 30
  3174.1   223.8  3399.8   217.9  3526.9  214.55  3653.6  212.36  3688.1  209.24
  4018.2  210.64    4117  209.97  4611.3  208.24  4796.9  207.79  4925.4  204.37
    4963   198.6  4966.1  192.82  4967.1  192.32  5014.7  192.82  5055.5  204.51
  5165.2   206.5  5342.4  206.72  5357.4  200.75  5379.1  206.75  5416.6  207.42
    6205  212.91  6720.5  214.16  6833.2  215.07  6942.7  215.46  7053.8  216.14
  7147.6  216.74  7385.4  219.27  7591.3  220.06  8034.7   224.2  8138.3  225.12
#Mann= 20 ,-1 , 0
  3174.1     .04       0  3399.8     .04       0  3526.9     .05       0
  3653.6     .12       0  4018.2     .05       0    4117     .04       0
  4611.3     .12       0  4796.9     .12       0  4966.1     .05       0
  5014.7      .1       0  5165.2     .12       0    6205     .05       0
  6720.5    .013       0  6833.2    .013       0  6942.7     .12       0
  7053.8     .05       0  7147.6     .12       0  7385.4     .05       0
  7591.3     .12       0  8034.7     .05       0
Bank Sta=4966.1,5014.7
XS Rating Curve= 0 ,0
Exp/Cntr=0.3,0.1

Type RM Length L Ch R = 1 ,76972   ,884,884,884
BEGIN DESCRIPTION:
Mapping XS c43cf093
END DESCRIPTION:
XS GIS Cut Line= 3
      2498125.49     13529728.83      2496319.95     13528487.52
      2493229.81     13527654.22
#Sta/Elev= 30
  2870.9  223.15  3030.8  223.24  3157.8  222.16  3268.6  221.72    3560  218.17
    3693  215.85  3977.1  211.43  4134.8  209.19  4404.4     206  4619.3  205.71
  4865.6  207.22  4901.4  202.05  4946.1  203.77    5009  195.89  5014.1   192.3
  5015.1   191.8  5063.4   192.3  5067.1  201.52  5091.9  206.74  5121.6   206.8
  5540.2  209.48  5663.5  209.53  6042.5  211.69  6239.2  213.07  6900.8  215.93
    7211  221.84  7561.6  221.25    7718  222.58  8233.6  226.75  8262.5  226.72
#Mann= 20 ,-1 , 0
  2870.9     .05       0  3030.8     .04       0  3157.8     .05       0
  3268.6     .12       0    3560     .05       0    3693     .04       0
  3977.1     .04       0  4134.8     .05       0  4404.4     .04       0
  4619.3     .05       0  5014.1     .05       0  5063.4      .1       0
  5121.6     .12       0  5540.2     .12       0  5663.5     .05       0
  6042.5     .05       0  6239.2     .12       0  7561.6     .05       0
    7718     .12       0  8233.6     .05       0
Bank Sta=5014.1,5063.4
XS Rating Curve= 0 ,0
Exp/Cntr=0.3,0.1

Type RM Length L Ch R = 1 ,76088   ,1083,1083,1083
BEGIN DESCRIPTION:
Mapping XS 6dcfa6c9
END DESCRIPTION:
XS GIS Cut Line= 3
      2498151.53      13528756.6      2496771.34     13527767.03
      2494289.36     13527281.05
#Sta/Elev= 30
  3382.1  223.97  3396.5  223.64  3673.7  222.46  4402.4  213.07  4619.7  209.67
  4738.3  205.37  4754.7  204.56    4779  203.28  4792.9  198.84  4820.7  200.85
  4842.1  205.12  4856.9  205.45  4928.2  206.74  4942.3   202.1  4947.2  189.99
  4948.2  189.49  4996.5  189.99  5028.3  190.58    5043  200.63  5049.3  202.67
  5086.8  206.91  5331.4  205.04  5512.9  206.66  5724.4  208.46  6057.7  208.81
  6547.1  210.95  6686.1  211.61  6879.5  213.55  6910.3  213.76  7609.5  221.36
#Mann= 17 ,-1 , 0
  3382.1     .12       0  3396.5     .04       0  4402.4     .05       0
  4619.7     .12       0  4738.3     .05       0  4754.7     .12       0
  4856.9     .05       0  4947.2     .05       0  4996.5     .05       0
  5049.3     .12       0  5512.9     .05       0  5724.4     .04       0
  6057.7     .12       0  6547.1     .05       0  6686.1     .12       0
  6879.5     .05       0  6910.3     .12       0
Bank Sta=4947.2,4996.5
XS Rating Curve= 0 ,0
Exp/Cntr=0.3,0.1

Type RM Length L Ch R = 1 ,75005   ,893,893,893
BEGIN DESCRIPTION:
Mapping XS 80ac248c
END DESCRIPTION:
XS GIS Cut Line= 3
      2498576.87     13528096.87      2497405.02     13526968.42
      2494714.08     13526395.51
#Sta/Elev= 30
  3390.6  220.58  3651.6  219.62  3865.3  218.64    3973  218.41  4119.5  217.46
  4311.4  214.43  4529.7  209.86  4795.5  208.28  4934.9  207.21    4949  205.61
  4956.3  200.98  4963.2  201.22  4977.3  196.78  4980.9  190.65  4981.9  190.15
  5030.4  190.65  5048.1  196.62  5099.3  203.07  5207.2  205.16  5350.2  204.59
  5452.1  204.26  5668.3  204.44  5810.6  207.08  5971.4  209.34  6127.3  208.86
  6356.2  207.62  6649.3  207.43  6749.2  207.67  7328.1  211.63  7768.7  223.19
#Mann= 20 ,-1 , 0
  3390.6     .05       0  3651.6     .05       0  3865.3     .12       0
    3973     .03       0  4119.5     .12       0  4311.4     .05       0
  4529.7     .12       0  4795.5     .12       0  4980.9     .05       0
  5030.4      .1       0  5207.2     .12       0  5350.2      .1       0
  5452.1     .12       0  5668.3     .05       0  5810.6     .12       0
  5971.4     .05       0  6127.3    .013       0  6356.2     .05       0
  6649.3    .013       0  6749.2     .12       0
Bank Sta=4980.9,5030.4
XS Rating Curve= 0 ,0
Exp/Cntr=0.3,0.1

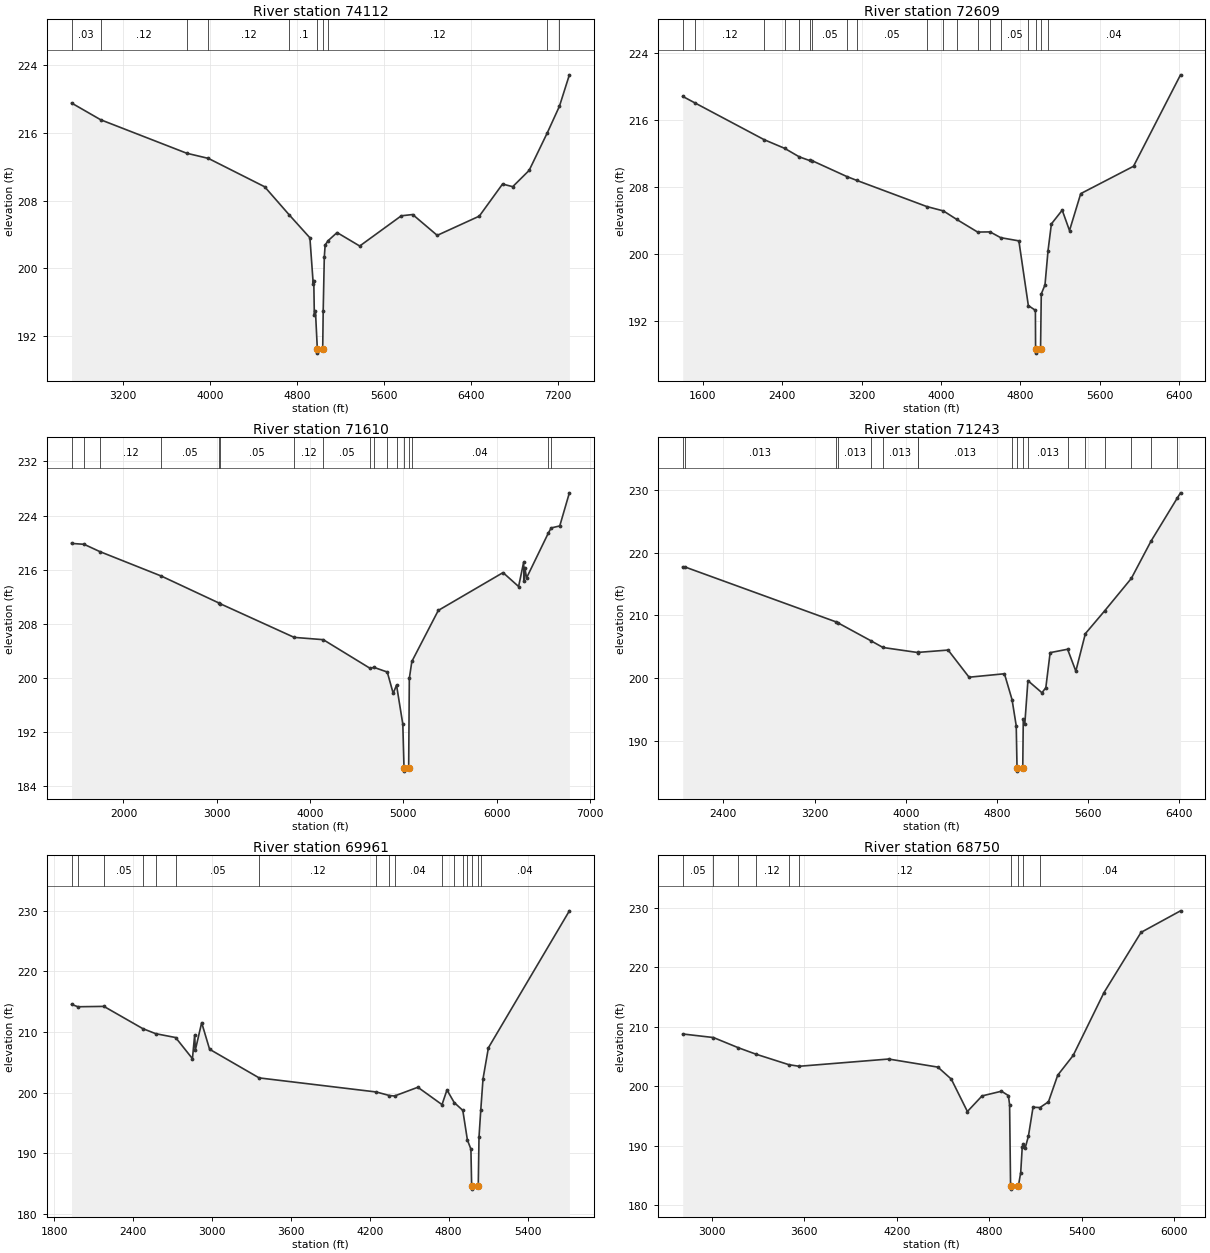
Type RM Length L Ch R = 1 ,74112   ,1503,1503,1503
BEGIN DESCRIPTION:
Mapping XS eabb848e
END DESCRIPTION:
XS GIS Cut Line= 3
      2498750.52     13527758.38      2497717.52     13526195.85
      2495061.23     13525692.37
#Sta/Elev= 30
  2727.3  219.54  2995.4  217.56  3785.9  213.61    3985     213  4502.4  209.65
  4728.4  206.33  4918.5  203.62    4949  198.19  4954.1  198.57  4959.2  194.55
  4969.4     195  4986.7   190.5  4987.7     190  5036.2   190.5  5040.6  194.93
  5050.8  201.31  5058.7  202.78  5087.3   203.3  5168.3  204.24  5376.5  202.65
  5758.8  206.22  5863.4  206.37    6089  203.91  6475.7  206.18  6689.5  209.97
    6783  209.66  6933.8  211.58  7102.1  216.05  7212.8  219.17    7304  222.87
#Mann= 10 ,-1 , 0
  2727.3     .03       0  2995.4     .12       0  3785.9     .05       0
    3985     .12       0  4728.4      .1       0  4986.7     .05       0
  5036.2      .1       0  5087.3     .12       0  7102.1     .04       0
  7212.8     .03       0
Bank Sta=4986.7,5036.2
XS Rating Curve= 0 ,0
Exp/Cntr=0.3,0.1

Type RM Length L Ch R = 1 ,72609   ,999,999,999
BEGIN DESCRIPTION:
Mapping XS edbc94ff
END DESCRIPTION:
XS GIS Cut Line= 3
      2498724.48     13527636.87      2497700.16     13524928.49
      2495678.76      13524286.5
#Sta/Elev= 30
  1396.8  218.83  1520.4  218.05  2217.7  213.67  2423.7  212.64  2572.3  211.62
  2674.7  211.19  2703.9  211.15  3052.3  209.27  3152.6  208.81  3856.6   205.7
  4023.8  205.18  4158.9  204.16  4368.6  202.66  4493.9  202.68  4601.5  201.99
  4784.3  201.61  4879.8   193.9  4950.9  193.33  4952.8  188.73  4953.8  188.23
  5002.9  188.73  5010.1  195.28  5047.6  196.37  5078.4  200.46  5112.1  203.63
  5221.1  205.27  5294.6  202.84  5407.7  207.24  5939.5   210.5  6413.3   221.4
#Mann= 19 ,-1 , 0
  1396.8     .03       0  1520.4     .12       0  2217.7     .05       0
  2423.7     .12       0  2572.3     .05       0  2674.7     .12       0
  2703.9     .05       0  3052.3     .12       0  3152.6     .05       0
  3856.6     .12       0  4023.8     .05       0  4158.9     .12       0
  4368.6     .05       0  4493.9     .12       0  4601.5     .05       0
  4879.8      .1       0  4952.8     .05       0  5002.9      .1       0
  5078.4     .04       0
Bank Sta=4952.8,5002.9
XS Rating Curve= 0 ,0
Exp/Cntr=0.3,0.1

Type RM Length L Ch R = 1 ,71610   ,367,367,367
BEGIN DESCRIPTION:
Mapping XS 0e34a90f
END DESCRIPTION:
XS GIS Cut Line= 3
      2498819.95       13527741.      2497839.05     13524355.58
      2497214.05      13522654.2
#Sta/Elev= 30
  1443.2  219.87  1577.5  219.74  1746.5  218.66  2403.4  215.05  3026.3  211.03
  3034.1  210.96  3829.9  205.96  4141.9  205.62  4643.6  201.38  4685.5  201.52
    4828  200.83  4891.5  197.67  4927.2   198.9  4994.6  193.11  5007.3  186.66
  5008.3  186.16  5057.4  186.66  5064.4  199.88  5091.3  202.39  5374.9  209.95
  6069.1  215.55    6236  213.49  6289.5  217.05    6297  214.34  6302.3   216.3
  6321.5  214.77  6554.6   221.4  6585.1  222.16  6677.2  222.46  6780.4  227.36
#Mann= 17 ,-1 , 0
  1443.2     .03       0  1577.5    .013       0  1746.5     .12       0
  2403.4     .05       0  3026.3    .013       0  3034.1     .05       0
  3829.9     .12       0  4141.9     .05       0  4643.6     .04       0
  4685.5     .05       0    4828     .04       0  4927.2     .05       0
  5007.3     .05       0  5057.4     .05       0  5091.3     .04       0
  6554.6     .05       0  6585.1     .04       0
Bank Sta=5007.3,5057.4
XS Rating Curve= 0 ,0
Exp/Cntr=0.3,0.1

Type RM Length L Ch R = 1 ,71243   ,1282,1282,1282
BEGIN DESCRIPTION:
Mapping XS d82dfaf6
END DESCRIPTION:
XS GIS Cut Line= 3
       2498932.8     13527133.34      2498177.59     13524268.77
      2497874.08     13522898.63
#Sta/Elev= 30
  2044.1  217.72  2061.5  217.71  3389.8  208.93  3407.9  208.76    3698  205.89
  3800.7  204.85  4104.6  204.05  4108.8  204.07  4371.9  204.44  4555.4  200.11
  4865.7  200.66  4932.6  196.52  4969.1  192.36  4976.1  185.63  4977.1  185.13
  5026.3  185.63  5030.9  193.37    5044  192.58  5071.6  199.56  5194.8  197.63
  5228.6  198.44  5266.5  204.03  5419.6  204.57  5491.8  201.08  5575.4  207.06
  5744.3  210.69  5978.5  215.87  6150.7   221.8  6381.7   228.7  6409.9  229.52
#Mann= 18 ,-1 , 0
  2044.1     .05       0  2061.5    .013       0  3389.8     .05       0
  3407.9    .013       0    3698     .05       0  3800.7    .013       0
  4104.6     .05       0  4108.8    .013       0  4932.6     .05       0
  4976.1     .05       0  5026.3     .05       0  5071.6    .013       0
  5419.6     .04       0  5575.4    .013       0  5744.3     .04       0
  5978.5    .013       0  6150.7     .04       0  6381.7    .013       0
Bank Sta=4976.1,5026.3
XS Rating Curve= 0 ,0
Exp/Cntr=0.3,0.1

Type RM Length L Ch R = 1 ,69961   ,1211,1211,1211
BEGIN DESCRIPTION:
Mapping XS a6748efc
END DESCRIPTION:
XS GIS Cut Line= 3
      2499123.77     13526881.58       2499332.1     13523938.91
      2499158.49     13523122.91
#Sta/Elev= 30
  1933.3  214.55  1981.9  214.16  2179.1  214.22  2474.5  210.56  2573.6  209.72
  2724.3  209.09  2852.2  205.61  2869.2  209.53  2874.2  207.03  2922.3  211.54
  2982.5  207.16  3359.4  202.44  4250.3  200.12    4349  199.54  4388.3  199.46
  4565.9   200.9  4749.4  198.04    4787  200.45  4842.1  198.38  4907.4  197.09
  4942.4  192.21  4969.1  190.71  4974.6  184.62  4975.6  184.12  5024.9  184.62
  5030.5  192.65  5043.8  197.09  5061.1  202.29    5102   207.4  5717.6  229.96
#Mann= 17 ,-1 , 0
  1933.3     .05       0  1981.9     .12       0  2179.1     .05       0
  2474.5     .12       0  2573.6     .04       0  2724.3     .05       0
  3359.4     .12       0  4250.3    .013       0    4349     .12       0
  4388.3     .04       0  4749.4     .12       0  4842.1     .04       0
  4907.4     .12       0  4942.4     .05       0  4974.6     .05       0
  5024.9     .05       0  5043.8     .04       0
Bank Sta=4974.6,5024.9
XS Rating Curve= 0 ,0
Exp/Cntr=0.3,0.1

Type RM Length L Ch R = 1 ,68750   ,981,981,981
BEGIN DESCRIPTION:
Mapping XS d8dab51a
END DESCRIPTION:
XS GIS Cut Line= 3
      2499757.44     13526213.24      2500425.85     13524155.92
      2500365.14     13523089.13
#Sta/Elev= 30
  2810.1   208.8  3009.8   208.2  3171.6  206.48  3284.2  205.41  3499.1  203.63
  3565.8  203.36  4147.1  204.58  4466.6  203.22  4553.7   201.2  4658.3  195.74
  4753.4  198.37  4879.6  199.16  4924.5  198.42  4932.2  196.87  4938.5  183.17
  4939.5  182.67    4989  183.17  5004.3  185.44  5014.3  189.76  5019.7  190.19
  5034.3  189.68  5054.3  191.58  5084.4  196.46  5129.4  196.41  5184.5  197.38
  5244.6  201.86  5344.8  205.18  5545.1  215.78  5785.5  225.91  6041.8  229.54
#Mann= 10 ,-1 , 0
  2810.1     .05       0  3009.8     .12       0  3171.6     .05       0
  3284.2     .12       0  3499.1     .05       0  3565.8     .12       0
  4938.5     .05       0    4989     .12       0  5019.7     .05       0
  5129.4     .04       0
Bank Sta=4938.5,4989
XS Rating Curve= 0 ,0
Exp/Cntr=0.3,0.1