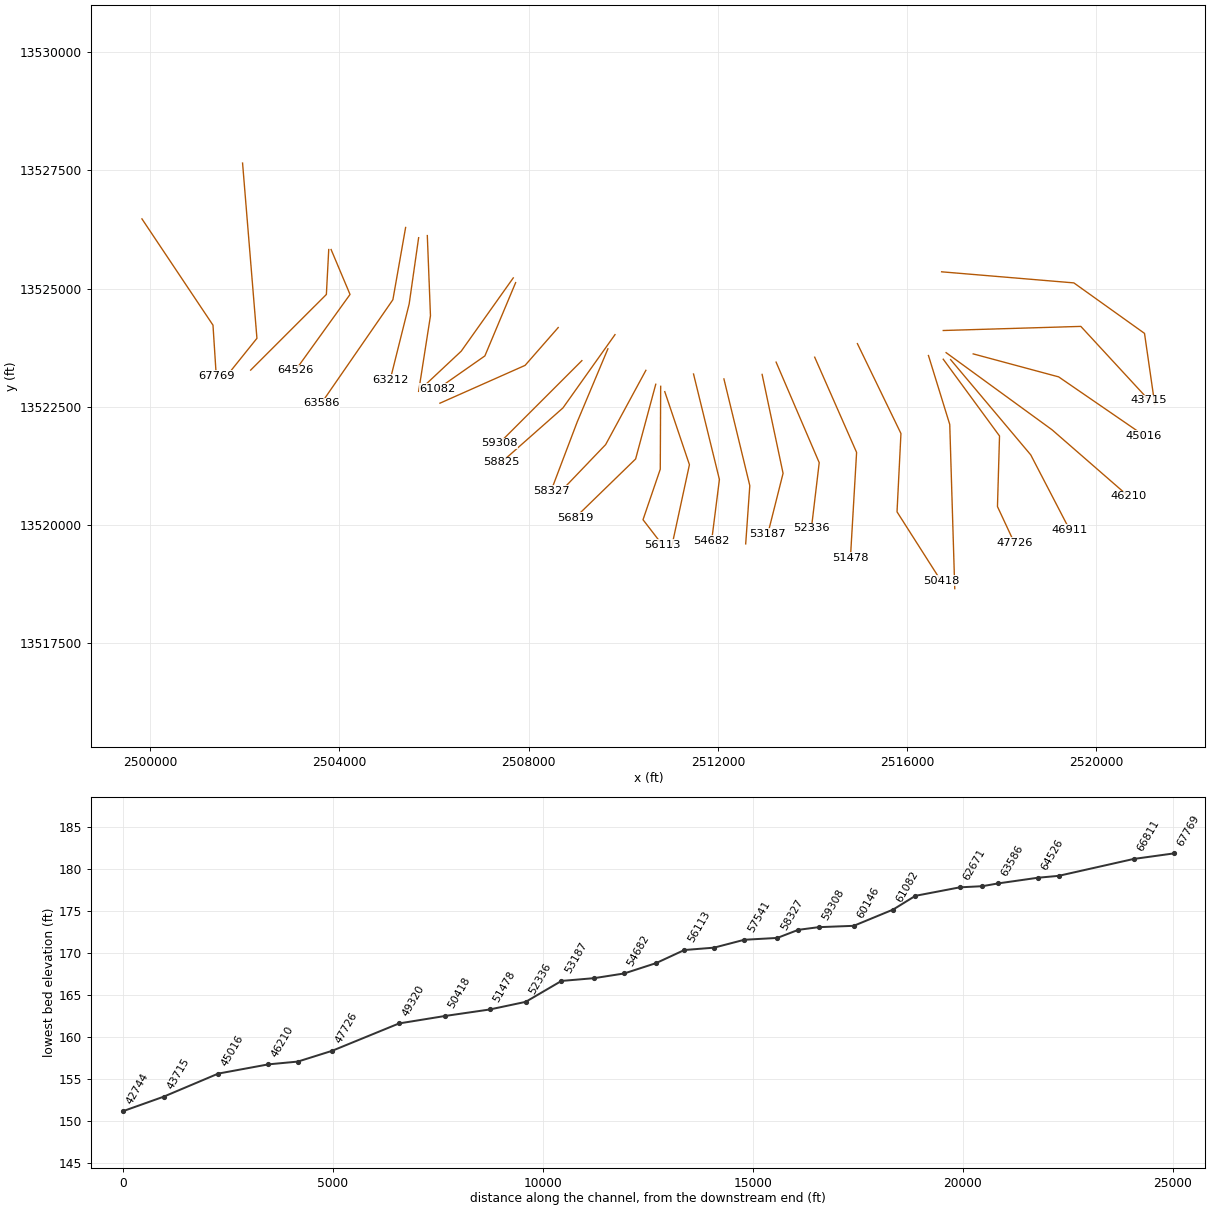
HEC-RAS study TWELVEMILE CREEK.prj: TWELVEMILE CREEK Base Level Engineering

--- TWELVEMILE CREEK.g01 (geometry) --- (continued)

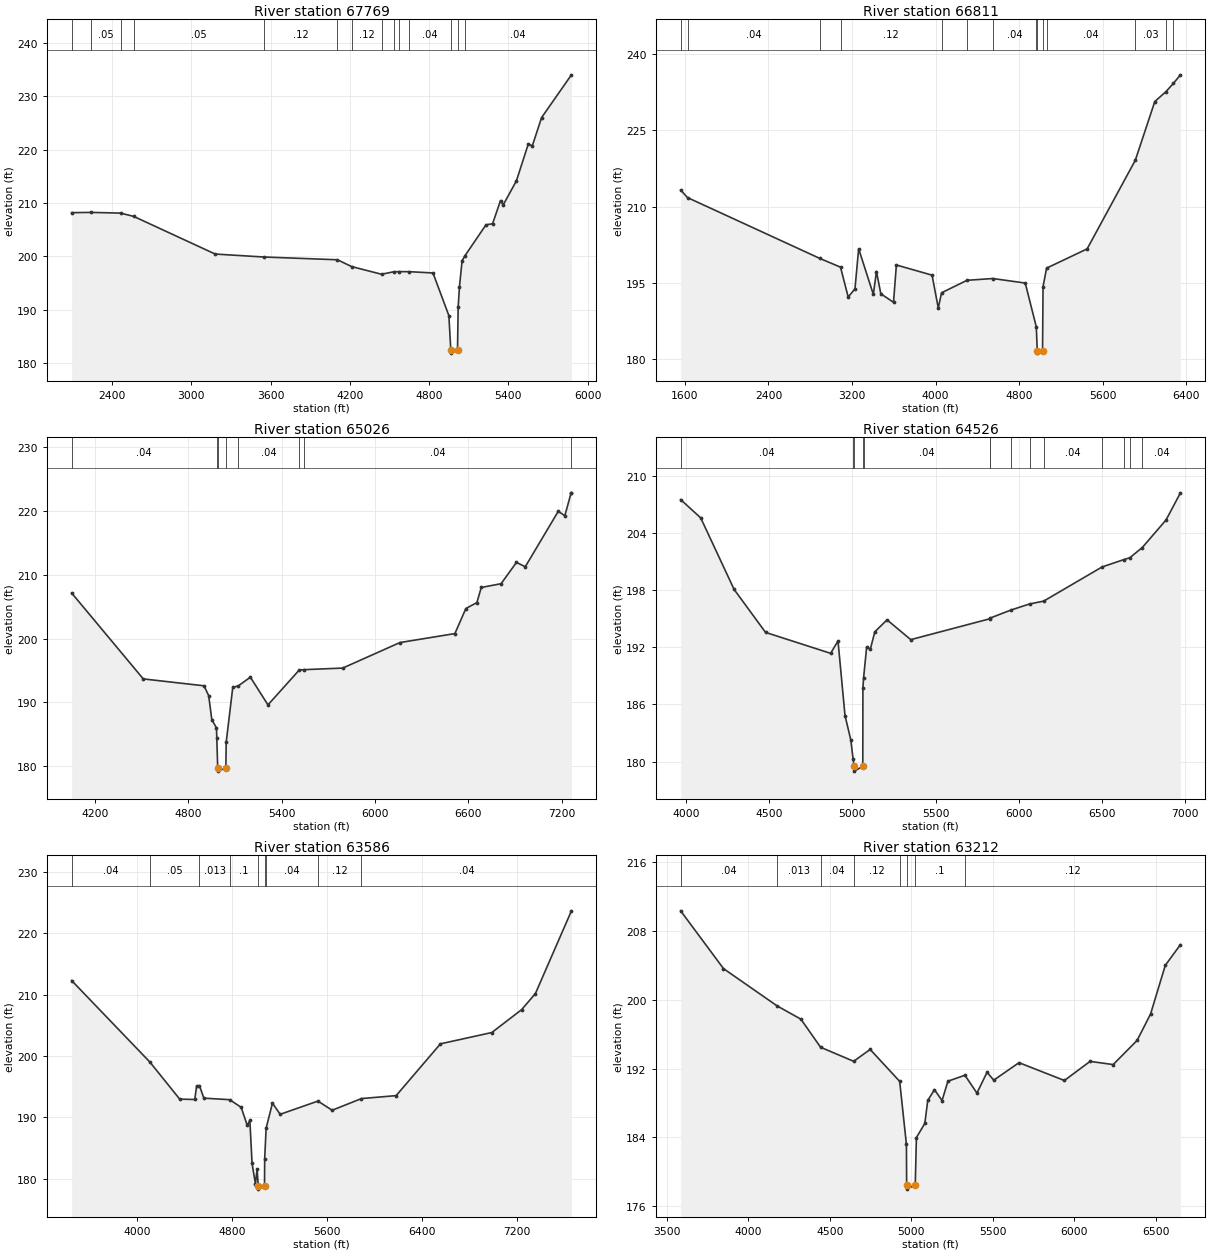
Type RM Length L Ch R = 1 ,67769   ,958,958,958
BEGIN DESCRIPTION:
Mapping XS 15a051f7
END DESCRIPTION:
XS GIS Cut Line= 3
      2499826.92      13526473.6      2501328.63     13524225.37
      2501398.05     13523149.44
#Sta/Elev= 30
  2095.2  208.19  2240.5  208.24  2465.2  208.11  2564.7  207.49  3181.4  200.44
  3548.2  199.89  4106.6  199.37  4214.4  198.09  4439.8  196.66  4531.6  197.12
    4575  197.15  4650.3  197.14  4829.3   196.9  4949.5  188.92  4964.3  182.39
  4965.3  181.89  5014.9  182.39  5019.7  190.46  5029.7  194.33  5049.7  199.22
  5072.5  200.17  5230.1  205.91  5280.2  206.12  5340.3  210.45  5360.4  209.63
  5460.6  214.15  5550.8  221.07  5580.8  220.69    5651  225.99    5877     234
#Mann= 14 ,-1 , 0
  2095.2     .12       0  2240.5     .05       0  2465.2     .12       0
  2564.7     .05       0  3548.2     .12       0  4106.6     .05       0
  4214.4     .12       0  4439.8     .05       0  4531.6     .04       0
    4575     .03       0  4650.3     .04       0  4964.3     .05       0
  5014.9     .04       0  5072.5     .04       0
Bank Sta=4964.3,5014.9
XS Rating Curve= 0 ,0
Exp/Cntr=0.3,0.1

Type RM Length L Ch R = 1 ,66811   ,1785,1785,1785
BEGIN DESCRIPTION:
Mapping XS 4115cdf6
END DESCRIPTION:
XS GIS Cut Line= 3
      2501953.63     13527654.18      2502257.45     13523947.59
      2501589.54     13523114.87
#Sta/Elev= 30
  1558.9  213.26  1624.9  211.77  2892.7  199.82  3090.1  198.11  3163.4  192.26
  3228.4  193.84  3263.8  201.72  3404.2  192.77  3434.3  197.25  3476.2  192.88
  3597.6  191.21    3625  198.54  3966.9  196.54  4026.3  190.08  4057.8  193.08
  4301.7  195.53  4548.8  195.88  4859.1  194.99  4965.1   186.4  4974.3  181.73
  4975.3  181.23  5024.9  181.73  5029.7   194.3  5063.7  197.92    5452   201.7
  5913.4  219.11  6100.1  230.64    6206  232.56  6278.2   234.2  6345.4  235.88
#Mann= 14 ,-1 , 0
  1558.9     .03       0  1624.9     .04       0  2892.7     .05       0
  3090.1     .12       0  4057.8     .05       0  4301.7     .12       0
  4548.8     .04       0  4965.1     .12       0  4974.3     .05       0
  5024.9     .12       0  5063.7     .04       0  5913.4     .03       0
    6206     .04       0  6278.2     .03       0
Bank Sta=4974.3,5024.9
XS Rating Curve= 0 ,0
Exp/Cntr=0.3,0.1

Type RM Length L Ch R = 1 ,65026   ,500,500,500
BEGIN DESCRIPTION:
TWELVEMILE CREEK 94.0
END DESCRIPTION:
XS GIS Cut Line= 3
        2503775.     13525824.98        2503725.       13524875.
      2502125.03     13523275.03
#Sta/Elev= 30
  4048.7  207.15  4509.3  193.68  4899.9   192.6  4929.9  191.05  4949.9  187.31
    4980     186  4981.9  184.49  4987.9  179.72    4989  179.22  5040.3  179.72
  5042.4  183.73  5084.8  192.35  5120.9   192.6    5198  193.95  5311.1  189.61
  5512.1  195.07  5542.8  195.13    5792  195.38  6159.6  199.38  6513.2  200.79
  6583.9  204.72  6654.6  205.65  6682.9  208.02  6810.2  208.61  6909.2  211.95
  6965.8  211.27  7177.9  219.96  7220.3  219.27  7260.6  222.86  7262.7  222.86
#Mann= 8 ,-1 , 0
  4048.7     .04       0  4981.9     .12       0  4987.9     .05       0
  5040.3     .12       0  5120.9     .04       0  5512.1     .12       0
  5542.8     .04       0  7260.6     .03       0
Bank Sta=4987.9,5040.3
XS Rating Curve= 0 ,0
Exp/Cntr=0.3,0.1

Type RM Length L Ch R = 1 ,64526   ,940,940,940
BEGIN DESCRIPTION:
TWELVEMILE CREEK 93.0
END DESCRIPTION:
XS GIS Cut Line= 3
      2503824.99     13525825.02        2504225.       13524875.
        2503075.       13523275.
#Sta/Elev= 30
  3969.2  207.55  4089.6  205.63  4290.3   198.1  4479.2  193.58  4869.8  191.38
  4914.2  192.68  4956.3  184.83  4990.8  182.29  5005.1  180.23  5010.6  179.49
  5011.7  178.99    5063  179.49  5063.8  187.72  5067.5  188.74  5086.2  192.04
    5108   191.8  5135.5  193.65  5208.7   194.9  5351.1  192.82    5825  195.01
  5826.8  195.08  5950.8  195.92  6064.5  196.57  6149.2  196.87  6499.6  200.46
  6629.4  201.23  6666.1  201.43    6741   202.5  6884.2  205.41  6970.4  208.26
#Mann= 14 ,-1 , 0
  3969.2     .04       0  5005.1     .12       0  5010.6     .04       0
    5063     .12       0  5067.5     .04       0    5825     .05       0
  5826.8     .04       0  5950.8     .05       0  6064.5     .12       0
  6149.2     .04       0  6499.6     .05       0  6629.4     .04       0
  6666.1     .05       0    6741     .04       0
Bank Sta=5010.6,5063
XS Rating Curve= 0 ,0
Exp/Cntr=0.3,0.1

Type RM Length L Ch R = 1 ,63586   ,374,374,374
BEGIN DESCRIPTION:
Mapping XS 298483fb
END DESCRIPTION:
XS GIS Cut Line= 3
      2505399.82     13526291.38      2505130.72     13524763.56
      2503620.31     13522576.08
#Sta/Elev= 30
  3451.9  212.27  4111.4  198.99  4362.1  192.97  4488.8  192.91  4504.2  195.08
  4528.6  195.15  4565.2  193.13    4783  192.88  4879.9  191.63  4930.7   188.7
  4952.9   189.5  4971.3  182.53    5000  179.16  5013.6  181.62  5023.7  178.82
  5024.8  178.32  5076.4  178.82  5077.7  183.27    5090  188.25  5143.3  192.32
  5208.1   190.5  5526.4  192.65  5645.6  191.16  5892.9  193.06    6185  193.54
  6558.2  201.97  6990.8  203.81  7241.6  207.53  7357.9  210.15  7661.5  223.62
#Mann= 9 ,-1 , 0
  3451.9     .04       0  4111.4     .05       0  4528.6    .013       0
    4783      .1       0  5023.7     .05       0  5076.4      .1       0
    5090     .04       0  5526.4     .12       0  5892.9     .04       0
Bank Sta=5023.7,5076.4
XS Rating Curve= 0 ,0
Exp/Cntr=0.3,0.1

Type RM Length L Ch R = 1 ,63212   ,541,541,541
BEGIN DESCRIPTION:
TWELVEMILE CREEK 90.0
END DESCRIPTION:
XS GIS Cut Line= 3
        2505675.     13526074.97        2505475.       13524675.
      2505075.01     13523075.03
#Sta/Elev= 30
  3586.2  210.32  3848.8  203.61  4177.2  199.28  4323.6  197.73  4444.1  194.47
  4646.8  192.84  4747.8  194.22  4928.8  190.51  4970.1  183.19  4971.5  178.49
  4972.5  177.99  5024.3  178.49  5031.3  183.98  5082.8  185.62  5100.9  188.29
  5142.1  189.54  5188.5  188.28  5224.6  190.53  5328.6  191.22  5402.4  189.15
  5464.2  191.56  5505.5  190.65  5660.1  192.68  5938.4  190.61  6095.6  192.83
  6237.3  192.46  6384.2  195.27  6466.7  198.34  6556.9  203.99  6649.6  206.39
#Mann= 8 ,-1 , 0
  3586.2     .04       0  4177.2    .013       0  4444.1     .04       0
  4646.8     .12       0  4928.8      .1       0  4971.5     .05       0
  5024.3      .1       0  5328.6     .12       0
Bank Sta=4971.5,5024.3
XS Rating Curve= 0 ,0
Exp/Cntr=0.3,0.1

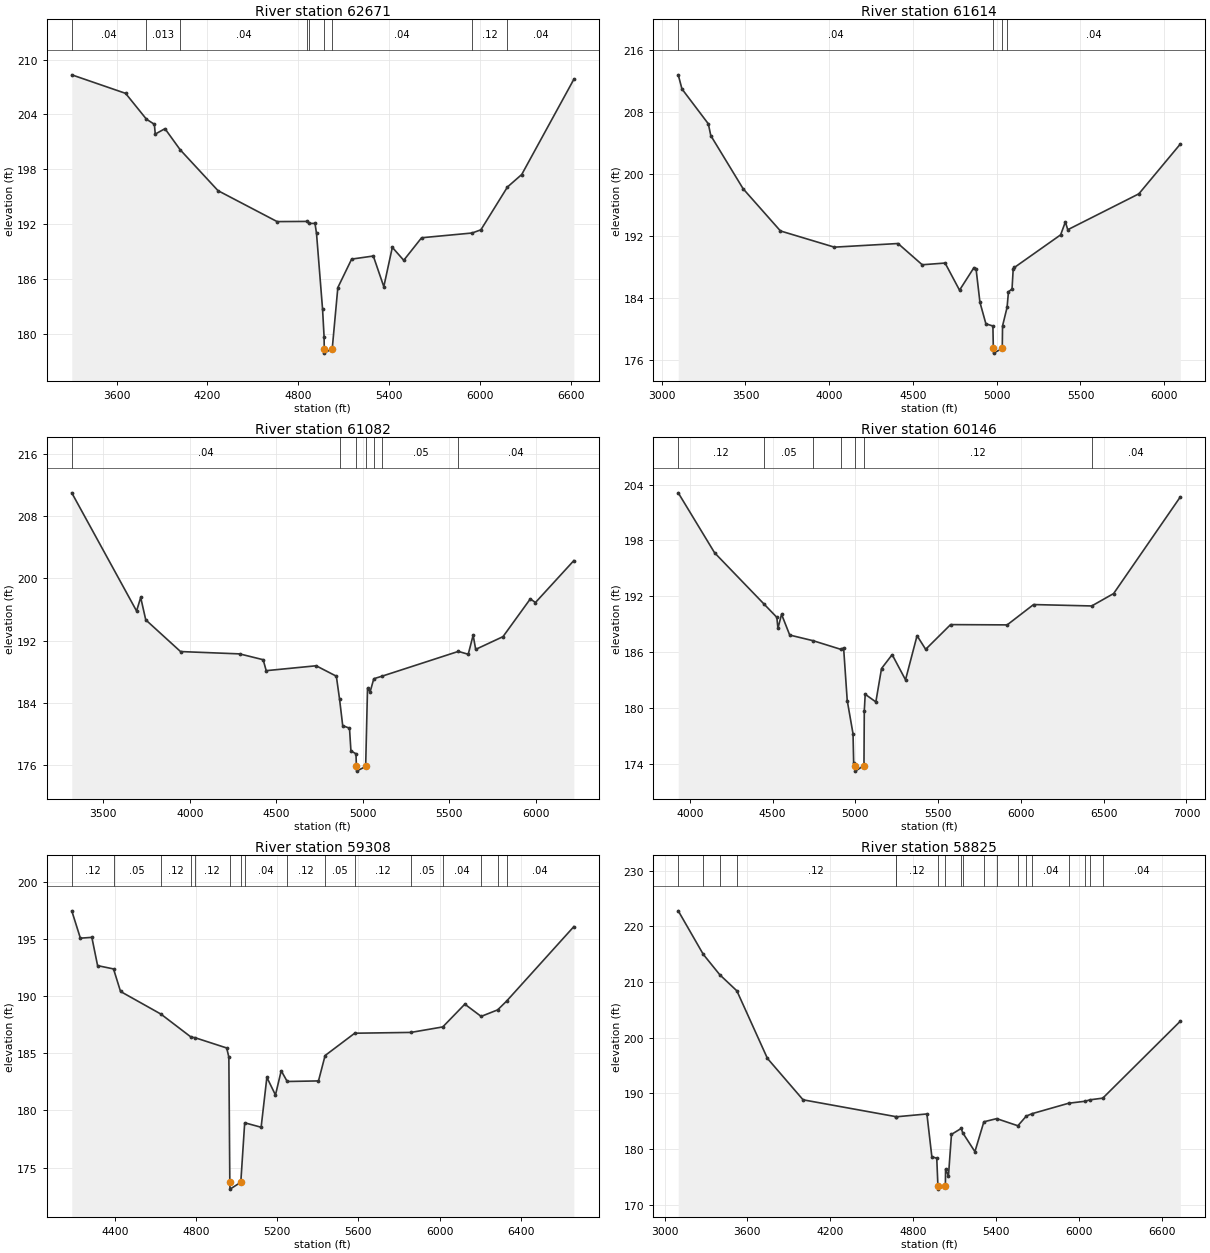
Type RM Length L Ch R = 1 ,62671   ,1057,1057,1057
BEGIN DESCRIPTION:
TWELVEMILE CREEK 89.0
END DESCRIPTION:
XS GIS Cut Line= 3
      2505858.28     13526120.14        2505925.       13524425.
      2505674.99     13522824.96
#Sta/Elev= 30
  3303.6  208.34    3659  206.31  3796.7  203.48  3849.2  202.92    3855  201.85
  3919.2  202.44  4019.6  200.13  4269.5  195.65  4659.8  192.26  4859.3  192.28
    4871  192.06    4910  192.06    4920  190.96    4960  182.65    4970  179.63
  4971.1  178.35  4972.2  177.85  5023.9  178.35  5060.8  185.03  5151.9  188.15
  5295.1  188.49  5364.4  185.13  5420.6  189.44    5496  188.02  5613.9  190.49
  5947.4  191.01  6005.6  191.36    6181  196.05  6275.3  197.42  6619.5  207.85
#Mann= 9 ,-1 , 0
  3303.6     .04       0  3796.7    .013       0  4019.6     .04       0
  4859.3      .1       0    4871     .04       0  4971.1     .04       0
  5023.9     .04       0  5947.4     .12       0    6181     .04       0
Bank Sta=4971.1,5023.9
XS Rating Curve= 0 ,0
Exp/Cntr=0.3,0.1

Type RM Length L Ch R = 1 ,61614   ,532,532,532
BEGIN DESCRIPTION:
TWELVEMILE CREEK 88.0
END DESCRIPTION:
XS GIS Cut Line= 3
      2507675.01     13525225.02        2506575.       13523675.
      2505774.98     13522924.98
#Sta/Elev= 30
  3098.8  212.74    3121  210.92  3278.4  206.42  3293.2   204.9  3486.3  198.04
    3709   192.6  4030.8  190.51  4410.9  190.98  4555.4  188.24  4691.9  188.46
  4778.1  184.96  4864.2  187.87  4876.9  187.68  4899.9   183.4  4935.5  180.62
  4977.3  180.34  4979.9  177.44    4981  176.84  5033.2  177.44  5034.9  180.35
    5062  182.75  5070.1  184.75  5091.5  185.11  5098.4  187.67  5105.7  187.89
  5381.7   192.1    5410  193.77  5424.2  192.76  5848.7  197.39  6096.1  203.81
#Mann= 4 ,-1 , 0
  3098.8     .04       0  4979.9     .04       0  5033.2     .04       0
    5062     .04       0
Bank Sta=4979.9,5033.2
XS Rating Curve= 0 ,0
Exp/Cntr=0.3,0.1

Type RM Length L Ch R = 1 ,61082   ,936,936,936
BEGIN DESCRIPTION:
TWELVEMILE CREEK 87.0
END DESCRIPTION:
XS GIS Cut Line= 3
        2507725.     13525124.99        2507075.       13523575.
      2506075.01     13522875.01
#Sta/Elev= 30
  3317.9  211.02  3692.4  195.81  3716.2  197.55  3745.4  194.67  3946.4  190.59
    4288  190.29  4423.9  189.54  4441.5  188.13  4730.1  188.76  4846.8  187.42
  4865.5  184.45  4883.6  181.05  4922.8  180.73  4931.1  177.81  4960.3  177.43
  4962.8   175.8  4963.9   175.2  5016.2   175.8    5027  185.87  5041.8  185.38
  5063.2  187.09  5112.2  187.43    5552  190.61    5609  190.24  5637.3  192.69
  5652.1  190.87    5810  192.51  5967.8  197.37  5997.4   196.9  6219.3   202.3
#Mann= 7 ,-1 , 0
  3317.9     .04       0  4865.5      .1       0  4962.8     .05       0
  5016.2      .1       0  5063.2     .12       0  5112.2     .05       0
    5552     .04       0
Bank Sta=4962.8,5016.2
XS Rating Curve= 0 ,0
Exp/Cntr=0.3,0.1

Type RM Length L Ch R = 1 ,60146   ,838,838,838
BEGIN DESCRIPTION:
TWELVEMILE CREEK 85.0
END DESCRIPTION:
XS GIS Cut Line= 3
      2508625.01     13524175.01        2507925.       13523375.
        2506125.       13522575.
#Sta/Elev= 30
  3930.3  203.11    4150  196.68  4447.1  191.21  4525.9  189.76  4532.5  188.57
  4554.4  190.09  4603.7  187.86  4745.8  187.25    4912  186.33  4929.3  186.48
  4951.1  180.84  4986.2  177.27    4990   174.1  4998.7  173.87  4999.8  173.27
  5052.2  173.87  5054.2  179.73  5059.7  181.51    5124  180.69  5158.2  184.27
  5222.5  185.76  5303.2  183.06  5372.9  187.79  5424.9  186.33  5575.4  188.98
  5917.3  188.95  6076.7  191.13    6428  190.98  6560.3  192.31  6963.1  202.67
#Mann= 7 ,-1 , 0
  3930.3     .12       0  4447.1     .05       0  4745.8      .1       0
    4912     .12       0  4998.7     .05       0  5052.2     .12       0
    6428     .04       0
Bank Sta=4998.7,5052.2
XS Rating Curve= 0 ,0
Exp/Cntr=0.3,0.1

Type RM Length L Ch R = 1 ,59308   ,483,483,483
BEGIN DESCRIPTION:
TWELVEMILE CREEK 84.0
END DESCRIPTION:
XS GIS Cut Line= 3
        2509125.       13523475.        2508575.       13522925.
      2507374.98     13521724.98
#Sta/Elev= 30
  4187.3  197.44  4229.7  195.05  4286.3  195.12  4314.6  192.65  4393.1  192.36
  4427.7  190.39  4626.9  188.41  4776.9  186.38  4792.9  186.36    4951  185.45
  4961.6  184.65  4966.4  173.71  4967.5  173.11  5020.5  173.71  5039.7  178.91
  5120.7  178.52    5149  182.88  5191.4  181.34  5219.7  183.46  5249.3  182.52
  5403.5  182.57  5436.1  184.79    5582  186.74    5859  186.81    6016  187.29
  6124.8  189.28  6205.2  188.21  6286.5  188.78  6330.3  189.54  6662.2  196.06
#Mann= 16 ,-1 , 0
  4187.3     .12       0  4393.1     .05       0  4626.9     .12       0
  4776.9     .05       0  4792.9     .12       0  4966.4     .05       0
  5020.5     .12       0  5039.7     .04       0  5249.3     .12       0
  5436.1     .05       0    5582     .12       0    5859     .05       0
    6016     .04       0  6205.2     .05       0  6286.5     .12       0
  6330.3     .04       0
Bank Sta=4966.4,5020.5
XS Rating Curve= 0 ,0
Exp/Cntr=0.3,0.1

Type RM Length L Ch R = 1 ,58825   ,498,498,498
BEGIN DESCRIPTION:
TWELVEMILE CREEK 83.0
END DESCRIPTION:
XS GIS Cut Line= 3
      2509825.01     13524025.01        2508725.       13522475.
      2507425.02     13521325.02
#Sta/Elev= 30
  3099.4  222.77  3280.7  214.96  3400.7  211.28  3524.1   208.4  3745.3  196.27
  4003.6  188.83  4674.9  185.81  4678.8  185.78  4900.4  186.29  4936.1  178.63
  4971.8  178.32  4980.1  173.39  4981.2  172.79  5034.2  173.39  5035.6  176.39
  5056.5  175.15  5078.3  182.62  5149.5   183.7  5159.2  182.93  5248.1  179.52
  5312.9  184.88  5405.7  185.45  5559.2  184.17  5620.3  185.91  5661.9  186.34
  5927.7  188.22  6046.1  188.57  6081.4  188.83  6174.2  189.13  6735.7  202.95
#Mann= 19 ,-1 , 0
  3099.4     .04       0  3280.7    .013       0  3400.7     .05       0
  3524.1     .12       0  4674.9     .04       0  4678.8     .12       0
  4980.1     .05       0  5034.2     .12       0  5149.5     .12       0
  5159.2      .1       0  5312.9     .12       0  5405.7     .05       0
  5559.2     .12       0  5620.3     .05       0  5661.9     .04       0
  5927.7     .05       0  6046.1     .12       0  6081.4     .05       0
  6174.2     .04       0
Bank Sta=4980.1,5034.2
XS Rating Curve= 0 ,0
Exp/Cntr=0.3,0.1

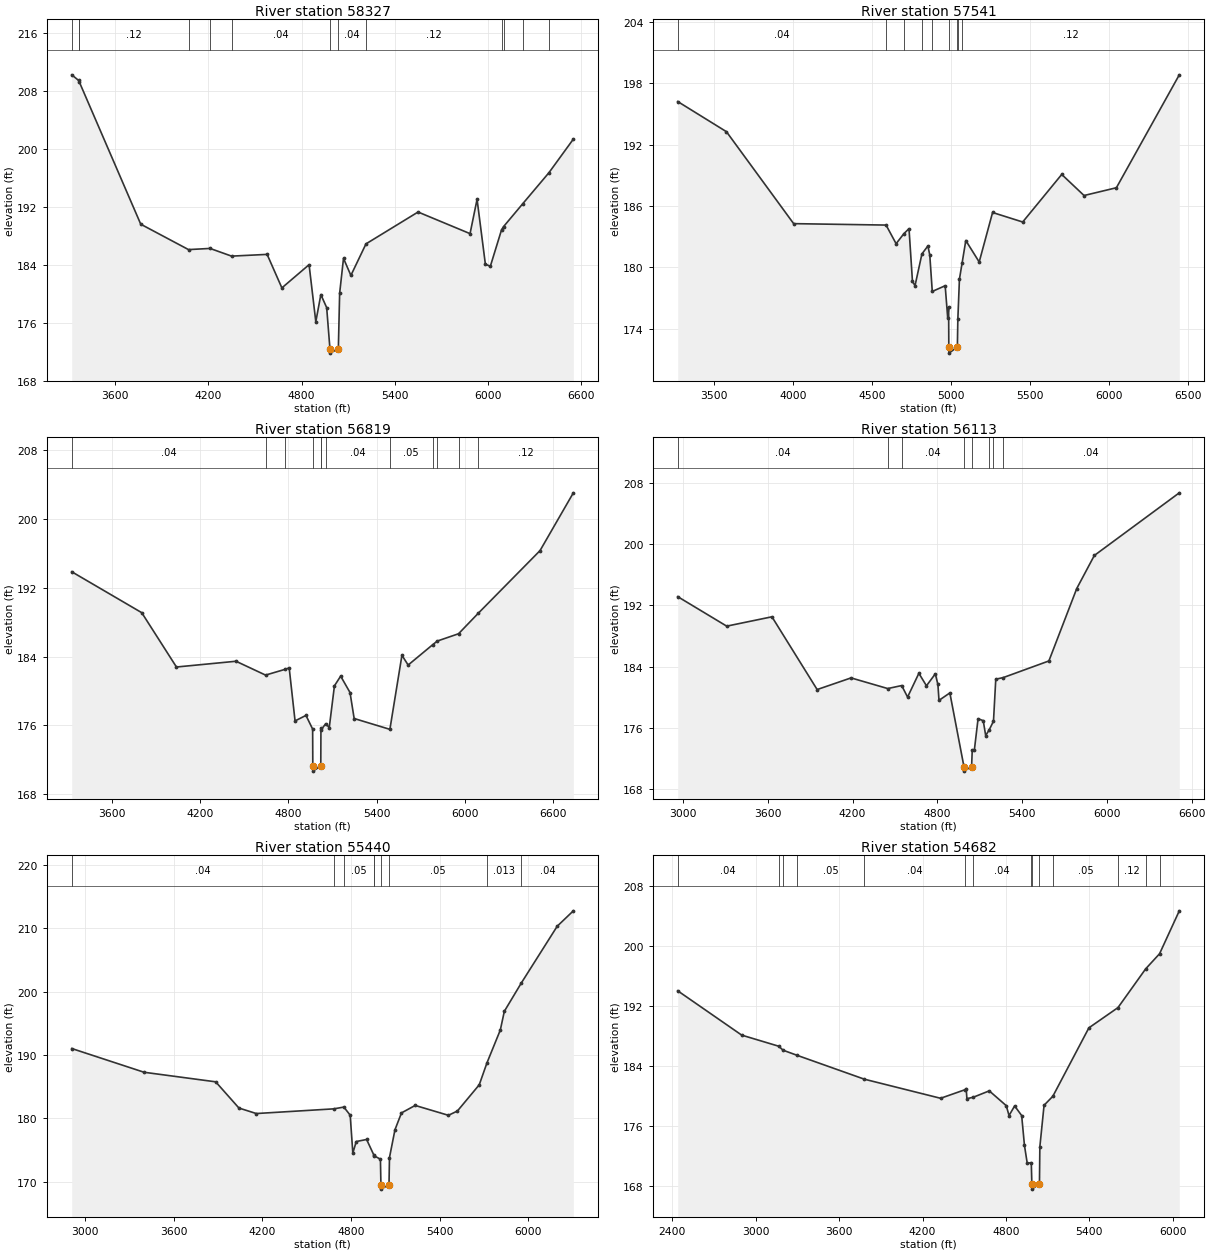
Type RM Length L Ch R = 1 ,58327   ,786,786,786
BEGIN DESCRIPTION:
TWELVEMILE CREEK 82.0
END DESCRIPTION:
XS GIS Cut Line= 3
      2509675.01     13523725.03        2509025.       13522175.
        2508475.     13520725.01
#Sta/Elev= 30
  3319.2  210.19  3363.9  209.41  3367.1  209.25  3763.8   189.6  4071.4   186.1
  4210.2  186.26  4349.1   185.2  4577.9  185.44    4673  180.82  4848.2  184.02
  4891.6  176.16  4924.1   179.9  4961.6   178.1  4982.6  172.43  4983.8  171.83
  5036.8  172.43  5045.2  180.09    5070  184.89  5117.6  182.54  5214.9  186.89
  5550.3  191.28  5885.3   188.3  5930.5  193.03    5984  184.09    6016   183.8
  6088.3  188.83  6101.2  189.27  6225.1  192.43  6393.9  196.71  6550.8  201.33
#Mann= 13 ,-1 , 0
  3319.2    .013       0  3363.9     .05       0  3367.1     .12       0
  4071.4     .05       0  4210.2     .12       0  4349.1     .04       0
  4982.6     .05       0  5036.8     .04       0  5214.9     .12       0
  6088.3     .05       0  6101.2     .12       0  6225.1     .05       0
  6393.9     .12       0
Bank Sta=4982.6,5036.8
XS Rating Curve= 0 ,0
Exp/Cntr=0.3,0.1

Type RM Length L Ch R = 1 ,57541   ,722,722,722
BEGIN DESCRIPTION:
Mapping XS e59fe1fa
END DESCRIPTION:
XS GIS Cut Line= 3
      2510477.92     13523270.47      2509627.24     13521699.33
      2508663.73     13520692.41
#Sta/Elev= 30
  3267.3  196.21  3576.4  193.26  4002.5  184.27  4588.5  184.13  4652.1  182.31
    4702   183.3  4733.9  183.78  4755.8  178.63    4772   178.2  4815.8  181.31
  4853.8  182.09  4865.6   181.2  4881.4  177.64  4963.2   178.2  4979.3  175.05
  4985.1  176.11  4986.3  172.21  4987.4  171.61  5040.5  172.21  5043.5   174.9
  5053.6  178.84  5070.6  180.42    5094  182.62  5178.9  180.52  5263.8  185.36
  5454.7  184.43  5702.2  189.08  5843.7  187.02  6048.8  187.78  6447.6  198.82
#Mann= 9 ,-1 , 0
  3267.3     .04       0  4588.5    .013       0    4702     .12       0
  4815.8     .05       0  4881.4      .1       0  4986.3     .05       0
  5040.5      .1       0  5043.5     .04       0  5070.6     .12       0
Bank Sta=4986.3,5040.5
XS Rating Curve= 0 ,0
Exp/Cntr=0.3,0.1

Type RM Length L Ch R = 1 ,56819   ,706,706,706
BEGIN DESCRIPTION:
Mapping XS e8d60810
END DESCRIPTION:
XS GIS Cut Line= 3
      2510686.26     13522975.32      2510260.92     13521395.51
      2508984.87     13520154.17
#Sta/Elev= 30
  3323.9  193.86  3800.6   189.1    4037  182.78  4442.7  183.45  4643.9  181.84
  4779.1  182.52  4804.8  182.68  4844.8  176.51  4919.1  177.15  4964.6  175.56
  4965.7  171.27  4966.9  170.67    5020  171.27  5021.1  175.63  5023.9  175.51
  5053.8  176.19  5077.7  175.73    5113  180.59  5155.4  181.72  5219.2  179.81
  5247.3  176.79  5490.7  175.53  5572.7  184.14  5615.1  183.01  5781.9  185.37
  5813.6   185.8  5958.4  186.65  6091.9  189.02  6513.3  196.32  6740.2  203.04
#Mann= 12 ,-1 , 0
  3323.9     .04       0  4643.9    .013       0  4779.1     .04       0
  4965.7     .04       0    5020     .04       0  5023.9    .013       0
  5053.8     .04       0  5490.7     .05       0  5781.9     .12       0
  5813.6     .04       0  5958.4     .05       0  6091.9     .12       0
Bank Sta=4965.7,5020
XS Rating Curve= 0 ,0
Exp/Cntr=0.3,0.1

Type RM Length L Ch R = 1 ,56113   ,673,673,673
BEGIN DESCRIPTION:
Mapping XS a7b3d88c
END DESCRIPTION:
XS GIS Cut Line= 4
      2510790.44     13522931.99      2510781.76     13521178.49
      2510417.17     13520110.78      2510825.15     13519581.29
#Sta/Elev= 30
  2962.5  193.15  3309.5   189.3  3629.5  190.52  3949.5  181.03  4189.5  182.55
  4449.2  181.16  4547.8  181.55  4589.5  180.05  4669.5  183.15  4723.2  181.52
  4785.9  183.08  4804.2  181.69  4811.9  179.62  4888.8  180.59  4988.4  170.99
  4989.6  170.39  5042.7  170.99  5047.3  173.15  5062.5  173.18  5088.5  177.23
  5125.1  176.97  5142.4  175.03  5167.7  175.79  5197.6   176.9  5213.8  182.38
  5266.5  182.59  5589.7  184.76    5787  194.21  5911.4  198.52  6512.7  206.69
#Mann= 8 ,-1 , 0
  2962.5     .04       0  4449.2    .013       0  4547.8     .04       0
  4988.4     .05       0  5042.7     .04       0  5167.7    .013       0
  5197.6     .12       0  5266.5     .04       0
Bank Sta=4988.4,5042.7
XS Rating Curve= 0 ,0
Exp/Cntr=0.3,0.1

Type RM Length L Ch R = 1 ,55440   ,758,758,758
BEGIN DESCRIPTION:
Mapping XS 33c06402
END DESCRIPTION:
XS GIS Cut Line= 3
      2510877.26     13522819.07      2511398.08     13521273.98
      2511025.19     13519548.32
#Sta/Elev= 30
  2910.2  191.04  3399.9  187.29  3884.7  185.78  4042.1  181.64  4159.7  180.77
  4684.3  181.51  4752.4  181.79  4795.4  180.51  4813.2  174.52  4836.4  176.35
  4906.6  176.67  4955.4  174.22  4956.3  174.12    5000  173.55  5003.4  169.53
  5004.6  168.83  5058.1  169.53  5061.4  173.82  5098.5  178.21  5142.6  180.87
  5235.4  182.05  5460.4  180.49  5521.3  181.17  5669.1  185.31  5721.6  188.79
  5811.7  193.96    5839  196.92  5954.7  201.42  6197.1  210.36  6306.2  212.79
#Mann= 9 ,-1 , 0
  2910.2     .04       0  4684.3    .013       0  4752.4     .05       0
  4955.4     .04       0  4956.3     .05       0  5003.4     .05       0
  5058.1     .05       0  5721.6    .013       0  5954.7     .04       0
Bank Sta=5003.4,5058.1
XS Rating Curve= 0 ,0
Exp/Cntr=0.3,0.1

Type RM Length L Ch R = 1 ,54682   ,716,716,716
BEGIN DESCRIPTION:
Mapping XS ebbf0bcd
END DESCRIPTION:
XS GIS Cut Line= 3
      2511484.89     13523192.34      2512031.76     13520961.48
      2511866.86     13519659.69
#Sta/Elev= 30
    2438  194.04  2898.6  188.13    3165  186.65  3196.1  186.12  3296.9  185.44
    3782  182.25  4329.7  179.71  4506.5  180.86  4513.7  181.01  4518.9  179.66
  4564.9  179.85  4679.8   180.7  4801.9  178.73  4822.1  177.41  4862.4  178.69
  4912.9  177.41    4933  173.43  4953.1  171.04  4982.2  171.13  4986.2   168.3
  4987.4   167.6    5041   168.3  5043.8  173.25  5074.1  178.78  5137.3  179.98
  5396.6   189.1    5606   191.8  5805.4  196.97  5905.2  198.98  6047.1   204.7
#Mann= 14 ,-1 , 0
    2438     .04       0    3165    .013       0  3196.1     .04       0
  3296.9     .05       0    3782     .04       0  4506.5    .013       0
  4564.9     .04       0  4982.2     .12       0  4986.2     .05       0
    5041     .12       0  5137.3     .05       0    5606     .12       0
  5805.4    .013       0  5905.2     .04       0
Bank Sta=4986.2,5041
XS Rating Curve= 0 ,0
Exp/Cntr=0.3,0.1

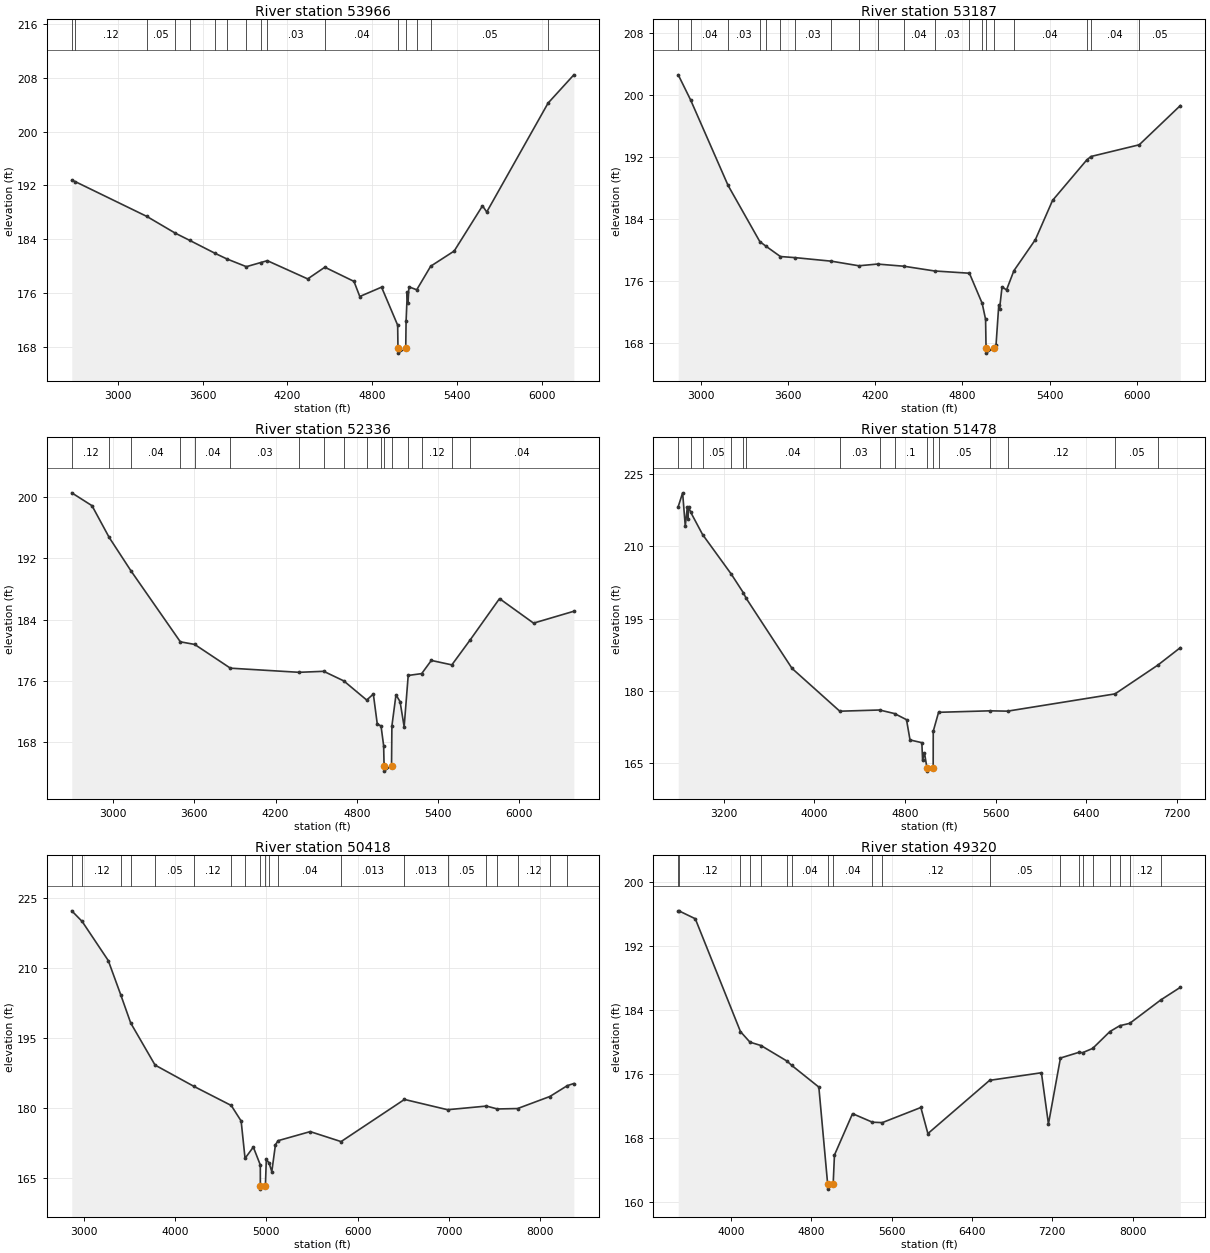
Type RM Length L Ch R = 1 ,53966   ,779,779,779
BEGIN DESCRIPTION:
Mapping XS 47e390ed
END DESCRIPTION:
XS GIS Cut Line= 3
      2512127.25      13523088.2      2512674.12     13520831.27
      2512587.36     13519599.36
#Sta/Elev= 30
  2671.8  192.79  2697.6  192.56  3203.7  187.39  3405.2   184.9    3506  183.84
  3688.8  181.88  3771.1  181.06  3908.9  179.91  4009.7  180.52  4057.5   180.8
  4343.4  178.09  4464.8  179.83  4671.2  177.72  4712.4  175.47  4866.7  176.86
  4980.8   171.2  4982.9  167.74    4984  167.04  5037.9  167.74  5040.4  171.77
  5049.1  176.11  5054.1  174.48  5060.5  176.91  5115.8  176.47  5214.8  179.98
  5381.3  182.24  5581.8  188.97  5611.8  188.05  6046.3  204.26    6229  208.47
#Mann= 16 ,-1 , 0
  2671.8     .04       0  2697.6     .12       0  3203.7     .05       0
  3405.2     .12       0    3506     .04       0  3688.8     .03       0
  3771.1     .04       0  3908.9     .05       0  4009.7    .013       0
  4057.5     .03       0  4464.8     .04       0  4982.9     .04       0
  5037.9     .04       0  5115.8     .12       0  5214.8     .05       0
  6046.3     .04       0
Bank Sta=4982.9,5037.9
XS Rating Curve= 0 ,0
Exp/Cntr=0.3,0.1

Type RM Length L Ch R = 1 ,53187   ,851,851,851
BEGIN DESCRIPTION:
Mapping XS 7a5637fa
END DESCRIPTION:
XS GIS Cut Line= 3
      2512934.54     13523183.67      2513377.24     13521091.69
      2513056.05      13519815.6
#Sta/Elev= 30
  2844.5  202.55  2929.5  199.32  3187.6   188.3  3405.6  181.08  3447.2  180.49
  3547.4  179.15  3647.5  179.01  3898.5  178.55  4086.9  177.96  4215.6  178.18
  4397.4   177.9  4608.1  177.29  4847.7     177  4935.6  173.12    4959  171.06
  4962.2  167.41  4963.4  166.71  5017.3  167.41    5031  167.79  5049.9  172.94
  5055.1   172.4  5072.2  175.24  5103.1  174.85  5153.7  177.32  5301.7  181.33
  5419.9  186.38  5653.8  191.56  5683.5  192.03  6016.1  193.54  6298.7  198.59
#Mann= 20 ,-1 , 0
  2844.5     .05       0  2929.5     .04       0  3187.6     .03       0
  3405.6     .04       0  3447.2    .013       0  3547.4     .04       0
  3647.5     .03       0  3898.5     .03       0  4086.9     .05       0
  4215.6     .03       0  4397.4     .04       0  4608.1     .03       0
  4847.7     .04       0  4935.6     .05       0  4962.2     .03       0
  5017.3     .03       0  5153.7     .04       0  5653.8     .05       0
  5683.5     .04       0  6016.1     .05       0
Bank Sta=4962.2,5017.3
XS Rating Curve= 0 ,0
Exp/Cntr=0.3,0.1

Type RM Length L Ch R = 1 ,52336   ,858,858,858
BEGIN DESCRIPTION:
Mapping XS 109c4185
END DESCRIPTION:
XS GIS Cut Line= 3
      2513229.66     13523444.15      2514141.13     13521317.38
       2513976.3     13519929.29
#Sta/Elev= 30
  2693.4  200.55    2843  198.87  2969.9  194.73  3130.4  190.38  3496.1   181.1
  3602.1  180.76    3866  177.66  4373.3  177.12  4555.8  177.25  4704.3     176
  4873.7   173.5  4922.8  174.28  4951.8  170.38  4979.7  170.11    4999  167.54
  5002.2  164.92  5003.4  164.22  5057.3  164.92    5060  170.11  5090.2  174.18
  5120.4  173.29  5150.6  170.01  5180.6  176.71  5280.2  176.95  5351.5  178.67
  5503.2  178.09  5640.7   181.4  5855.6  186.74  6107.3  183.54  6405.1  185.09
#Mann= 17 ,-1 , 0
  2693.4     .12       0  2969.9     .05       0  3130.4     .04       0
  3496.1    .013       0  3602.1     .04       0    3866     .03       0
  4373.3     .05       0  4555.8     .12       0  4704.3     .05       0
  4873.7     .12       0  4979.7      .1       0  5002.2     .05       0
  5057.3      .1       0  5180.6     .03       0  5280.2     .12       0
  5503.2     .03       0  5640.7     .04       0
Bank Sta=5002.2,5057.3
XS Rating Curve= 0 ,0
Exp/Cntr=0.3,0.1

Type RM Length L Ch R = 1 ,51478   ,1060,1060,1060
BEGIN DESCRIPTION:
Mapping XS c2e52902
END DESCRIPTION:
XS GIS Cut Line= 3
      2514045.64     13523548.29      2514931.06      13521534.4
       2514801.3     13519309.22
#Sta/Elev= 30
  2798.7  218.27  2837.5  221.13  2860.8  214.23  2878.7  218.14  2884.1  215.78
  2889.7  218.23  2909.5  217.06  3013.3  212.47  3266.4  204.25  3372.8  200.38
  3397.7  199.23  3802.6  184.65  4223.7  175.76  4574.9  176.01  4706.6  175.27
  4812.3     174  4843.3  169.79  4947.6  169.22  4954.3   165.6  4970.9   167.1
  4992.3  164.01  4993.5  163.31  5047.6  164.01  5048.1  171.59  5095.2  175.53
    5547  175.84  5703.5  175.77    6652  179.36  7029.5  185.34  7227.6  188.96
#Mann= 16 ,-1 , 0
  2798.7     .05       0  2909.5     .12       0  3013.3     .05       0
  3266.4    .013       0  3372.8     .12       0  3397.7     .04       0
  4223.7     .03       0  4574.9     .05       0  4706.6      .1       0
  4992.3     .05       0  5047.6      .1       0  5095.2     .05       0
    5547     .03       0  5703.5     .12       0    6652     .05       0
  7029.5     .12       0
Bank Sta=4992.3,5047.6
XS Rating Curve= 0 ,0
Exp/Cntr=0.3,0.1

Type RM Length L Ch R = 1 ,50418   ,1098,1098,1098
BEGIN DESCRIPTION:
Mapping XS e304b202
END DESCRIPTION:
XS GIS Cut Line= 4
      2514948.42     13523834.74      2515868.56      13521933.7
      2515785.62     13520277.14      2516714.04     13518819.44
#Sta/Elev= 30
  2869.8  222.15  2983.6  219.87  3269.5   211.5  3407.6  204.09  3515.4  198.12
  3782.1  189.11  4209.6  184.53  4616.3  180.46  4724.8  177.13  4767.6  169.13
  4858.2  171.55  4934.8  167.71  4935.3  163.24  4936.5  162.54  4990.6  163.24
  5000.5   168.9  5030.9  168.13  5060.6  166.29  5100.7  172.06  5129.8  172.92
  5481.1  174.86  5819.3  172.72  6513.6  181.75  6985.4  179.55  7411.7  180.33
  7531.4  179.71  7752.5   179.8  8105.9  182.38  8297.4  184.71  8368.7  185.16
#Mann= 20 ,-1 , 0
  2869.8     .05       0  2983.6     .12       0  3407.6     .05       0
  3515.4     .04       0  3782.1     .05       0  4209.6     .12       0
  4616.3     .12       0  4767.6     .12       0  4935.3     .05       0
  4990.6     .12       0  5030.9      .1       0  5129.8     .04       0
  5819.3    .013       0  6513.6    .013       0  6985.4     .05       0
  7411.7     .05       0  7531.4     .12       0  7752.5     .12       0
  8105.9    .013       0  8297.4     .12       0
Bank Sta=4935.3,4990.6
XS Rating Curve= 0 ,0
Exp/Cntr=0.3,0.1

Type RM Length L Ch R = 1 ,49320   ,1594,1594,1594
BEGIN DESCRIPTION:
Mapping XS a71d0532
END DESCRIPTION:
XS GIS Cut Line= 3
      2516450.16     13523582.99      2516900.01     13522125.03
      2517005.72     13518652.42
#Sta/Elev= 30
  3474.4  196.35  3480.6  196.42  3644.2  195.43  4094.2  181.33  4188.9  180.01
  4298.8  179.59  4555.9  177.66  4605.6   177.1  4874.6   174.4  4961.9  162.35
  4963.2  161.65  5017.5  162.35  5030.2  165.91  5210.3  171.08  5408.4  170.01
  5506.9  169.96  5890.6  171.85  5960.7  168.59  6575.3  175.24  7091.2  176.19
  7161.2  169.79  7280.7  178.03  7464.3  178.74  7501.7   178.7  7601.6  179.23
  7773.5  181.34    7872  182.07  7970.5  182.36  8280.3  185.29  8474.4  186.86
#Mann= 20 ,-1 , 0
  3474.4     .05       0  3480.6     .12       0  4094.2     .05       0
  4188.9     .12       0  4298.8     .04       0  4555.9     .12       0
  4605.6     .04       0  4961.9     .04       0  5017.5     .04       0
  5408.4    .013       0  5506.9     .12       0  6575.3     .05       0
  7280.7     .12       0  7464.3     .05       0  7501.7     .12       0
  7601.6     .05       0  7773.5     .12       0    7872    .013       0
  7970.5     .12       0  8280.3     .05       0
Bank Sta=4961.9,5017.5
XS Rating Curve= 0 ,0
Exp/Cntr=0.3,0.1

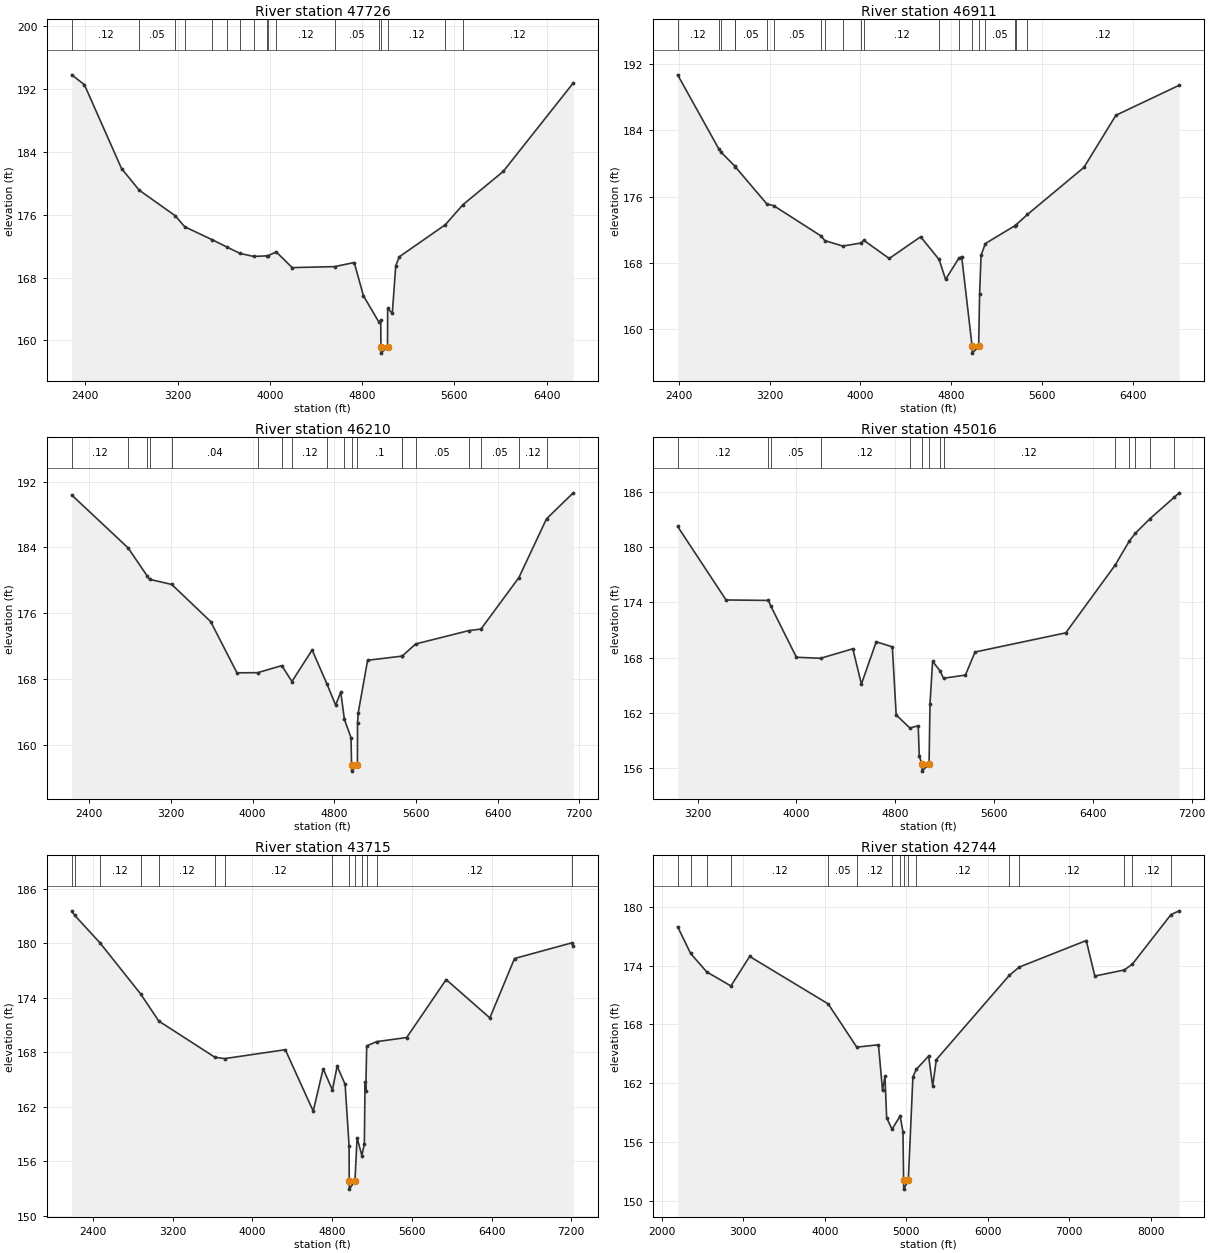
Type RM Length L Ch R = 1 ,47726   ,815,815,815
BEGIN DESCRIPTION:
Mapping XS b6e6729e
END DESCRIPTION:
XS GIS Cut Line= 4
      2516762.64     13523504.91       2517951.9     13521881.62
      2517908.49     13520388.56      2518264.38      13519624.7
#Sta/Elev= 30
  2282.9  193.77  2392.5  192.52  2714.4  181.86  2867.4  179.11  3178.9  175.87
  3262.9  174.45  3501.6   172.8    3631  171.86  3741.1  171.07  3860.8  170.68
    3977  170.76  3980.5  170.74    4056  171.26  4194.3  169.26  4563.4  169.39
    4732  169.91    4812  165.68  4947.1  162.31  4962.1  162.56  4963.4  159.19
  4964.8  158.39  5020.8  159.19  5022.1   164.1  5062.2  163.44  5092.2  169.49
  5122.2  170.63  5522.6  174.72  5674.7  177.26  6024.1  181.49  6631.6  192.74
#Mann= 17 ,-1 , 0
  2282.9     .12       0  2867.4     .05       0  3178.9     .12       0
  3262.9     .05       0  3501.6     .12       0    3631     .05       0
  3741.1     .12       0  3860.8     .05       0    3977     .12       0
  3980.5     .05       0    4056     .12       0  4563.4     .05       0
  4947.1     .12       0  4963.4     .05       0  5020.8     .12       0
  5522.6    .013       0  5674.7     .12       0
Bank Sta=4963.4,5020.8
XS Rating Curve= 0 ,0
Exp/Cntr=0.3,0.1

Type RM Length L Ch R = 1 ,46911   ,701,701,701
BEGIN DESCRIPTION:
Mapping XS 1a5206ea
END DESCRIPTION:
XS GIS Cut Line= 3
      2516918.88     13523496.23      2518611.62     13521482.31
      2519436.29     13519893.74
#Sta/Elev= 30
  2389.9  190.69  2751.3  181.79  2773.1  181.35  2896.6  179.64  2898.9  179.58
  3177.5  175.09  3235.8  174.91  3653.6  171.25  3687.1  170.69  3845.3  170.03
  4003.4  170.39    4031  170.72  4254.8  168.53  4531.9  171.15  4694.1  168.41
  4751.7  166.01  4868.7  168.57  4893.5  168.76  4985.7  157.91  4987.1  157.11
  5043.1  157.91  5051.5  164.27  5064.5  168.91    5102  170.33  5363.7  172.49
  5373.9  172.61  5473.1  173.84    5971  179.52  6252.9  185.81  6810.6  189.43
#Mann= 20 ,-1 , 0
  2389.9     .12       0  2751.3     .04       0  2773.1     .05       0
  2896.6     .03       0  2898.9     .05       0  3177.5     .12       0
  3235.8     .05       0  3653.6     .12       0  3687.1     .05       0
  3845.3     .04       0  4003.4     .05       0    4031     .12       0
  4694.1     .05       0  4868.7      .1       0  4985.7     .05       0
  5043.1      .1       0    5102     .05       0  5363.7     .12       0
  5373.9     .05       0  5473.1     .12       0
Bank Sta=4985.7,5043.1
XS Rating Curve= 0 ,0
Exp/Cntr=0.3,0.1

Type RM Length L Ch R = 1 ,46210   ,1194,1194,1194
BEGIN DESCRIPTION:
Mapping XS 622f42d4
END DESCRIPTION:
XS GIS Cut Line= 3
       2516823.4     13523643.79      2519063.01     13522011.83
      2520677.63     13520605.54
#Sta/Elev= 30
  2229.6  190.37  2781.6  183.94  2966.1  180.57  2991.4  180.12  3209.4  179.49
  3590.5  174.97  3847.7  168.74  4051.2  168.76  4287.2  169.62    4386  167.68
    4584  171.52  4730.3  167.35  4814.2  164.81  4864.4   166.4  4899.9  163.08
  4964.9  160.85  4970.2  157.58  4971.5  156.78  5027.6  157.58  5028.6  162.65
  5035.2  163.85  5127.3  170.27  5462.9  170.77  5468.2   170.8  5597.5  172.25
  6116.3  173.87  6237.9  174.07  6608.7  180.32  6879.7  187.48  7141.9  190.64
#Mann= 19 ,-1 , 0
  2229.6     .12       0  2781.6     .04       0  2966.1     .05       0
  2991.4     .03       0  3209.4     .04       0  4051.2     .12       0
  4287.2     .05       0    4386     .12       0  4730.3     .05       0
  4899.9      .1       0  4970.2     .05       0  5027.6      .1       0
  5462.9     .05       0  5468.2     .12       0  5597.5     .05       0
  6116.3    .013       0  6237.9     .05       0  6608.7     .12       0
  6879.7     .05       0
Bank Sta=4970.2,5027.6
XS Rating Curve= 0 ,0
Exp/Cntr=0.3,0.1

Type RM Length L Ch R = 1 ,45016   ,1301,1301,1301
BEGIN DESCRIPTION:
Mapping XS 54598e94
END DESCRIPTION:
XS GIS Cut Line= 3
      2517396.36     13523617.72       2519201.9     13523131.62
      2521007.43     13521890.31
#Sta/Elev= 30
  3037.8  182.24  3429.9  174.26  3772.8  174.21    3792  173.61  3999.5  168.04
  4194.9  167.93  4456.3  168.96  4525.8  165.13  4645.7  169.72  4776.2  169.17
  4807.3  161.78  4918.6  160.36  4985.7  160.61  4994.5  157.27  5016.1  156.48
  5017.4  155.68  5073.7  156.48  5081.1  162.98  5102.1  167.59  5161.9  166.58
  5190.7  165.76  5367.9  166.11  5445.7  168.61  6180.5  170.69  6580.5  178.05
  6695.1  180.66  6743.6   181.5  6862.3  183.08  7059.7  185.42  7098.7  185.89
#Mann= 14 ,-1 , 0
  3037.8     .12       0  3772.8     .04       0    3792     .05       0
  4194.9     .12       0  4918.6      .1       0  5016.1     .05       0
  5073.7      .1       0  5161.9     .03       0  5190.7     .12       0
  6580.5     .05       0  6695.1     .03       0  6743.6    .013       0
  6862.3     .03       0  7059.7     .05       0
Bank Sta=5016.1,5073.7
XS Rating Curve= 0 ,0
Exp/Cntr=0.3,0.1

Type RM Length L Ch R = 1 ,43715   ,971,971,971
BEGIN DESCRIPTION:
Mapping XS 8859a23b
END DESCRIPTION:
XS GIS Cut Line= 3
       2516762.7     13524112.52      2519670.65     13524199.33
      2521110.83     13522637.68
#Sta/Elev= 30
  2186.7  183.57    2215  183.09  2470.3  180.04  2876.8  174.44  3060.6  171.43
  3623.3  167.45  3721.6   167.3    4330  168.28  4610.1  161.52  4710.1  166.18
  4802.7  163.84  4850.2  166.47  4930.2  164.47  4970.2  157.66  4971.4  153.83
  4972.8  152.93  5029.1  153.83  5050.3   158.6  5098.5  156.62  5123.4  157.94
  5130.2  164.76  5137.5  163.73  5146.9   168.7  5248.1  169.17  5548.1  169.62
  5944.5     176  6382.8  171.78  6630.6  178.32  7210.4  180.06  7220.3  179.73
#Mann= 14 ,-1 , 0
  2186.7     .12       0    2215     .05       0  2470.3     .12       0
  2876.8     .05       0  3060.6     .12       0  3623.3     .05       0
  3721.6     .12       0  4802.7     .05       0  4971.4     .05       0
  5029.1     .05       0  5098.5     .12       0  5146.9      .1       0
  5248.1     .12       0  7210.4     .05       0
Bank Sta=4971.4,5029.1
XS Rating Curve= 0 ,0
Exp/Cntr=0.3,0.1

Type RM Length L Ch R = 1 ,42744   ,1340,1340,1340
BEGIN DESCRIPTION:
Mapping XS ef1dc809
END DESCRIPTION:
XS GIS Cut Line= 4
      2516727.98     13525353.84      2519523.08     13525119.46
      2521016.13     13524051.76      2521233.15       13522550.
#Sta/Elev= 30
  2193.1  177.96  2352.8  175.23  2550.6  173.35  2847.3  171.92  3077.5  174.93
  4041.6  170.09  4392.2  165.68  4658.7  165.92  4708.9  161.26    4739  162.72
  4759.1  158.48  4825.4   157.3  4924.3  158.66  4959.8  157.05  4967.6   152.1
    4969   151.2  5025.3   152.1  5081.7  162.65  5122.9  163.41  5274.6  164.77
  5324.9   161.7  5369.2  164.41  6264.2  172.99  6386.4  173.84  7209.7  176.55
  7315.3  172.93  7677.6  173.55  7776.8  174.15  8250.2   179.2  8350.9  179.58
#Mann= 16 ,-1 , 0
  2193.1     .04       0  2352.8    .013       0  2550.6     .05       0
  2847.3     .12       0  4041.6     .05       0  4392.2     .12       0
  4825.4     .05       0  4924.3      .1       0  4967.6     .05       0
  5025.3      .1       0  5122.9     .12       0  6264.2     .05       0
  6386.4     .12       0  7677.6     .05       0  7776.8     .12       0
  8250.2    .013       0
Bank Sta=4967.6,5025.3
XS Rating Curve= 0 ,0
Exp/Cntr=0.3,0.1