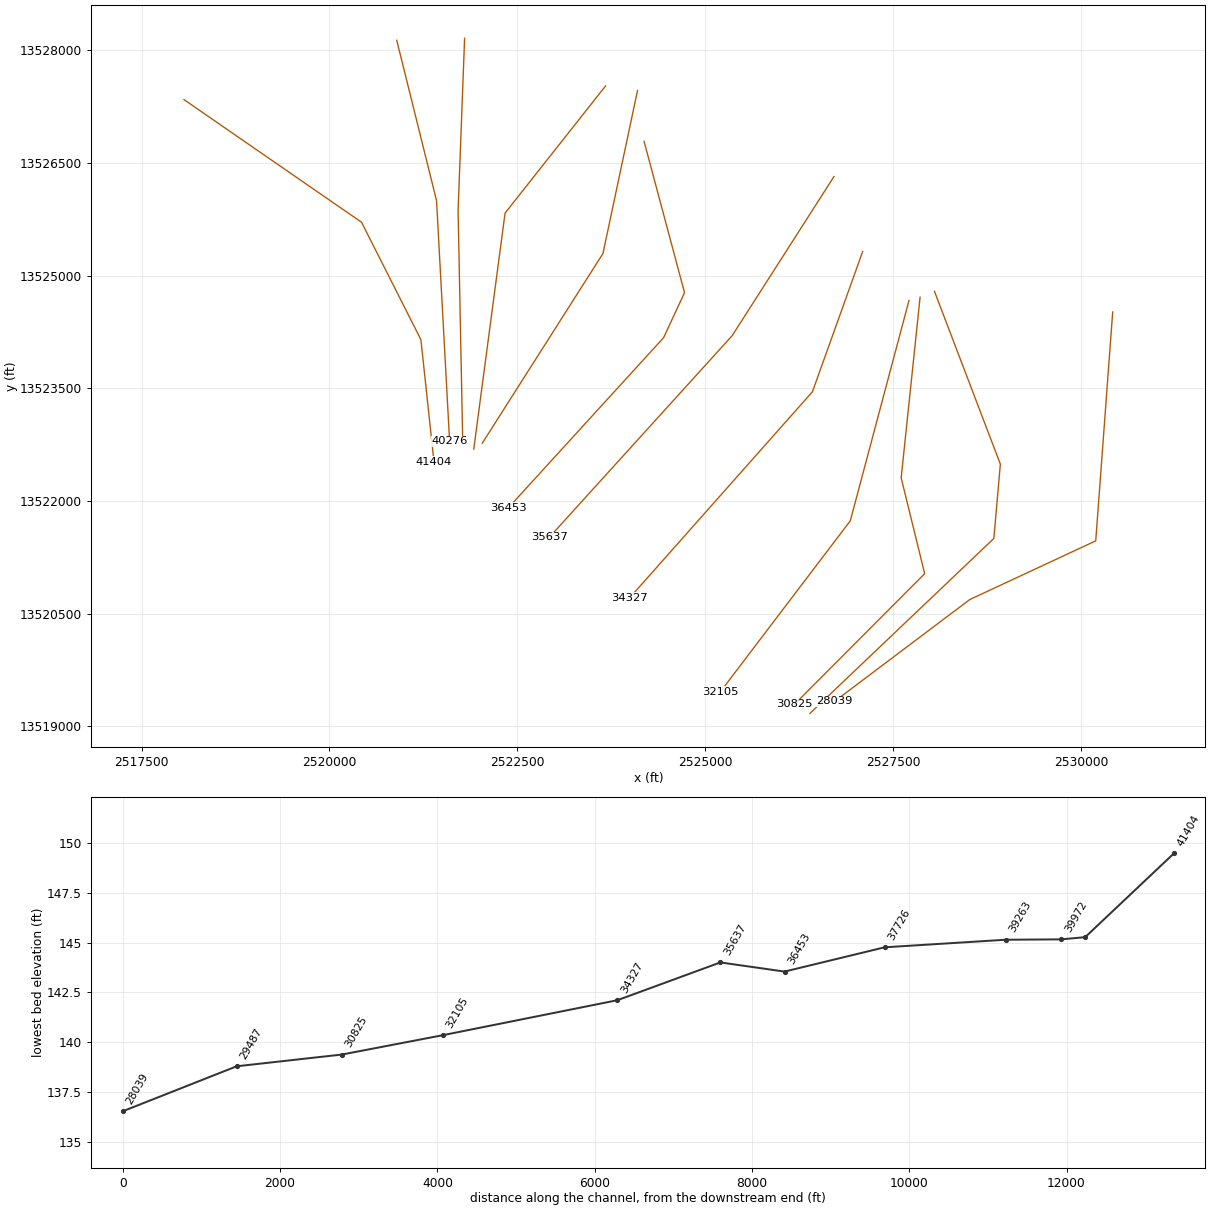
HEC-RAS study TWELVEMILE CREEK.prj: TWELVEMILE CREEK Base Level Engineering

--- TWELVEMILE CREEK.g01 (geometry) --- (continued)

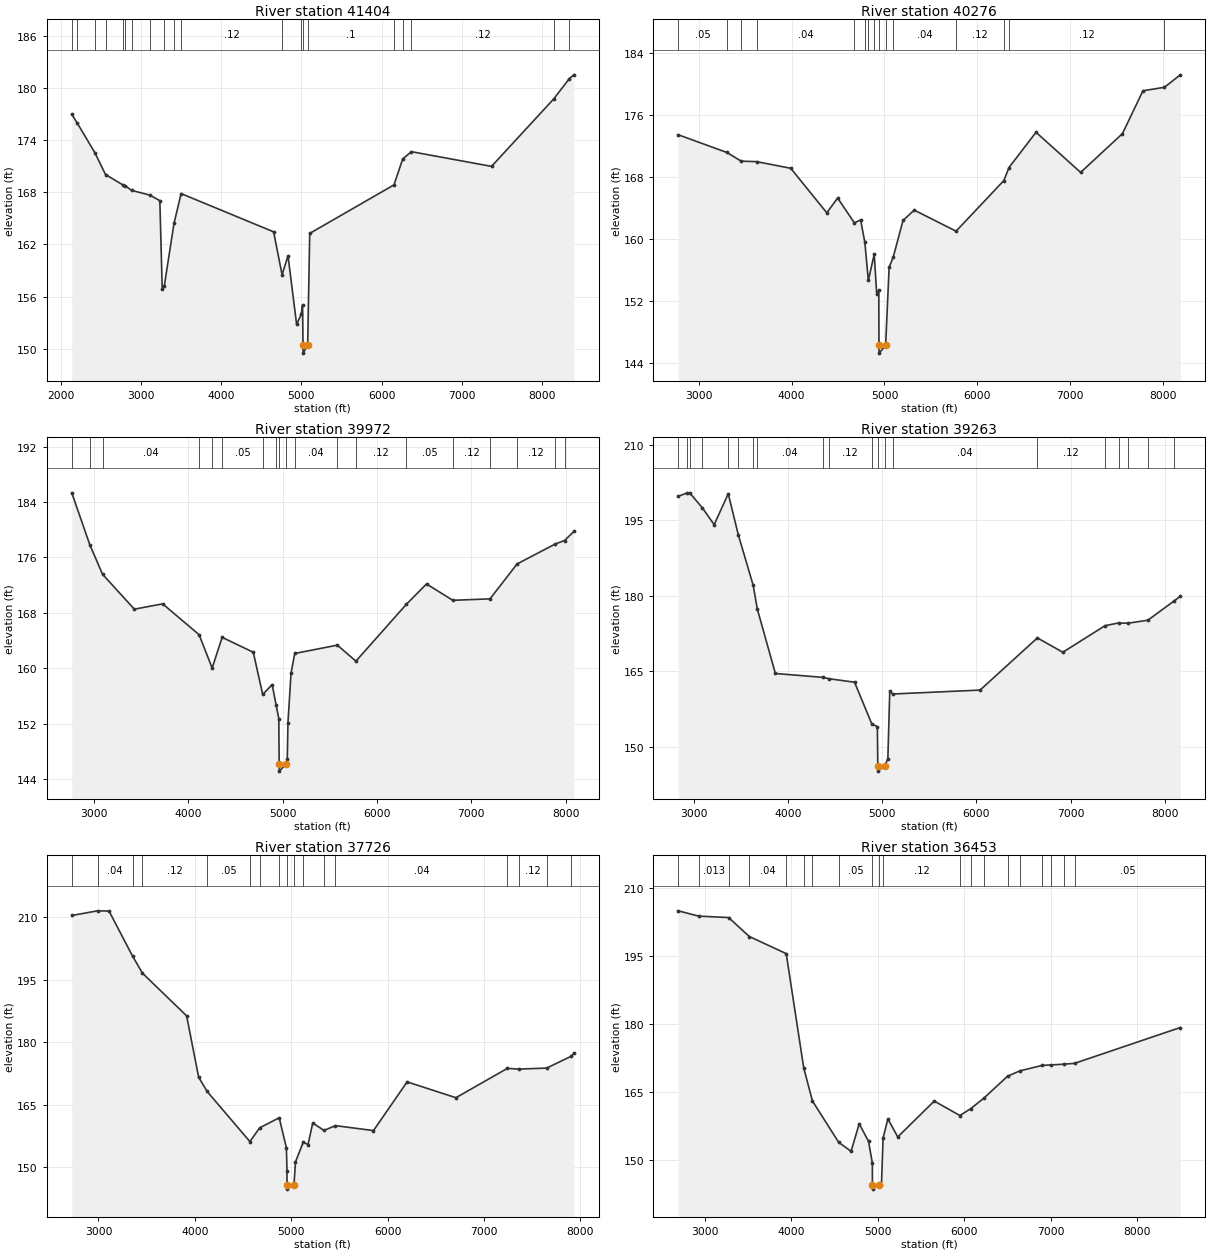
Type RM Length L Ch R = 1 ,41404   ,1128,1128,1128
BEGIN DESCRIPTION:
Mapping XS f3b47fb3
END DESCRIPTION:
XS GIS Cut Line= 4
      2518064.73     13527341.69      2520425.85     13525709.74
      2521215.78     13524147.24       2521389.4     13522523.95
#Sta/Elev= 30
  2140.1  176.96  2208.9  175.94  2427.6  172.55  2560.6  170.03    2776  168.84
  2804.4  168.75  2884.6  168.21  3110.4  167.67    3237  167.03  3266.8  156.85
    3292  157.19  3413.9  164.43    3502  167.84  4654.4  163.44  4759.5  158.51
  4833.5  160.68    4941  152.79  4998.6  153.96  5014.9  155.02  5020.2  150.39
  5021.6  149.49  5078.3  150.39  5103.9  163.26  6153.4  168.84  6262.3  171.83
  6371.2  172.66  7368.4  170.97  8144.2  178.74  8338.3  181.07  8393.7   181.5
#Mann= 20 ,-1 , 0
  2140.1    .013       0  2208.9     .04       0  2427.6    .013       0
  2560.6     .05       0    2776     .04       0  2804.4     .05       0
  2884.6     .04       0  3110.4     .05       0    3292     .12       0
  3413.9      .1       0    3502     .12       0  4759.5     .05       0
  4998.6      .1       0  5020.2     .05       0  5078.3      .1       0
  6153.4     .04       0  6262.3     .05       0  6371.2     .12       0
  8144.2    .013       0  8338.3     .12       0
Bank Sta=5020.2,5078.3
XS Rating Curve= 0 ,0
Exp/Cntr=0.3,0.1

Type RM Length L Ch R = 1 ,40276   ,304,304,304
BEGIN DESCRIPTION:
Mapping XS 2fdd87de
END DESCRIPTION:
XS GIS Cut Line= 3
      2520894.61     13528131.59      2521424.12      13525996.2
      2521597.73     13522793.06
#Sta/Elev= 30
  2778.4  173.48  3301.4   171.2  3456.6  170.07  3622.2  170.01  3990.6  169.15
  4378.3   163.4  4495.5  165.31    4676   162.1  4742.7  162.48  4788.4  159.59
    4826  154.67  4889.3  158.04  4916.3  152.91  4938.5  153.44  4940.6  146.28
  4942.1  145.28  5012.4  146.28  5049.8  156.36  5093.1  157.64    5200  162.42
  5320.2  163.75    5771  161.03  6285.8  167.57  6341.2  169.25  6632.1   173.8
  7112.8  168.62  7563.4  173.63  7783.8  179.16  8015.4  179.61  8186.3  181.22
#Mann= 15 ,-1 , 0
  2778.4     .05       0  3301.4     .04       0  3456.6     .05       0
  3622.2     .04       0    4676     .05       0  4788.4      .1       0
    4826     .12       0  4889.3      .1       0  4940.6     .05       0
  5012.4      .1       0  5093.1     .04       0    5771     .12       0
  6285.8     .05       0  6341.2     .12       0  8015.4    .013       0
Bank Sta=4940.6,5012.4
XS Rating Curve= 0 ,0
Exp/Cntr=0.3,0.1

Type RM Length L Ch R = 1 ,39972   ,709,709,709
BEGIN DESCRIPTION:
Mapping XS ecefb54f
END DESCRIPTION:
XS GIS Cut Line= 3
      2521797.38     13528157.69      2521710.58     13525865.99
       2521771.3     13522838.24
#Sta/Elev= 30
  2764.6  185.33  2955.7  177.84  3090.6  173.58  3427.8  168.54    3728  169.31
    4114  164.86  4252.6  160.04  4358.5  164.48  4688.7  162.32  4788.3  156.23
  4888.8  157.66  4930.8  154.68  4958.9  152.76    4963  146.17  4964.5  145.17
  5034.8  146.17  5048.9  146.92  5055.9  152.13  5088.9  159.32  5128.2  162.15
  5579.3  163.35  5776.4  161.04  6310.7  169.24  6524.7  172.18  6803.5  169.82
  7197.7  170.03  7485.1  175.07  7888.2  177.94  7987.7  178.45  8086.3  179.75
#Mann= 19 ,-1 , 0
  2764.6     .04       0  2955.7    .013       0  3090.6     .04       0
    4114     .05       0  4252.6     .04       0  4358.5     .05       0
  4788.3     .12       0  4930.8     .05       0    4963     .05       0
  5034.8     .05       0  5128.2     .04       0  5579.3     .05       0
  5776.4     .12       0  6310.7     .05       0  6803.5     .12       0
  7197.7     .05       0  7485.1     .12       0  7888.2    .013       0
  7987.7     .05       0
Bank Sta=4963,5034.8
XS Rating Curve= 0 ,0
Exp/Cntr=0.3,0.1

Type RM Length L Ch R = 1 ,39263   ,1537,1537,1537
BEGIN DESCRIPTION:
Mapping XS c4eff555
END DESCRIPTION:
XS GIS Cut Line= 3
      2523672.37     13527523.96      2522335.58     13525831.27
      2521918.98     13522689.47
#Sta/Elev= 30
  2837.2  199.78  2934.2  200.47  2961.9  200.39  3092.6   197.5  3218.3  194.14
  3367.7  200.29  3475.8  192.03  3632.5  182.07  3676.2  177.36  3867.6  164.56
  4375.1  163.78  4432.1  163.53  4707.7  162.82    4889  154.61  4949.7  153.97
  4954.4  146.15  4955.9  145.15  5026.7  146.15  5060.9  147.61  5081.1  160.99
  5112.1  160.48  6039.4  161.26  6647.2  171.63  6917.1  168.78  7364.8  174.06
  7507.7   174.6  7607.5  174.55  7819.4  175.15  8093.4  178.92  8163.4   179.9
#Mann= 20 ,-1 , 0
  2837.2     .12       0  2934.2     .05       0  2961.9     .12       0
  3092.6     .04       0  3367.7     .05       0  3475.8     .03       0
  3632.5     .12       0  3676.2     .04       0  4375.1     .05       0
  4432.1     .12       0    4889     .05       0  4954.4     .05       0
  5026.7     .05       0  5112.1     .04       0  6647.2     .12       0
  7364.8     .12       0  7507.7    .013       0  7607.5     .12       0
  7819.4     .05       0  8093.4     .12       0
Bank Sta=4954.4,5026.7
XS Rating Curve= 0 ,0
Exp/Cntr=0.3,0.1

Type RM Length L Ch R = 1 ,37726   ,1273,1273,1273
BEGIN DESCRIPTION:
Mapping XS 53a060d8
END DESCRIPTION:
XS GIS Cut Line= 3
      2524097.72     13527463.17      2523637.66     13525293.08
      2522032.68     13522768.49
#Sta/Elev= 30
  2723.2  210.47  2990.7  211.59  3109.8  211.53    3355  200.68  3456.4  196.63
  3914.9  186.38    4040  171.63  4127.4  168.23  4571.5  156.19  4672.9  159.48
  4875.7  161.91  4950.5  154.67  4956.4  149.15  4956.7  145.77  4958.2  144.77
    5029  145.77  5044.5   151.3  5125.4  156.05  5174.9  155.47  5223.6  160.66
    5340  158.86    5459  160.01    5854  158.83  6202.9  170.52  6709.3  166.72
  7243.2  173.76  7362.2  173.59  7650.9  173.83  7904.6  176.66  7933.1  177.36
#Mann= 17 ,-1 , 0
  2723.2    .013       0  2990.7     .04       0    3355     .05       0
  3456.4     .12       0  4127.4     .05       0  4571.5     .12       0
  4672.9     .04       0  4875.7     .12       0  4956.7     .05       0
    5029     .12       0  5125.4     .04       0    5340     .05       0
    5459     .04       0  7243.2    .013       0  7362.2     .12       0
  7650.9     .05       0  7904.6     .12       0
Bank Sta=4956.7,5029
XS Rating Curve= 0 ,0
Exp/Cntr=0.3,0.1

Type RM Length L Ch R = 1 ,36453   ,816,816,816
BEGIN DESCRIPTION:
Mapping XS 3c29e184
END DESCRIPTION:
XS GIS Cut Line= 4
      2524184.54     13526786.12      2524722.73     13524772.24
      2524444.95     13524173.28      2522379.01     13521907.69
#Sta/Elev= 30
  2690.9  204.89  2927.8  203.72  3273.6  203.41  3513.2  199.23  3940.6  195.46
  4143.2  170.28  4244.4  162.97  4548.3  153.85  4691.2  151.89  4785.4  157.95
  4893.7  154.07  4937.8  149.25  4938.1  144.55  4939.6  143.55  5010.4  144.55
  5042.9  144.55  5061.9  154.81  5117.2  159.02  5231.7  155.05  5653.7  162.96
  5950.6  159.77  6077.3   161.3  6229.8  163.63    6502  168.43  6643.5  169.61
  6903.3  170.82  7007.9  170.93    7154  171.09  7278.8  171.28  8501.8  179.17
#Mann= 20 ,-1 , 0
  2690.9    .013       0  2927.8    .013       0  3273.6     .04       0
  3513.2     .04       0  3940.6     .12       0  4143.2     .05       0
  4244.4     .12       0  4548.3     .05       0  4938.1     .05       0
  5010.4     .05       0  5061.9     .12       0  5950.6     .05       0
  6077.3    .013       0  6229.8    .013       0    6502     .05       0
  6643.5     .05       0  6903.3     .04       0  7007.9     .05       0
    7154    .013       0  7278.8     .05       0
Bank Sta=4938.1,5010.4
XS Rating Curve= 0 ,0
Exp/Cntr=0.3,0.1

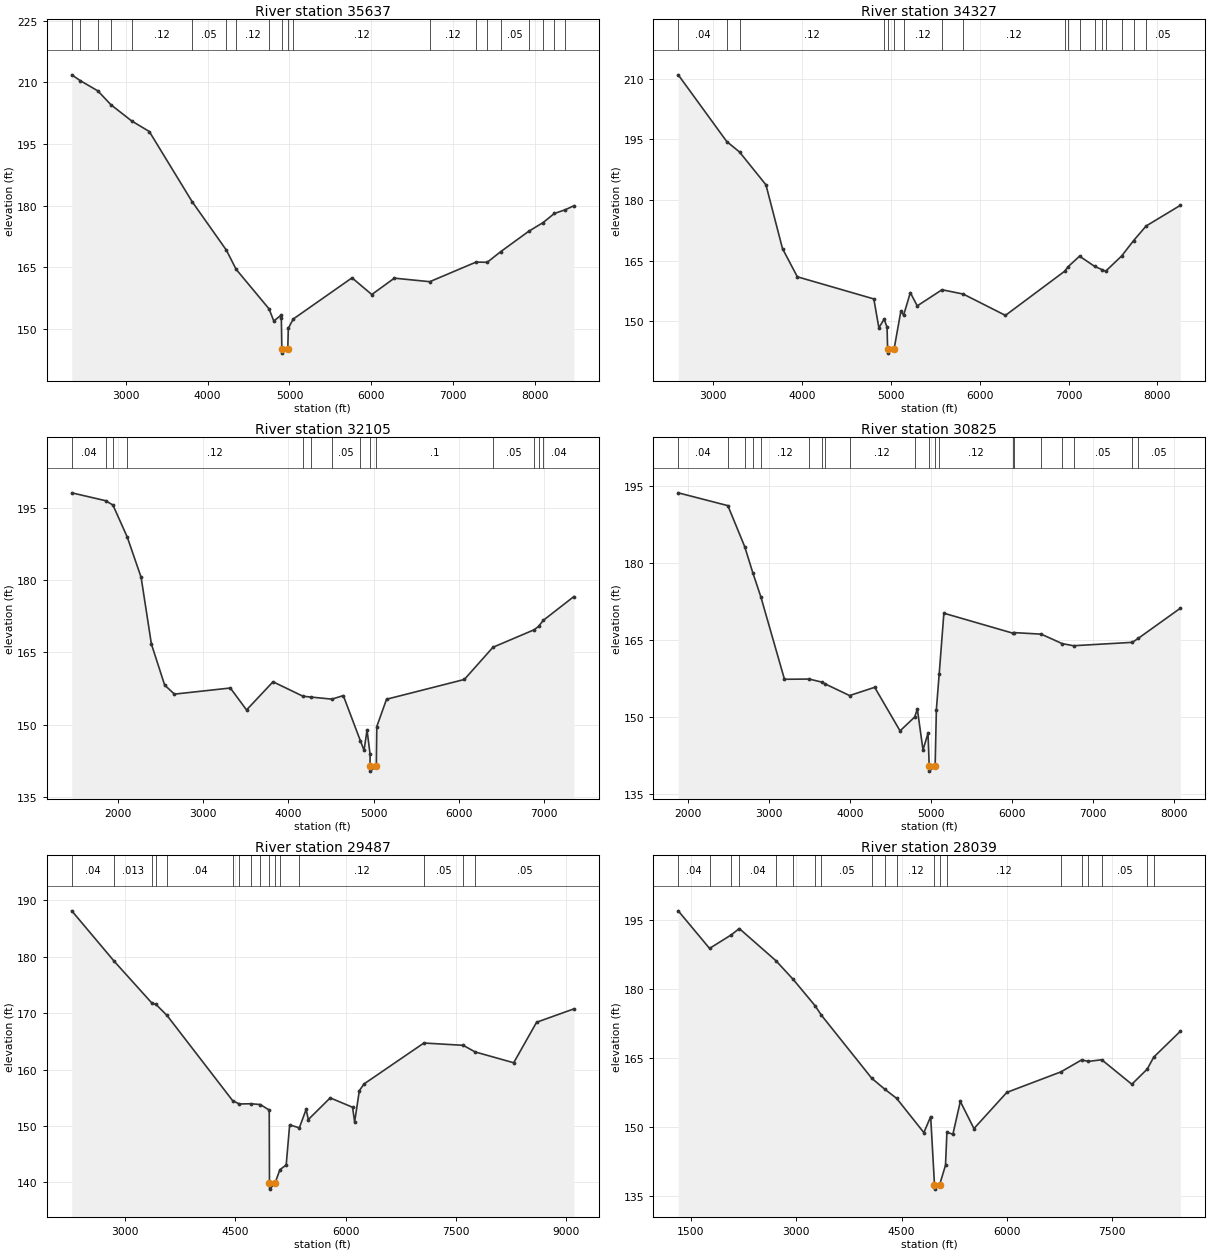
Type RM Length L Ch R = 1 ,35637   ,1310,1310,1310
BEGIN DESCRIPTION:
Mapping XS a6a510f9
END DESCRIPTION:
XS GIS Cut Line= 3
      2526710.58     13526317.38      2525356.41     13524199.33
      2522925.83       13521517.
#Sta/Elev= 30
  2340.4  211.87  2443.2  210.47  2660.1  207.94    2819  204.57  3072.6  200.62
  3287.5  198.05  3809.6  180.98  4230.5  169.08  4347.9  164.46  4750.1  154.81
  4808.3  151.85  4893.8  153.21  4900.7  152.58  4906.8  145.01  4908.3  144.01
  4979.4  145.01  4985.7  150.03    5045  152.31  5764.3  162.37  6005.6   158.3
  6281.3  162.29  6714.1  161.43  7279.5  166.21  7416.1  166.16    7581  168.76
  7921.4   173.7  8098.7  175.85  8235.9  178.06  8371.7  178.99  8474.1  179.94
#Mann= 20 ,-1 , 0
  2340.4     .12       0  2443.2     .12       0  2660.1     .04       0
    2819     .04       0  3072.6     .12       0  3809.6     .05       0
  4230.5     .03       0  4347.9     .12       0  4750.1      .1       0
  4906.8     .05       0  4979.4      .1       0    5045     .12       0
  6714.1     .12       0  7279.5     .04       0  7416.1     .04       0
    7581     .05       0  7921.4     .12       0  8098.7    .013       0
  8235.9     .05       0  8371.7     .03       0
Bank Sta=4906.8,4979.4
XS Rating Curve= 0 ,0
Exp/Cntr=0.3,0.1

Type RM Length L Ch R = 1 ,34327   ,2222,2222,2222
BEGIN DESCRIPTION:
Mapping XS 1a641e21
END DESCRIPTION:
XS GIS Cut Line= 3
      2527092.53     13525319.14      2526424.12      13523452.8
      2523993.69     13520709.88
#Sta/Elev= 30
  2609.4  210.91    3155  194.42  3298.6  191.84    3596  183.72  3782.2  167.94
  3949.2  160.98  4809.2  155.51  4866.1  148.38  4924.5  150.48  4958.1  148.56
  4964.5  143.11    4966  142.11  5037.1  143.11  5113.7  152.51  5144.5   151.5
  5219.9  157.06  5297.7  153.79  5576.3  157.78  5815.3  156.71  6289.6  151.44
  6956.5  162.37  6991.6  163.41  7123.3  166.08  7292.1  163.57  7376.6  162.74
  7416.1  162.35  7596.8  166.13  7731.8  169.95  7872.6  173.55  8256.6  178.64
#Mann= 18 ,-1 , 0
  2609.4     .04       0    3155     .05       0  3298.6     .12       0
  4924.5      .1       0  4964.5     .05       0  5037.1      .1       0
  5144.5     .12       0  5576.3     .05       0  5815.3     .12       0
  6956.5     .05       0  6991.6     .12       0  7123.3     .05       0
  7292.1     .12       0  7376.6     .05       0  7416.1     .12       0
  7596.8     .05       0  7731.8     .12       0  7872.6     .05       0
Bank Sta=4964.5,5037.1
XS Rating Curve= 0 ,0
Exp/Cntr=0.3,0.1

Type RM Length L Ch R = 1 ,32105   ,1280,1280,1280
BEGIN DESCRIPTION:
Mapping XS 8d588da3
END DESCRIPTION:
XS GIS Cut Line= 3
      2527708.84     13524668.07      2526927.59     13521734.05
      2525200.23     13519459.83
#Sta/Elev= 30
  1457.8  198.07  1854.2  196.44  1940.7  195.54  2109.6  188.87  2271.4  180.56
  2392.3  166.71  2547.6  158.21  2662.3  156.32  3318.6  157.59  3508.9  153.04
  3819.6  158.88  4171.4  155.88  4265.3  155.71  4511.1  155.28  4644.4  156.02
  4843.6   146.7  4887.6  144.66    4923  148.86  4958.4   143.9  4958.7  141.35
  4960.2  140.35  5031.7  141.35  5037.4   149.6  5151.8  155.26  6064.8  159.36
  6400.9  166.04  6884.1  169.67  6936.6  170.38  6989.7   171.6  7349.9  176.55
#Mann= 14 ,-1 , 0
  1457.8     .04       0  1854.2    .013       0  1940.7     .04       0
  2109.6     .12       0  4171.4     .05       0  4265.3     .12       0
  4511.1     .05       0  4843.6      .1       0  4958.7     .05       0
  5031.7      .1       0  6400.9     .05       0  6884.1     .04       0
  6936.6     .05       0  6989.7     .04       0
Bank Sta=4958.7,5031.7
XS Rating Curve= 0 ,0
Exp/Cntr=0.3,0.1

Type RM Length L Ch R = 1 ,30825   ,1338,1338,1338
BEGIN DESCRIPTION:
Mapping XS ae94f2ac
END DESCRIPTION:
XS GIS Cut Line= 4
      2527856.41     13524711.45      2527604.67     13522306.96
      2527917.17     13521030.92      2526183.78     13519289.71
#Sta/Elev= 30
  1883.7  193.73  2495.3  191.23  2703.3  183.21  2802.7  178.13  2902.2   173.4
    3193  157.32  3498.6  157.36  3657.1  156.75  3697.5  156.39  3995.7  154.14
  4304.9  155.75  4617.7  147.24  4797.9  149.95  4830.9   151.5  4900.5  143.52
  4962.3  146.78  4977.2  140.38  4978.7  139.38  5050.2  140.38  5065.2   151.4
  5100.3  158.39  5157.9  170.22  6014.7  166.29  6026.4  166.43  6357.8  166.13
  6616.6  164.28  6755.7  163.87  7481.1  164.53  7552.8   165.3    8072  171.19
#Mann= 20 ,-1 , 0
  1883.7     .04       0  2495.3     .05       0  2703.3    .013       0
  2802.7     .04       0  2902.2     .12       0  3498.6     .05       0
  3657.1     .12       0  3697.5     .05       0  3995.7     .12       0
  4797.9     .05       0  4977.2     .05       0  5050.2     .05       0
  5100.3     .12       0  6014.7     .05       0  6026.4     .12       0
  6357.8     .05       0  6616.6     .12       0  6755.7     .05       0
  7481.1     .04       0  7552.8     .05       0
Bank Sta=4977.2,5050.2
XS Rating Curve= 0 ,0
Exp/Cntr=0.3,0.1

Type RM Length L Ch R = 1 ,29487   ,1448,1448,1448
BEGIN DESCRIPTION:
Mapping XS 38e6b426
END DESCRIPTION:
XS GIS Cut Line= 4
       2528047.4     13524789.56      2528924.12     13522489.26
      2528837.31     13521499.67      2526391.82     13519171.37
#Sta/Elev= 30
  2273.2  188.14    2851  179.19    3362   171.8  3419.5  171.54  3568.6   169.6
  4463.3  154.46  4554.2  153.89  4711.6  153.93  4839.2  153.79    4960  152.81
  4963.6  139.79  4965.1  138.79  5036.7  139.79  5105.4  142.24  5190.9  143.08
  5237.9  150.18  5369.7  149.66    5462  152.92  5492.1  151.13  5789.7  154.97
  6093.9  153.31  6122.2   150.7  6186.1  156.25  6249.6  157.44  7064.5   164.7
  7600.2  164.29  7761.1  163.12  8286.5   161.2  8597.9  168.38  9104.9  170.75
#Mann= 16 ,-1 , 0
  2273.2     .04       0    2851    .013       0    3362     .05       0
  3419.5    .013       0  3568.6     .04       0  4463.3     .05       0
  4554.2     .04       0  4711.6     .05       0  4839.2     .04       0
  4963.6     .05       0  5036.7     .04       0  5105.4     .05       0
  5369.7     .12       0  7064.5     .05       0  7600.2     .12       0
  7761.1     .05       0
Bank Sta=4963.6,5036.7
XS Rating Curve= 0 ,0
Exp/Cntr=0.3,0.1

Type RM Length L Ch R = 1 ,28039   ,756,756,756
BEGIN DESCRIPTION:
Mapping XS 88b37d3d
END DESCRIPTION:
XS GIS Cut Line= 4
      2530418.48     13524514.89      2530192.78     13521467.99
      2528517.43     13520686.74      2526720.56     13519332.57
#Sta/Elev= 30
  1318.5  196.95  1764.8  188.79  2075.1  191.74    2188  193.11  2710.8  186.12
  2954.9  182.09  3269.9  176.32  3356.8  174.32  4076.3  160.59  4259.2  158.25
  4430.6  156.23  4818.4   148.8  4915.3  152.28  4969.7  137.53  4971.2  136.53
  5043.8  137.53  5126.6  141.71  5146.6  148.87  5231.9  148.45  5337.9  155.57
  5531.9  149.67  6000.2  157.53  6771.9  161.99  7066.9  164.59  7163.4  164.26
  7352.7  164.62  7781.5   159.3  8000.2  162.58  8094.8  165.21  8472.3   170.8
#Mann= 20 ,-1 , 0
  1318.5     .04       0  1764.8     .04       0  2075.1    .013       0
    2188     .04       0  2710.8    .013       0  2954.9     .05       0
  3269.9    .013       0  3356.8     .05       0  4076.3     .12       0
  4259.2     .05       0  4430.6     .12       0  4969.7     .05       0
  5043.8     .12       0  5146.6     .12       0  6771.9     .05       0
  7066.9     .05       0  7163.4     .12       0  7352.7     .05       0
  8000.2     .12       0  8094.8     .05       0
Bank Sta=4969.7,5043.8
XS Rating Curve= 0 ,0
Exp/Cntr=0.3,0.1