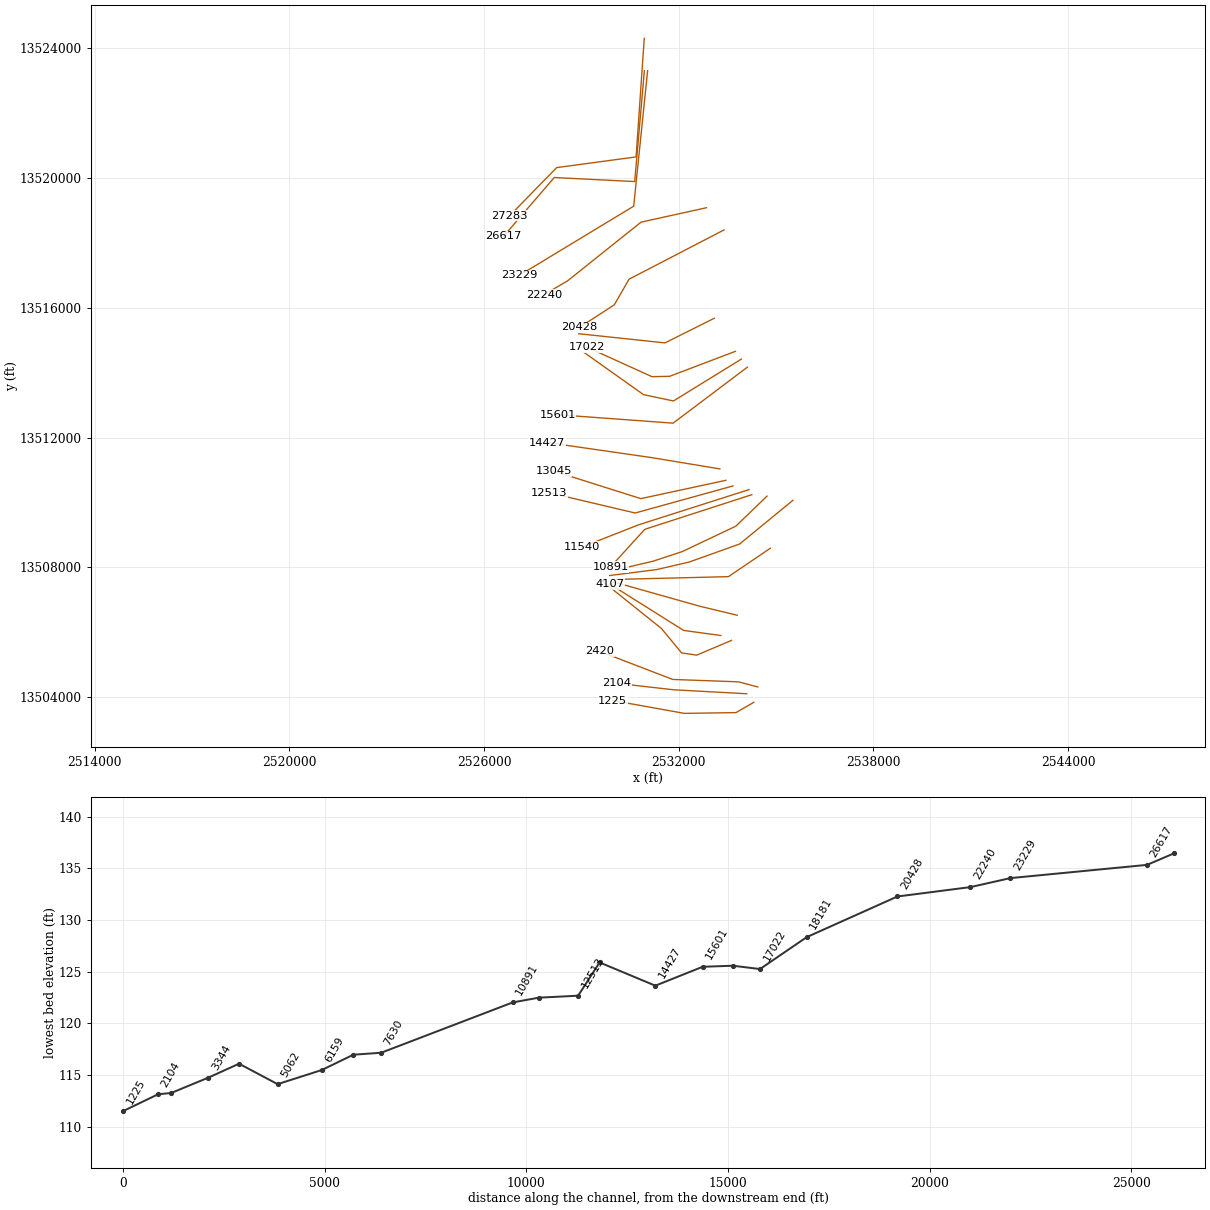
HEC-RAS study TWELVEMILE CREEK.prj: TWELVEMILE CREEK Base Level Engineering

--- TWELVEMILE CREEK.g01 (geometry) --- (continued)

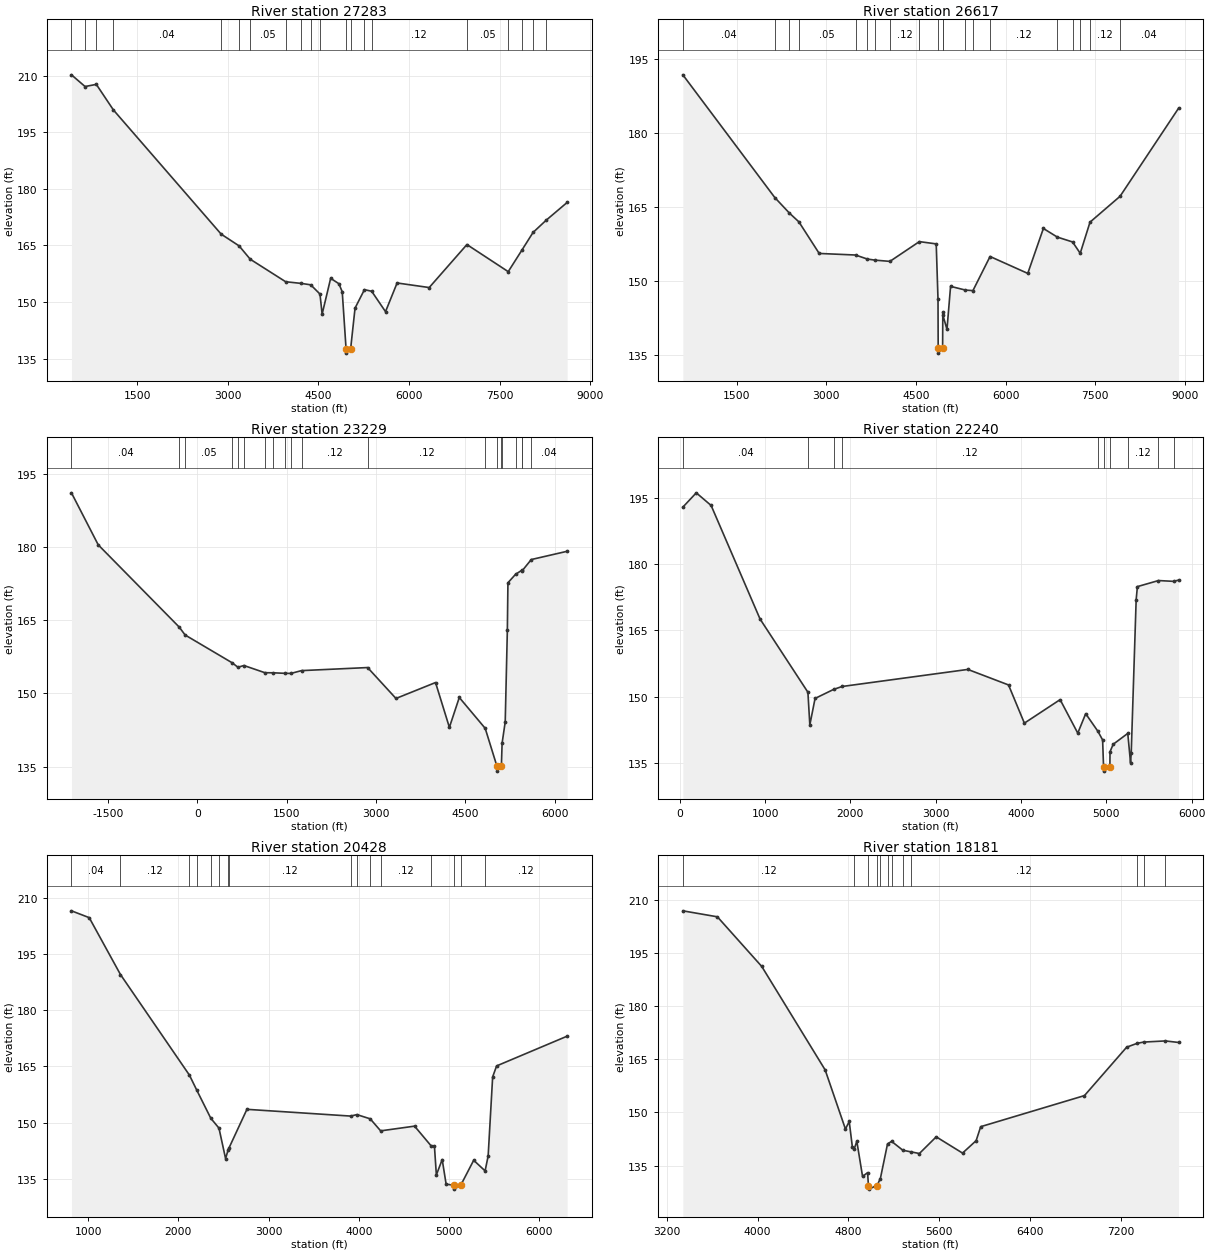
Type RM Length L Ch R = 1 ,27283   ,666,666,666
BEGIN DESCRIPTION:
Mapping XS a0fa6fd8
END DESCRIPTION:
XS GIS Cut Line= 4
      2530939.31      13524306.5      2530687.57     13520652.02
      2528239.66     13520322.16      2526791.12     13518838.92
#Sta/Elev= 30
   412.4  210.19   637.7  207.09   824.2  207.66    1107  200.88  2891.2  167.97
  3187.8  164.86  3372.6  161.32  3958.3  155.36  4220.1  154.91  4373.7  154.54
  4526.8  152.09  4562.5  146.78  4703.7  156.26  4839.7  154.84  4895.5  152.69
  4959.3  137.44  4960.8  136.44  5033.4  137.44  5107.4  148.37  5262.7  153.26
  5382.5  152.84  5611.9  147.43  5803.6  155.03  6335.2  153.82  6959.5  165.21
  7643.4  158.03  7867.9  163.69  8053.8  168.41  8272.1  171.67  8618.8  176.37
#Mann= 20 ,-1 , 0
   412.4     .04       0   637.7    .013       0   824.2     .03       0
    1107     .04       0  2891.2     .05       0  3187.8     .12       0
  3372.6     .05       0  3958.3     .05       0  4220.1     .12       0
  4373.7     .05       0  4526.8     .12       0  4959.3     .05       0
  5033.4     .12       0  5262.7     .05       0  5382.5     .12       0
  6959.5     .05       0  7643.4     .05       0  7867.9     .12       0
  8053.8     .05       0  8272.1     .05       0
Bank Sta=4959.3,5033.4
XS Rating Curve= 0 ,0
Exp/Cntr=0.3,0.1

Type RM Length L Ch R = 1 ,26617   ,3388,3388,3388
BEGIN DESCRIPTION:
Mapping XS 24f024d4
END DESCRIPTION:
XS GIS Cut Line= 4
      2530942.96     13523308.28      2530644.34      13519891.6
      2528165.18      13520016.6      2526609.78     13518211.23
#Sta/Elev= 30
   600.1  191.81  2138.7  166.91  2384.3  163.74  2542.2  161.97    2882  155.56
  3489.8  155.24  3688.3  154.42    3818   154.2  4065.3  153.95  4558.2  157.96
  4840.2   157.5  4870.2  146.23  4873.2  136.33  4874.7  135.33  4947.3  136.33
  4950.3  143.61  4952.6  143.01  5020.4  140.15  5080.5  148.88  5328.2  148.13
  5454.3  148.01  5741.3  154.94  6372.1  151.51  6633.5  160.63  6866.6  158.88
    7122  157.89    7250  155.59  7413.8  161.91  7916.8  167.16  8895.1  185.02
#Mann= 20 ,-1 , 0
   600.1     .04       0  2138.7     .05       0  2384.3     .12       0
  2542.2     .05       0  3489.8     .12       0  3688.3     .05       0
    3818     .12       0  4065.3     .12       0  4558.2     .12       0
  4873.2     .05       0  4947.3     .12       0  4952.6     .05       0
  5328.2     .04       0  5454.3     .12       0  5741.3     .12       0
  6866.6     .12       0    7122     .05       0    7250     .12       0
  7413.8     .12       0  7916.8     .04       0
Bank Sta=4873.2,4947.3
XS Rating Curve= 0 ,0
Exp/Cntr=0.3,0.1

Type RM Length L Ch R = 1 ,23229   ,989,989,989
BEGIN DESCRIPTION:
Mapping XS b309d988
END DESCRIPTION:
XS GIS Cut Line= 3
      2531043.47     13523312.57      2530613.79     13519132.92
      2527085.11     13516997.48
#Sta/Elev= 30
 -2115.7  191.23 -1665.8  180.54    -306  163.65  -206.4  162.02   582.2  156.32
   681.6  155.39     781  155.75  1134.1  154.27  1277.9  154.25  1476.7  154.14
  1572.5  154.13  1749.2   154.7  2858.9  155.33  3335.2  148.98  3999.7  152.25
  4232.5  143.04  4398.9  149.18  4834.1  142.84  5031.4  135.05  5032.9  134.05
  5105.6  135.05  5118.1   139.8  5170.3  144.17  5206.3  163.09  5215.9  172.75
  5344.2  174.49  5455.1  175.37  5457.2  175.25  5607.8  177.52  6210.5  179.22
#Mann= 20 ,-1 , 0
 -2115.7     .04       0    -306     .12       0  -206.4     .05       0
   582.2    .013       0   681.6     .12       0     781     .05       0
  1134.1     .12       0  1277.9     .05       0  1476.7     .12       0
  1572.5    .013       0  1749.2     .12       0  2858.9     .12       0
  4834.1      .1       0  5031.4     .05       0  5105.6      .1       0
  5118.1     .12       0  5344.2     .05       0  5455.1     .12       0
  5457.2     .05       0  5607.8     .04       0
Bank Sta=5031.4,5105.6
XS Rating Curve= 0 ,0
Exp/Cntr=0.3,0.1

Type RM Length L Ch R = 1 ,22240   ,1812,1812,1812
BEGIN DESCRIPTION:
Mapping XS 04dec8b9
END DESCRIPTION:
XS GIS Cut Line= 4
      2532858.79     13519086.05      2530840.52     13518641.17
      2528572.73      13516829.1      2527845.77     13516405.95
#Sta/Elev= 30
    35.7  192.88   193.2  196.12   367.3  193.26   940.7  167.59  1501.9  151.02
  1524.4  143.63  1585.8  149.62  1802.1  151.65  1902.1  152.32  3376.7  156.18
  3853.6  152.67  4039.3  144.03  4458.3  149.35  4665.3  141.77  4758.1  146.17
  4899.8  142.23  4956.6  140.23  4967.4  134.18  4968.9  133.18  5041.7  134.18
  5043.2  137.56  5080.4  139.25  5251.3  141.71  5283.9  135.06  5291.9  137.31
  5349.7  171.94  5364.2  174.91  5611.4  176.28  5789.4   176.1  5846.4  176.38
#Mann= 10 ,-1 , 0
    35.7     .04       0  1501.9     .12       0  1802.1    .013       0
  1902.1     .12       0  4899.8      .1       0  4967.4     .05       0
  5041.7      .1       0  5251.3     .12       0  5611.4     .05       0
  5789.4     .12       0
Bank Sta=4967.4,5041.7
XS Rating Curve= 0 ,0
Exp/Cntr=0.3,0.1

Type RM Length L Ch R = 1 ,20428   ,2247,2247,2247
BEGIN DESCRIPTION:
Mapping XS 70dd6b9c
END DESCRIPTION:
XS GIS Cut Line= 4
      2533401.27     13518402.44       2530471.6     13516883.35
      2530015.87     13516091.25      2528941.63      13515396.8
#Sta/Elev= 30
   815.5  206.45  1012.4  204.63  1358.6  189.47  2122.7  162.66    2204  158.66
  2359.7  151.16  2450.2  148.53  2523.5  140.41  2551.3  142.68  2559.4  143.14
    2760  153.54  3910.1  151.74  3978.5  152.13  4126.3  151.01  4241.9   147.8
  4617.8  149.06  4799.1  143.86  4837.7   143.8  4859.3  136.06    4924  140.15
  4967.4  133.61  5054.3  133.27  5055.8  132.27  5128.6  133.27  5272.9  139.96
  5399.4  137.13  5433.2   141.1    5483  162.18  5526.9  165.11  6308.6  173.04
#Mann= 16 ,-1 , 0
   815.5     .04       0  1358.6     .12       0  2122.7     .05       0
    2204     .12       0  2359.7     .05       0  2450.2     .12       0
  2551.3    .013       0  2559.4     .12       0  3910.1     .05       0
  3978.5     .12       0  4126.3     .05       0  4241.9     .12       0
  4799.1      .1       0  5054.3     .05       0  5128.6      .1       0
  5399.4     .12       0
Bank Sta=5054.3,5128.6
XS Rating Curve= 0 ,0
Exp/Cntr=0.3,0.1

Type RM Length L Ch R = 1 ,18181   ,1159,1159,1159
BEGIN DESCRIPTION:
Mapping XS 0da2437e
END DESCRIPTION:
XS GIS Cut Line= 3
       2533097.5     13515678.94      2531578.37     13514919.38
      2528919.93      13515201.5
#Sta/Elev= 30
  3339.9  206.95  3644.6  205.26  4036.1  191.23  4595.1  162.01    4774  145.31
  4807.3  147.45  4835.5  140.15  4850.7  139.63  4874.4  141.85  4924.9  131.94
  4969.6  132.99  4976.6  129.34  4978.1  128.34  5052.2  129.34    5082  131.33
  5145.2  141.12  5181.2  141.83  5280.3  139.32  5351.2  138.87  5426.1   138.4
  5574.7  143.11  5806.7  138.52  5926.7  142.03  5966.9  145.98    6882  154.76
  7254.1  168.43  7345.5  169.51  7404.1  169.88  7595.6   170.2  7711.7  169.77
#Mann= 12 ,-1 , 0
  3339.9     .12       0  4850.7      .1       0  4976.6     .05       0
  5052.2      .1       0    5082     .05       0  5145.2      .1       0
  5181.2     .12       0  5280.3     .05       0  5351.2     .12       0
  7345.5     .05       0  7404.1     .12       0  7595.6     .05       0
Bank Sta=4976.6,5052.2
XS Rating Curve= 0 ,0
Exp/Cntr=0.3,0.1

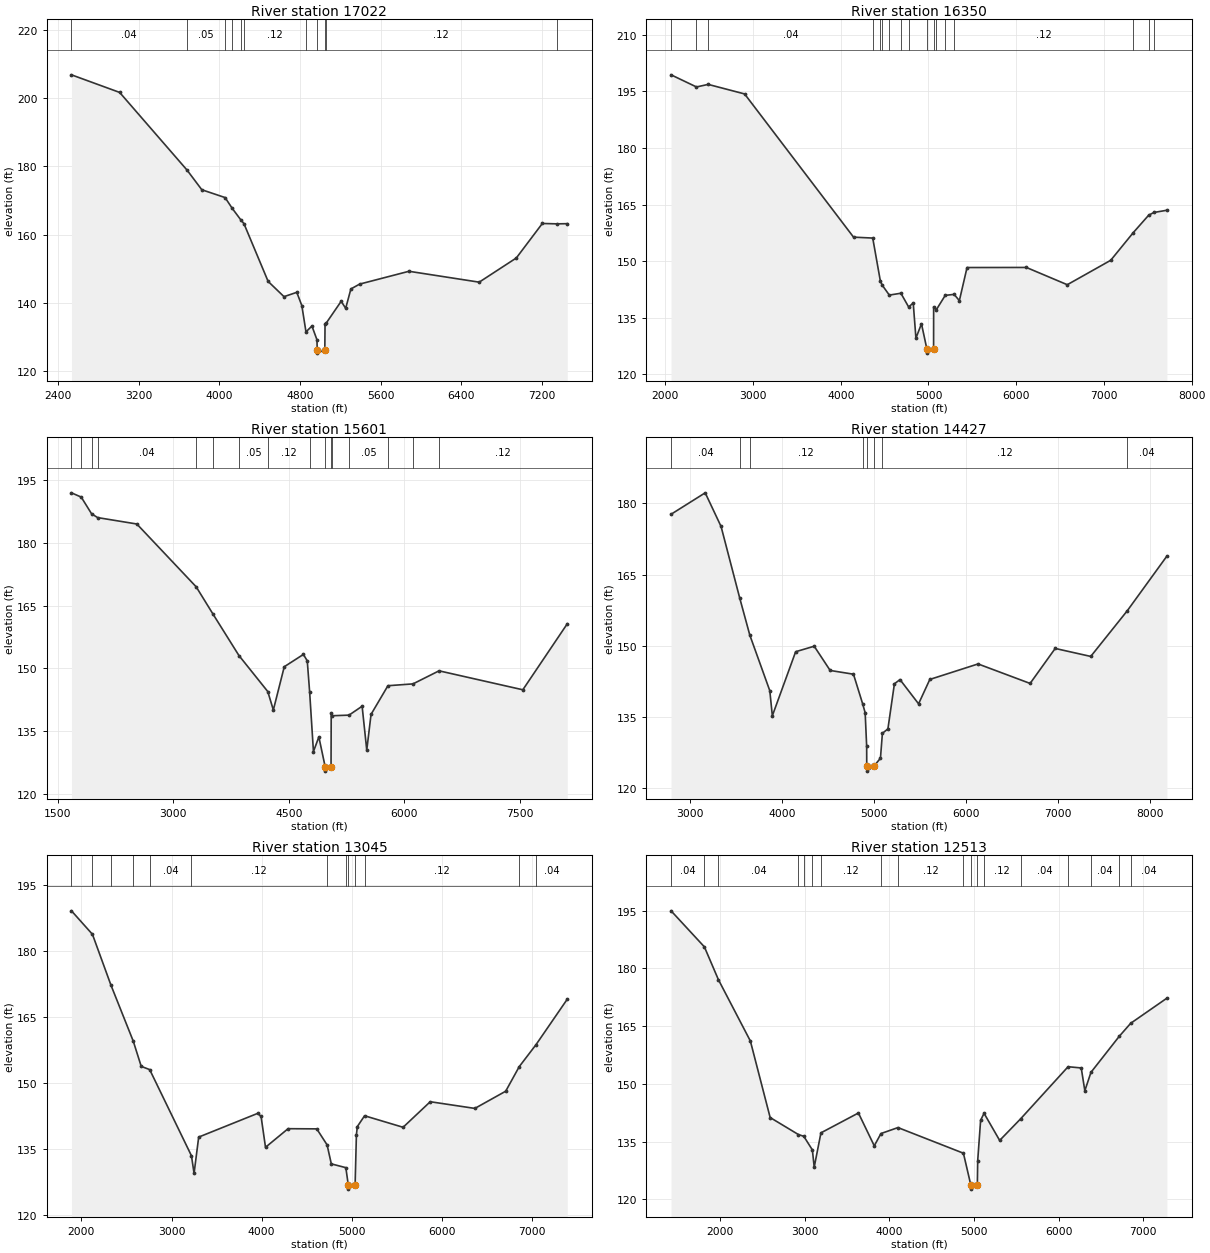
Type RM Length L Ch R = 1 ,17022   ,672,672,672
BEGIN DESCRIPTION:
Mapping XS a3c77619
END DESCRIPTION:
XS GIS Cut Line= 4
       2533748.5     13514658.96      2531719.43     13513888.56
       2531176.9     13513877.71      2529169.75     13514789.06
#Sta/Elev= 30
    2535  206.86  3012.9   201.7  3680.6  178.95  3827.8  173.16  4058.4  170.87
  4130.3  167.67  4213.2  164.38  4245.5  163.23  4485.5  146.28  4642.8  141.81
  4769.8  143.08  4819.9  139.17  4860.8  131.48  4919.9   133.2  4969.9  129.15
  4972.1  126.25  4973.6  125.25  5047.7  126.25  5049.9  133.82  5059.5  133.97
  5209.9  140.45  5254.6  138.39  5306.2  144.07  5392.9  145.49    5882  149.25
  6578.7  146.06  6946.8  153.15    7205  163.27  7347.6  163.16  7452.4  163.21
#Mann= 11 ,-1 , 0
    2535     .04       0  3680.6     .05       0  4058.4     .04       0
  4130.3     .05       0  4213.2     .04       0  4245.5     .12       0
  4860.8      .1       0  4972.1     .05       0  5047.7      .1       0
  5059.5     .12       0  7347.6     .05       0
Bank Sta=4972.1,5047.7
XS Rating Curve= 0 ,0
Exp/Cntr=0.3,0.1

Type RM Length L Ch R = 1 ,16350   ,749,749,749
BEGIN DESCRIPTION:
Mapping XS e70aa250
END DESCRIPTION:
XS GIS Cut Line= 4
      2533932.94     13514420.23      2531838.79     13513129.01
      2530916.48     13513324.33      2529082.72      13514626.4
#Sta/Elev= 30
  2065.7  199.41  2355.4  196.19  2488.7  196.87  2903.9  194.34  4145.8  156.34
  4364.5   156.1  4451.3  144.72  4473.1  143.59  4553.4  140.97  4685.5  141.46
  4773.5  137.83  4826.2  138.85  4856.9  129.54  4920.1  133.36  4982.6  126.57
  4984.1  125.57  5058.2  126.57  5058.9  137.87  5089.8   137.1  5190.9  140.89
    5292  141.16    5352   139.5  5439.5  148.28    6116   148.3  6582.2  143.72
  7077.2   150.2  7335.4  157.57  7510.1  162.17  7569.6  162.89  7717.7  163.48
#Mann= 17 ,-1 , 0
  2065.7     .04       0  2355.4    .013       0  2488.7     .04       0
  4364.5     .05       0  4451.3     .04       0  4473.1     .05       0
  4553.4     .12       0  4685.5     .05       0  4773.5      .1       0
  4982.6     .05       0  5058.2      .1       0  5089.8     .04       0
  5190.9      .1       0    5292     .12       0  7335.4     .05       0
  7510.1     .12       0  7569.6     .05       0
Bank Sta=4982.6,5058.2
XS Rating Curve= 0 ,0
Exp/Cntr=0.3,0.1

Type RM Length L Ch R = 1 ,15601   ,1174,1174,1174
BEGIN DESCRIPTION:
Mapping XS 52c723c1
END DESCRIPTION:
XS GIS Cut Line= 3
      2534117.43     13514170.68      2531827.94     13512445.42
      2528269.41      13512705.8
#Sta/Elev= 30
  1679.1  191.98  1805.9  190.96  1940.6  186.96  2019.3  186.06  2527.5  184.53
    3298  169.51  3515.7  163.01  3852.5   153.1  4226.8  144.49  4299.1  140.08
  4440.8  150.42  4689.2  153.36  4739.3  151.83  4770.3  144.35  4819.5  130.14
  4889.7  133.65  4972.2  126.47  4973.7  125.47  5047.8  126.47  5050.1  139.26
  5066.7  138.71  5281.1  138.85  5451.2  140.98  5511.4   130.5  5567.2  139.04
  5786.1  145.88  6111.5  146.32  6449.7  149.44  7536.8  144.91  8113.9  160.69
#Mann= 16 ,-1 , 0
  1679.1     .05       0  1805.9     .12       0  1940.6    .013       0
  2019.3     .04       0    3298     .05       0  3515.7     .04       0
  3852.5     .05       0  4226.8     .12       0  4770.3      .1       0
  4972.2     .05       0  5047.8      .1       0  5066.7     .12       0
  5281.1     .05       0  5786.1     .04       0  6111.5     .05       0
  6449.7     .12       0
Bank Sta=4972.2,5047.8
XS Rating Curve= 0 ,0
Exp/Cntr=0.3,0.1

Type RM Length L Ch R = 1 ,14427   ,1382,1382,1382
BEGIN DESCRIPTION:
Mapping XS dfb425b9
END DESCRIPTION:
XS GIS Cut Line= 3
      2533271.08     13511034.83       2531176.9     13511382.05
      2527943.36     13511848.64
#Sta/Elev= 30
  2793.7  177.68  3164.8  182.19  3337.1  175.12  3539.7  160.08  3649.6  152.26
  3866.9  140.56  3894.6  135.28    4148  148.76  4349.7  149.92  4523.1  144.82
  4776.5  144.03  4876.5  137.79  4903.6  135.92    4920  128.84  4920.7  124.64
  4922.2  123.64  4996.9  124.64  5069.9  126.36  5090.9   131.6  5150.8  132.52
  5221.5  142.01  5282.1   142.9  5484.2   137.8  5606.4  142.93  6130.8  146.19
  6696.6  142.09  6969.4  149.45  7355.6  147.77  7753.6   157.4  8183.5  168.88
#Mann= 8 ,-1 , 0
  2793.7     .04       0  3539.7     .03       0  3649.6     .12       0
  4876.5      .1       0  4920.7     .05       0  4996.9      .1       0
  5090.9     .12       0  7753.6     .04       0
Bank Sta=4920.7,4996.9
XS Rating Curve= 0 ,0
Exp/Cntr=0.3,0.1

Type RM Length L Ch R = 1 ,13045   ,532,532,532
BEGIN DESCRIPTION:
Mapping XS 646b1173
END DESCRIPTION:
XS GIS Cut Line= 3
      2533455.55     13510683.27      2530834.01     13510119.03
      2528143.04     13510969.72
#Sta/Elev= 30
  1889.3  189.16  2122.2  183.82  2328.3  172.23  2575.7  159.51  2663.7   153.8
  2757.7  153.06  3221.2  133.48  3250.3  129.47  3301.5  137.72  3956.1  143.11
  3993.9  142.43  4043.3   135.4  4293.7  139.63  4612.1  139.59  4726.8  135.95
  4773.7  131.63  4934.9  130.77  4961.7  126.89  4963.2  125.89  5037.9  126.89
  5052.3  138.28  5062.8  140.12  5142.9  142.57  5570.4  139.95  5871.8  145.76
    6367  144.24  6709.3  148.15  6859.4  153.73  7046.5  158.75  7393.1  169.08
#Mann= 13 ,-1 , 0
  1889.3     .04       0  2122.2    .013       0  2328.3     .04       0
  2575.7     .12       0  2757.7     .04       0  3221.2     .12       0
  4726.8     .05       0  4934.9      .1       0  4961.7     .05       0
  5037.9      .1       0  5142.9     .12       0  6859.4     .05       0
  7046.5     .04       0
Bank Sta=4961.7,5037.9
XS Rating Curve= 0 ,0
Exp/Cntr=0.3,0.1

Type RM Length L Ch R = 1 ,12513   ,973,973,973
BEGIN DESCRIPTION:
Mapping XS 1f1d4657
END DESCRIPTION:
XS GIS Cut Line= 3
      2533672.51     13510509.64       2530660.4     13509676.32
      2528004.19     13510301.31
#Sta/Elev= 30
  1424.1  194.97  1817.4  185.61  1983.4  177.07  2360.4  161.15    2594  141.27
  2926.8  136.86  2991.2  136.39  3092.4  132.86  3114.2  128.38  3193.6  137.29
  3636.1  142.45  3823.2  133.92  3902.2  137.11    4103  138.66  4875.7     132
  4963.8  123.67  4965.3  122.67    5040  123.67  5044.3  130.02  5078.8  140.56
  5119.4  142.37  5303.7  135.32  5551.9  140.95  6111.5  154.47  6266.8  154.15
  6309.2  148.23  6381.5  153.01  6716.6   162.4  6851.1  165.76  7278.1  172.28
#Mann= 18 ,-1 , 0
  1424.1     .04       0  1817.4    .013       0  1983.4     .04       0
  2926.8     .05       0  2991.2     .12       0  3092.4     .05       0
  3193.6     .12       0  3902.2     .05       0    4103     .12       0
  4875.7      .1       0  4963.8     .05       0    5040      .1       0
  5119.4     .12       0  5551.9     .04       0  6111.5     .12       0
  6381.5     .04       0  6716.6     .05       0  6851.1     .04       0
Bank Sta=4963.8,5040
XS Rating Curve= 0 ,0
Exp/Cntr=0.3,0.1

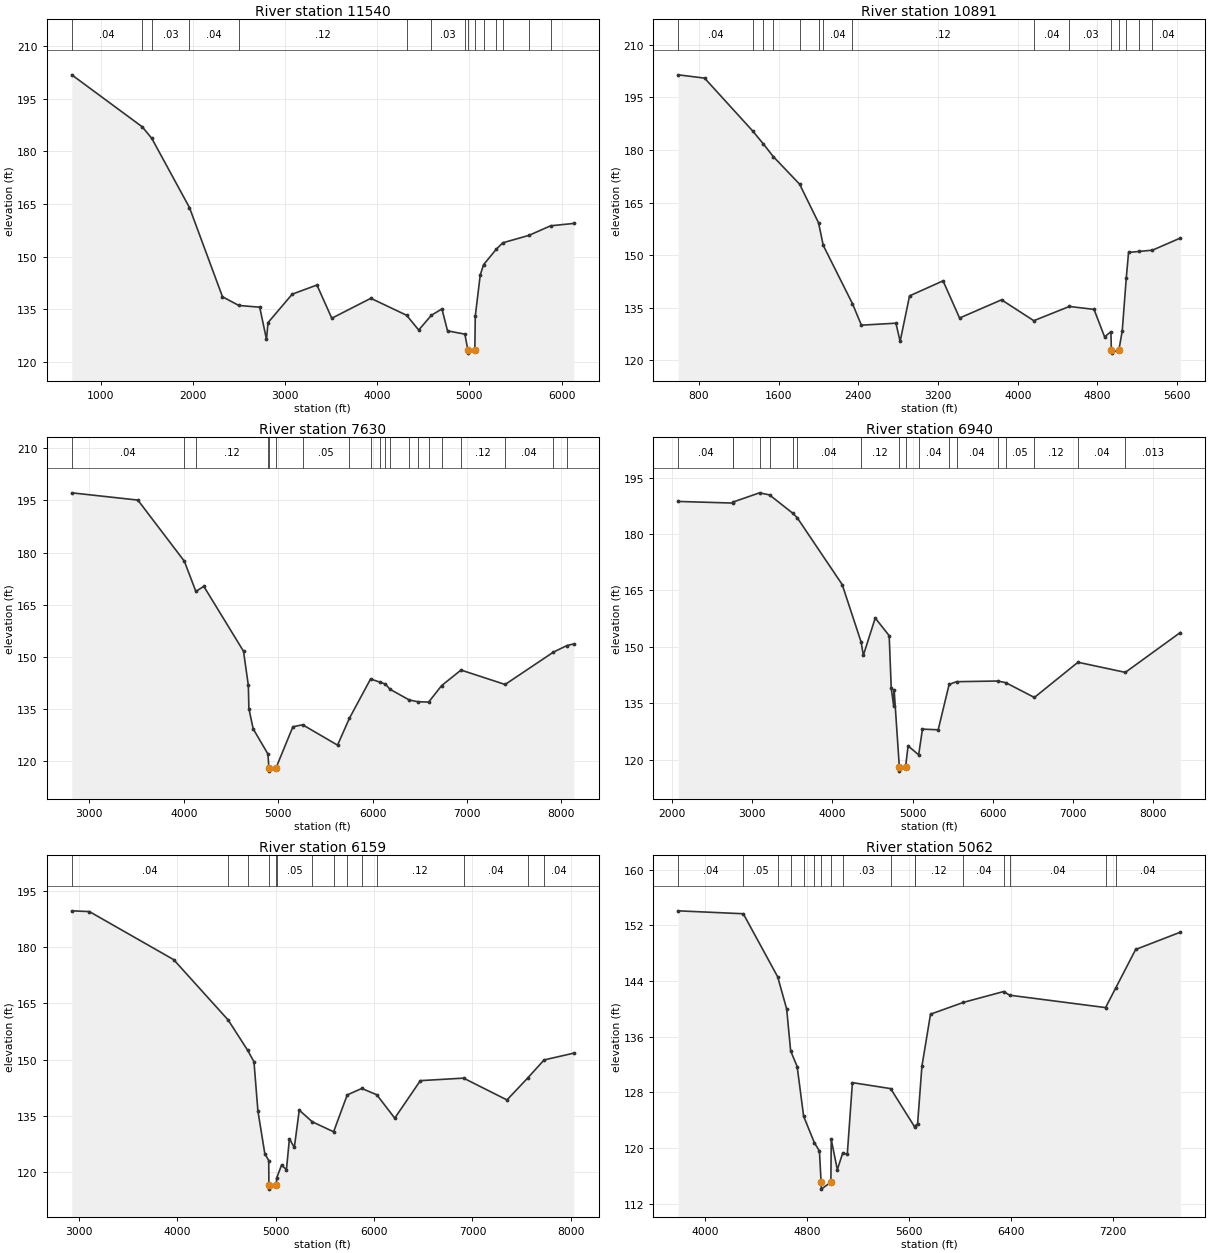
Type RM Length L Ch R = 1 ,11540   ,649,649,649
BEGIN DESCRIPTION:
Mapping XS 0cd95690
END DESCRIPTION:
XS GIS Cut Line= 3
      2534167.36     13510396.81      2530764.57     13509311.74
      2529019.89     13508626.02
#Sta/Elev= 30
   687.4  201.76  1452.7  186.93    1555  183.67  1964.1  163.95  2322.4  138.53
  2498.5  136.07  2726.1  135.56  2799.6   126.4  2815.9  131.16  3078.8  139.28
  3346.9  141.88  3507.9  132.42  3931.7   138.1  4319.7  133.26  4450.8  129.06
  4587.8  133.26  4702.8  135.08  4763.5  128.82  4951.7  127.89  4983.2  123.48
  4984.7  122.48  5059.6  123.48  5064.4  133.03  5118.1  144.71  5153.6  147.65
  5290.6  152.04  5362.6  153.91    5646  156.02  5881.3  158.75  6133.6  159.43
#Mann= 15 ,-1 , 0
   687.4     .04       0  1452.7    .013       0    1555     .03       0
  1964.1     .04       0  2498.5     .12       0  4319.7     .04       0
  4587.8     .03       0  4951.7      .1       0  4983.2     .05       0
  5059.6      .1       0  5153.6     .12       0  5290.6    .013       0
  5362.6     .05       0    5646     .04       0  5881.3     .05       0
Bank Sta=4983.2,5059.6
XS Rating Curve= 0 ,0
Exp/Cntr=0.3,0.1

Type RM Length L Ch R = 1 ,10891   ,3261,3261,3261
BEGIN DESCRIPTION:
Mapping XS b6c7eb97
END DESCRIPTION:
XS GIS Cut Line= 3
      2534254.16     13510240.56      2530955.54     13509172.85
      2529896.64      13508009.8
#Sta/Elev= 30
   592.1  201.47   856.5  200.53  1341.8  185.37  1444.2  181.82  1546.6  178.12
  1810.3  170.26  2000.3  159.24    2048  152.77  2340.9  136.15  2430.6     130
  2777.5  130.57  2819.5  125.38  2914.1  138.36  3250.5  142.66  3416.2  132.04
  3837.5  137.24  4161.3  131.28  4518.2  135.34  4765.9  134.51    4872  126.67
  4935.5  128.13  4939.9  123.02  4941.4  122.02  5016.3  123.02  5049.1  128.37
  5089.9  143.55  5112.6  150.77  5217.1  151.05  5352.2  151.41  5632.1  154.87
#Mann= 15 ,-1 , 0
   592.1     .04       0  1341.8    .013       0  1444.2     .03       0
  1546.6     .12       0  1810.3     .05       0  2000.3     .03       0
    2048     .04       0  2340.9     .12       0  4161.3     .04       0
  4518.2     .03       0  4939.9     .05       0  5016.3     .03       0
  5089.9     .04       0  5217.1    .013       0  5352.2     .04       0
Bank Sta=4939.9,5016.3
XS Rating Curve= 0 ,0
Exp/Cntr=0.3,0.1

Type RM Length L Ch R = 1 ,7630    ,690,690,690
BEGIN DESCRIPTION:
Mapping XS 48e94542
END DESCRIPTION:
XS GIS Cut Line= 5
       2534722.9     13510197.15      2533759.36     13509268.34
      2532110.06     13508487.09      2531215.96     13508191.95
      2530035.45     13507914.18
#Sta/Elev= 30
  2814.3  197.19  3514.5   195.1  4006.9  177.51  4128.7  168.83  4212.8   170.3
  4633.2  151.63  4684.5  141.79  4690.1  135.14  4735.5  129.32  4892.1  122.06
  4901.9  118.15  4903.4  117.15  4978.6  118.15    5156   129.9  5259.9  130.48
  5629.1  124.63  5754.3  132.32  5978.8  143.65  6081.4  142.71    6136   142.2
    6184  140.71  6389.2  137.61  6479.9  137.11  6594.3  137.01  6731.1  141.74
  6936.9  146.22  7404.1  142.07  7915.5  151.38  8059.9  153.28  8131.9  153.73
#Mann= 20 ,-1 , 0
  2814.3     .04       0  4006.9    .013       0  4128.7     .12       0
  4892.1      .1       0  4901.9     .05       0  4978.6      .1       0
  5259.9     .05       0  5754.3     .04       0  5978.8     .05       0
  6081.4     .04       0    6136     .05       0    6184     .04       0
  6389.2     .12       0  6479.9     .03       0  6594.3     .12       0
  6731.1     .03       0  6936.9     .12       0  7404.1     .04       0
  7915.5    .013       0  8059.9     .04       0
Bank Sta=4901.9,4978.6
XS Rating Curve= 0 ,0
Exp/Cntr=0.3,0.1

Type RM Length L Ch R = 1 ,6940    ,781,781,781
BEGIN DESCRIPTION:
Mapping XS bd088a6a
END DESCRIPTION:
XS GIS Cut Line= 5
      2535521.51     13510066.94      2533880.89     13508721.46
      2532327.07     13508165.91      2531320.12     13507931.53
      2529873.63     13507749.49
#Sta/Elev= 30
  2075.6  188.67  2754.5  188.24  2763.6  188.54    3090  190.96  3214.3  190.41
  3503.4  185.55  3559.4  184.36  4120.9  166.58  4357.8  151.24  4384.7  147.74
  4533.3  157.67  4707.4  152.97  4732.8  139.07  4763.6  134.24  4768.9  138.61
  4834.3  117.96  4835.8  116.96    4911  117.96    4943  123.68  5075.1  121.29
  5122.4  128.13  5318.7  127.95  5455.2  140.02  5547.3  140.74  6060.9  140.92
  6161.2  140.49  6518.8  136.55  7062.5  145.91  7653.4  143.22  8339.3  153.82
#Mann= 18 ,-1 , 0
  2075.6     .04       0  2754.5     .05       0  2763.6     .04       0
    3090    .013       0  3214.3     .04       0  3503.4     .03       0
  3559.4     .04       0  4357.8     .12       0  4834.3     .05       0
    4911     .12       0  5075.1     .04       0  5455.2     .05       0
  5547.3     .04       0  6060.9     .12       0  6161.2     .05       0
  6518.8     .12       0  7062.5     .04       0  7653.4    .013       0
Bank Sta=4834.3,4911
XS Rating Curve= 0 ,0
Exp/Cntr=0.3,0.1

Type RM Length L Ch R = 1 ,6159    ,1097,1097,1097
BEGIN DESCRIPTION:
Mapping XS 908b7d53
END DESCRIPTION:
XS GIS Cut Line= 3
       2534827.1     13508591.27      2533533.67     13507714.52
      2529995.73     13507627.35
#Sta/Elev= 30
  2928.5  189.62  3107.6  189.42  3964.2  176.61  4517.8  160.53  4714.3  152.53
  4779.8  149.41  4819.9  136.31  4889.9  124.94  4929.9   123.1  4931.5  116.48
    4933  115.48  5008.2  116.48  5009.2  118.36  5059.9  121.87  5109.9  120.68
  5139.9  128.88    5190  126.58    5240  136.52  5372.1  133.42  5589.1  130.76
  5727.4  140.58  5875.6   142.3    6028  140.61  6210.3  134.39  6470.4  144.38
  6909.5  145.05  7350.6  139.24  7564.3  145.17  7727.8   149.9  8030.1  151.71
#Mann= 14 ,-1 , 0
  2928.5     .04       0  4517.8     .05       0  4714.3     .12       0
  4931.5     .05       0  5008.2     .12       0  5009.2     .05       0
  5372.1     .04       0  5589.1     .05       0  5727.4     .04       0
  5875.6     .05       0    6028     .12       0  6909.5     .04       0
  7564.3    .013       0  7727.8     .04       0
Bank Sta=4931.5,5008.2
XS Rating Curve= 0 ,0
Exp/Cntr=0.3,0.1

Type RM Length L Ch R = 1 ,5062    ,955,955,955
BEGIN DESCRIPTION:
Mapping XS 9ee9f128
END DESCRIPTION:
XS GIS Cut Line= 3
      2533802.72     13506525.29      2532648.25     13506803.06
      2529997.53     13507550.51
#Sta/Elev= 30
  3789.6  154.09  4300.4  153.67  4570.3  144.61  4640.9  139.98  4672.1  133.97
  4723.2  131.72    4774  124.58  4858.2  120.78  4898.1  119.58  4911.1  115.11
  4912.6  114.11  4987.9  115.11  4990.8  121.24  5038.5  116.91  5080.5  119.28
  5116.9  119.15    5157  129.41    5457  128.55  5645.6  123.05  5647.8  123.16
  5668.6  123.48  5702.6  131.76    5770  139.24  6028.6  140.94  6345.1   142.5
    6391  141.97  7144.3  140.19  7225.2  143.05  7380.5  148.54  7731.1  151.02
#Mann= 17 ,-1 , 0
  3789.6     .04       0  4300.4     .05       0  4570.3     .12       0
  4672.1     .05       0    4774     .12       0  4858.2      .1       0
  4911.1     .05       0  4987.9      .1       0  5080.5     .03       0
    5457     .12       0  5645.6     .05       0  5647.8     .12       0
  6028.6     .04       0  6345.1     .12       0    6391     .04       0
  7144.3    .013       0  7225.2     .04       0
Bank Sta=4911.1,4987.9
XS Rating Curve= 0 ,0
Exp/Cntr=0.3,0.1

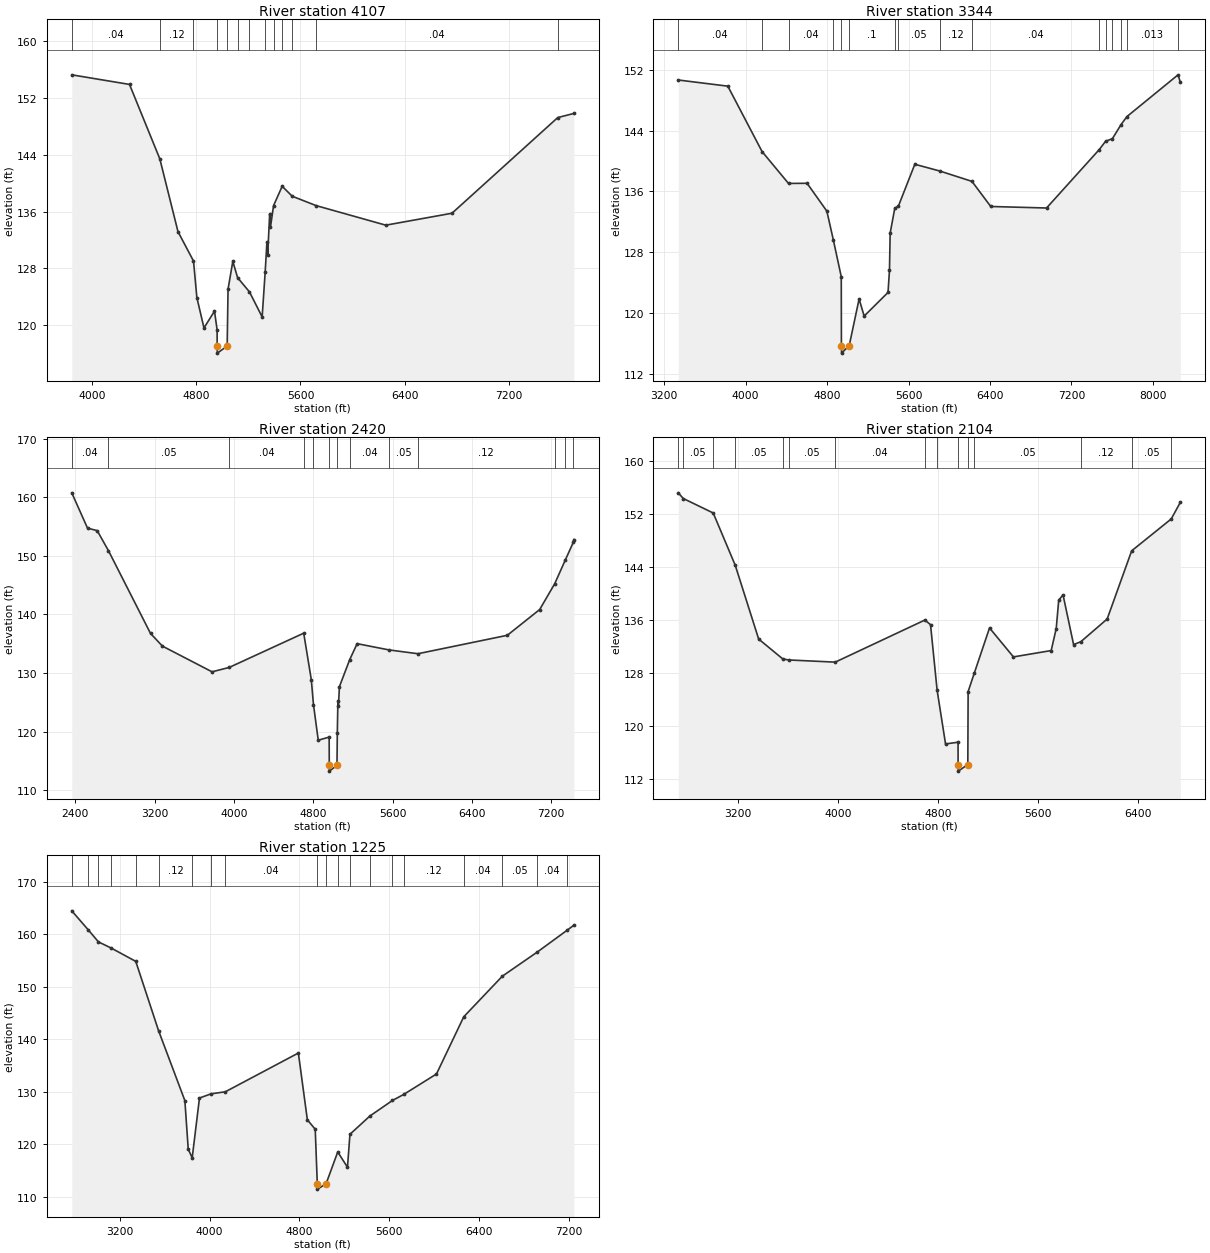
Type RM Length L Ch R = 1 ,4107    ,763,763,763
BEGIN DESCRIPTION:
Mapping XS 199d57b9
END DESCRIPTION:
XS GIS Cut Line= 3
      2533299.28     13505900.28      2532153.46     13506056.53
      2529873.57     13507489.96
#Sta/Elev= 30
  3846.4  155.22  4289.1  153.87  4521.4  143.41  4660.8  133.17  4779.7  129.04
  4805.5  123.91    4860  119.63  4940.7  121.99  4960.9  119.35  4961.1  117.09
  4962.6  116.09  5037.9  117.09  5044.6  125.08  5081.1  128.98  5118.2  126.69
  5208.9   124.7  5306.1  121.18  5329.1  127.43  5342.6  131.68  5348.5   129.9
  5363.8  135.66  5369.7  133.78  5393.6  136.83  5459.6  139.55  5536.6  138.15
  5720.2  136.83  6254.2  134.08  6761.8  135.76  7572.5  149.21  7695.9  149.79
#Mann= 13 ,-1 , 0
  3846.4     .04       0  4521.4     .12       0  4779.7      .1       0
  4961.1     .05       0  5037.9      .1       0  5118.2     .12       0
  5208.9      .1       0  5329.1     .05       0  5393.6     .12       0
  5459.6     .05       0  5536.6     .12       0  5720.2     .04       0
  7572.5    .013       0
Bank Sta=4961.1,5037.9
XS Rating Curve= 0 ,0
Exp/Cntr=0.3,0.1

Type RM Length L Ch R = 1 ,3344    ,924,924,924
BEGIN DESCRIPTION:
Mapping XS a9551748
END DESCRIPTION:
XS GIS Cut Line= 5
      2533629.29     13505749.47      2532556.76     13505295.23
      2532092.69     13505362.09      2531467.69     13506117.29
      2529659.91     13507566.24
#Sta/Elev= 30
  3338.1  150.65    3825  149.84  4161.5  141.24    4421  137.05  4603.5  137.07
  4797.6  133.41  4861.5  129.61  4939.1  124.79  4940.6  115.74  4942.1  114.74
  5017.4  115.74  5114.4  121.86  5163.9  119.61  5398.4  122.72  5412.7  125.63
  5419.2  130.51  5464.6  133.77  5500.8  134.09  5661.5  139.57  5907.4  138.68
  6222.8  137.32  6407.2  134.02  6955.1  133.82  7473.2  141.51  7534.7  142.59
  7602.1  142.94    7687  144.79  7744.5  145.84  8246.6  151.33  8268.8  150.37
#Mann= 16 ,-1 , 0
  3338.1     .04       0  4161.5     .05       0    4421     .04       0
  4861.5      .1       0  4940.6     .05       0  5017.4      .1       0
  5464.6     .12       0  5500.8     .05       0  5907.4     .12       0
  6222.8     .04       0  7473.2    .013       0  7534.7     .04       0
  7602.1    .013       0    7687     .04       0  7744.5    .013       0
  8246.6     .04       0
Bank Sta=4940.6,5017.4
XS Rating Curve= 0 ,0
Exp/Cntr=0.3,0.1

Type RM Length L Ch R = 1 ,2420    ,316,316,316
BEGIN DESCRIPTION:
Mapping XS 0185b348
END DESCRIPTION:
XS GIS Cut Line= 4
      2534438.48     13504314.37      2533842.69     13504472.23
      2531814.92     13504546.11      2529558.99     13505413.78
#Sta/Elev= 30
  2364.6  160.78  2523.4  154.75  2621.2  154.32  2734.2  150.91  3158.8  136.76
  3278.8   134.6  3779.2  130.21  3951.9  130.96  4703.3  136.81  4779.8  128.88
  4801.8   124.6  4849.9  118.53  4959.9  119.06  4961.1  114.25  4962.6  113.25
  5038.8  114.25  5042.1  119.78  5048.1   125.3  5053.5  124.42  5063.5  127.68
  5167.1  132.29    5242  135.02  5563.5  133.95  5854.9   133.3  6756.4  136.45
  7082.7  140.85    7234  145.25  7340.4  149.28  7422.6  152.37  7427.1   152.8
#Mann= 13 ,-1 , 0
  2364.6     .04       0  2734.2     .05       0  3951.9     .04       0
  4703.3     .05       0  4801.8      .1       0  4961.1     .05       0
  5038.8      .1       0  5167.1     .04       0  5563.5     .05       0
  5854.9     .12       0    7234     .05       0  7340.4     .12       0
  7422.6     .05       0
Bank Sta=4961.1,5038.8
XS Rating Curve= 0 ,0
Exp/Cntr=0.3,0.1

Type RM Length L Ch R = 1 ,2104    ,879,879,879
BEGIN DESCRIPTION:
Mapping XS 96646631
END DESCRIPTION:
XS GIS Cut Line= 3
      2534099.67     13504105.14      2531851.37     13504226.67
      2530098.98      13504426.2
#Sta/Elev= 30
  2721.5  155.22  2762.1  154.36  3001.3  152.17  3177.3  144.27  3364.7  133.11
    3558   130.1  3603.8  129.95    3977  129.62  4693.5  135.98  4739.1  135.29
  4792.1  125.34  4859.3  117.25  4959.4  117.51  4959.7  114.14  4961.2  113.14
  5037.4  114.14  5039.9  125.17  5088.7  127.93    5211  134.79  5402.2  130.41
  5704.2  131.37  5744.4   134.7  5764.5     139  5798.9  139.79  5883.4  132.27
  5941.2  132.71  6151.8  136.14  6347.7  146.45  6664.2  151.27  6736.8  153.78
#Mann= 15 ,-1 , 0
  2721.5     .04       0  2762.1     .05       0  3001.3     .12       0
  3177.3     .05       0    3558     .12       0  3603.8     .05       0
    3977     .04       0  4693.5     .05       0  4792.1      .1       0
  4959.7     .05       0  5037.4      .1       0  5088.7     .05       0
  5941.2     .12       0  6347.7     .05       0  6664.2    .075       0
Bank Sta=4959.7,5037.4
XS Rating Curve= 0 ,0
Exp/Cntr=0.3,0.1

Type RM Length L Ch R = 1 ,1225    ,0,0,0
BEGIN DESCRIPTION:
TWELVEMILE CREEK 1.0
END DESCRIPTION:
XS GIS Cut Line= 4
      2534316.35     13503841.09      2533766.23      13503523.4
      2532175.49     13503500.04      2529968.81     13503896.61
#Sta/Elev= 30
  2773.8  164.47  2920.7  160.84  3011.5  158.55  3123.2   157.4  3343.2  154.85
  3546.3  141.65  3780.3  128.34  3810.3   119.1  3845.5  117.45  3910.3  128.83
  4012.9  129.63  4140.4  130.02  4790.4   137.4  4870.4  124.68  4940.5  122.89
  4958.8  112.49  4960.3  111.49  5036.6  112.49  5140.8  118.56  5227.5  115.66
  5249.4  121.93    5427  125.41  5627.8  128.37  5728.2  129.52  6019.5  133.41
  6262.3   144.3  6605.8  152.03  6917.8  156.64  7182.6  160.78    7242  161.73
#Mann= 20 ,-1 , 0
  2773.8     .05       0  2920.7     .12       0  3011.5     .05       0
  3123.2     .12       0  3343.2     .04       0  3546.3     .12       0
  3845.5     .05       0  4012.9     .05       0  4140.4     .04       0
  4958.8     .05       0  5036.6     .05       0  5140.8     .05       0
  5249.4      .1       0    5427     .12       0  5627.8      .1       0
  5728.2     .12       0  6262.3     .04       0  6605.8     .05       0
  6917.8     .04       0  7182.6    .075       0
Bank Sta=4958.8,5036.6
XS Rating Curve= 0 ,0
Exp/Cntr=0.3,0.1

Chan Stop Cuts=-1
Use User Specified Reach Order=0
Composite Channel Slope=5