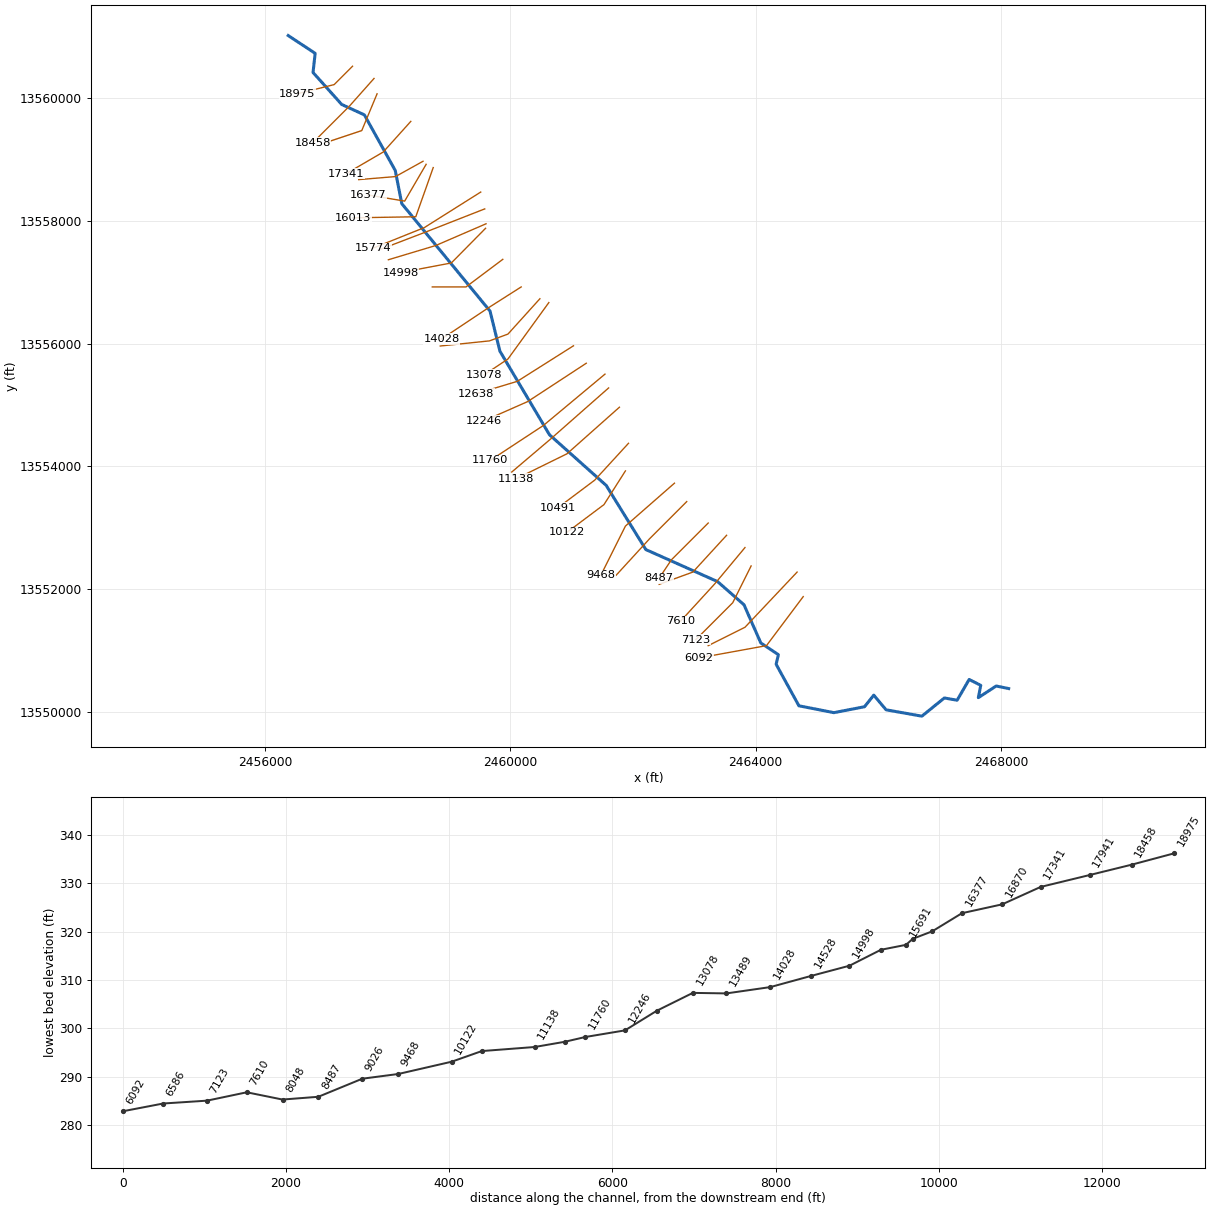
--- WOODS CREEK.prj (project) ---

Proj Title=WOODS CREEK Base Level Engineering
Current Plan=p01
Default Exp/Contr=0.3,0.1
English Units
Geom File=g01
Flow File=f01
Plan File=p01
BEGIN DESCRIPTION:
WOODS CREEK
END DESCRIPTION:

--- WOODS CREEK.p01 (plan) ---

Plan Title=Multiple Run
Short Identifier=Multiple
Geom File=g01
Flow File=f01
Subcritical Flow
K Sum by GR= 0
Std Step Tol= 0.01
Critical Tol= 0.01
Num of Std Step Trials= 20
Max Error Tol= 0.3
Flow Tol Ratio= 0.001
Split Flow NTrial= 30
Split Flow Tol= 0.02
Split Flow Ratio= 0.02
Log Output Level= 0
Friction Slope Method= 1
Unsteady Friction Slope Method= 2
Unsteady Bridges Friction Slope Method= 1
Parabolic Critical Depth
Global Vel Dist=  1 , 1 , 1
Global Log Level= 0
CheckData=True
Encroach Param= -1, 0, 0, 0
BEGIN DESCRIPTION:
Multiple Run
END DESCRIPTION:

--- WOODS CREEK.f01 (steady flow) ---

Flow Title=Multiple
Number of Profiles=7
Profile Names=10-year,25-year,50-year,1pct_min,100-year,1pct_plu,500-year
River Rch & RM= WOODS CREEK,Reach-1,18975
     601     968    1300     846    1688    3367    2817
River Rch & RM= WOODS CREEK,Reach-1,16013
     819    1345    1828    1203    2400    4789    4098
River Rch & RM= WOODS CREEK,Reach-1,14028
     992    1645    2251    1489    2971    5929    5136
River Rch & RM= WOODS CREEK,Reach-1,12246
    1146    1914    2629    1746    3483    6950    6063
River Rch & RM= WOODS CREEK,Reach-1,9468
    1223    2042    2806    1863    3716    7415    6465
River Rch & RM= WOODS CREEK,Reach-1,5592
    1503    2527    3487    2321    4631    9239    8093
River Rch & RM= WOODS CREEK,Reach-1,2153
    1555    2619    3618    2411    4811    9599    8427
Boundary for River Rch & Prof#=WOODS CREEK,Reach-1,1
Up Type=0
Dn Type=3
Dn Slope=0.005
Boundary for River Rch & Prof#=WOODS CREEK,Reach-1,2
Up Type=0
Dn Type=3
Dn Slope=0.005
Boundary for River Rch & Prof#=WOODS CREEK,Reach-1,3
Up Type=0
Dn Type=3
Dn Slope=0.005
Boundary for River Rch & Prof#=WOODS CREEK,Reach-1,4
Up Type=0
Dn Type=3
Dn Slope=0.005
Boundary for River Rch & Prof#=WOODS CREEK,Reach-1,5
Up Type=0
Dn Type=3
Dn Slope=0.005
Boundary for River Rch & Prof#=WOODS CREEK,Reach-1,6
Up Type=0
Dn Type=3
Dn Slope=0.005
Boundary for River Rch & Prof#=WOODS CREEK,Reach-1,7
Up Type=0
Dn Type=3
Dn Slope=0.005

--- WOODS CREEK.g01 (geometry) ---

Geom Title=Existing Conditions

River Reach=WOODS CREEK,Reach-1
Reach XY= 30
      2456375.00     13561025.00      2456814.94     13560735.00
      2456780.45     13560422.53      2457247.86     13559901.16
      2457617.61     13559731.33      2458121.54     13558823.50
      2458227.67     13558283.50      2459666.86     13556531.06
      2459828.54     13555876.46      2460635.78     13554515.32
      2461561.38     13553688.21      2462208.32     13552641.64
      2463378.00     13552119.54      2463808.79     13551741.71
      2464083.02     13551118.66      2464369.61     13550927.44
      2464332.81     13550771.59      2464704.47     13550094.10
      2465275.10     13549982.33      2465774.00     13550078.54
      2465925.10     13550267.72      2466126.48     13550028.61
      2466709.66     13549924.95      2467076.28     13550221.63
      2467284.68     13550185.19      2467480.81     13550523.46
      2467670.04     13550427.54      2467630.48     13550226.96
      2467921.69     13550416.94      2468125.00     13550375.00

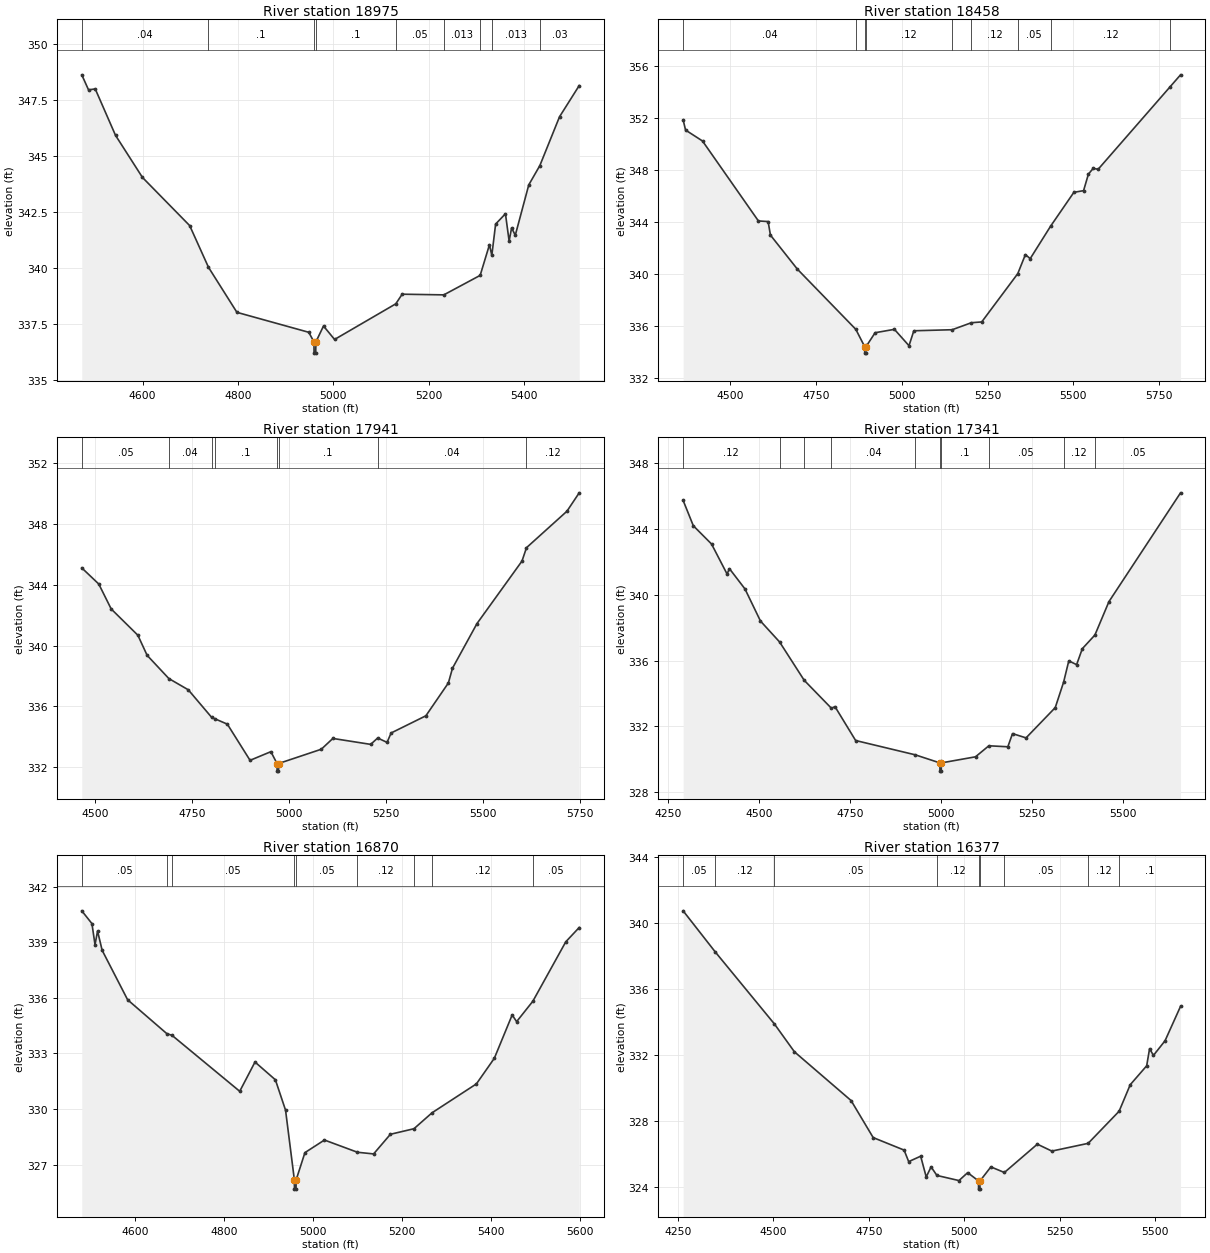
Type RM Length L Ch R = 1,18975,517,517,517
BEGIN DESCRIPTION:
WOODS CREEK 42.0
END DESCRIPTION:
XS GIS Cut Line= 3
      2457424.97     13560524.97      2457125.00     13560225.00
      2456524.99     13560075.00
#Sta/Elev= 30
  4472.7  348.64  4486.8  347.97  4500.9  348.01  4543.4  345.94  4599.9  344.06
  4698.9  341.91  4738.3  340.05  4797.9  338.04  4948.5  337.15  4959.4  336.72
  4959.6  336.22  4963.1  336.22  4963.4  336.72  4979.4  337.43  5002.6  336.83
  5130.9  338.42  5144.3  338.85  5231.6  338.82  5307.8  339.69  5327.3  341.06
  5332.2  340.58  5340.2  341.98  5360.8  342.44  5368.5  341.22  5373.7  341.81
  5381.4  341.48  5409.7  343.73  5432.9  344.59  5474.2  346.77  5515.4  348.16
#Mann=9,-1,0
  4472.7    0.04       0  4738.3     0.1       0  4959.4    0.05       0
  4963.4     0.1       0  5130.9    0.05       0  5231.6   0.013       0
  5307.8    0.05       0  5332.2   0.013       0  5432.9    0.03       0
Bank Sta=4959.4,4963.4
Exp/Cntr=0.3,0.1

Type RM Length L Ch R = 1,18458,517,517,517
BEGIN DESCRIPTION:
WOODS CREEK 41.0
END DESCRIPTION:
XS GIS Cut Line= 3
      2457775.00     13560325.00      2457375.00     13559875.00
      2456775.01     13559275.01
#Sta/Elev= 30
  4362.3  351.84  4369.4  351.05  4418.8  350.21  4581.8  344.06  4610.2  344.01
  4616.9  342.97  4695.5  340.35  4865.9  335.72  4891.7  334.39  4892.0  333.89
  4895.5  333.89  4895.7  334.39  4922.2  335.46  4978.5  335.72  5021.0  334.46
  5035.1  335.61  5146.9  335.69  5203.0  336.23  5233.1  336.29  5338.3  340.01
  5360.4  341.47  5374.5  341.16  5433.8  343.65  5501.8  346.26  5530.1  346.39
  5544.2  347.66  5558.4  348.11  5572.5  348.03  5782.8  354.39  5812.9  355.30
#Mann=9,-1,0
  4362.3    0.04       0  4865.9    0.12       0  4891.7    0.05       0
  4895.7    0.12       0  5146.9     0.1       0  5203.0    0.12       0
  5338.3    0.05       0  5433.8    0.12       0  5782.8    0.04       0
Bank Sta=4891.7,4895.7
Exp/Cntr=0.3,0.1

Type RM Length L Ch R = 1,17941,600,600,600
BEGIN DESCRIPTION:
WOODS CREEK 40.0
END DESCRIPTION:
XS GIS Cut Line= 3
      2457824.99     13560074.98      2457575.00     13559475.00
      2456975.03     13559275.01
#Sta/Elev= 30
  4466.3  345.11  4510.1  344.05  4542.1  342.41  4610.9  340.68  4634.7  339.36
  4690.8  337.83  4740.9  337.09  4801.0  335.28  4808.9  335.19  4841.6  334.83
  4900.1  332.45  4953.8  333.02  4969.6  332.24  4969.9  331.74  4973.4  331.74
  4973.6  332.24  5083.8  333.18  5113.6  333.89  5211.1  333.50  5229.2  333.92
  5253.3  333.63  5263.8  334.25  5353.4  335.38  5411.4  337.54  5422.0  338.51
  5485.2  341.45  5601.2  345.56  5612.8  346.44  5717.1  348.84  5748.7  350.05
#Mann=8,-1,0
  4466.3    0.05       0  4690.8    0.04       0  4801.0    0.05       0
  4808.9     0.1       0  4969.6    0.05       0  4973.6     0.1       0
  5229.2    0.04       0  5612.8    0.12       0
Bank Sta=4969.6,4973.6
Exp/Cntr=0.3,0.1

Type RM Length L Ch R = 1,17341,471,471,471
BEGIN DESCRIPTION:
WOODS CREEK 39.0
END DESCRIPTION:
XS GIS Cut Line= 3
      2458374.98     13559624.98      2457925.00     13559125.00
      2457324.98     13558774.99
#Sta/Elev= 30
  4290.9  345.73  4318.9  344.19  4369.0  343.08  4411.6  341.26  4418.3  341.58
  4460.9  340.35  4503.5  338.40  4556.0  337.13  4623.7  334.80  4698.5  333.10
  4708.3  333.20  4765.1  331.14  4929.1  330.27  4996.7  329.78  4996.9  329.28
  5000.4  329.28  5000.7  329.78  5094.6  330.15  5131.3  330.82  5183.5  330.76
  5196.3  331.56  5233.5  331.30  5313.8  333.14  5336.8  334.69  5351.0  335.98
  5372.5  335.75  5388.2  336.72  5422.8  337.55  5461.4  339.58  5658.2  346.19
#Mann=10,-1,0
  4290.9    0.12       0  4556.0    0.05       0  4623.7    0.12       0
  4698.5    0.04       0  4929.1     0.1       0  4996.7    0.05       0
  5000.7     0.1       0  5131.3    0.05       0  5336.8    0.12       0
  5422.8    0.05       0
Bank Sta=4996.7,5000.7
Exp/Cntr=0.3,0.1

Type RM Length L Ch R = 1,16870,493,493,493
BEGIN DESCRIPTION:
WOODS CREEK 38.0
END DESCRIPTION:
XS GIS Cut Line= 3
      2458574.97     13558974.98      2458125.00     13558725.00
      2457525.02     13558675.00
#Sta/Elev= 30
  4480.5  340.70  4503.3  340.01  4510.2  338.87  4515.9  339.61  4526.2  338.57
  4583.4  335.90  4671.5  334.07  4683.1  333.98  4835.1  330.96  4869.4  332.54
  4915.2  331.58  4938.0  329.94  4957.8  326.18  4958.0  325.68  4961.5  325.68
  4961.8  326.18  4981.5  327.65  5025.3  328.33  5099.4  327.67  5135.7  327.58
  5173.4  328.64  5226.3  328.94  5266.9  329.80  5366.5  331.36  5406.7  332.74
  5446.8  335.08  5456.8  334.72  5493.2  335.82  5567.2  339.03  5597.3  339.80
#Mann=9,-1,0
  4480.5    0.05       0  4671.5    0.12       0  4683.1    0.05       0
  4957.8    0.05       0  4961.8    0.05       0  5099.4    0.12       0
  5226.3    0.04       0  5266.9    0.12       0  5493.2    0.05       0
Bank Sta=4957.8,4961.8
Exp/Cntr=0.3,0.1

Type RM Length L Ch R = 1,16377,364,364,364
BEGIN DESCRIPTION:
WOODS CREEK 37.0
END DESCRIPTION:
XS GIS Cut Line= 3
      2458624.98     13558924.97      2458275.00     13558325.00
      2457674.96     13558425.01
#Sta/Elev= 30
  4263.7  340.75  4347.3  338.27  4502.8  333.88  4555.2  332.19  4703.6  329.23
  4761.5  326.98  4842.5  326.22  4854.5  325.52  4885.9  325.85  4900.4  324.59
  4913.2  325.20  4928.5  324.68  4986.2  324.37  5009.0  324.85  5037.4  324.35
  5037.6  323.85  5041.1  323.85  5041.4  324.35  5069.8  325.20  5105.2  324.86
  5191.5  326.58  5229.5  326.16  5324.6  326.63  5405.7  328.58  5434.8  330.19
  5477.9  331.34  5485.5  332.38  5495.6  331.97  5526.0  332.86  5566.6  334.95
#Mann=9,-1,0
  4263.7    0.05       0  4347.3    0.12       0  4502.8    0.05       0
  4928.5    0.12       0  5037.4    0.05       0  5041.4    0.12       0
  5105.2    0.05       0  5324.6    0.12       0  5405.7     0.1       0
Bank Sta=5037.4,5041.4
Exp/Cntr=0.3,0.1

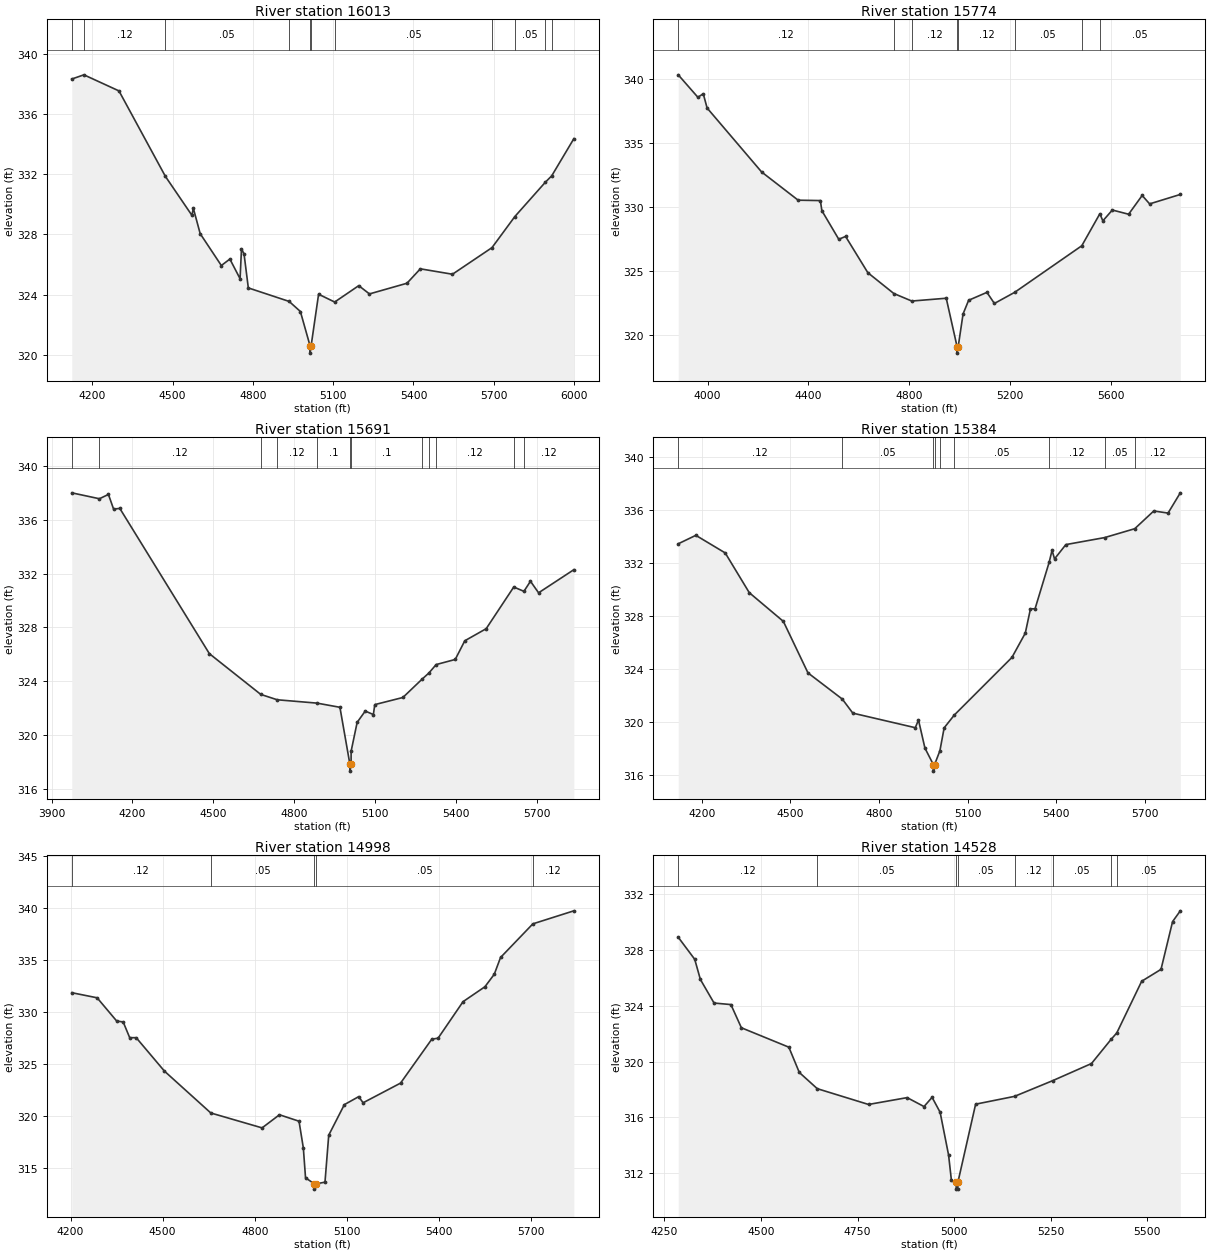
Type RM Length L Ch R = 1,16013,239,239,239
BEGIN DESCRIPTION:
Mapping XS ef8e4358
END DESCRIPTION:
XS GIS Cut Line= 3
      2458740.64     13558871.54      2458455.93     13558069.49
      2457431.66     13558052.13
#Sta/Elev= 30
  4123.7  338.34  4169.1  338.62  4300.0  337.55  4473.5  331.86  4572.5  329.27
  4577.8  329.74  4603.4  328.05  4682.4  325.93  4714.3  326.36  4752.4  325.05
  4757.7  327.05  4767.3  326.69  4783.2  324.44  4935.8  323.54  4977.7  322.87
  5013.6  320.60  5013.9  320.10  5017.9  320.60  5045.7  324.02  5105.8  323.50
  5195.7  324.59  5235.7  324.04  5375.8  324.75  5425.8  325.71  5545.8  325.35
  5693.4  327.12  5778.9  329.19  5893.1  331.48  5916.6  331.90  5999.2  334.37
#Mann=11,-1,0
  4123.7    0.05       0  4169.1    0.12       0  4473.5    0.05       0
  4935.8    0.12       0  5013.6    0.05       0  5017.9    0.12       0
  5105.8    0.05       0  5693.4     0.1       0  5778.9    0.05       0
  5893.1    0.12       0  5916.6    0.05       0
Bank Sta=5013.6,5017.9
Exp/Cntr=0.3,0.1

Type RM Length L Ch R = 1,15774,83,83,83
BEGIN DESCRIPTION:
Mapping XS d86032bf
END DESCRIPTION:
XS GIS Cut Line= 3
      2459515.00     13558472.29      2458594.82     13557892.41
      2457754.56     13557555.61
#Sta/Elev= 30
  3883.4  340.35  3961.5  338.59  3982.7  338.87  3998.0  337.75  4214.4  332.74
  4359.4  330.53  4447.6  330.50  4453.5  329.71  4520.6  327.47  4547.7  327.69
  4636.0  324.85  4739.1  323.22  4810.4  322.63  4947.2  322.85  4990.3  319.05
  4990.5  318.55  4994.6  319.05  5014.0  321.62  5036.1  322.69  5108.7  323.31
  5138.3  322.44  5218.7  323.31  5485.2  326.96  5557.0  329.47  5568.8  328.91
  5606.5  329.76  5671.1  329.43  5724.9  330.90  5754.5  330.24  5876.3  330.98
#Mann=8,-1,0
  3883.4    0.12       0  4739.1    0.05       0  4810.4    0.12       0
  4990.3    0.05       0  4994.6    0.12       0  5218.7    0.05       0
  5485.2    0.12       0  5557.0    0.05       0
Bank Sta=4990.3,4994.6
Exp/Cntr=0.3,0.1

Type RM Length L Ch R = 1,15691,307,307,307
BEGIN DESCRIPTION:
Mapping XS 3bbfaede
END DESCRIPTION:
XS GIS Cut Line= 3
      2459580.94     13558197.97      2458615.65     13557819.49
      2457844.86     13557524.37
#Sta/Elev= 30
  3974.9  338.01  4077.3  337.57  4110.9  337.89  4130.0  336.80  4153.1  336.85
  4485.3  326.04  4675.8  323.01  4736.9  322.61  4884.7  322.36  4969.5  322.05
  5006.6  317.80  5006.8  317.30  5010.9  317.80  5011.0  318.78  5033.4  320.93
  5063.4  321.77  5093.5  321.51  5098.8  322.25  5203.0  322.78  5274.0  324.14
  5299.4  324.60  5326.4  325.23  5397.2  325.61  5432.6  327.00  5512.0  327.90
  5614.2  331.00  5652.0  330.68  5676.2  331.43  5706.3  330.57  5837.1  332.29
#Mann=12,-1,0
  3974.9    0.05       0  4077.3    0.12       0  4675.8    0.05       0
  4736.9    0.12       0  4884.7     0.1       0  5006.6    0.05       0
  5010.9     0.1       0  5274.0    0.12       0  5299.4    0.05       0
  5326.4    0.12       0  5614.2    0.05       0  5652.0    0.12       0
Bank Sta=5006.6,5010.9
Exp/Cntr=0.3,0.1

Type RM Length L Ch R = 1,15384,386,386,386
BEGIN DESCRIPTION:
Mapping XS 0cf45707
END DESCRIPTION:
XS GIS Cut Line= 3
      2459601.81     13557954.93      2458782.32     13557600.74
      2458009.02     13557368.41
#Sta/Elev= 30
  4120.3  333.45  4179.9  334.09  4279.4  332.76  4360.8  329.76  4476.3  327.59
  4559.6  323.70  4675.9  321.72  4711.5  320.66  4923.0  319.56  4933.9  320.14
  4955.7  318.02  4984.1  316.78  4984.4  316.28  4988.5  316.78  5006.4  317.82
  5020.8  319.55  5055.3  320.52  5250.4  324.87  5295.5  326.70  5313.1  328.54
  5328.6  328.54  5376.3  332.05  5386.2  332.96  5394.6  332.31  5432.9  333.39
  5564.4  333.92  5666.2  334.59  5730.7  335.93  5779.0  335.77  5820.5  337.30
#Mann=9,-1,0
  4120.3    0.12       0  4675.9    0.05       0  4984.1    0.05       0
  4988.5    0.05       0  5006.4    0.12       0  5055.3    0.05       0
  5376.3    0.12       0  5564.4    0.05       0  5666.2    0.12       0
Bank Sta=4984.1,4988.5
Exp/Cntr=0.3,0.1

Type RM Length L Ch R = 1,14998,470,470,470
BEGIN DESCRIPTION:
Mapping XS 7f5b5e8e
END DESCRIPTION:
XS GIS Cut Line= 3
      2459594.84     13557882.01      2459035.79     13557316.02
      2458210.36     13557159.95
#Sta/Elev= 30
  4204.0  331.84  4286.6  331.35  4350.3  329.12  4371.5  329.03  4392.7  327.52
  4413.9  327.52  4505.9  324.31  4657.0  320.29  4824.0  318.86  4880.6  320.12
  4944.3  319.50  4958.4  316.93  4965.5  314.07  4994.4  313.48  4994.7  312.98
  4999.1  313.48  5028.9  313.65  5041.1  318.16  5091.9  321.09  5138.7  321.86
  5153.0  321.27  5275.1  323.16  5376.9  327.38  5397.3  327.47  5478.7  330.98
  5549.9  332.41  5580.4  333.61  5600.8  335.22  5706.1  338.45  5839.6  339.70
#Mann=5,-1,0
  4204.0    0.12       0  4657.0    0.05       0  4994.4    0.05       0
  4999.1    0.05       0  5706.1    0.12       0
Bank Sta=4994.4,4999.1
Exp/Cntr=0.3,0.1

Type RM Length L Ch R = 1,14528,500,500,500
BEGIN DESCRIPTION:
WOODS CREEK 33.0
END DESCRIPTION:
XS GIS Cut Line= 3
      2459874.99     13557374.99      2459275.00     13556925.00
      2458724.99     13556925.00
#Sta/Elev= 30
  4285.6  328.90  4328.3  327.32  4342.9  325.88  4378.3  324.19  4422.0  324.08
  4449.1  322.42  4572.0  321.03  4599.1  319.22  4645.6  318.06  4778.3  316.93
  4878.3  317.42  4922.0  316.78  4942.9  317.44  4963.7  316.37  4985.6  313.31
  4992.9  311.50  5005.1  311.37  5005.5  310.87  5009.5  310.87  5009.8  311.37
  5055.6  316.95  5156.4  317.51  5254.8  318.63  5355.6  319.86  5406.4  321.59
  5421.1  322.05  5485.6  325.75  5535.6  326.60  5565.6  330.02  5585.6  330.79
#Mann=8,-1,0
  4285.6    0.12       0  4645.6    0.05       0  5005.1    0.05       0
  5009.8    0.05       0  5156.4    0.12       0  5254.8    0.05       0
  5406.4    0.03       0  5421.1    0.05       0
Bank Sta=5005.1,5009.8
Exp/Cntr=0.3,0.1

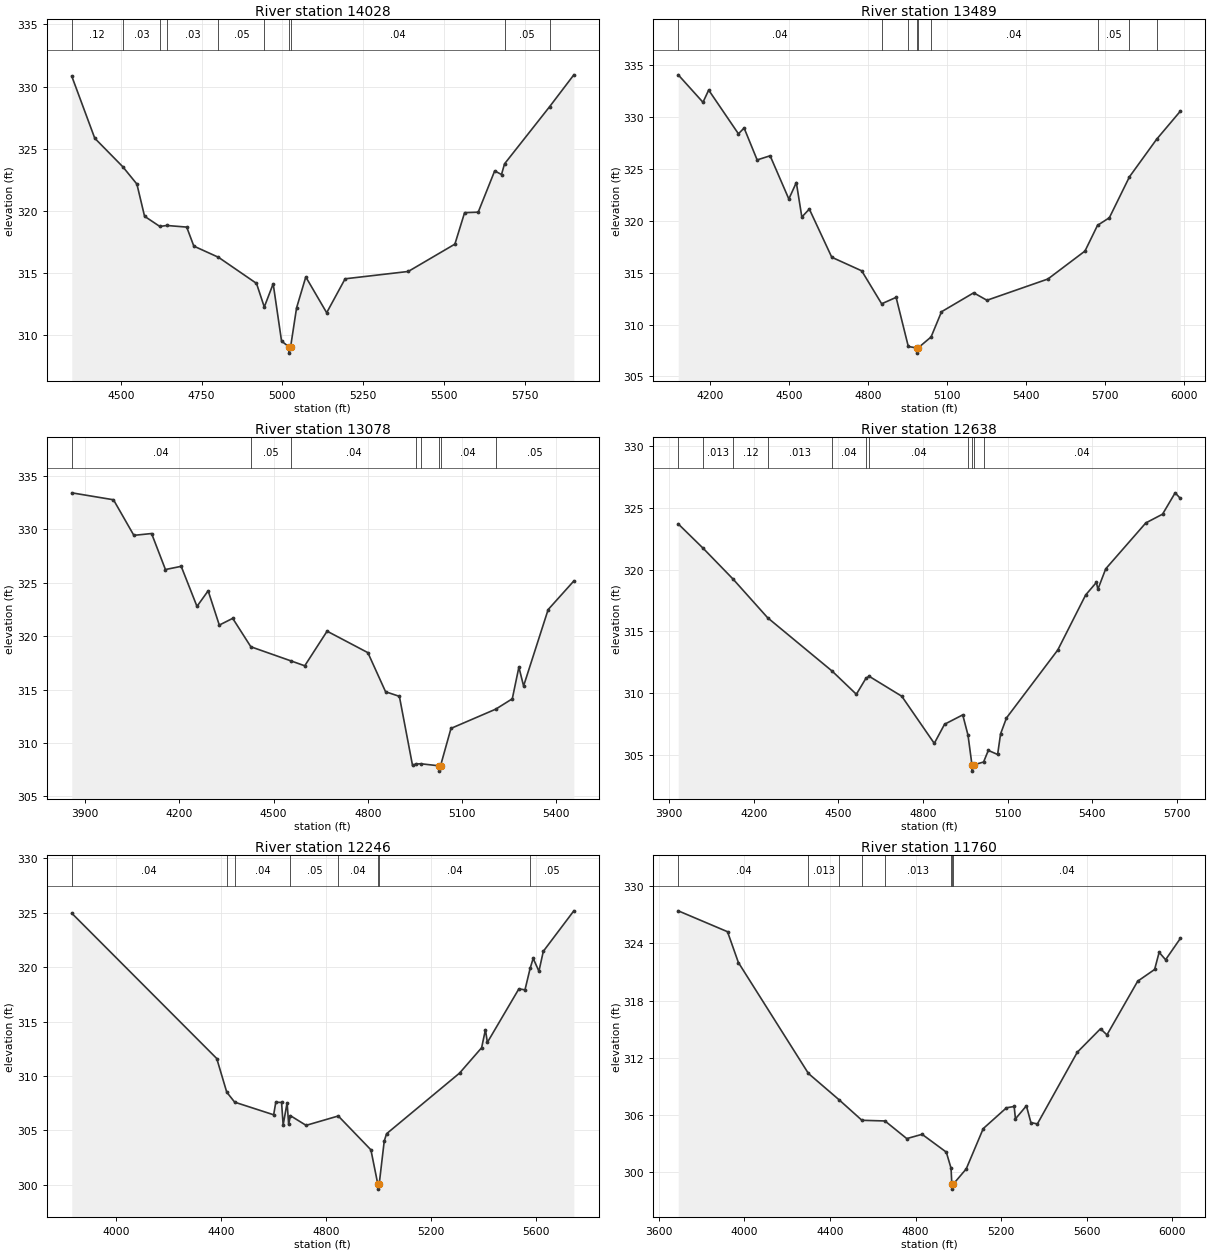
Type RM Length L Ch R = 1,14028,539,539,539
BEGIN DESCRIPTION:
WOODS CREEK 32.0
END DESCRIPTION:
XS GIS Cut Line= 3
      2460175.01     13556925.01      2459625.00     13556575.00
      2458875.02     13556075.01
#Sta/Elev= 30
  4348.3  330.84  4419.4  325.85  4506.3  323.55  4549.8  322.16  4573.5  319.57
  4620.8  318.75  4642.1  318.83  4703.9  318.70  4725.9  317.17  4802.2  316.27
  4919.8  314.17  4943.9  312.27  4971.4  314.14  4997.3  309.53  5020.3  309.06
  5020.7  308.56  5025.3  309.06  5043.8  312.20  5072.3  314.69  5136.9  311.81
  5194.0  314.54  5389.3  315.13  5533.6  317.33  5563.6  319.86  5605.7  319.90
  5656.7  323.22  5677.8  322.93  5687.2  323.79  5826.7  328.39  5901.6  330.95
#Mann=10,-1,0
  4348.3    0.12       0  4506.3    0.03       0  4620.8    0.05       0
  4642.1    0.03       0  4802.2    0.05       0  4943.9    0.04       0
  5020.3    0.04       0  5025.3    0.04       0  5687.2    0.05       0
  5826.7    0.04       0
Bank Sta=5020.3,5025.3
Exp/Cntr=0.3,0.1

Type RM Length L Ch R = 1,13489,411,411,411
BEGIN DESCRIPTION:
Mapping XS 0975a43b
END DESCRIPTION:
XS GIS Cut Line= 4
      2460480.22     13556732.67      2459959.40     13556156.30
      2459657.32     13556045.19      2458855.23     13555961.85
#Sta/Elev= 30
  4080.0  334.10  4173.9  331.45  4195.5  332.63  4308.4  328.41  4330.0  328.97
  4379.4  325.89  4428.7  326.29  4499.7  322.12  4528.1  323.71  4549.0  320.38
  4577.4  321.15  4662.6  316.50  4776.2  315.19  4851.9  312.01  4906.7  312.63
  4953.0  307.89  4984.9  307.75  4985.3  307.25  4990.0  307.75  5039.4  308.81
  5078.9  311.24  5201.1  313.07  5251.4  312.35  5482.6  314.40  5623.4  317.10
  5671.0  319.58  5715.8  320.31  5792.1  324.26  5895.1  327.88  5985.1  330.59
#Mann=9,-1,0
  4080.0    0.04       0  4851.9    0.05       0  4953.0     0.1       0
  4984.9    0.05       0  4990.0     0.1       0  5039.4    0.04       0
  5671.0    0.05       0  5792.1    0.04       0  5895.1    0.05       0
Bank Sta=4984.9,4990
Exp/Cntr=0.3,0.1

Type RM Length L Ch R = 1,13078,440,440,440
BEGIN DESCRIPTION:
Mapping XS 0387d497
END DESCRIPTION:
XS GIS Cut Line= 3
      2460626.09     13556670.21      2459959.40     13555750.05
      2459573.99     13555493.11
#Sta/Elev= 30
  3857.0  333.41  3989.9  332.76  4054.8  329.43  4111.3  329.60  4155.4  326.23
  4205.6  326.53  4255.9  322.78  4291.5  324.24  4327.0  321.03  4369.7  321.66
  4427.5  319.00  4556.1  317.67  4599.2  317.22  4670.4  320.46  4800.3  318.45
  4856.7  314.79  4900.7  314.36  4942.6  307.89  4952.3  308.02  4968.7  308.05
  5026.2  307.86  5026.7  307.36  5031.8  307.86  5065.1  311.36  5207.6  313.16
  5260.4  314.13  5281.4  317.09  5296.4  315.33  5374.6  322.48  5456.5  325.16
#Mann=8,-1,0
  3857.0    0.04       0  4427.5    0.05       0  4556.1    0.04       0
  4952.3     0.1       0  4968.7    0.04       0  5026.2    0.04       0
  5031.8    0.04       0  5207.6    0.05       0
Bank Sta=5026.2,5031.8
Exp/Cntr=0.3,0.1

Type RM Length L Ch R = 1,12638,392,392,392
BEGIN DESCRIPTION:
Mapping XS ee6915c3
END DESCRIPTION:
XS GIS Cut Line= 3
      2461027.99     13555965.33      2460111.31     13555385.46
      2459444.65     13555184.08
#Sta/Elev= 30
  3931.7  323.72  4020.3  321.74  4126.5  319.24  4249.0  316.11  4477.6  311.79
  4563.6  309.91  4597.4  311.20  4608.9  311.37  4724.7  309.75  4840.0  305.93
  4876.5  307.48  4941.0  308.24  4959.7  306.59  4973.7  304.18  4974.2  303.68
  4979.3  304.18  5014.9  304.42  5031.7  305.36  5064.7  305.03  5075.2  306.70
  5096.1  307.99  5278.1  313.50  5377.0  317.96  5415.2  318.98  5420.4  318.42
  5448.2  320.08  5590.4  323.80  5649.8  324.51  5694.5  326.24  5712.8  325.79
#Mann=11,-1,0
  3931.7    0.05       0  4020.3   0.013       0  4126.5    0.12       0
  4249.0   0.013       0  4477.6    0.04       0  4597.4    0.05       0
  4608.9    0.04       0  4959.7     0.1       0  4973.7    0.05       0
  4979.3     0.1       0  5014.9    0.04       0
Bank Sta=4973.7,4979.3
Exp/Cntr=0.3,0.1

Type RM Length L Ch R = 1,12246,486,486,486
BEGIN DESCRIPTION:
Mapping XS d98c35ce
END DESCRIPTION:
XS GIS Cut Line= 3
      2461236.30     13555680.60      2460281.45     13555055.60
      2459573.13     13554743.11
#Sta/Elev= 30
  3830.3  324.95  4383.4  311.60  4421.5  308.51  4451.8  307.59  4600.5  306.43
  4608.7  307.59  4630.7  307.56  4636.7  305.49  4651.8  307.54  4657.8  305.54
  4664.3  306.35  4724.2  305.46  4847.0  306.32  4971.5  303.21  4997.5  300.10
  4998.0  299.60  5003.3  300.10  5022.3  304.01  5031.3  304.69  5309.7  310.26
  5393.9  312.59  5408.4  314.25  5415.8  313.08  5536.0  318.00  5559.3  317.91
  5579.1  319.90  5590.6  320.80  5612.5  319.62  5629.2  321.45  5745.7  325.17
#Mann=8,-1,0
  3830.3    0.04       0  4421.5    0.05       0  4451.8    0.04       0
  4664.3    0.05       0  4847.0    0.04       0  4997.5    0.04       0
  5003.3    0.04       0  5579.1    0.05       0
Bank Sta=4997.5,5003.3
Exp/Cntr=0.3,0.1

Type RM Length L Ch R = 1,11760,252,252,252
BEGIN DESCRIPTION:
Mapping XS bd1dec93
END DESCRIPTION:
XS GIS Cut Line= 3
      2461541.87     13555503.52      2460538.40     13554666.71
      2459668.43     13554094.83
#Sta/Elev= 30
  3690.5  327.42  3920.9  325.23  3971.7  322.00  4299.3  310.36  4441.1  307.63
  4549.4  305.45  4657.1  305.38  4759.2  303.53  4830.8  303.98  4944.0  302.11
  4966.2  300.42  4969.8  298.73  4970.2  298.23  4975.6  298.73  5037.1  300.35
  5116.7  304.58  5225.2  306.76  5261.3  306.90  5267.3  305.60  5318.5  306.97
  5339.6  305.21  5369.8  305.07  5556.5  312.59  5665.0  315.05  5695.2  314.41
  5838.9  320.04  5918.1  321.27  5939.2  323.07  5969.3  322.29  6038.2  324.52
#Mann=8,-1,0
  3690.5    0.04       0  4299.3   0.013       0  4441.1    0.04       0
  4549.4    0.05       0  4657.1   0.013       0  4966.2    0.04       0
  4969.8    0.04       0  4975.6    0.04       0
Bank Sta=4969.8,4975.6
Exp/Cntr=0.3,0.1

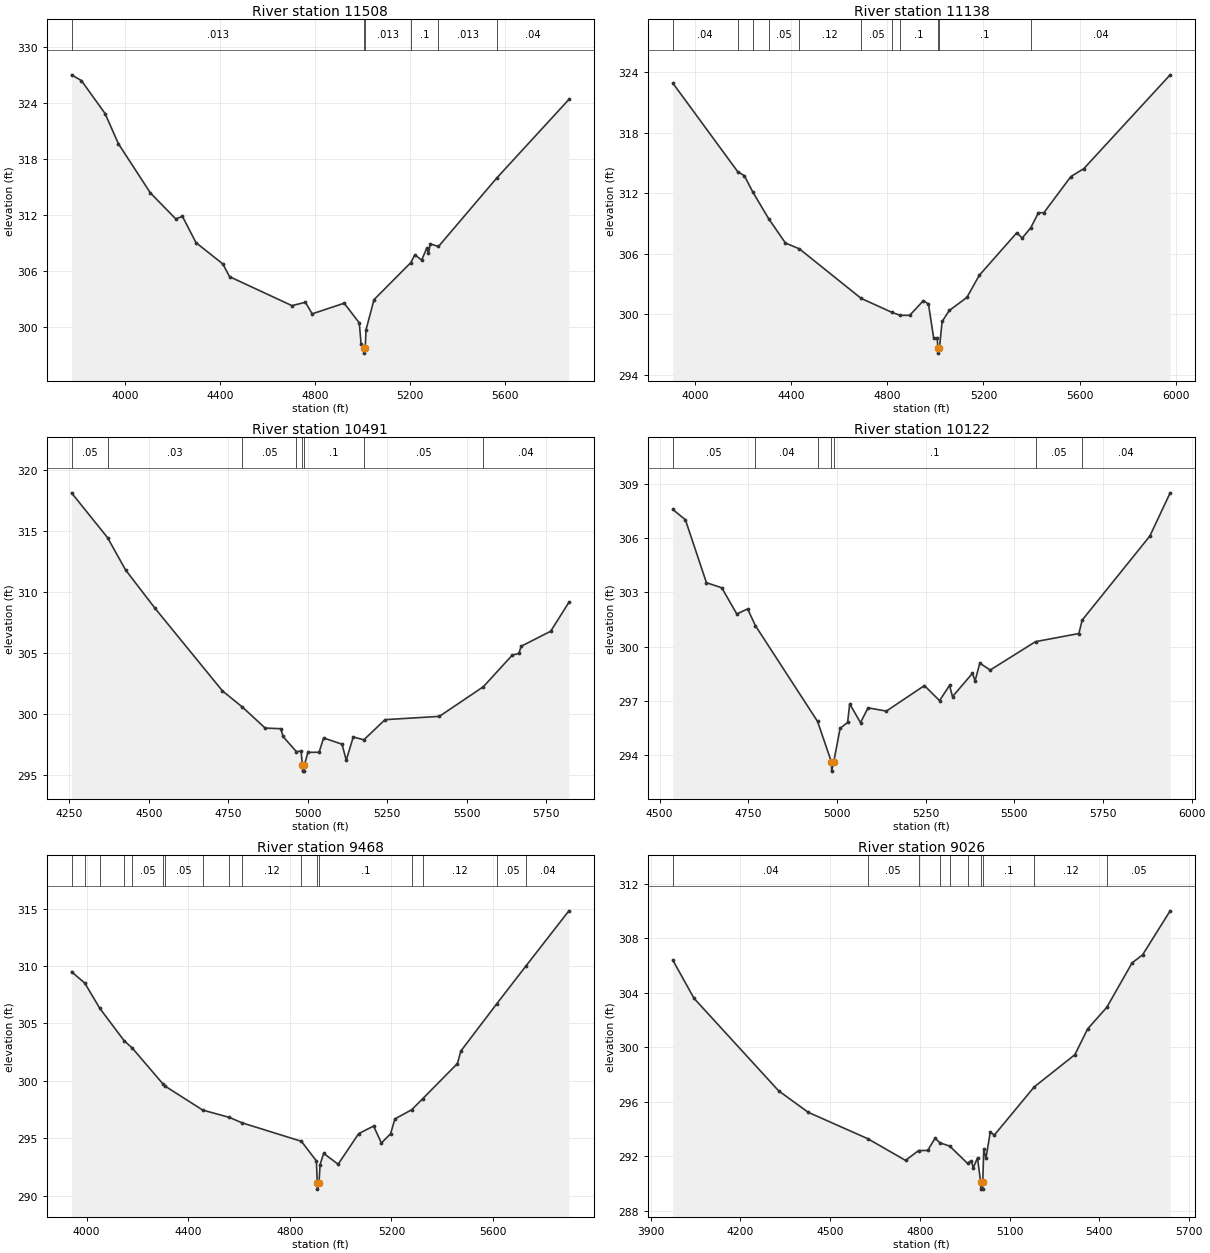
Type RM Length L Ch R = 1,11508,370,370,370
BEGIN DESCRIPTION:
Mapping XS 98e32131
END DESCRIPTION:
XS GIS Cut Line= 3
      2461600.91     13555277.84      2460642.56     13554434.08
      2460021.07     13553906.33
#Sta/Elev= 30
  3774.9  327.07  3816.6  326.45  3916.0  322.92  3972.2  319.68  4106.9  314.40
  4213.1  311.64  4241.6  311.89  4298.5  309.08  4411.4  306.80  4439.9  305.43
  4702.1  302.33  4758.7  302.69  4787.1  301.45  4921.8  302.59  4985.4  300.48
  4993.0  298.22  5004.2  297.74  5004.7  297.24  5010.2  297.74  5013.9  299.76
  5047.3  302.97  5202.4  306.95  5219.1  307.78  5247.7  307.21  5269.7  308.53
  5276.2  307.92  5284.0  308.95  5318.5  308.67  5563.6  316.01  5867.1  324.43
#Mann=6,-1,0
  3774.9   0.013       0  5004.2    0.03       0  5010.2   0.013       0
  5202.4     0.1       0  5318.5   0.013       0  5563.6    0.04       0
Bank Sta=5004.2,5010.2
Exp/Cntr=0.3,0.1

Type RM Length L Ch R = 1,11138,647,647,647
BEGIN DESCRIPTION:
Mapping XS 5dec2139
END DESCRIPTION:
XS GIS Cut Line= 3
      2461777.09     13554963.57      2460922.08     13554204.04
      2460093.08     13553796.05
#Sta/Elev= 30
  3908.8  322.94  4178.5  314.16  4206.4  313.75  4240.6  312.17  4306.8  309.51
  4377.0  307.08  4435.1  306.50  4691.7  301.59  4820.0  300.20  4853.9  299.91
  4893.8  299.91  4950.7  301.37  4971.6  301.03  4993.3  297.65  5007.5  297.69
  5011.2  296.66  5011.7  296.16  5017.2  296.66  5028.4  299.30  5058.2  300.39
  5131.2  301.68  5182.9  303.88  5339.0  308.10  5361.4  307.57  5397.1  308.60
  5428.8  310.09  5451.3  310.08  5563.6  313.67  5617.6  314.46  5976.4  323.76
#Mann=11,-1,0
  3908.8    0.04       0  4178.5    0.05       0  4240.6    0.03       0
  4306.8    0.05       0  4435.1    0.12       0  4691.7    0.05       0
  4820.0    0.12       0  4853.9     0.1       0  5011.2    0.05       0
  5017.2     0.1       0  5397.1    0.04       0
Bank Sta=5011.2,5017.2
Exp/Cntr=0.3,0.1

Type RM Length L Ch R = 1,10491,369,369,369
BEGIN DESCRIPTION:
WOODS CREEK 24.0
END DESCRIPTION:
XS GIS Cut Line= 3
      2461924.98     13554374.98      2461375.00     13553775.00
      2460775.01     13553325.01
#Sta/Elev= 30
  4256.9  318.14  4370.0  314.47  4426.8  311.82  4518.6  308.70  4731.4  301.90
  4794.3  300.57  4865.8  298.85  4915.1  298.80  4921.9  298.16  4963.9  296.92
  4978.6  296.96  4982.9  295.82  4983.4  295.32  4988.7  295.32  4989.2  295.82
  5000.2  296.86  5035.4  296.87  5049.5  298.04  5107.3  297.53  5120.8  296.22
  5142.7  298.12  5176.2  297.89  5242.7  299.54  5413.5  299.81  5551.8  302.24
  5642.7  304.83  5663.5  304.97  5670.8  305.56  5763.5  306.79  5820.8  309.16
#Mann=8,-1,0
  4256.9    0.05       0  4370.0    0.03       0  4794.3    0.05       0
  4963.9     0.1       0  4982.9    0.05       0  4989.2     0.1       0
  5176.2    0.05       0  5551.8    0.04       0
Bank Sta=4982.9,4989.2
Exp/Cntr=0.3,0.1

Type RM Length L Ch R = 1,10122,654,654,654
BEGIN DESCRIPTION:
WOODS CREEK 23.0
END DESCRIPTION:
XS GIS Cut Line= 3
      2461874.99     13553924.98      2461525.00     13553375.00
      2460924.99     13552925.00
#Sta/Elev= 30
  4537.5  307.59  4573.0  307.02  4632.3  303.54  4675.5  303.26  4717.8  301.81
  4748.3  302.09  4770.5  301.16  4945.5  295.87  4984.7  293.62  4985.2  293.12
  4991.0  293.62  5009.1  295.49  5030.2  295.81  5036.1  296.84  5066.6  295.80
  5087.8  296.62  5139.4  296.44  5246.7  297.85  5289.4  297.02  5317.5  297.86
  5325.9  297.24  5382.1  298.53  5389.4  298.11  5402.9  299.09  5432.1  298.71
  5559.9  300.28  5682.1  300.73  5691.3  301.47  5882.1  306.12  5939.4  308.51
#Mann=7,-1,0
  4537.5    0.05       0  4770.5    0.04       0  4945.5     0.1       0
  4984.7    0.05       0  4991.0     0.1       0  5559.9    0.05       0
  5691.3    0.04       0
Bank Sta=4984.7,4991
Exp/Cntr=0.3,0.1

Type RM Length L Ch R = 1,9468,442,442,442
BEGIN DESCRIPTION:
WOODS CREEK 22.0
END DESCRIPTION:
XS GIS Cut Line= 3
      2462674.99     13553724.99      2461875.00     13553025.00
      2461475.02     13552225.03
#Sta/Elev= 30
  3940.8  309.50  3992.9  308.51  4052.2  306.31  4147.7  303.50  4179.7  302.86
  4302.4  299.69  4307.2  299.57  4457.1  297.46  4562.2  296.82  4611.9  296.35
  4845.6  294.74  4904.6  293.03  4907.8  291.08  4908.3  290.58  4914.7  291.08
  4918.9  292.72  4933.1  293.69  4990.0  292.75  5070.9  295.41  5129.6  296.07
  5160.3  294.59  5196.7  295.41  5213.4  296.69  5279.6  297.49  5323.4  298.46
  5459.4  301.51  5473.4  302.61  5615.0  306.73  5729.5  310.01  5898.2  314.80
#Mann=17,-1,0
  3940.8    0.05       0  3992.9    0.04       0  4052.2    0.05       0
  4147.7    0.04       0  4179.7    0.05       0  4302.4    0.04       0
  4307.2    0.05       0  4457.1    0.04       0  4562.2    0.05       0
  4611.9    0.12       0  4845.6     0.1       0  4907.8    0.05       0
  4914.7     0.1       0  5279.6    0.05       0  5323.4    0.12       0
  5615.0    0.05       0  5729.5    0.04       0
Bank Sta=4907.8,4914.7
Exp/Cntr=0.3,0.1

Type RM Length L Ch R = 1,9026,539,539,539
BEGIN DESCRIPTION:
WOODS CREEK 21.0
END DESCRIPTION:
XS GIS Cut Line= 3
      2462875.03     13553425.03      2462275.00     13552825.00
      2461725.01     13552225.01
#Sta/Elev= 30
  3974.4  306.41  4045.2  303.61  4328.0  296.82  4427.0  295.24  4626.3  293.30
  4752.3  291.71  4796.0  292.43  4826.4  292.44  4851.0  293.34  4867.1  293.00
  4900.0  292.76  4959.6  291.49  4971.9  291.69  4978.7  291.17  4992.9  291.89
  5003.5  290.10  5004.0  289.60  5010.0  289.60  5010.5  290.10  5013.8  292.51
  5021.2  291.87  5035.4  293.77  5049.6  293.58  5182.3  297.10  5318.4  299.47
  5361.0  301.36  5425.2  302.95  5509.6  306.21  5544.7  306.80  5636.9  310.03
#Mann=10,-1,0
  3974.4    0.04       0  4626.3    0.05       0  4796.0    0.12       0
  4867.1    0.04       0  4900.0    0.12       0  4959.6     0.1       0
  5003.5    0.05       0  5010.5     0.1       0  5182.3    0.12       0
  5425.2    0.05       0
Bank Sta=5003.5,5010.5
Exp/Cntr=0.3,0.1

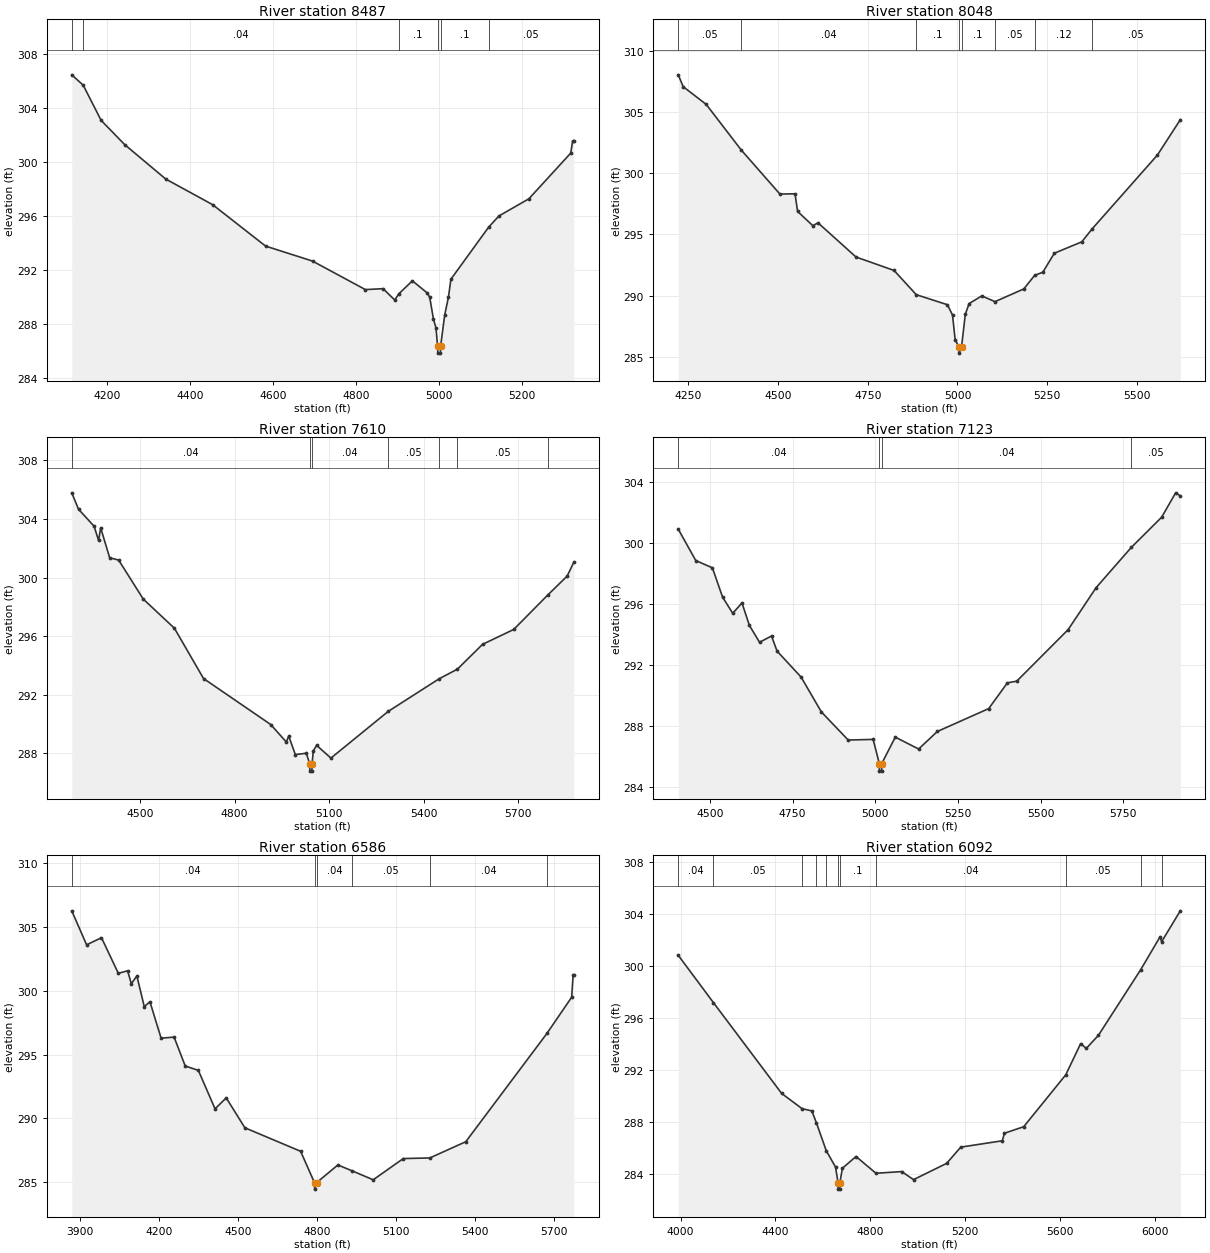
Type RM Length L Ch R = 1,8487,439,439,439
BEGIN DESCRIPTION:
WOODS CREEK 20.0
END DESCRIPTION:
XS GIS Cut Line= 3
      2463225.01     13553075.01      2462625.00     13552475.00
      2462425.00     13552175.00
#Sta/Elev= 30
  4115.1  306.45  4142.7  305.68  4185.8  303.08  4242.4  301.29  4341.4  298.74
  4454.5  296.84  4581.8  293.78  4694.9  292.67  4822.2  290.56  4864.7  290.63
  4892.9  289.79  4902.8  290.25  4935.4  291.21  4971.2  290.31  4977.2  289.98
  4986.2  288.36  4992.2  287.73  4996.1  286.36  4996.6  285.86  5002.8  285.86
  5003.3  286.36  5013.2  288.68  5022.2  290.00  5028.2  291.33  5119.0  295.18
  5143.9  296.01  5216.0  297.28  5316.7  300.66  5321.2  301.53  5324.2  301.53
#Mann=6,-1,0
  4115.1    0.05       0  4142.7    0.04       0  4902.8     0.1       0
  4996.1    0.05       0  5003.3     0.1       0  5119.0    0.05       0
Bank Sta=4996.1,5003.3
Exp/Cntr=0.3,0.1

Type RM Length L Ch R = 1,8048,438,438,438
BEGIN DESCRIPTION:
WOODS CREEK 19.0
END DESCRIPTION:
XS GIS Cut Line= 3
      2463524.97     13552874.97      2462975.00     13552275.00
      2462425.03     13552075.01
#Sta/Elev= 30
  4221.8  308.05  4235.6  307.08  4299.8  305.63  4397.4  301.90  4505.1  298.30
  4547.3  298.32  4554.4  296.88  4597.0  295.71  4611.2  295.95  4717.2  293.15
  4823.3  292.05  4885.1  290.07  4971.9  289.25  4986.1  288.41  4993.5  286.39
  5004.0  285.79  5004.5  285.29  5011.2  285.79  5021.8  288.47  5032.3  289.34
  5067.6  289.97  5104.4  289.50  5184.7  290.54  5215.0  291.65  5237.9  291.91
  5269.8  293.46  5346.3  294.39  5375.5  295.46  5557.1  301.49  5620.9  304.38
#Mann=8,-1,0
  4221.8    0.05       0  4397.4    0.04       0  4885.1     0.1       0
  5004.0    0.05       0  5011.2     0.1       0  5104.4    0.05       0
  5215.0    0.12       0  5375.5    0.05       0
Bank Sta=5004,5011.2
Exp/Cntr=0.3,0.1

Type RM Length L Ch R = 1,7610,487,487,487
BEGIN DESCRIPTION:
WOODS CREEK 18.0
END DESCRIPTION:
XS GIS Cut Line= 3
      2463824.99     13552674.98      2463325.00     13552075.00
      2462775.03     13551475.03
#Sta/Elev= 30
  4282.5  305.78  4304.0  304.66  4353.4  303.50  4367.7  302.53  4374.3  303.39
  4402.9  301.35  4431.5  301.19  4509.6  298.53  4608.6  296.54  4701.0  293.11
  4914.5  289.97  4963.9  288.78  4971.7  289.18  4992.6  287.92  5027.7  288.01
  5038.3  287.29  5038.8  286.79  5045.3  286.79  5045.8  287.29  5049.8  288.17
  5060.3  288.55  5105.7  287.68  5288.0  290.87  5448.6  293.08  5507.6  293.75
  5587.3  295.44  5686.6  296.46  5794.2  298.80  5856.2  300.10  5877.4  301.05
#Mann=7,-1,0
  4282.5    0.04       0  5038.3    0.04       0  5045.8    0.04       0
  5288.0    0.05       0  5448.6    0.04       0  5507.6    0.05       0
  5794.2    0.04       0
Bank Sta=5038.3,5045.8
Exp/Cntr=0.3,0.1

Type RM Length L Ch R = 1,7123,537,537,537
BEGIN DESCRIPTION:
WOODS CREEK 17.0
END DESCRIPTION:
XS GIS Cut Line= 3
      2463925.00     13552375.00      2463625.00     13551775.00
      2463025.03     13551175.03
#Sta/Elev= 30
  4403.7  300.93  4456.8  298.87  4507.1  298.39  4537.9  296.47  4568.6  295.41
  4596.6  296.09  4618.9  294.62  4649.7  293.51  4686.0  293.92  4702.8  292.93
  4775.4  291.23  4836.9  288.94  4918.0  287.10  4993.5  287.14  5012.1  285.56
  5012.6  285.06  5019.1  285.06  5019.6  285.56  5060.5  287.29  5131.1  286.51
  5187.7  287.66  5343.2  289.16  5399.8  290.85  5428.1  290.96  5583.6  294.34
  5668.5  297.10  5774.7  299.73  5866.5  301.71  5908.9  303.31  5923.0  303.11
#Mann=4,-1,0
  4403.7    0.04       0  5012.1    0.04       0  5019.6    0.04       0
  5774.7    0.05       0
Bank Sta=5012.1,5019.6
Exp/Cntr=0.3,0.1

Type RM Length L Ch R = 1,6586,494,494,494
BEGIN DESCRIPTION:
WOODS CREEK 16.0
END DESCRIPTION:
XS GIS Cut Line= 3
      2464674.98     13552274.98      2463825.00     13551375.00
      2463225.03     13551075.02
#Sta/Elev= 30
  3868.5  306.24  3924.9  303.58  3981.5  304.14  4045.5  301.35  4080.7  301.55
  4094.8  300.54  4116.1  301.14  4144.2  298.74  4165.6  299.13  4208.1  296.28
  4257.5  296.36  4299.9  294.10  4349.7  293.76  4413.2  290.75  4455.7  291.61
  4526.5  289.27  4738.5  287.43  4791.3  284.97  4791.8  284.47  4798.9  284.97
  4880.1  286.36  4935.5  285.89  5014.4  285.20  5128.8  286.86  5229.8  286.91
  5366.4  288.18  5674.9  296.65  5768.9  299.48  5774.4  301.20  5777.2  301.20
#Mann=6,-1,0
  3868.5    0.04       0  4791.3    0.05       0  4798.9    0.04       0
  4935.5    0.05       0  5229.8    0.04       0  5674.9    0.05       0
Bank Sta=4791.3,4798.9
Exp/Cntr=0.3,0.1

Type RM Length L Ch R = 1,6092,500,500,500
BEGIN DESCRIPTION:
WOODS CREEK 15.0
END DESCRIPTION:
XS GIS Cut Line= 3
      2464774.98     13551874.98      2464175.00     13551075.00
      2463075.01     13550875.00
#Sta/Elev= 30
  3989.7  300.86  4138.1  297.22  4426.1  290.23  4512.2  289.06  4553.2  288.89
  4572.6  287.97  4614.0  285.83  4653.2  284.57  4663.9  283.37  4664.4  282.87
  4671.1  282.87  4671.6  283.37  4682.4  284.48  4739.7  285.38  4823.8  284.09
  4932.4  284.22  4982.4  283.60  5121.8  284.85  5181.5  286.10  5356.8  286.59
  5365.7  287.17  5447.0  287.67  5624.3  291.66  5687.2  294.06  5711.3  293.70
  5762.1  294.70  5940.5  299.75  6022.6  302.29  6028.7  301.90  6107.7  304.28
#Mann=11,-1,0
  3989.7    0.04       0  4138.1    0.05       0  4512.2     0.1       0
  4572.6    0.05       0  4614.0     0.1       0  4663.9    0.04       0
  4671.6     0.1       0  4823.8    0.04       0  5624.3    0.05       0
  5940.5    0.12       0  6028.7    0.05       0
Bank Sta=4663.9,4671.6
Exp/Cntr=0.3,0.1