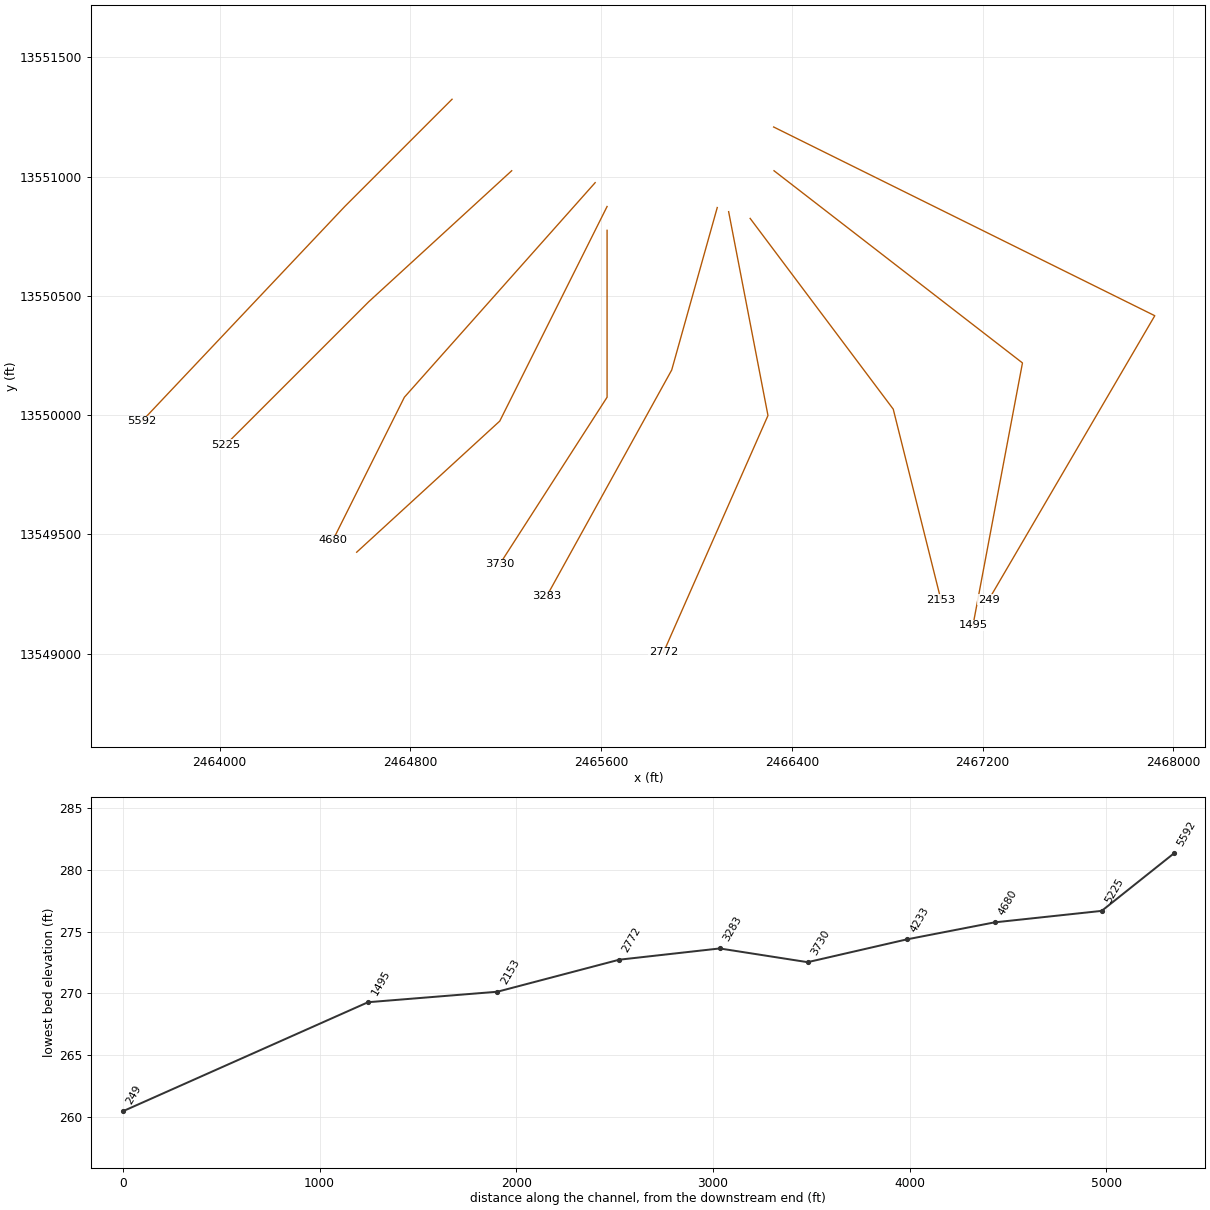
HEC-RAS study WOODS CREEK.prj: WOODS CREEK Base Level Engineering

--- WOODS CREEK.g01 (geometry) --- (continued)

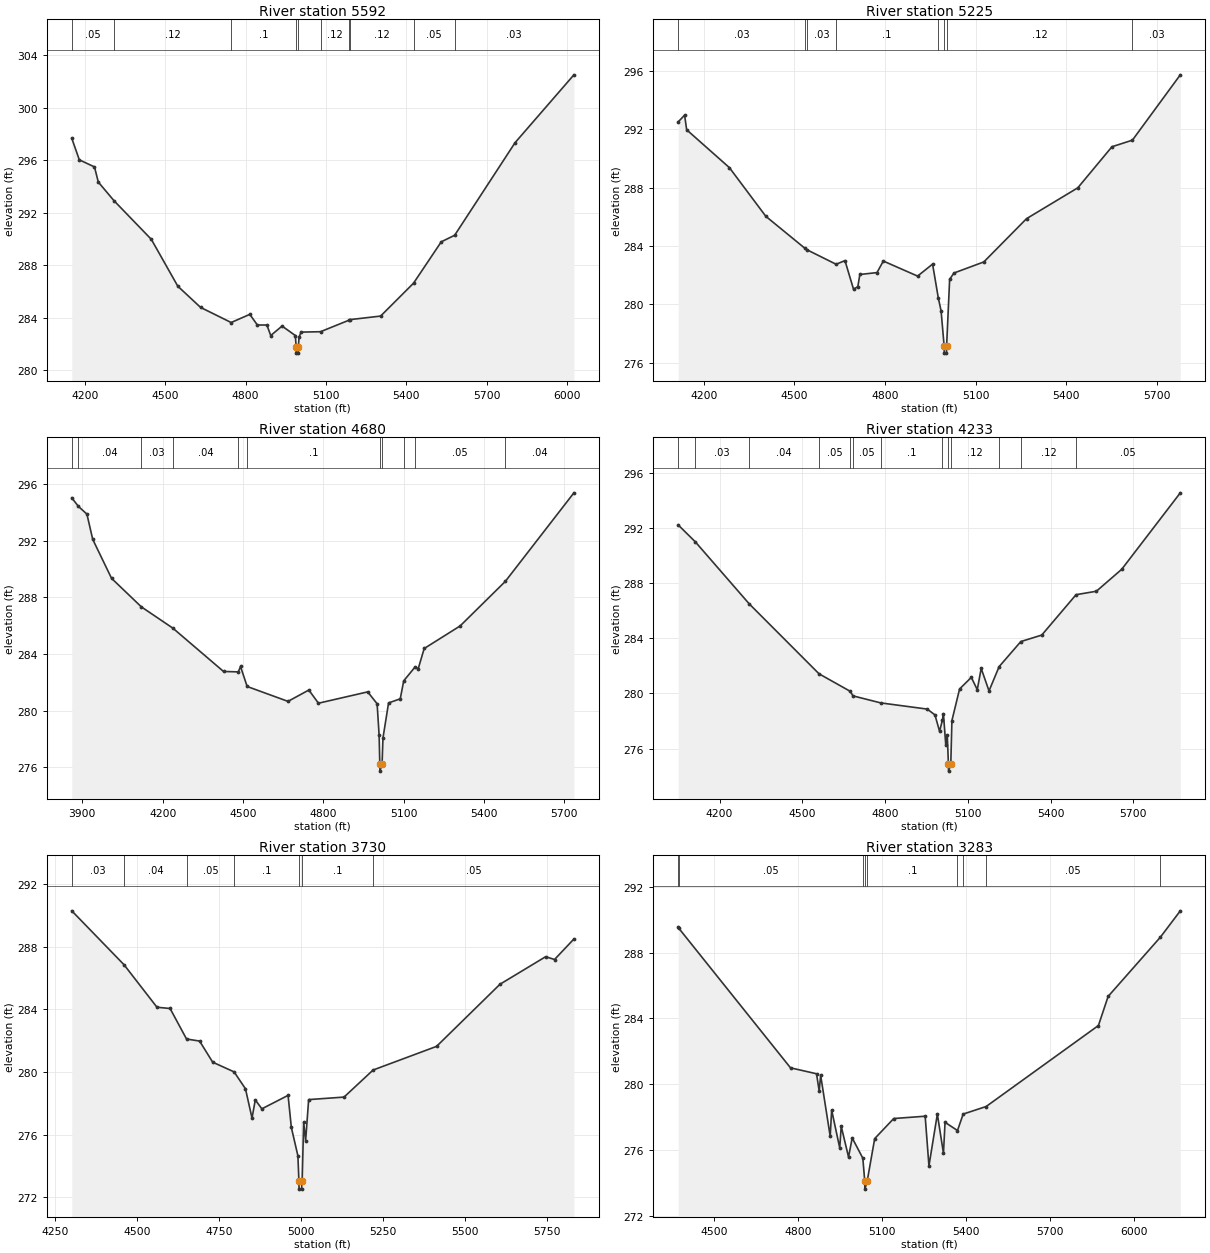
Type RM Length L Ch R = 1,5592,367,367,367
BEGIN DESCRIPTION:
WOODS CREEK 14.0
END DESCRIPTION:
XS GIS Cut Line= 3
      2464974.97     13551324.97      2464525.00     13550875.00
      2463675.00     13549975.00
#Sta/Elev= 30
  4151.4  297.67  4179.6  296.03  4236.2  295.49  4250.4  294.34  4308.6  292.93
  4448.3  289.98  4547.3  286.41  4632.2  284.80  4746.3  283.65  4815.9  284.27
  4844.2  283.46  4879.8  283.46  4894.0  282.66  4936.4  283.38  4985.8  282.66
  4989.0  281.82  4989.5  281.32  4996.7  281.32  4997.2  281.82  4999.9  282.54
  5007.2  282.92  5079.9  282.95  5185.4  283.82  5189.8  283.87  5304.2  284.14
  5427.0  286.64  5530.5  289.79  5580.6  290.29  5806.2  297.34  6025.7  302.50
#Mann=10,-1,0
  4151.4    0.05       0  4308.6    0.12       0  4746.3     0.1       0
  4989.0    0.05       0  4997.2     0.1       0  5079.9    0.12       0
  5185.4    0.05       0  5189.8    0.12       0  5427.0    0.05       0
  5580.6    0.03       0
Bank Sta=4989,4997.2
Exp/Cntr=0.3,0.1

Type RM Length L Ch R = 1,5225,545,545,545
BEGIN DESCRIPTION:
WOODS CREEK 13.0
END DESCRIPTION:
XS GIS Cut Line= 3
      2465225.02     13551025.02      2464625.00     13550475.00
      2464025.00     13549875.00
#Sta/Elev= 30
  4115.3  292.49  4136.6  292.95  4143.4  291.95  4284.9  289.36  4405.5  286.03
  4535.6  283.83  4540.8  283.75  4638.2  282.75  4667.5  283.00  4695.9  281.04
  4710.1  281.22  4716.8  282.05  4773.6  282.18  4794.5  282.97  4908.0  281.94
  4957.6  282.76  4976.6  280.44  4985.8  279.56  4995.8  277.17  4996.3  276.67
  5003.6  276.67  5004.1  277.17  5014.1  281.72  5028.3  282.15  5127.3  282.91
  5268.7  285.87  5438.4  287.98  5551.5  290.79  5619.2  291.24  5777.8  295.71
#Mann=8,-1,0
  4115.3    0.03       0  4535.6    0.12       0  4540.8    0.03       0
  4638.2     0.1       0  4976.6    0.12       0  4995.8    0.05       0
  5004.1    0.12       0  5619.2    0.03       0
Bank Sta=4995.8,5004.1
Exp/Cntr=0.3,0.1

Type RM Length L Ch R = 1,4680,447,447,447
BEGIN DESCRIPTION:
WOODS CREEK 12.0
END DESCRIPTION:
XS GIS Cut Line= 3
      2465575.01     13550975.02      2464775.00     13550075.00
      2464475.00     13549475.00
#Sta/Elev= 30
  3860.5  295.02  3885.4  294.41  3917.0  293.87  3938.7  292.09  4009.0  289.34
  4120.1  287.33  4238.3  285.82  4427.1  282.77  4482.4  282.74  4490.6  283.12
  4515.4  281.71  4667.9  280.66  4745.7  281.46  4781.6  280.53  4965.6  281.33
  5000.7  280.49  5008.2  278.26  5010.7  276.24  5011.2  275.74  5019.2  276.24
  5022.5  278.07  5043.4  280.55  5087.0  280.84  5100.1  282.11  5142.6  283.09
  5154.1  282.96  5176.5  284.39  5310.6  285.98  5479.3  289.12  5735.5  295.37
#Mann=11,-1,0
  3860.5    0.03       0  3885.4    0.04       0  4120.1    0.03       0
  4238.3    0.04       0  4482.4    0.12       0  4515.4     0.1       0
  5010.7    0.05       0  5019.2     0.1       0  5100.1    0.12       0
  5142.6    0.05       0  5479.3    0.04       0
Bank Sta=5010.7,5019.2
Exp/Cntr=0.3,0.1

Type RM Length L Ch R = 1,4233,503,503,503
BEGIN DESCRIPTION:
WOODS CREEK 11.0
END DESCRIPTION:
XS GIS Cut Line= 3
      2465625.00     13550875.00      2465175.00     13549975.00
      2464574.98     13549424.98
#Sta/Elev= 30
  4050.0  292.22  4111.9  291.00  4307.3  286.50  4560.6  281.42  4673.7  280.15
  4683.6  279.82  4784.2  279.31  4952.8  278.86  4980.8  278.44  4997.5  277.25
  5007.8  278.06  5011.5  278.53  5019.9  276.29  5025.5  276.97  5029.6  274.86
  5030.1  274.36  5038.2  274.86  5042.3  278.03  5070.1  280.32  5112.6  281.16
  5134.2  280.27  5148.4  281.81  5176.8  280.18  5213.4  281.94  5292.1  283.76
  5367.9  284.23  5492.3  287.16  5565.9  287.41  5657.7  289.00  5870.2  294.55
#Mann=13,-1,0
  4050.0    0.04       0  4111.9    0.03       0  4307.3    0.04       0
  4560.6    0.05       0  4673.7     0.1       0  4683.6    0.05       0
  4784.2     0.1       0  5007.8    0.12       0  5029.6    0.05       0
  5038.2    0.12       0  5213.4    0.05       0  5292.1    0.12       0
  5492.3    0.05       0
Bank Sta=5029.6,5038.2
Exp/Cntr=0.3,0.1

Type RM Length L Ch R = 1,3730,447,447,447
BEGIN DESCRIPTION:
WOODS CREEK 10.0
END DESCRIPTION:
XS GIS Cut Line= 3
      2465625.00     13550775.03      2465625.00     13550075.00
      2465175.00     13549375.00
#Sta/Elev= 30
  4300.3  290.30  4460.0  286.85  4560.3  284.14  4600.3  284.06  4650.5  282.11
  4690.3  281.98  4730.3  280.63  4795.7  280.01  4830.3  278.93  4850.3  277.06
  4860.3  278.22  4880.3  277.65  4960.3  278.51  4970.3  276.46  4990.3  274.65
  4993.4  273.02  4993.9  272.52  5001.7  272.52  5002.2  273.02  5003.3  273.02
  5007.9  276.81  5013.9  275.62  5023.1  278.24  5131.1  278.40  5219.8  280.13
  5413.4  281.64  5607.0  285.61  5746.3  287.37  5773.4  287.19  5832.5  288.50
#Mann=7,-1,0
  4300.3    0.03       0  4460.0    0.04       0  4650.5    0.05       0
  4795.7     0.1       0  4993.4    0.05       0  5002.2     0.1       0
  5219.8    0.05       0
Bank Sta=4993.4,5002.2
Exp/Cntr=0.3,0.1

Type RM Length L Ch R = 1,3283,511,511,511
BEGIN DESCRIPTION:
Mapping XS d5804a66
END DESCRIPTION:
XS GIS Cut Line= 3
      2466087.01     13550870.70      2465896.04     13550189.28
      2465371.21     13549239.40
#Sta/Elev= 30
  4371.0  289.57  4372.8  289.49  4772.1  281.00  4865.0  280.64  4874.5  279.59
  4879.7  280.55  4913.8  276.84  4919.0  278.43  4947.9  276.13  4953.1  277.45
  4979.3  275.58  4992.4  276.74  5030.3  275.51  5037.1  274.13  5037.6  273.63
  5046.0  274.13  5072.7  276.70  5140.7  277.92  5252.9  278.06  5266.4  275.04
  5296.4  278.19  5318.2  275.81  5323.9  277.69  5368.3  277.19  5388.6  278.19
  5470.6  278.65  5871.5  283.57  5906.2  285.34  6092.8  288.94  6163.9  290.54
#Mann=9,-1,0
  4371.0    0.03       0  4372.8    0.05       0  5030.3     0.1       0
  5037.1    0.05       0  5046.0     0.1       0  5368.3   0.013       0
  5388.6     0.1       0  5470.6    0.05       0  6092.8    0.03       0
Bank Sta=5037.1,5046
Exp/Cntr=0.3,0.1

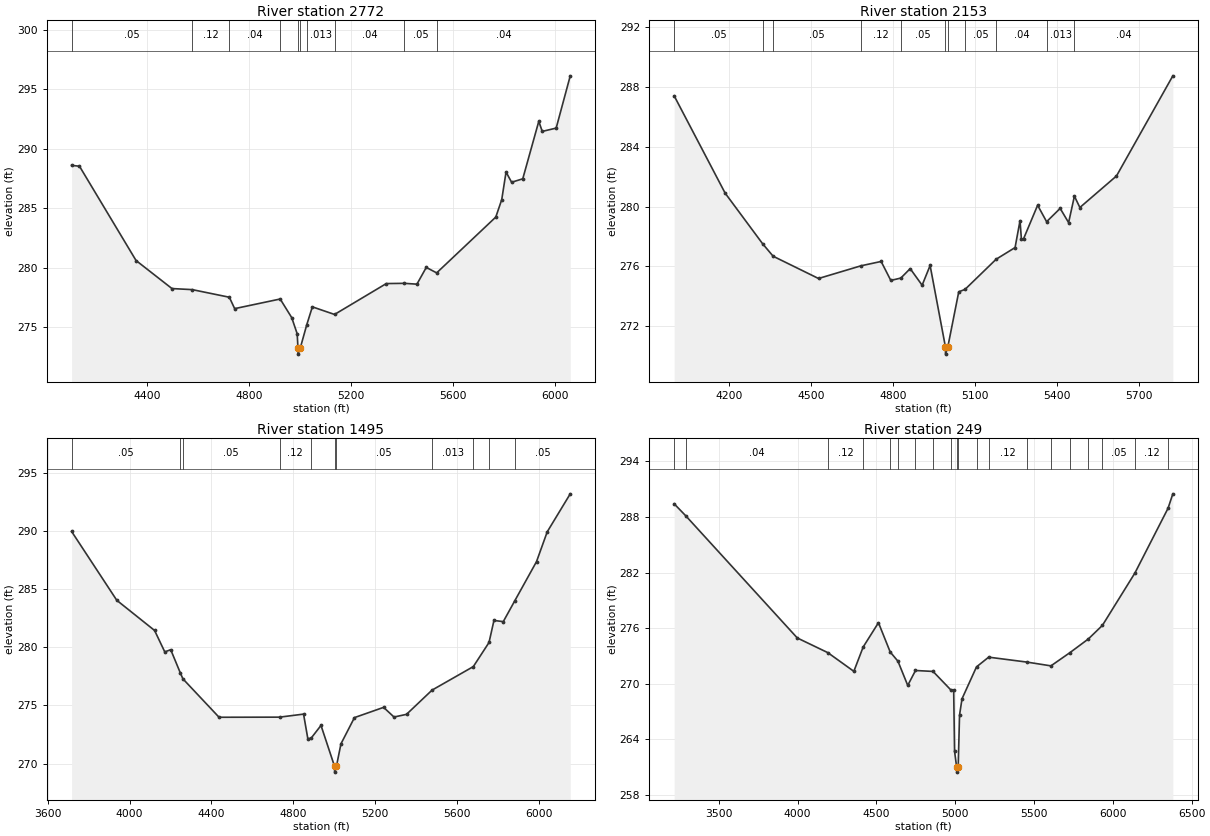
Type RM Length L Ch R = 1,2772,619,619,619
BEGIN DESCRIPTION:
Mapping XS c01ef77b
END DESCRIPTION:
XS GIS Cut Line= 3
      2466134.75     13550853.37      2466299.68     13549998.31
      2465861.32     13549004.41
#Sta/Elev= 30
  4104.5  288.61  4135.4  288.54  4357.5  280.60  4498.4  278.24  4578.1  278.15
  4723.5  277.51  4744.5  276.55  4923.1  277.36  4968.5  275.79  4989.9  274.43
  4992.9  273.22  4993.4  272.72  5001.8  273.22  5027.4  275.19  5049.4  276.70
  5136.5  276.06  5339.6  278.66  5410.5  278.68  5459.8  278.61  5496.5  280.02
  5537.3  279.56  5769.4  284.26  5792.7  285.73  5809.6  288.05  5831.4  287.19
  5875.2  287.48  5938.1  292.32  5951.7  291.47  6006.3  291.75  6061.6  296.15
#Mann=10,-1,0
  4104.5    0.05       0  4578.1    0.12       0  4723.5    0.04       0
  4923.1    0.05       0  4992.9    0.05       0  5001.8    0.05       0
  5027.4   0.013       0  5136.5    0.04       0  5410.5    0.05       0
  5537.3    0.04       0
Bank Sta=4992.9,5001.8
Exp/Cntr=0.3,0.1

Type RM Length L Ch R = 1,2153,658,658,658
BEGIN DESCRIPTION:
WOODS CREEK 7.0
END DESCRIPTION:
XS GIS Cut Line= 3
      2466224.98     13550825.03      2466825.00     13550025.00
      2467025.01     13549224.96
#Sta/Elev= 30
  4000.2  287.41  4186.7  280.90  4323.6  277.52  4362.3  276.68  4528.4  275.19
  4683.8  276.04  4757.5  276.33  4792.9  275.06  4829.6  275.22  4863.8  275.85
  4907.5  274.74  4936.7  276.06  4992.6  270.63  4993.1  270.13  5001.7  270.63
  5041.5  274.30  5064.4  274.46  5178.4  276.48  5247.6  277.26  5265.7  279.06
  5270.8  277.81  5278.5  277.84  5330.1  280.09  5363.0  278.99  5412.6  279.88
  5443.5  278.93  5464.7  280.70  5484.7  279.94  5618.7  282.05  5824.9  288.75
#Mann=11,-1,0
  4000.2    0.05       0  4323.6    0.12       0  4362.3    0.05       0
  4683.8    0.12       0  4829.6    0.05       0  4992.6    0.04       0
  5001.7    0.05       0  5064.4    0.05       0  5178.4    0.04       0
  5363.0   0.013       0  5464.7    0.04       0
Bank Sta=4992.6,5001.7
Exp/Cntr=0.3,0.1

Type RM Length L Ch R = 1,1495,1246,1246,1246
BEGIN DESCRIPTION:
WOODS CREEK 6.0
END DESCRIPTION:
XS GIS Cut Line= 3
      2466325.03     13551024.98      2467366.86     13550218.94
      2467159.31     13549118.57
#Sta/Elev= 30
  3716.8  289.94  3937.7  284.03  4122.4  281.44  4172.2  279.60  4201.2  279.79
  4248.3  277.79  4260.7  277.29  4437.4  273.99  4733.3  274.00  4850.4  274.26
  4871.3  272.15  4887.2  272.19  4935.6  273.29  5001.8  269.78  5002.3  269.28
  5011.0  269.78  5033.2  271.71  5099.1  273.96  5241.6  274.84  5292.4  274.01
  5353.5  274.24  5478.4  276.32  5680.1  278.34  5756.8  280.41  5780.9  282.30
  5826.5  282.20  5881.8  283.96  5988.9  287.35  6041.3  289.91  6153.8  293.17
#Mann=11,-1,0
  3716.8    0.05       0  4248.3    0.04       0  4260.7    0.05       0
  4733.3    0.12       0  4887.2    0.05       0  5001.8    0.05       0
  5011.0    0.05       0  5478.4   0.013       0  5680.1    0.05       0
  5756.8   0.013       0  5881.8    0.05       0
Bank Sta=5001.8,5011
Exp/Cntr=0.3,0.1

Type RM Length L Ch R = 1,249,0,0,0
BEGIN DESCRIPTION:
WOODS CREEK 5.0
END DESCRIPTION:
XS GIS Cut Line= 3
      2466323.48     13551208.50      2467921.69     13550416.94
      2467225.01     13549225.01
#Sta/Elev= 30
  3216.5  289.42  3290.4  288.12  3997.7  274.94  4191.1  273.36  4356.5  271.34
  4415.8  273.97  4512.7  276.59  4587.1  273.43  4636.4  272.43  4698.5  269.82
  4747.7  271.43  4859.0  271.33  4970.3  269.36  4990.0  269.29  4995.6  262.70
  5009.2  260.96  5009.7  260.46  5018.5  260.96  5027.2  266.62  5042.9  268.38
  5134.8  271.82  5212.0  272.87  5453.8  272.34  5607.1  271.93  5726.2  273.34
  5844.2  274.83  5933.7  276.30  6139.9  281.95  6350.4  288.95  6380.6  290.50
#Mann=20,-1,0
  3216.5    0.05       0  3290.4    0.04       0  4191.1    0.12       0
  4415.8     0.1       0  4587.1    0.05       0  4636.4   0.013       0
  4747.7    0.05       0  4859.0    0.05       0  4970.3    0.12       0
  5009.2    0.05       0  5018.5    0.12       0  5134.8     0.1       0
  5212.0    0.12       0  5453.8    0.05       0  5607.1    0.12       0
  5726.2    0.05       0  5844.2    0.12       0  5933.7    0.05       0
  6139.9    0.12       0  6350.4    0.05       0
Bank Sta=5009.2,5018.5
Exp/Cntr=0.3,0.1

Chan Stop Cuts=-1