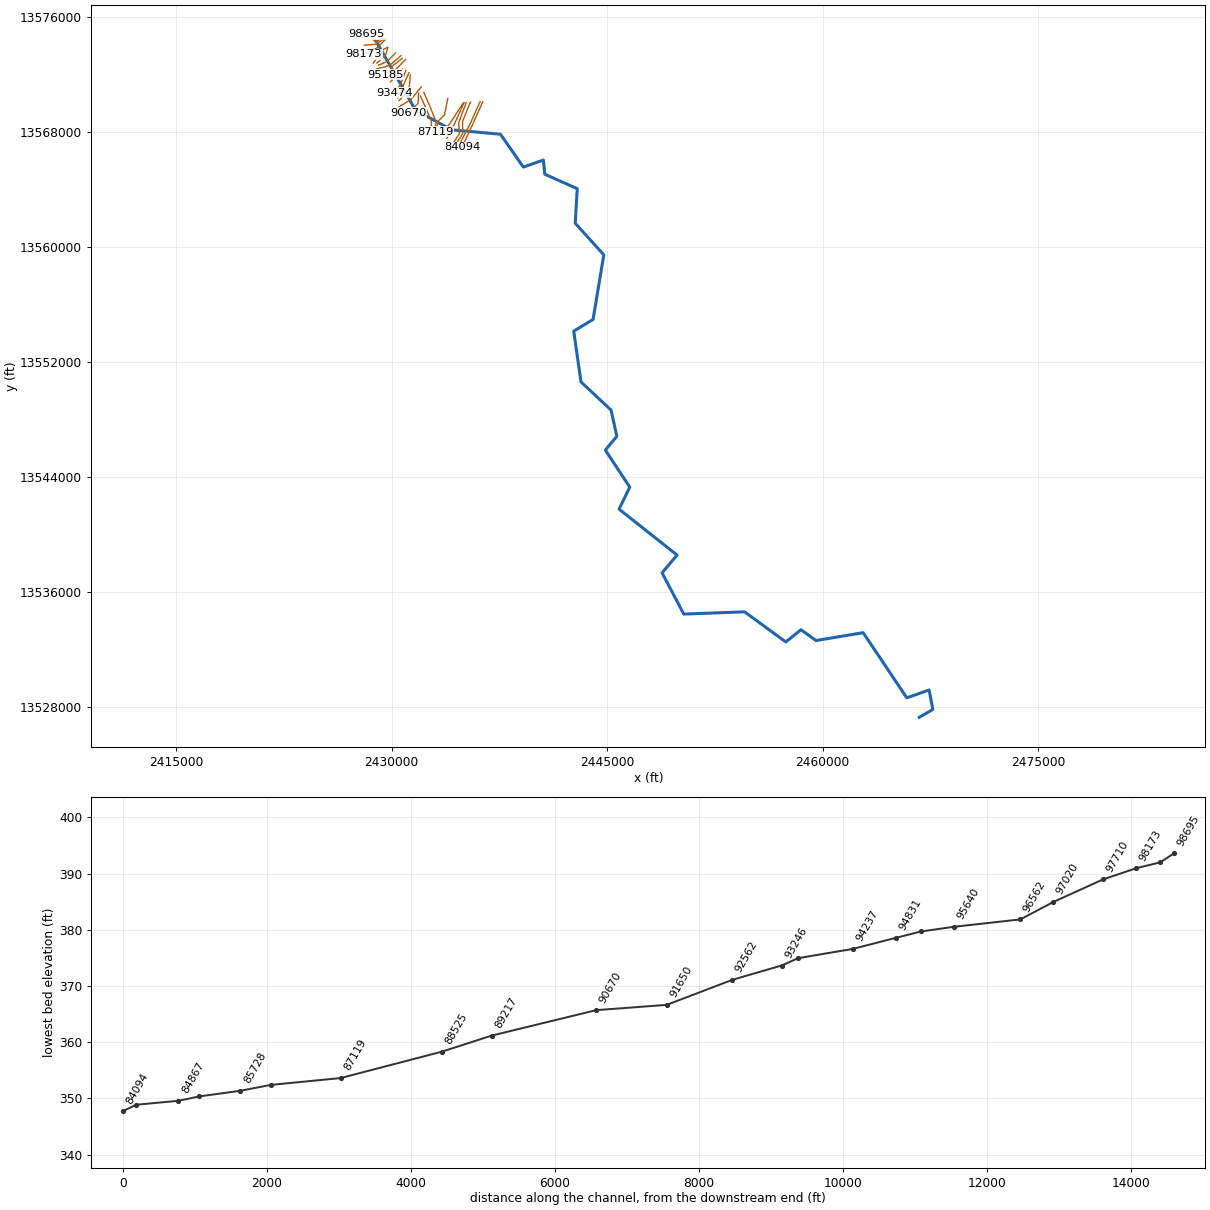
--- YORKTOWN CREEK.prj (project) ---

Proj Title=YORKTOWN CREEK Base Level Engineering
Current Plan=p01
Default Exp/Contr=0.3,0.1
English Units
Geom File=g01
Flow File=f01
Plan File=p01
Y Axis Title=Elevation
X Axis Title(PF)=Main Channel Distance
X Axis Title(XS)=Station
BEGIN DESCRIPTION:
YORKTOWN CREEK
END DESCRIPTION:
DSS Export Rating Curves= 0
DSS Export Rating Curve Sorted= 0
DSS Export Volume Flow Curves= 0
DXF OffsetX= 0
DXF OffsetY= 0
DXF ScaleX= 1
DXF ScaleY= 10

--- YORKTOWN CREEK.p01 (plan) ---

Plan Title=Multiple Run
Program Version=4.10
Short Identifier=Multiple
Geom File=g01
Flow File=f01
Subcritical Flow
K Sum by GR= 0
Std Step Tol= 0.01
Critical Tol= 0.01
Num of Std Step Trials= 20
Max Error Tol= 0.3
Flow Tol Ratio= 0.001
Split Flow NTrial= 30
Split Flow Tol= 0.02
Split Flow Ratio= 0.02
Log Output Level= 0
Friction Slope Method= 1
Unsteady Friction Slope Method= 2
Unsteady Bridges Friction Slope Method= 1
Parabolic Critical Depth
Global Vel Dist= 1 , 1 , 1
Global Log Level= 0
CheckData=True
Encroach Param=-1 ,0,0, 0
BEGIN DESCRIPTION:
Multiple Run
END DESCRIPTION:
Computation Interval=1HOUR
Output Interval=1HOUR
Run HTab= 0
Run UNet= 0
Run PostProcess= 0
Run WQNet= 0
UNET Theta= 1
UNET Theta Warmup= 1
UNET ZTol= 0.02
UNET ZSATol= 0.05
UNET MxIter= 20
UNET MaxInSteps= 0
UNET DtIC= 0
UNET DtMin= 0
UNET MaxCRTS= 20
UNET WFStab= 2
UNET SFStab= 1
UNET WFX= 1
UNET SFX= 1
UNET DSS MLevel= 4
UNET DZMax Abort= 100
UNET Convert EG Bridges= 0
UNET Use Existing IB Tables=-1
UNET Froude Reduction=False
UNET Froude Limit= 1
UNET Froude Power= 10
UNET Time Slicing=0,0, 5
UNET Junction Losses=0
Instantaneous Interval=1HOUR
Write IC File= 0
Write IC File at Sim End=0
Echo Input=False
Echo Parameters=False
Echo Output=False
Write Detailed= 0
WQ AD Non Conservative
WQ ULTIMATE=-1
WQ Max Comp Step=1HOUR
WQ Output Interval=15MIN
WQ Output Selected Increments= 0
WQ Output face flow=0
WQ Output face velocity=0
WQ Output face area=0
WQ Output face dispersion=0
WQ Output cell volume=0
WQ Output cell surface area=0
WQ Output cell continuity=0
WQ Output cumulative cell continuity=0
WQ Output face conc=0
WQ Output face dconc_dx=0
WQ Output face courant=0
WQ Output face peclet=0
WQ Output face adv mass=0
WQ Output face disp mass=0
WQ Output cell mass=0
WQ Output cell source sink temp=0
WQ Output cell source sink nsm=0
WQ Output MaxMinRange=-1
WQ Daily Max Min Mean=-1
WQ Daily Range=0
WQ Daily Time=0
WQ Create Restart=0
WQ Fixed Restart=0
WQ System Summary=0
WQ Use Fixed Temperature=0
Sorting and Armoring Iterations= 10
XS Update Threshold= 0.02
Hydraulics Update Threshold= 0.02
Energy Slope Method= 1
Volume Change Method= 0
XS Weighting Method= 0
Number of US Weighted Cross Sections= 1
Number of DS Weighted Cross Sections= 1
Upstream XS Weight=0.25
Main XS Weight=0.5
Downstream XS Weight=0.25
Number of DS XS's Weighted with US Boundary= 1
Upstream Boundary Weight= 1
Weight of XSs Associated with US Boundary= 0
Number of US XS's Weighted with DS Boundary= 1
Downstream Boundary Weight= 0.5
Weight of XSs Associated with DS Boundary= 0.5
Sediment Output Level= 4
Mass or Volume Output= 0
Output Increment Type= 1
Profile and TS Output Increment= 10
XS Output Flag= 0
XS Output Increment= 10
Disregard all LS=0
Disregard all Conn=0
Disregard all Breaches=0
Disregard all Pumps=0

--- YORKTOWN CREEK.f01 (steady flow) ---

Flow Title=Multiple
Number of Profiles=7
Profile Names=10-year,25-year,50-year,1pct_min,100-year,1pct_plu,500-year
River Rch & RM= YORKTOWN CREEK,Reach-1,98695
     581     935    1253     814    1624    3240    2701
River Rch & RM= YORKTOWN CREEK,Reach-1,97020
     778    1271    1720    1127    2248    4485    3806
River Rch & RM= YORKTOWN CREEK,Reach-1,93474
     923    1518    2064    1357    2708    5403    4619
River Rch & RM= YORKTOWN CREEK,Reach-1,89217
    1005    1657    2257    1486    2964    5914    5069
River Rch & RM= YORKTOWN CREEK,Reach-1,85728
    1138    1887    2579    1702    3396    6777    5844
River Rch & RM= YORKTOWN CREEK,Reach-1,83085
    1183    1963    2686    1774    3540    7064    6101
River Rch & RM= YORKTOWN CREEK,Reach-1,81352
    1316    2195    3013    1996    3983    7948    6905
River Rch & RM= YORKTOWN CREEK,Reach-1,79896
    1385    2311    3173    2102    4194    8368    7268
River Rch & RM= YORKTOWN CREEK,Reach-1,75570
    1513    2534    3488    2316    4621    9219    8045
River Rch & RM= YORKTOWN CREEK,Reach-1,72726
    1616    2713    3739    2485    4959    9895    8654
River Rch & RM= YORKTOWN CREEK,Reach-1,65548
    1618    2714    3739    2484    4956    9889    8641
River Rch & RM= YORKTOWN CREEK,Reach-1,64806
    2778    4769    6674    4498    8975   17908   16103
River Rch & RM= YORKTOWN CREEK,Reach-1,60594
    2976    5125    7188    4854    9685   19324   17444
River Rch & RM= YORKTOWN CREEK,Reach-1,59628
    3175    5477    7690    5198   10371   20692   18714
River Rch & RM= YORKTOWN CREEK,Reach-1,52863
    4196    7305   10320    7014   13994   27921   25527
River Rch & RM= YORKTOWN CREEK,Reach-1,51759
    4874    8518   12063    8210   16381   32685   29933
River Rch & RM= YORKTOWN CREEK,Reach-1,44817
    5864   10302   14643    9998   19948   39802   36681
River Rch & RM= YORKTOWN CREEK,Reach-1,42221
    5931   10421   14814   10115   20183   40270   37119
River Rch & RM= YORKTOWN CREEK,Reach-1,41721
    5954   10459   14865   10148   20248   40400   37222
River Rch & RM= YORKTOWN CREEK,Reach-1,39309
    6118   10750   15279   10431   20813   41527   38260
River Rch & RM= YORKTOWN CREEK,Reach-1,35718
    6092   10695   15194   10368   20686   41275   37988
River Rch & RM= YORKTOWN CREEK,Reach-1,32863
    6112   10720   15219   10377   20704   41310   37962
River Rch & RM= YORKTOWN CREEK,Reach-1,29019
    6316   11085   15746   10740   21430   42758   39325
River Rch & RM= YORKTOWN CREEK,Reach-1,26590
    6287   11025   15650   10668   21285   42468   39004
River Rch & RM= YORKTOWN CREEK,Reach-1,25341
    6432   11281   16017   10919   21787   43471   39935
River Rch & RM= YORKTOWN CREEK,Reach-1,20258
    6445   11301   16041   10932   21813   43523   39959
River Rch & RM= YORKTOWN CREEK,Reach-1,16462
    6567   11515   16346   11141   22229   44353   40723
River Rch & RM= YORKTOWN CREEK,Reach-1,13990
    6590   11553   16397   11173   22292   44479   40819
River Rch & RM= YORKTOWN CREEK,Reach-1,12111
    6569   11504   16316   11110   22167   44230   40533
River Rch & RM= YORKTOWN CREEK,Reach-1,8907
    7795   13708   19499   13312   26560   52995   48808
Boundary for River Rch & Prof#=YORKTOWN CREEK,Reach-1,1
Up Type=0
Dn Type=3
Dn Slope=0.002
Boundary for River Rch & Prof#=YORKTOWN CREEK,Reach-1,2
Up Type=0
Dn Type=3
Dn Slope=0.002
Boundary for River Rch & Prof#=YORKTOWN CREEK,Reach-1,3
Up Type=0
Dn Type=3
Dn Slope=0.002
Boundary for River Rch & Prof#=YORKTOWN CREEK,Reach-1,4
Up Type=0
Dn Type=3
Dn Slope=0.002
Boundary for River Rch & Prof#=YORKTOWN CREEK,Reach-1,5
Up Type=0
Dn Type=3
Dn Slope=0.002
Boundary for River Rch & Prof#=YORKTOWN CREEK,Reach-1,6
Up Type=0
Dn Type=3
Dn Slope=0.002
Boundary for River Rch & Prof#=YORKTOWN CREEK,Reach-1,7
Up Type=0
Dn Type=3
Dn Slope=0.002

--- YORKTOWN CREEK.g01 (geometry) ---

Geom Title=Existing Conditions
Program Version=4.10

River Reach=YORKTOWN CREEK  ,Reach-1
Reach XY= 30
        2428875.       13574425.      2431664.59     13569535.16
      2434180.84     13568177.05      2437573.54     13567871.47
      2439168.79      13565582.8      2440563.42     13566073.61
      2440661.36     13565088.46      2442919.54     13564077.45
      2442778.31     13561676.74      2444767.68      13559474.9
      2444021.66     13554976.72       2442676.2      13554164.5
      2443177.06     13550630.85      2445273.39     13548668.97
       2445674.6     13546838.91      2444876.96     13545880.89
      2446575.06     13543305.01      2445830.46     13541772.54
      2449871.46     13538573.54      2448824.98      13537338.9
      2450335.76     13534465.32      2454569.06     13534622.74
      2457438.86     13532525.52      2458490.21      13533374.5
      2459545.18     13532624.71      2462823.45     13533171.25
       2465861.7     13528638.34      2467417.18     13529181.19
      2467671.25     13527826.55        2466725.       13527275.

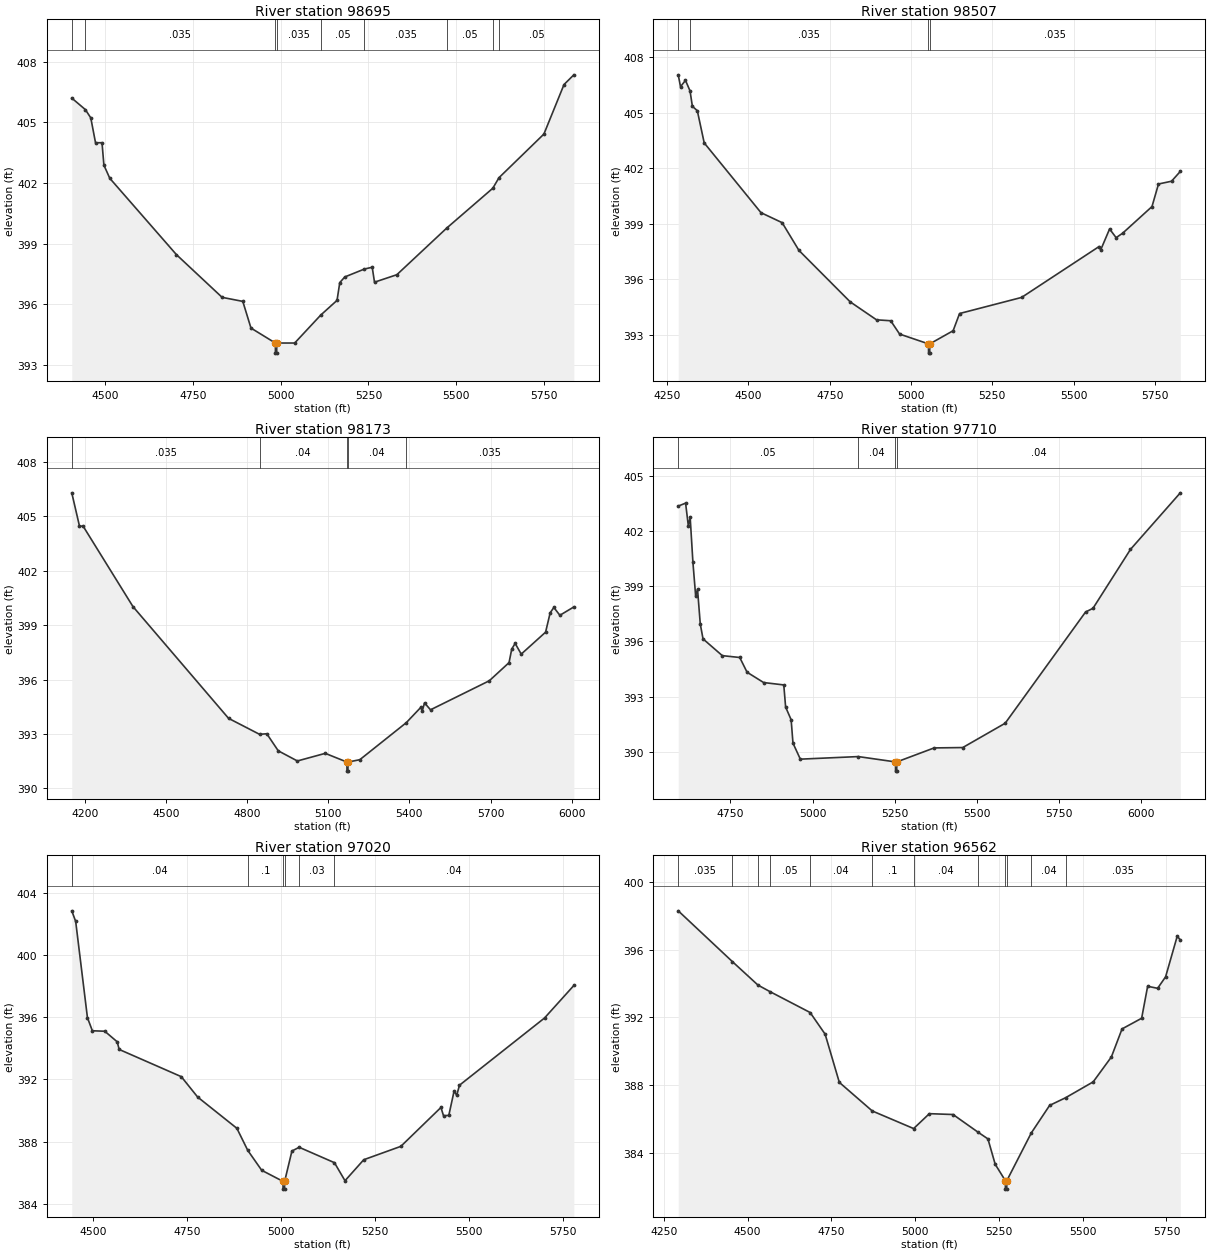
Type RM Length L Ch R = 1 ,98695   ,188,188,188
BEGIN DESCRIPTION:
YORKTOWN CREEK 138.0
END DESCRIPTION:
XS GIS Cut Line= 3
      2429475.03     13574575.01        2428875.       13574325.
      2428274.97     13574825.03
#Sta/Elev= 30
  4404.5   406.2  4443.2  405.63  4458.7  405.22  4472.2  403.99  4490.7  403.99
  4496.1  402.88  4512.9  402.23    4703  398.45    4833  396.34    4892  396.14
  4915.3  394.82  4984.8  394.08  4985.1  393.58  4988.6  393.58  4988.8  394.08
  5039.9  394.08    5114  395.46  5160.6  396.19  5168.4  397.07  5182.8  397.35
  5238.5  397.74  5260.9  397.83  5267.4  397.09  5331.1  397.46  5473.4  399.77
  5604.7  401.74  5622.2  402.26  5750.3  404.42  5807.6  406.87  5835.6  407.35
#Mann= 9 ,-1 , 0
  4404.5    .013       0  4443.2    .035       0  4984.8    .035       0
  4988.8    .035       0    5114     .05       0  5238.5    .035       0
  5473.4     .05       0  5604.7    .035       0  5622.2     .05       0
Bank Sta=4984.8,4988.8
XS Rating Curve= 0 ,0
Exp/Cntr=0.3,0.1

Type RM Length L Ch R = 1 ,98507   ,334,334,334
BEGIN DESCRIPTION:
Mapping XS c01848e8
END DESCRIPTION:
XS GIS Cut Line= 3
      2429529.85     13574541.28      2428876.61     13574126.77
      2428108.07     13574072.64
#Sta/Elev= 30
  4284.1  407.04  4291.1   406.4  4306.4  406.74  4320.4  406.17  4327.6  405.34
  4342.8   405.1    4364  403.36  4538.6  399.59  4603.7  399.05  4655.4  397.55
    4813  394.77  4893.9   393.8  4937.5  393.75  4964.9  393.03  5053.7   392.5
    5054     392  5057.5     392  5057.7   392.5  5129.5  393.21  5149.3  394.14
  5340.1  395.01  5578.4  397.76  5583.4  397.58  5610.7  398.71  5630.8  398.24
  5650.8  398.48  5741.1  399.92  5761.1  401.14  5801.2  401.29  5828.2  401.82
#Mann= 4 ,-1 , 0
  4284.1    .013       0  4320.4    .035       0  5053.7    .035       0
  5057.7    .035       0
Bank Sta=5053.7,5057.7
XS Rating Curve= 0 ,0
Exp/Cntr=0.3,0.1

Type RM Length L Ch R = 1 ,98173   ,463,463,463
BEGIN DESCRIPTION:
YORKTOWN CREEK 137.0
END DESCRIPTION:
XS GIS Cut Line= 3
      2429575.02     13574475.02        2428975.       13573875.
      2428068.57     13573433.02
#Sta/Elev= 30
  4151.2  406.29  4179.5  404.47  4193.7  404.44  4377.5  400.02  4731.1  393.86
  4845.6  392.98  4872.5  393.01  4914.9  392.07  4985.6  391.51  5088.8  391.93
  5168.9  391.45  5169.1  390.95  5172.6  390.95  5172.9  391.45  5216.6  391.58
  5388.4  393.62  5441.9  394.46  5447.5  394.26  5455.9  394.71  5478.1  394.33
  5695.4  395.93  5768.5  396.93  5778.5  397.68  5791.1  397.99  5813.6   397.4
  5903.7  398.61  5920.7  399.68  5934.3  399.97  5956.5  399.54  6008.2     400
#Mann= 5 ,-1 , 0
  4151.2    .035       0  4845.6     .04       0  5168.9     .04       0
  5172.9     .04       0  5388.4    .035       0
Bank Sta=5168.9,5172.9
XS Rating Curve= 0 ,0
Exp/Cntr=0.3,0.1

Type RM Length L Ch R = 1 ,97710   ,690,690,690
BEGIN DESCRIPTION:
YORKTOWN CREEK 136.0
END DESCRIPTION:
XS GIS Cut Line= 3
      2429725.01       13573925.        2429325.       13573725.
      2428724.99     13572824.99
#Sta/Elev= 30
  4590.9  403.34  4613.3   403.5  4621.7  402.26  4627.2  402.74  4635.6  400.29
    4644  398.45  4649.6  398.83    4658  396.94  4666.4  396.13  4725.1  395.22
  4778.2  395.12  4800.5  394.32  4850.9  393.76  4912.3  393.63  4917.9  392.43
  4934.7  391.74  4940.3  390.47  4962.7   389.6  5139.1  389.74  5252.5  389.45
  5252.7  388.95  5256.2  388.95  5256.5  389.45  5370.1  390.21  5457.3  390.23
  5586.5  391.55  5831.3  397.59  5853.9  397.79  5968.1  400.99  6119.8  404.06
#Mann= 4 ,-1 , 0
  4590.9     .05       0  5139.1     .04       0  5252.5     .05       0
  5256.5     .04       0
Bank Sta=5252.5,5256.5
XS Rating Curve= 0 ,0
Exp/Cntr=0.3,0.1

Type RM Length L Ch R = 1 ,97020   ,458,458,458
BEGIN DESCRIPTION:
YORKTOWN CREEK 135.0
END DESCRIPTION:
XS GIS Cut Line= 3
      2429724.99     13573874.96        2429575.       13573375.
      2428975.01     13572825.01
#Sta/Elev= 30
  4442.5  402.83  4452.9  402.15  4484.2  395.96  4497.3  395.12  4530.3  395.09
  4563.4  394.41  4568.6  393.92  4733.9  392.17  4777.4  390.86  4881.8  388.85
  4910.8  387.43  4947.9  386.15  5004.5  385.44  5004.8  384.94  5008.6  384.94
  5008.9  385.44  5028.3  387.39  5047.6  387.63  5141.4  386.64  5169.5  385.48
  5219.4  386.83  5318.1  387.69  5424.8  390.19  5431.6  389.66  5445.7  389.68
  5459.9  391.26  5466.7  390.97  5474.1  391.62  5700.4  395.94  5778.4  398.03
#Mann= 6 ,-1 , 0
  4442.5     .04       0  4910.8      .1       0  5004.5     .05       0
  5008.9      .1       0  5047.6     .03       0  5141.4     .04       0
Bank Sta=5004.5,5008.9
XS Rating Curve= 0 ,0
Exp/Cntr=0.3,0.1

Type RM Length L Ch R = 1 ,96562   ,922,922,922
BEGIN DESCRIPTION:
YORKTOWN CREEK 134.0
END DESCRIPTION:
XS GIS Cut Line= 3
      2430274.98     13573524.98        2429675.       13572925.
        2429075.       13572675.
#Sta/Elev= 30
  4292.9  398.29  4454.4  395.29  4530.9   393.9  4567.1  393.51  4686.5  392.28
  4731.3     391  4773.7  388.15    4872  386.46  4995.5  385.42  5042.4   386.3
  5113.1  386.25  5188.8  385.19  5217.2  384.81  5238.9  383.31  5269.2  382.34
  5269.5  381.84  5273.3  381.84  5273.6  382.34  5346.6  385.16  5401.4  386.79
  5448.8  387.24  5531.4  388.18  5585.6  389.65  5617.5  391.31    5676  391.94
  5693.9  393.83  5723.7  393.71  5747.5  394.39  5782.2  396.79  5791.4  396.57
#Mann= 12 ,-1 , 0
  4292.9    .035       0  4454.4     .05       0  4530.9    .035       0
  4567.1     .05       0  4686.5     .04       0    4872      .1       0
  4995.5     .04       0  5188.8     .05       0  5269.2     .04       0
  5273.6     .05       0  5346.6     .04       0  5448.8    .035       0
Bank Sta=5269.2,5273.6
XS Rating Curve= 0 ,0
Exp/Cntr=0.3,0.1

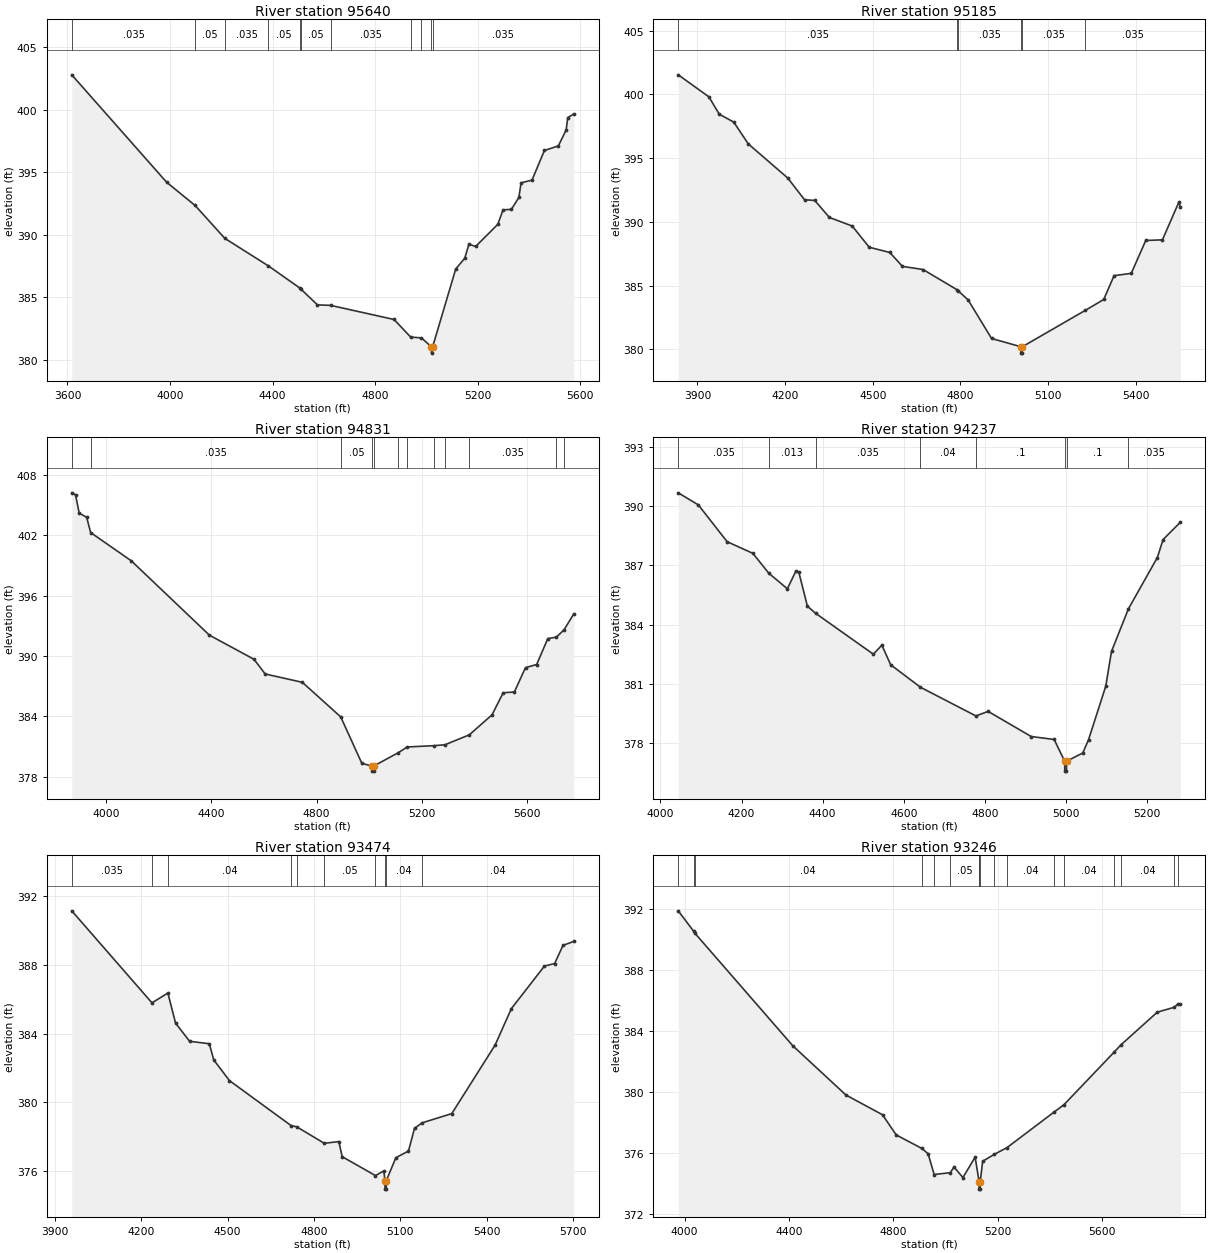
Type RM Length L Ch R = 1 ,95640   ,455,455,455
BEGIN DESCRIPTION:
Mapping XS fbad51cc
END DESCRIPTION:
XS GIS Cut Line= 4
      2430656.46     13573344.59      2429910.72     13572703.57
      2429552.32     13572566.84       2428975.9     13572434.89
#Sta/Elev= 30
  3616.8  402.79  3986.7   394.2  4097.9  392.34  4213.7  389.71  4383.6  387.51
  4505.4  385.75    4511  385.64  4574.9  384.39  4626.3  384.35  4873.9  383.22
  4938.7  381.81  4980.7  381.75  5019.8  381.03  5020.1  380.53  5024.3  381.03
  5114.4  387.26  5149.6  388.12  5165.7  389.23  5192.5  389.07  5278.4  390.83
    5299  391.99  5331.5  392.03  5360.6  392.98  5369.3  394.15  5411.9  394.37
  5460.3  396.74  5514.5   397.1  5545.3  398.39  5551.3  399.37  5575.1  399.66
#Mann= 11 ,-1 , 0
  3616.8    .035       0  4097.9     .05       0  4213.7    .035       0
  4383.6     .05       0  4505.4      .1       0    4511     .05       0
  4626.3    .035       0  4938.7      .1       0  4980.7    .035       0
  5019.8    .035       0  5024.3    .035       0
Bank Sta=5019.8,5024.3
XS Rating Curve= 0 ,0
Exp/Cntr=0.3,0.1

Type RM Length L Ch R = 1 ,95185   ,354,354,354
BEGIN DESCRIPTION:
Mapping XS 93240fbd
END DESCRIPTION:
XS GIS Cut Line= 4
      2430739.86     13573157.15      2429962.05     13572546.01
       2429892.6     13572261.28      2429539.25     13572004.93
#Sta/Elev= 30
  3834.3  401.54  3939.4  399.81  3974.7  398.45  4024.4  397.83  4074.1  396.12
  4209.3  393.44  4266.6  391.74  4301.9  391.68  4351.6  390.35  4430.2  389.67
    4488  388.01  4558.5   387.6  4601.9  386.51  4672.4  386.26  4788.4  384.68
    4793  384.58  4826.6  383.88  4906.9  380.85  5007.5   380.2  5007.8   379.7
  5011.7   379.7  5012.1   380.2  5228.2  383.06  5290.9  383.91  5326.4  385.78
  5385.2  385.96  5434.8  388.54  5491.9  388.59  5548.3  391.56  5553.1   391.2
#Mann= 6 ,-1 , 0
  3834.3    .035       0  4788.4     .05       0    4793    .035       0
  5007.5    .035       0  5012.1    .035       0  5228.2    .035       0
Bank Sta=5007.5,5012.1
XS Rating Curve= 0 ,0
Exp/Cntr=0.3,0.1

Type RM Length L Ch R = 1 ,94831   ,594,594,594
BEGIN DESCRIPTION:
YORKTOWN CREEK 131.0
END DESCRIPTION:
XS GIS Cut Line= 3
      2430975.03     13573075.03        2430175.       13572275.
      2429625.02     13571725.02
#Sta/Elev= 30
  3869.2  406.23  3883.4  406.04  3897.5  404.21  3925.8   403.8    3941  402.28
  4095.5  399.47  4392.5  392.08  4562.2  389.68  4604.6  388.22    4746  387.39
    4892  383.95  4972.3  379.33  5012.4  379.06  5012.7  378.56  5016.7  378.56
    5017  379.06  5110.6  380.39  5144.7  380.96  5245.8  381.09  5288.2  381.18
    5381  382.17  5467.3  384.16  5509.7  386.35  5552.1  386.43  5594.6  388.85
    5637  389.16  5679.4  391.74    5712  391.88  5741.1  392.61  5778.4   394.2
#Mann= 12 ,-1 , 0
  3869.2    .013       0    3941    .035       0    4892     .05       0
  5012.4     .05       0    5017     .05       0  5110.6    .035       0
  5144.7     .05       0  5245.8    .035       0  5288.2     .05       0
    5381    .035       0    5712     .05       0  5741.1    .035       0
Bank Sta=5012.4,5017
XS Rating Curve= 0 ,0
Exp/Cntr=0.3,0.1

Type RM Length L Ch R = 1 ,94237   ,763,763,763
BEGIN DESCRIPTION:
YORKTOWN CREEK 130.0
END DESCRIPTION:
XS GIS Cut Line= 3
      2430774.99     13572424.99        2430225.       13571825.
        2429925.       13571525.
#Sta/Elev= 30
  4043.9  390.67  4093.5  390.06  4164.4   388.2    4228  387.61  4267.5   386.6
    4313  385.82    4334  386.71  4341.4  386.65  4362.4  384.94  4382.6  384.58
  4525.2  382.51  4546.1  382.97  4567.7  381.98  4641.3  380.84  4778.1  379.39
  4808.2  379.62  4914.4  378.35    4971   378.2  4996.9   377.1  4997.2   376.6
  5001.3   376.6  5001.7   377.1  5041.7  377.52  5055.8  378.19  5098.2  380.89
  5112.4  382.65    5154   384.8  5225.5   387.4  5239.7  388.31  5282.1  389.18
#Mann= 8 ,-1 , 0
  4043.9    .035       0  4267.5    .013       0  4382.6    .035       0
  4641.3     .04       0  4778.1      .1       0  4996.9     .05       0
  5001.7      .1       0    5154    .035       0
Bank Sta=4996.9,5001.7
XS Rating Curve= 0 ,0
Exp/Cntr=0.3,0.1

Type RM Length L Ch R = 1 ,93474   ,228,228,228
BEGIN DESCRIPTION:
Mapping XS 1c564177
END DESCRIPTION:
XS GIS Cut Line= 3
      2430989.81     13572309.87      2430614.82     13571351.56
       2430191.2     13570775.15
#Sta/Elev= 30
  3958.8  391.15  4237.4  385.79  4292.7  386.36  4319.4  384.61  4368.3  383.55
  4436.5  383.41  4452.4  382.46  4506.7  381.26  4720.9  378.64  4740.3  378.57
  4836.1  377.61  4886.7  377.71  4898.3  376.83  5013.9  375.73  5043.1     376
  5046.8  375.44  5047.2  374.94  5051.4  374.94  5051.8  375.44  5084.8  376.77
  5128.7  377.16  5149.6  378.48    5176   378.8  5279.2  379.34  5429.6  383.33
    5486  385.45  5600.9  387.93  5636.4  388.08  5665.7  389.14  5703.2  389.37
#Mann= 10 ,-1 , 0
  3958.8    .035       0  4237.4    .013       0  4292.7     .04       0
  4720.9     .05       0  4740.3     .04       0  4836.1     .05       0
  5013.9     .04       0  5046.8     .05       0  5051.8     .04       0
    5176     .04       0
Bank Sta=5046.8,5051.8
XS Rating Curve= 0 ,0
Exp/Cntr=0.3,0.1

Type RM Length L Ch R = 1 ,93246   ,684,684,684
BEGIN DESCRIPTION:
Mapping XS 32e0cfda
END DESCRIPTION:
XS GIS Cut Line= 3
      2431205.11     13572164.08      2430774.55     13571177.95
      2430434.26     13570400.16
#Sta/Elev= 30
  3975.8  391.91  4034.4  390.58  4038.7  390.46  4415.1  383.05  4618.7  379.82
  4759.1  378.52  4811.4   377.2    4910  376.31  4933.9  375.96    4957   374.6
  5018.9  374.72    5033  375.09  5067.3   374.4  5114.1  375.74  5127.8   374.3
    5129  374.14  5129.3  373.64  5133.6  373.64    5134  374.14  5142.9  375.47
  5187.4  375.92  5236.7  376.37  5417.7  378.71  5454.6  379.18    5648  382.65
  5672.5   383.1  5812.6  385.26  5878.3  385.58  5890.4  385.78  5900.8  385.78
#Mann= 17 ,-1 , 0
  3975.8     .04       0  4034.4    .013       0  4038.7     .04       0
    4910     .05       0    4957    .013       0  5018.9     .05       0
  5127.8     .04       0    5129     .03       0    5134     .04       0
  5187.4    .013       0  5236.7     .04       0  5417.7    .013       0
  5454.6     .04       0    5648    .013       0  5672.5     .04       0
  5878.3    .013       0  5890.4     .04       0
Bank Sta=5129,5134
XS Rating Curve= 0 ,0
Exp/Cntr=0.3,0.1

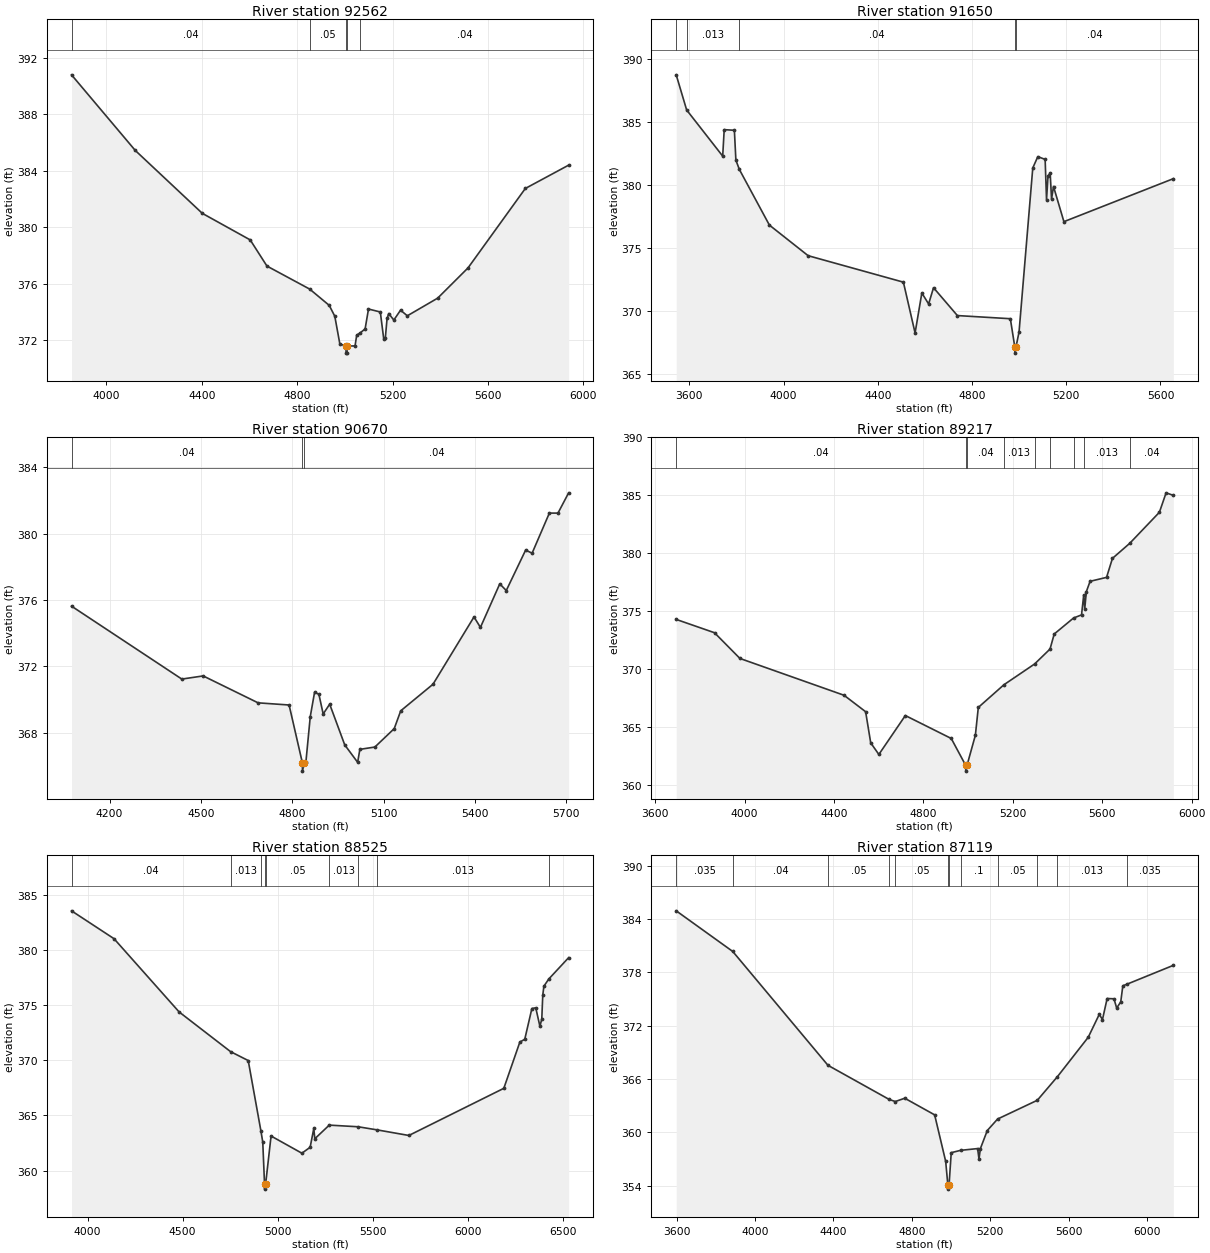
Type RM Length L Ch R = 1 ,92562   ,912,912,912
BEGIN DESCRIPTION:
Mapping XS dda91555
END DESCRIPTION:
XS GIS Cut Line= 3
      2431302.32     13572011.25       2431205.1     13570927.95
      2430510.65     13570212.66
#Sta/Elev= 30
  3853.6  390.79  4120.9  385.44    4402  380.99  4602.9  379.11  4673.1  377.26
  4852.4  375.63  4934.2  374.48  4957.6  373.71  4978.8  371.75  5004.5   371.6
  5004.9   371.1  5009.2   371.1  5009.6   371.6  5042.5  371.61  5049.5  372.37
  5063.8  372.53  5084.7  372.81  5098.9  374.22  5148.5  374.01  5162.7  372.12
  5169.6  372.18  5176.8  373.55  5183.8   373.9  5205.1  373.44  5233.4  374.14
  5261.7  373.74    5389  374.99  5516.3  377.13  5756.6  382.75  5938.2   384.4
#Mann= 5 ,-1 , 0
  3853.6     .04       0  4852.4     .05       0  5004.5     .05       0
  5009.6     .05       0  5063.8     .04       0
Bank Sta=5004.5,5009.6
XS Rating Curve= 0 ,0
Exp/Cntr=0.3,0.1

Type RM Length L Ch R = 1 ,91650   ,980,980,980
BEGIN DESCRIPTION:
Mapping XS 7876b7cf
END DESCRIPTION:
XS GIS Cut Line= 3
      2432066.22     13571171.02      2431338.95     13570274.76
      2430518.78     13569782.82
#Sta/Elev= 30
  3543.9  388.72  3588.3  385.93  3741.3  382.27  3747.7  384.37  3790.9  384.32
  3797.3  381.95  3812.1  381.21  3939.5   376.8  4104.1  374.37  4508.5  372.27
  4558.1  368.24  4586.8  371.41  4615.6  370.54  4636.4  371.83  4737.7  369.62
  4962.6  369.37  4981.4  367.14  4981.8  366.64  4986.6  367.14  4999.5  368.31
  5057.8  381.33  5079.2  382.23  5110.3  382.01  5116.2   378.8  5122.5  380.71
  5131.7  380.91  5137.5  378.87  5145.8  379.86    5190  377.07  5654.5  380.48
#Mann= 5 ,-1 , 0
  3543.9     .04       0  3588.3    .013       0  3812.1     .04       0
  4981.4     .04       0  4986.6     .04       0
Bank Sta=4981.4,4986.6
XS Rating Curve= 0 ,0
Exp/Cntr=0.3,0.1

Type RM Length L Ch R = 1 ,90670   ,1453,1453,1453
BEGIN DESCRIPTION:
Mapping XS 6946c4b7
END DESCRIPTION:
XS GIS Cut Line= 3
      2431878.72      13570726.6      2431837.05     13570018.23
      2431170.72     13569379.67
#Sta/Elev= 30
    4075  375.63  4437.2  371.24  4507.3  371.43  4687.7  369.81  4789.5  369.68
  4833.1   366.2  4833.5   365.7  4838.8   366.2  4844.8  366.27    4859  368.98
  4873.1  370.44  4887.3  370.33  4901.4  369.14  4922.8  369.73  4972.2  367.28
  5014.6  366.23  5021.9  367.01  5071.2  367.15  5134.8  368.26  5156.1  369.33
  5262.1  370.93  5396.7  374.98  5417.8  374.35  5481.3  376.97  5502.7  376.57
  5566.2     379  5587.6  378.82  5644.2  381.23  5672.5  381.23  5707.5  382.45
#Mann= 3 ,-1 , 0
    4075     .04       0  4833.1     .04       0  4838.8     .04       0
Bank Sta=4833.1,4838.8
XS Rating Curve= 0 ,0
Exp/Cntr=0.3,0.1

Type RM Length L Ch R = 1 ,89217   ,692,692,692
BEGIN DESCRIPTION:
Mapping XS 4e690654
END DESCRIPTION:
XS GIS Cut Line= 4
      2431996.76     13570525.19      2432371.77     13569733.51
       2432767.6     13568761.28      2432760.66     13568462.69
#Sta/Elev= 30
  3693.6  374.27    3865  373.12  3978.7   370.9  4444.7  367.72  4541.2   366.3
    4564  363.61  4600.4  362.61  4718.9  365.97  4924.3  363.99  4988.9  361.67
  4989.4  361.17  4994.9  361.67  5032.3  364.27  5045.4  366.67  5160.2  368.63
  5297.2  370.42  5366.3  371.71  5385.1  373.01  5471.5  374.39  5507.3  374.66
  5517.2   376.4  5521.6  375.17  5528.9  376.67  5545.6  377.56  5619.3   377.9
  5645.6  379.54    5723  380.84  5855.7  383.52  5885.7   385.2    5918  384.98
#Mann= 9 ,-1 , 0
  3693.6     .04       0  4988.9     .04       0  4994.9     .04       0
  5160.2    .013       0  5297.2     .04       0  5366.3    .013       0
  5471.5     .04       0  5517.2    .013       0    5723     .04       0
Bank Sta=4988.9,4994.9
XS Rating Curve= 0 ,0
Exp/Cntr=0.3,0.1

Type RM Length L Ch R = 1 ,88525   ,1406,1406,1406
BEGIN DESCRIPTION:
Mapping XS c5de8e1f
END DESCRIPTION:
XS GIS Cut Line= 4
      2432239.83     13570775.16      2432691.21     13569754.34
      2433107.88     13568684.89      2432996.76     13568351.54
#Sta/Elev= 30
  3915.4  383.57    4139  381.04  4481.6  374.39  4752.1  370.79    4845  369.98
  4911.9  363.58  4921.5  362.58  4930.7  358.81  4931.2  358.31  4936.8  358.81
  4965.2  363.13  5127.4  361.57  5170.8  362.11    5190  363.82  5195.3  362.88
  5271.3  364.12  5423.2  363.97  5522.4  363.69  5690.1  363.18  6189.7  367.46
  6274.1  371.66  6299.8  371.91  6337.3   374.7  6357.7  374.77  6379.5  373.09
  6389.4  373.74  6394.6  375.93  6400.6  376.73  6426.1  377.38  6530.7  379.32
#Mann= 9 ,-1 , 0
  3915.4     .04       0  4752.1    .013       0  4911.9     .05       0
  4930.7     .05       0  4936.8     .05       0  5271.3    .013       0
  5423.2     .05       0  5522.4    .013       0  6426.1     .04       0
Bank Sta=4930.7,4936.8
XS Rating Curve= 0 ,0
Exp/Cntr=0.3,0.1

Type RM Length L Ch R = 1 ,87119   ,966,966,966
BEGIN DESCRIPTION:
Mapping XS 017f172b
END DESCRIPTION:
XS GIS Cut Line= 4
       2433911.7     13570353.29      2433666.91     13569202.26
      2433255.45     13568806.42      2433052.33     13568046.01
#Sta/Elev= 30
  3598.1  384.91  3886.5  380.34    4372  367.54  4684.4   363.7  4715.3  363.47
  4763.5  363.84  4915.9  361.97  4972.2  356.74  4983.1  354.12  4983.6  353.62
  4989.5  354.12  5000.5  357.72  5048.3  357.98  5135.1  358.18    5142  357.01
  5149.2  358.18  5184.4  360.21  5236.8   361.5  5439.4  363.61  5542.2  366.27
  5699.2   370.7  5755.3  373.27  5771.7  372.69  5795.4  375.05  5830.3  375.02
  5844.1  373.98  5864.8  374.67  5875.5  376.48  5895.4  376.65  6132.9  378.78
#Mann= 12 ,-1 , 0
  3598.1    .035       0  3886.5     .04       0    4372     .05       0
  4684.4     .04       0  4715.3     .05       0  4983.1     .05       0
  4989.5     .05       0  5048.3      .1       0  5236.8     .05       0
  5439.4     .12       0  5542.2    .013       0  5895.4    .035       0
Bank Sta=4983.1,4989.5
XS Rating Curve= 0 ,0
Exp/Cntr=0.3,0.1

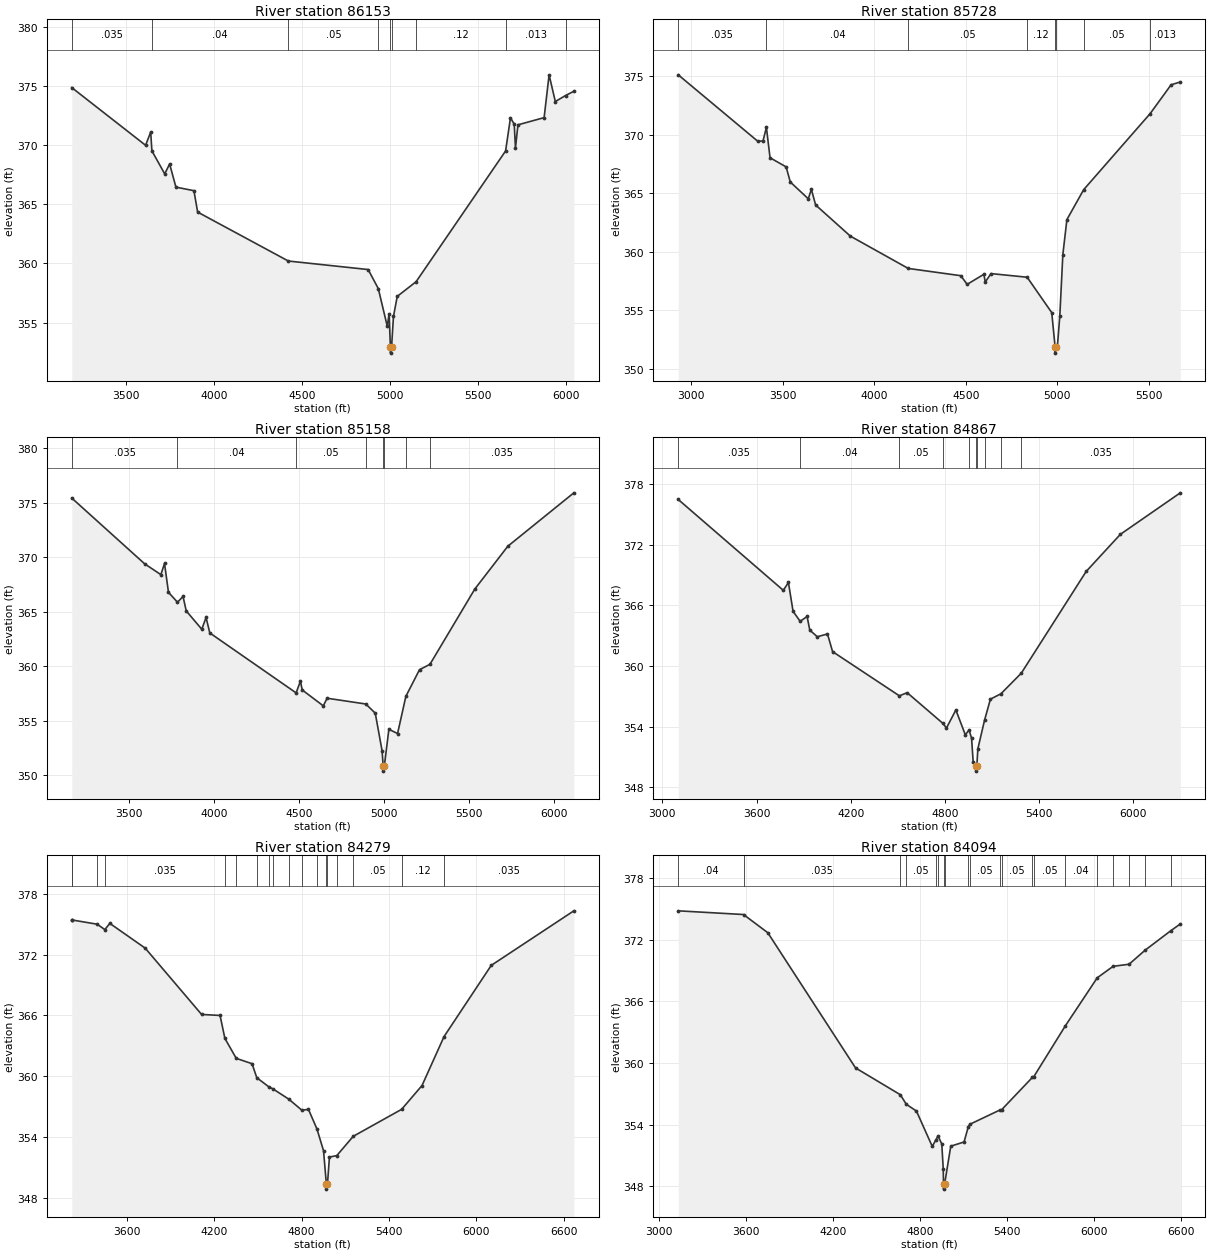
Type RM Length L Ch R = 1 ,86153   ,425,425,425
BEGIN DESCRIPTION:
Mapping XS a628ed4b
END DESCRIPTION:
XS GIS Cut Line= 3
       2434979.4     13570040.78      2433995.03     13568530.38
      2433265.89     13567775.19
#Sta/Elev= 30
  3190.8  374.87  3610.2  369.99  3639.3  371.11    3646  369.52  3718.9  367.57
  3746.8  368.41  3782.6  366.45  3884.9  366.15  3905.9  364.34  4421.3   360.2
  4874.7  359.48  4932.4  357.87  4983.4  354.68  4993.7  355.75  5001.2  352.91
  5001.7  352.41  5007.7  352.91  5018.6  355.51    5040  357.21  5147.1  358.45
  5655.6  369.51  5683.4  372.32  5704.7  371.77  5711.7  369.76  5725.8  371.72
  5874.5  372.33  5902.8  375.95  5938.1  373.69  5996.4   374.2  6043.4  374.56
#Mann= 9 ,-1 , 0
  3190.8    .035       0    3646     .04       0  4421.3     .05       0
  4932.4      .1       0  5001.2     .05       0  5007.7      .1       0
  5147.1     .12       0  5655.6    .013       0  5996.4    .035       0
Bank Sta=5001.2,5007.7
XS Rating Curve= 0 ,0
Exp/Cntr=0.3,0.1

Type RM Length L Ch R = 1 ,85728   ,570,570,570
BEGIN DESCRIPTION:
Mapping XS ce5be014
END DESCRIPTION:
XS GIS Cut Line= 3
      2435041.89      13570061.6       2434349.2      13568540.8
      2433855.02     13567588.85
#Sta/Elev= 30
  2928.8  375.12  3363.4  369.45  3391.9  369.47  3410.6  370.63  3430.5  368.04
  3518.4  367.26  3541.2  365.97  3639.3  364.54  3656.5  365.34  3679.5  364.01
  3869.4  361.35  4185.8  358.59  4473.2  357.97  4507.4  357.23    4599  358.09
  4606.5  357.43  4638.1  358.15  4835.5  357.84  4969.9  354.82  4988.5  351.86
    4989  351.36  4995.5  351.86  5000.8  351.93  5014.1  354.56  5030.6  359.78
  5052.7  362.76  5144.6  365.32  5507.8  371.81  5622.2  374.27  5672.5  374.51
#Mann= 8 ,-1 , 0
  2928.8    .035       0  3410.6     .04       0  4185.8     .05       0
  4835.5     .12       0  4988.5     .05       0  4995.5     .12       0
  5144.6     .05       0  5507.8    .013       0
Bank Sta=4988.5,4995.5
XS Rating Curve= 0 ,0
Exp/Cntr=0.3,0.1

Type RM Length L Ch R = 1 ,85158   ,291,291,291
BEGIN DESCRIPTION:
Mapping XS 66dab83e
END DESCRIPTION:
XS GIS Cut Line= 4
      2435187.72     13570066.79       2434661.7     13568655.38
      2434713.78     13567905.38      2434334.62     13567318.46
#Sta/Elev= 30
  3161.6  375.42  3590.4  369.39  3686.4  368.39  3707.8  369.42  3731.1  366.77
  3784.2  365.86  3816.8  366.39  3835.8  365.06  3927.4  363.38  3952.4  364.46
  3974.6  363.04  4482.9  357.54  4508.2  358.62  4518.8  357.81  4642.8  356.35
  4665.4  357.05  4893.1  356.52  4948.9  355.68    4989  352.24  4995.5  350.86
    4996  350.36  5002.6  350.86  5029.1   354.2  5080.3  353.81  5129.3  357.23
  5209.5  359.67  5270.9  360.16  5535.2  367.07  5729.6     371  6118.4   375.9
#Mann= 8 ,-1 , 0
  3161.6    .035       0  3784.2     .04       0  4482.9     .05       0
  4893.1      .1       0  4995.5     .05       0  5002.6      .1       0
  5129.3     .12       0  5270.9    .035       0
Bank Sta=4995.5,5002.6
XS Rating Curve= 0 ,0
Exp/Cntr=0.3,0.1

Type RM Length L Ch R = 1 ,84867   ,588,588,588
BEGIN DESCRIPTION:
Mapping XS 17ba69c6
END DESCRIPTION:
XS GIS Cut Line= 4
      2435489.81     13570113.68      2434937.74     13568775.17
      2434948.16     13567926.21      2434474.18     13567160.56
#Sta/Elev= 30
  3101.2  376.49  3770.4  367.49  3802.9  368.27  3832.5  365.41  3877.7  364.42
  3921.9   364.9    3939  363.55  3986.8  362.89  4051.7  363.17  4084.1  361.42
  4509.5  357.04  4559.3  357.35  4786.7  354.31  4809.3  353.85  4869.3  355.64
  4929.3  353.18  4953.3  353.65  4969.3  352.84  4979.3  350.53  4995.7  350.08
  4996.2  349.58  5002.8  350.08  5009.3  351.79  5051.8  354.62  5089.3  356.71
    5156  357.24  5285.8  359.28    5699  369.36    5917  373.04  6298.6  377.15
#Mann= 10 ,-1 , 0
  3101.2    .035       0  3877.7     .04       0  4509.5     .05       0
  4786.7      .1       0  4953.3     .12       0  4995.7     .05       0
  5002.8     .12       0  5051.8     .05       0    5156     .12       0
  5285.8    .035       0
Bank Sta=4995.7,5002.8
XS Rating Curve= 0 ,0
Exp/Cntr=0.3,0.1

Type RM Length L Ch R = 1 ,84279   ,185,185,185
BEGIN DESCRIPTION:
Mapping XS 14cae11e
END DESCRIPTION:
XS GIS Cut Line= 3
      2436156.48     13570139.73      2435432.53     13568530.38
      2434656.49     13567040.79
#Sta/Elev= 30
  3223.6  375.42  3224.9  375.42    3398     375  3450.3  374.47  3484.8  375.08
  3727.3  372.64  4114.2   366.1  4240.9     366  4273.9  363.74  4351.9  361.77
  4460.3  361.24  4492.8  359.86  4577.2  358.94  4602.3  358.77  4711.8  357.75
  4802.6  356.65  4847.2  356.74  4905.7   354.8  4950.8  352.65  4970.1  349.37
  4970.6  348.87  4977.7  349.37  4991.2  352.03  5041.8  352.18  5154.6  354.08
  5486.4  356.74  5626.4  359.09  5777.6  363.92  6101.3  370.94  6667.9  376.32
#Mann= 18 ,-1 , 0
  3223.6    .013       0  3224.9    .035       0    3398    .013       0
  3450.3    .035       0  4273.9    .013       0  4351.9    .035       0
  4492.8    .013       0  4577.2     .04       0  4602.3     .05       0
  4711.8    .013       0  4802.6     .05       0  4905.7     .12       0
  4970.1     .05       0  4977.7     .12       0  5041.8      .1       0
  5154.6     .05       0  5486.4     .12       0  5777.6    .035       0
Bank Sta=4970.1,4977.7
XS Rating Curve= 0 ,0
Exp/Cntr=0.3,0.1

Type RM Length L Ch R = 1 ,84094   ,513,513,513
BEGIN DESCRIPTION:
Mapping XS 1c0654e0
END DESCRIPTION:
XS GIS Cut Line= 3
      2436343.99     13570124.14      2435557.53     13568379.34
      2434906.96      13566968.9
#Sta/Elev= 30
  3130.6  374.81  3581.3  374.45    3749  372.68  4354.9  359.52  4664.3  356.91
  4705.5  355.98  4775.6  355.32  4884.7  351.88  4910.2  352.52  4924.6   352.9
  4950.5  352.12  4960.7  349.68  4962.4  348.22  4962.9  347.72    4970  348.22
  5012.5   351.9  5104.3  352.31  5133.6  353.79    5144  354.03  5354.7  355.44
    5364  355.45  5575.8  358.59    5584  358.62    5804  363.62    6024  368.29
  6133.9  369.41  6243.9  369.61  6353.9  370.97  6532.6  372.88  6597.7  373.53
#Mann= 20 ,-1 , 0
  3130.6     .04       0  3581.3    .035       0  4664.3    .013       0
  4705.5     .05       0  4910.2    .013       0  4924.6      .1       0
  4962.4     .05       0    4970      .1       0  5133.6    .013       0
    5144     .05       0  5354.7    .013       0    5364     .05       0
  5575.8    .013       0    5584     .05       0    5804     .04       0
    6024    .035       0  6133.9     .04       0  6243.9    .035       0
  6353.9     .04       0  6532.6    .013       0
Bank Sta=4962.4,4970
XS Rating Curve= 0 ,0
Exp/Cntr=0.3,0.1