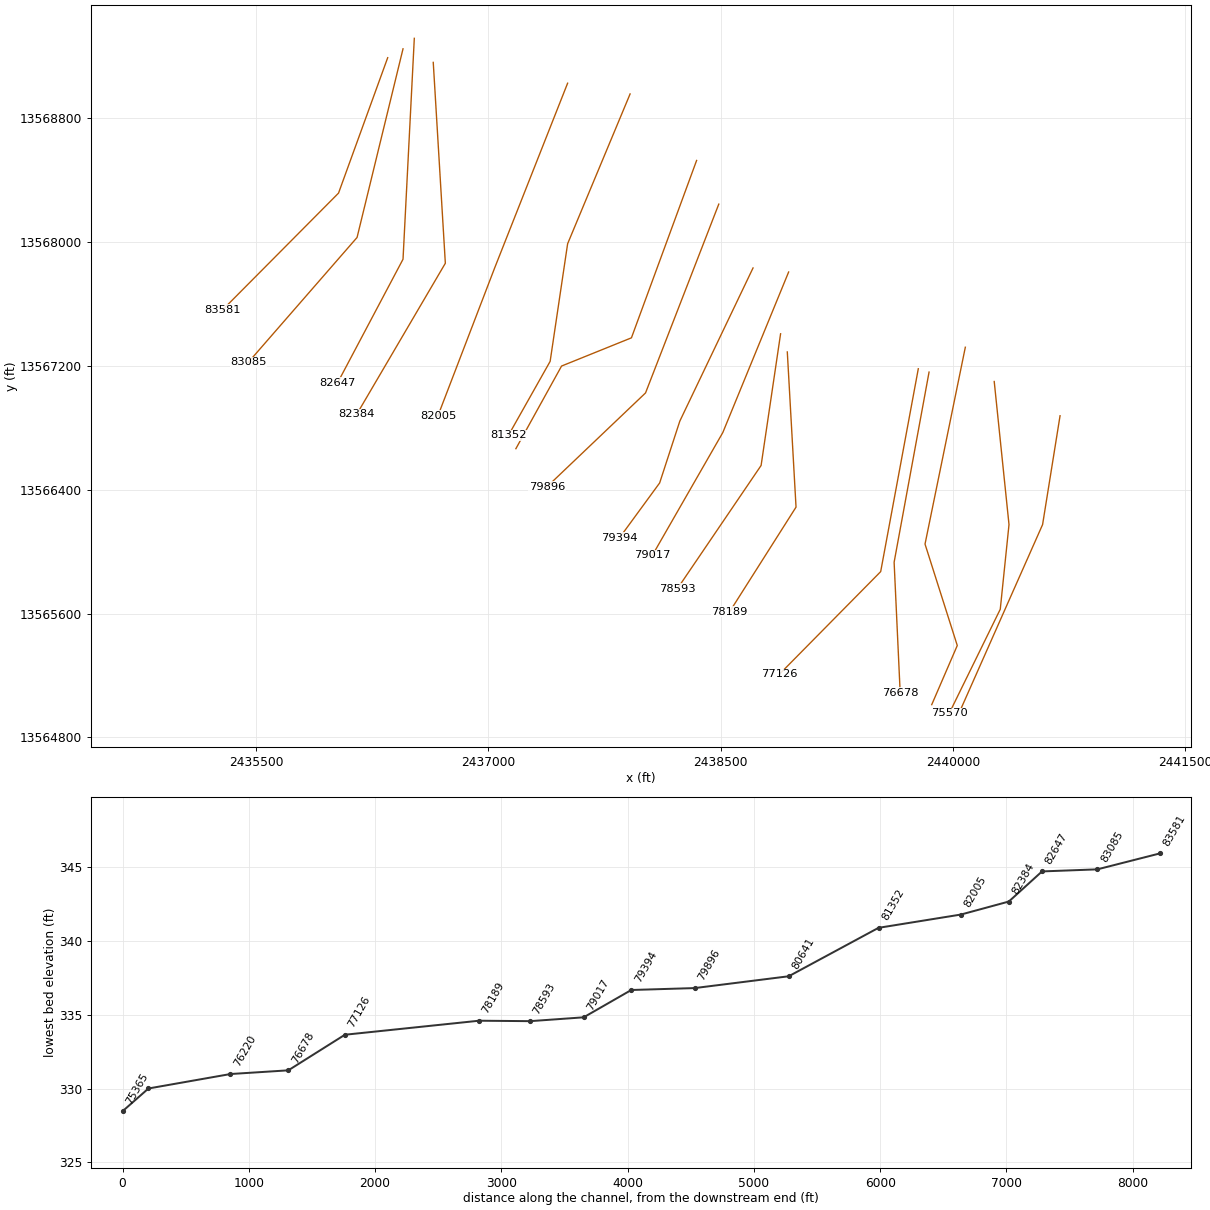
HEC-RAS study YORKTOWN CREEK.prj: YORKTOWN CREEK Base Level Engineering

--- YORKTOWN CREEK.g01 (geometry) --- (continued)

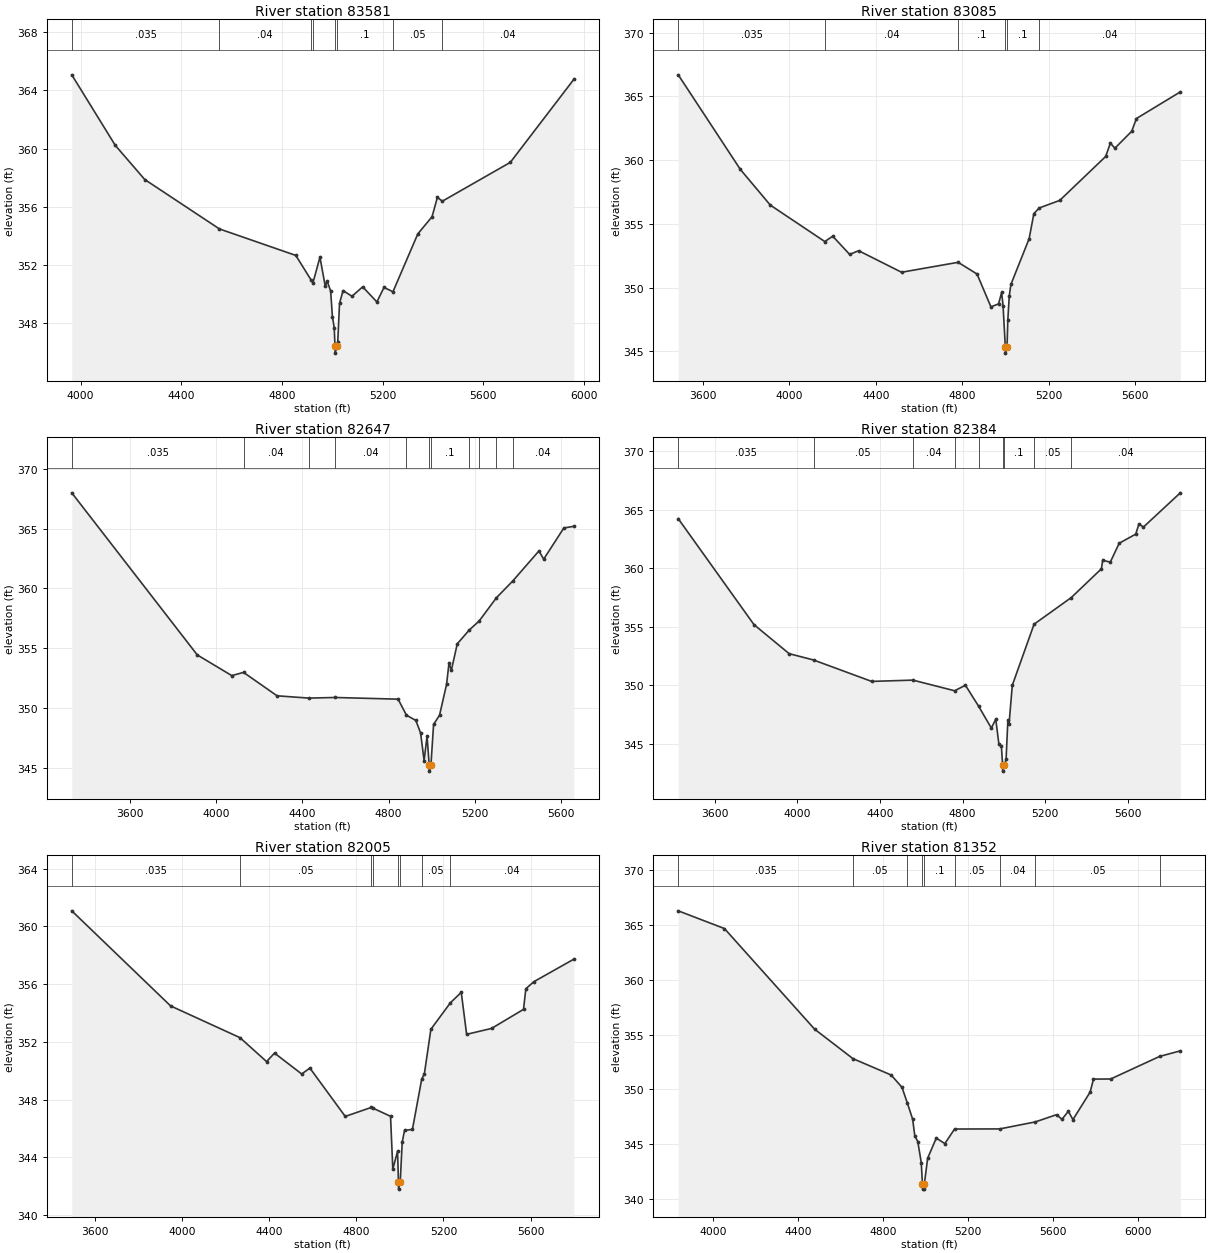
Type RM Length L Ch R = 1 ,83581   ,496,496,496
BEGIN DESCRIPTION:
Mapping XS 2bab466a
END DESCRIPTION:
XS GIS Cut Line= 3
      2436349.21     13569191.88      2436031.49     13568316.84
      2435281.48     13567561.62
#Sta/Elev= 30
    3965  365.07  4137.9  360.22    4255  357.87    4552  354.47  4855.3  352.65
    4915  350.99  4923.6  350.77  4951.3  352.53  4972.5  350.52  4979.6   350.9
  4993.8   350.2  5000.8  348.44  5007.9  347.69  5011.1  346.43  5011.6  345.93
  5018.8  346.43  5022.1  346.72  5029.1  349.35  5043.2  350.23  5078.6  349.84
    5121  350.49  5177.6  349.45  5205.9  350.45  5241.4  350.15  5340.2  354.13
  5396.8  355.31    5418  356.64  5437.8  356.38  5707.9  359.05  5960.3  364.76
#Mann= 8 ,-1 , 0
    3965    .035       0    4552     .04       0    4915     .05       0
  4923.6      .1       0  5011.1     .05       0  5018.8      .1       0
  5241.4     .05       0  5437.8     .04       0
Bank Sta=5011.1,5018.8
XS Rating Curve= 0 ,0
Exp/Cntr=0.3,0.1

Type RM Length L Ch R = 1 ,83085   ,438,438,438
BEGIN DESCRIPTION:
Mapping XS c8b93b17
END DESCRIPTION:
XS GIS Cut Line= 3
      2436448.15     13569249.11      2436151.28     13568030.38
      2435449.09     13567224.16
#Sta/Elev= 30
  3485.2   366.7  3772.8  359.27  3911.4  356.47  4163.5  353.61  4200.2  354.03
  4278.5   352.6  4320.2  352.89  4518.7   351.2  4780.4  351.98    4868  351.06
  4932.4  348.48  4967.7  348.72  4981.9  349.62  4988.6  348.54  4998.8  345.35
  4999.3  344.85  5006.8  345.35  5010.4  347.44  5017.1  349.33  5024.7  350.24
  5109.2  353.84    5131  355.81  5156.3  356.25  5250.6  356.84  5463.3  360.29
  5485.1  361.34    5506  360.94  5583.9  362.27  5605.7  363.27  5808.7  365.36
#Mann= 6 ,-1 , 0
  3485.2    .035       0  4163.5     .04       0  4780.4      .1       0
  4998.8     .05       0  5006.8      .1       0  5156.3     .04       0
Bank Sta=4998.8,5006.8
XS Rating Curve= 0 ,0
Exp/Cntr=0.3,0.1

Type RM Length L Ch R = 1 ,82647   ,263,263,263
BEGIN DESCRIPTION:
Mapping XS 4f1104da
END DESCRIPTION:
XS GIS Cut Line= 3
      2436521.07      13569316.8      2436448.16     13567889.76
      2436026.27     13567092.85
#Sta/Elev= 30
  3329.4  367.99    3912  354.43  4072.2   352.7  4126.8  352.97  4282.4  351.01
    4430  350.82  4552.2  350.87  4844.2  350.73    4883  349.39  4926.6  348.95
  4948.6   347.9  4964.9  345.59  4978.7  347.65  4988.5  345.21    4989  344.71
  4996.6  345.21  5008.9  348.62  5036.6  349.39  5069.2  351.97  5080.6  353.77
  5091.2  353.13  5118.9  355.36  5174.8  356.52  5220.1  357.26  5300.9  359.22
  5376.2  360.61    5498  363.13    5520  362.44  5613.6  365.05    5660  365.19
#Mann= 11 ,-1 , 0
  3329.4    .035       0  4126.8     .04       0    4430     .05       0
  4552.2     .04       0    4883      .1       0  4988.5     .05       0
  4996.6      .1       0  5174.8     .05       0  5220.1     .04       0
  5300.9     .05       0  5376.2     .04       0
Bank Sta=4988.5,4996.6
XS Rating Curve= 0 ,0
Exp/Cntr=0.3,0.1

Type RM Length L Ch R = 1 ,82384   ,379,379,379
BEGIN DESCRIPTION:
Mapping XS 7c3b3460
END DESCRIPTION:
XS GIS Cut Line= 3
      2436643.47     13569161.41      2436721.59     13567863.71
      2436148.66     13566887.12
#Sta/Elev= 30
  3422.8  364.25  3789.9  355.19  3960.2  352.71  4078.4  352.17  4359.7  350.34
  4559.4  350.45  4761.7  349.54  4814.1  350.01  4877.9  348.22  4939.6  346.35
  4961.1  347.11  4976.4  344.95  4988.4  344.81  4994.2  343.17  4994.7  342.67
  5002.3  343.17  5011.2  343.71  5019.7  347.03  5025.5  346.73  5041.2  350.01
  5146.7  355.23  5327.1  357.51  5473.1  359.97  5478.9  360.69    5516  360.54
    5559  362.15  5639.1  362.93  5654.7   363.8  5676.2  363.53  5855.1  366.46
#Mann= 9 ,-1 , 0
  3422.8    .035       0  4078.4     .05       0  4559.4     .04       0
  4761.7     .05       0  4877.9      .1       0  4994.2     .05       0
  5002.3      .1       0  5146.7     .05       0  5327.1     .04       0
Bank Sta=4994.2,5002.3
XS Rating Curve= 0 ,0
Exp/Cntr=0.3,0.1

Type RM Length L Ch R = 1 ,82005   ,653,653,653
BEGIN DESCRIPTION:
Mapping XS 1b68222d
END DESCRIPTION:
XS GIS Cut Line= 3
      2437511.54     13569026.94      2437038.44     13567828.99
      2436674.15     13566879.24
#Sta/Elev= 30
  3493.5  361.08  3947.2  354.49  4265.7  352.29    4388  350.63  4424.5  351.22
  4549.2  349.77  4586.8  350.18  4749.1  346.83  4868.1  347.45  4876.4   347.4
  4957.1  346.84  4967.5  343.18  4989.3  344.41  4993.5  342.29    4994  341.79
  5001.6  342.29  5010.7  345.05  5021.4  345.86  5057.6  345.93  5100.4  349.43
  5112.3  349.77  5142.3  352.87  5232.1  354.71  5281.8  355.43  5306.4  352.52
  5421.2  352.93  5567.6  354.25  5578.3  355.68  5615.3  356.17  5798.7  357.73
#Mann= 8 ,-1 , 0
  3493.5    .035       0  4265.7     .05       0  4868.1     .04       0
  4876.4      .1       0  4993.5     .05       0  5001.6      .1       0
  5100.4     .05       0  5232.1     .04       0
Bank Sta=4993.5,5001.6
XS Rating Curve= 0 ,0
Exp/Cntr=0.3,0.1

Type RM Length L Ch R = 1 ,81352   ,711,711,711
BEGIN DESCRIPTION:
Mapping XS 16037261
END DESCRIPTION:
XS GIS Cut Line= 4
      2437915.17     13568957.47      2437511.53     13567989.58
      2437398.68     13567230.03      2437129.78     13566752.96
#Sta/Elev= 30
  3835.7  366.31  4053.3  364.69  4477.9   355.5  4658.3  352.81  4838.5  351.31
  4889.2  350.19  4915.2  348.72  4939.6  347.27  4949.7  345.75  4963.8  345.23
    4980  343.32  4985.5  341.39    4986  340.89  4994.2  340.89  4994.7  341.39
  5010.3  343.72  5050.8  345.55  5091.2  345.05  5136.9  346.38  5349.6  346.39
  5517.2  347.03  5616.9  347.69  5642.7  347.27  5672.6     348  5694.3  347.24
  5775.2  349.75  5791.1  350.94    5872  350.95  6102.1  353.01  6199.9  353.52
#Mann= 9 ,-1 , 0
  3835.7    .035       0  4658.3     .05       0  4915.2      .1       0
  4985.5     .05       0  4994.7      .1       0  5136.9     .05       0
  5349.6     .04       0  5517.2     .05       0  6102.1     .04       0
Bank Sta=4985.5,4994.7
XS Rating Curve= 0 ,0
Exp/Cntr=0.3,0.1

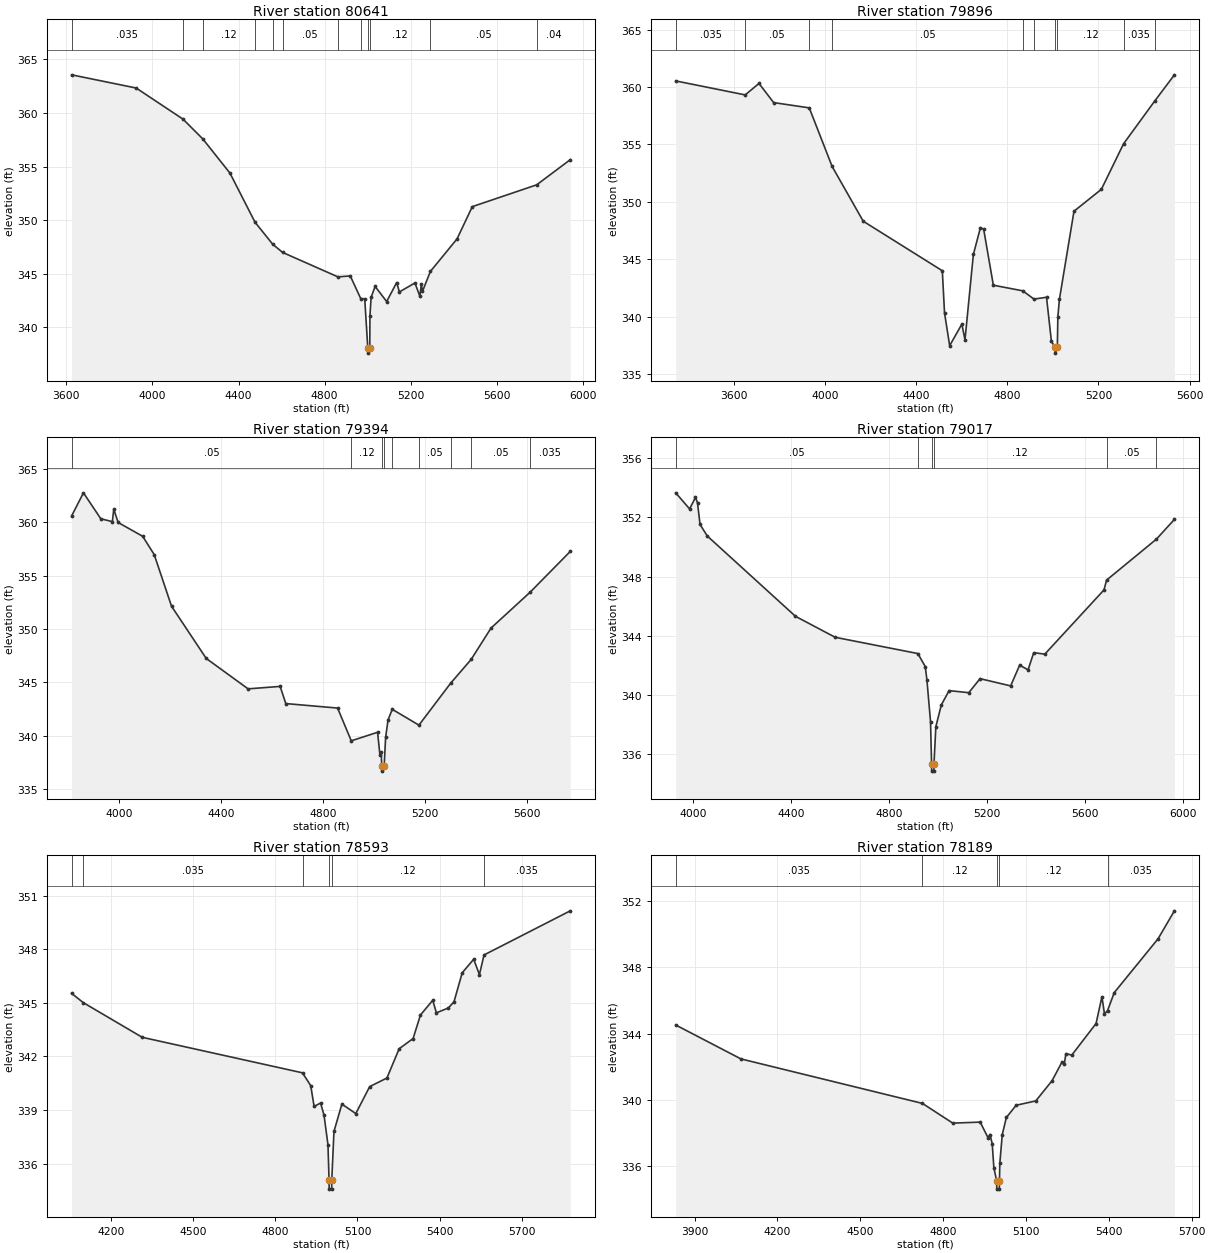
Type RM Length L Ch R = 1 ,80641   ,745,745,745
BEGIN DESCRIPTION:
Mapping XS 52325632
END DESCRIPTION:
XS GIS Cut Line= 4
      2438344.86     13568527.77      2437923.85     13567381.94
      2437472.46     13567199.65      2437177.34     13566665.83
#Sta/Elev= 30
  3624.3  363.56  3924.3  362.33  4141.9  359.43  4233.7  357.59  4360.1   354.4
  4476.9  349.81  4559.1  347.76  4604.9     347    4862  344.72  4919.3  344.81
  4967.9   342.7  4986.6  342.67  5000.7  338.11  5001.2  337.61    5010  338.11
  5010.7  341.07  5016.3  342.82  5034.8  343.83  5088.5  342.42    5135  344.19
  5147.6  343.32    5220  344.15  5242.8  342.91  5249.5  344.04  5254.9  343.37
  5291.7  345.23  5415.5  348.26  5486.5  351.27  5785.4   353.3  5941.8  355.65
#Mann= 12 ,-1 , 0
  3624.3    .035       0  4141.9     .05       0  4233.7     .12       0
  4476.9     .05       0  4559.1     .12       0  4604.9     .05       0
    4862      .1       0  4967.9     .12       0  5000.7     .05       0
    5010     .12       0  5291.7     .05       0  5785.4     .04       0
Bank Sta=5000.7,5010
XS Rating Curve= 0 ,0
Exp/Cntr=0.3,0.1

Type RM Length L Ch R = 1 ,79896   ,502,502,502
BEGIN DESCRIPTION:
Mapping XS 21bbee40
END DESCRIPTION:
XS GIS Cut Line= 3
      2438488.08     13568245.64        2438015.     13567026.04
      2437377.79     13566419.17
#Sta/Elev= 30
  3345.1  360.54  3649.9  359.32  3710.5  360.32  3774.8  358.65    3931  358.19
  4031.4  353.08  4167.8  348.31  4514.9  343.99  4524.5  340.32  4547.1  337.46
  4600.7  339.34  4614.3  337.96  4651.1  345.41  4682.1  347.75  4696.3  347.61
  4738.8  342.73    4868  342.24    4917  341.52  4972.1  341.68  4993.5  337.84
  5009.7  337.31  5010.2  336.81  5019.5  337.31  5021.8  339.98  5028.8  341.52
  5092.6  349.18  5212.8  351.09  5310.1  355.06  5445.9  358.76  5533.2  361.07
#Mann= 10 ,-1 , 0
  3345.1    .035       0  3649.9     .05       0    3931     .12       0
  4031.4     .05       0    4868      .1       0    4917     .12       0
  5009.7     .05       0  5019.5     .12       0  5310.1    .035       0
  5445.9    .013       0
Bank Sta=5009.7,5019.5
XS Rating Curve= 0 ,0
Exp/Cntr=0.3,0.1

Type RM Length L Ch R = 1 ,79394   ,377,377,377
BEGIN DESCRIPTION:
Mapping XS 7bd2df01
END DESCRIPTION:
XS GIS Cut Line= 4
      2438709.44     13567833.32      2438236.35     13566843.75
      2438106.14     13566444.44      2437846.28      13566089.3
#Sta/Elev= 30
    3813  360.59  3859.5  362.76  3927.6  360.33  3972.9  360.06  3978.5  361.23
  3995.6  359.98  4091.8  358.69  4137.2  356.97  4205.2  352.13  4341.3  347.24
  4505.6  344.39  4631.4  344.62  4653.5  343.01  4856.8  342.59  4910.4  339.52
  5013.7  340.32    5023  338.17  5028.3  338.47  5029.8  337.18  5030.3  336.68
  5039.6  337.18  5045.3  339.85  5054.9  341.49  5071.4  342.47    5176  340.99
  5300.1  344.91    5381  347.15    5459  350.09  5612.5  353.45  5769.9  357.27
#Mann= 9 ,-1 , 0
    3813     .05       0  4910.4     .12       0  5029.8     .05       0
  5039.6     .12       0  5071.4      .1       0    5176     .05       0
  5300.1     .12       0    5381     .05       0  5612.5    .035       0
Bank Sta=5029.8,5039.6
XS Rating Curve= 0 ,0
Exp/Cntr=0.3,0.1

Type RM Length L Ch R = 1 ,79017   ,424,424,424
BEGIN DESCRIPTION:
Mapping XS 23d0a07a
END DESCRIPTION:
XS GIS Cut Line= 3
      2438939.47     13567807.28      2438514.13     13566769.96
      2438059.18     13565977.05
#Sta/Elev= 30
  3928.9  353.67  3985.5  352.58  4009.5  353.36  4017.8     353  4028.1  351.53
  4057.5  350.75  4417.7  345.31  4579.8  343.89    4917  342.79  4947.3  341.91
  4954.1  341.01  4968.9  338.17  4973.1  335.33  4973.6  334.83  4982.5  334.83
    4983  335.33  4990.6  337.84  5012.9  339.31  5044.6  340.28  5124.9  340.14
  5171.1  341.09  5295.8   340.6  5332.5     342    5367  341.69  5390.1  342.85
  5435.3  342.75  5676.9   347.1  5687.3  347.76  5890.5  350.53  5964.2  351.87
#Mann= 6 ,-1 , 0
  3928.9     .05       0    4917     .12       0  4973.1     .05       0
    4983     .12       0  5687.3     .05       0  5890.5    .035       0
Bank Sta=4973.1,4983
XS Rating Curve= 0 ,0
Exp/Cntr=0.3,0.1

Type RM Length L Ch R = 1 ,78593   ,404,404,404
BEGIN DESCRIPTION:
Mapping XS fecba34b
END DESCRIPTION:
XS GIS Cut Line= 3
       2438887.4     13567408.02      2438761.53     13566557.29
      2438219.92     13565760.05
#Sta/Elev= 30
  4054.5  345.53  4097.2  345.01  4312.7  343.07    4899  341.08  4929.1  340.36
  4941.4   339.2  4965.1  339.39  4977.7  338.71  4992.1  337.06  4996.1  335.07
  4996.6  334.57  5005.5  334.57    5006  335.07    5014   337.8    5043  339.33
  5093.9   338.8  5144.7  340.31  5207.7  340.79  5252.5  342.43  5303.4     343
  5330.4  344.32  5375.2  345.14  5388.7  344.44  5432.2  344.71  5453.1  345.06
    5483  346.68    5525  347.44    5546  346.58  5562.9  347.68  5878.3  350.15
#Mann= 6 ,-1 , 0
  4054.5     .05       0  4097.2    .035       0    4899     .12       0
  4996.1     .05       0    5006     .12       0  5562.9    .035       0
Bank Sta=4996.1,5006
XS Rating Curve= 0 ,0
Exp/Cntr=0.3,0.1

Type RM Length L Ch R = 1 ,78189   ,1063,1063,1063
BEGIN DESCRIPTION:
Mapping XS 6744f97e
END DESCRIPTION:
XS GIS Cut Line= 3
       2438930.8     13567290.81      2438987.22     13566288.19
      2438557.55     13565611.13
#Sta/Elev= 30
  3831.5  344.52  4067.7  342.47  4725.1  339.78  4834.8  338.59  4934.2  338.65
  4962.5  337.71  4969.8   337.9  4977.8  337.34  4983.7   335.9  4993.8   335.1
  4994.3   334.6  5003.5   334.6    5004   335.1  5005.3  336.16  5014.2   337.9
    5029  338.93  5064.5  339.67  5135.6  339.93  5194.8  341.16  5230.3  342.28
  5238.7  342.14  5244.6  342.79  5265.9   342.7  5353.9  344.61  5375.1  346.23
  5384.3  345.19  5395.5  345.39  5419.8  346.48  5578.4  349.73  5637.6  351.42
#Mann= 5 ,-1 , 0
  3831.5    .035       0  4725.1     .12       0  4993.8     .05       0
    5004     .12       0  5395.5    .035       0
Bank Sta=4993.8,5004
XS Rating Curve= 0 ,0
Exp/Cntr=0.3,0.1

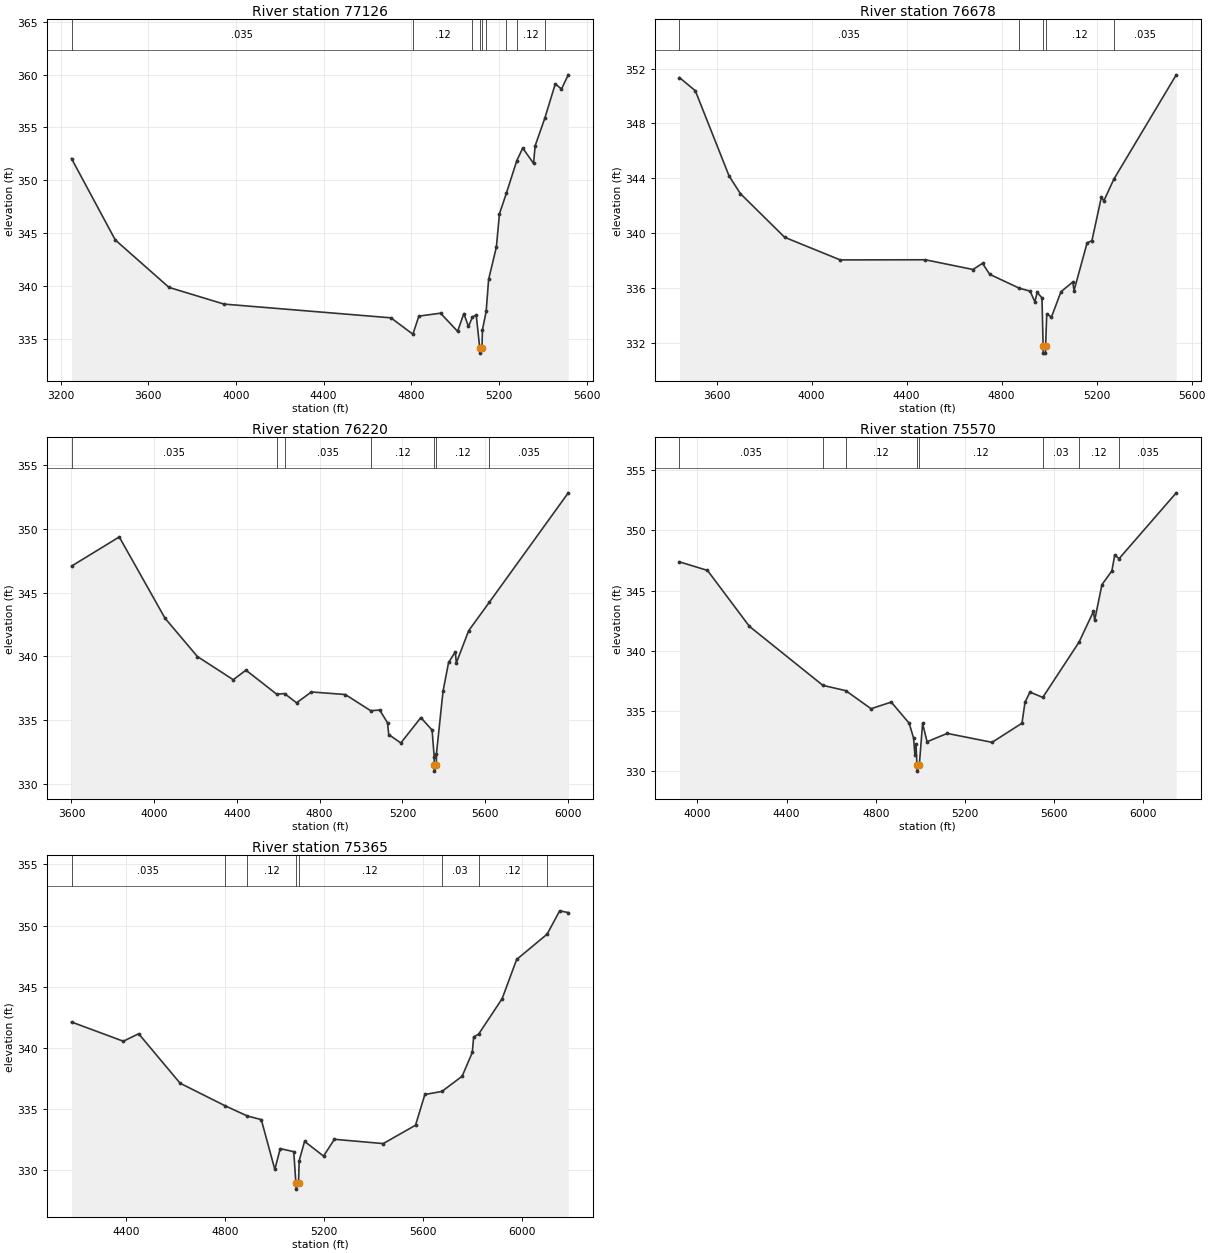
Type RM Length L Ch R = 1 ,77126   ,448,448,448
BEGIN DESCRIPTION:
Mapping XS 9246c0ef
END DESCRIPTION:
XS GIS Cut Line= 3
      2439777.14     13567182.25      2439534.09     13565871.53
      2438878.69     13565207.44
#Sta/Elev= 30
  3249.9  352.06  3449.5  344.36  3694.6  339.87  3945.5  338.29  4707.1  336.99
  4807.1  335.44  4834.4  337.15  4933.4  337.43  5011.2  335.71  5039.5  337.39
  5060.7  336.17  5078.9  337.07  5096.1  337.26  5112.1  334.15  5112.6  333.65
  5122.4  334.15  5124.4  335.85  5141.4  337.59  5152.7  340.63    5188  343.68
  5202.1  346.83  5233.5  348.77  5281.2  351.86  5308.2  353.05  5357.7   351.6
  5364.8  353.26    5409  355.88  5456.7  359.12    5485  358.64    5516  359.98
#Mann= 9 ,-1 , 0
  3249.9    .035       0  4807.1     .12       0  5078.9     .05       0
  5112.1     .05       0  5122.4     .05       0  5141.4     .12       0
  5233.5     .05       0  5281.2     .12       0    5409    .035       0
Bank Sta=5112.1,5122.4
XS Rating Curve= 0 ,0
Exp/Cntr=0.3,0.1

Type RM Length L Ch R = 1 ,76678   ,458,458,458
BEGIN DESCRIPTION:
Mapping XS f66e6628
END DESCRIPTION:
XS GIS Cut Line= 3
      2439846.59     13567160.58       2439620.9     13565932.29
      2439659.96     13565090.24
#Sta/Elev= 30
  3443.4  351.34  3510.1  350.38  3652.4  344.16  3699.7  342.88  3886.3  339.69
  4120.1  338.04  4478.5  338.05  4679.3  337.34  4719.6  337.79  4749.6  336.99
  4873.9  335.98  4919.8  335.76  4939.8  334.99  4949.8  335.67  4969.8  335.27
  4974.7  331.74  4975.2  331.24  4984.5  331.24    4985  331.74  4989.9  334.08
  5009.9  333.88  5049.9  335.72  5099.7  336.43  5104.7   335.8    5160  339.29
  5180.1  339.44  5220.1  342.64  5230.1  342.34  5272.8  343.94  5535.2  351.54
#Mann= 5 ,-1 , 0
  3443.4    .035       0  4873.9     .12       0  4974.7     .05       0
    4985     .12       0  5272.8    .035       0
Bank Sta=4974.7,4985
XS Rating Curve= 0 ,0
Exp/Cntr=0.3,0.1

Type RM Length L Ch R = 1 ,76220   ,650,650,650
BEGIN DESCRIPTION:
Mapping XS 7e09a6ca
END DESCRIPTION:
XS GIS Cut Line= 4
      2440080.98     13567321.21      2439820.55     13566049.48
      2440028.89      13565394.1      2439863.94     13565012.11
#Sta/Elev= 30
  3600.2  347.07  3831.1  349.36  4052.1  342.99  4208.8  339.98  4382.3  338.16
  4443.6  338.91    4592  337.03  4630.5  337.07  4688.5  336.35    4760   337.2
    4924     337  5046.6  335.73  5090.6  335.78  5128.1  334.78  5133.9  333.86
  5192.6   333.2  5289.3  335.19  5343.7  334.21  5353.8  332.12  5353.9  331.49
  5354.4  330.99  5364.2  331.49  5364.7  332.35  5396.5  337.25  5423.5  339.52
  5455.8  340.34    5461  339.48  5520.3     342    5620  344.23  6002.1  352.82
#Mann= 7 ,-1 , 0
  3600.2    .035       0    4592     .12       0  4630.5    .035       0
  5046.6     .12       0  5353.9    .035       0  5364.2     .12       0
    5620    .035       0
Bank Sta=5353.9,5364.2
XS Rating Curve= 0 ,0
Exp/Cntr=0.3,0.1

Type RM Length L Ch R = 1 ,75570   ,205,205,205
BEGIN DESCRIPTION:
Mapping XS afaad558
END DESCRIPTION:
XS GIS Cut Line= 4
       2440267.6     13567099.87      2440363.09     13566175.35
      2440306.66     13565628.47       2439976.8     13564955.71
#Sta/Elev= 30
  3919.4  347.38    4045  346.67  4232.9  342.03  4562.6  337.13  4665.3  336.69
  4778.8  335.19  4869.3  335.74  4949.7  333.99  4969.8  332.74  4975.6  331.32
  4980.6  332.25  4984.6  330.51  4985.1  330.01  4995.2  330.51    5010  333.97
  5030.1  332.45  5120.6  333.14  5321.7   332.4  5455.9  333.99  5469.3  335.72
  5491.6  336.57  5549.1  336.13  5711.9  340.72  5776.4  343.26    5782  342.54
  5814.6  345.49  5859.1  346.63  5871.9  347.94  5891.6  347.65  6147.9  353.11
#Mann= 8 ,-1 , 0
  3919.4    .035       0  4562.6     .05       0  4665.3     .12       0
  4984.6     .05       0  4995.2     .12       0  5549.1     .03       0
  5711.9     .12       0  5891.6    .035       0
Bank Sta=4984.6,4995.2
XS Rating Curve= 0 ,0
Exp/Cntr=0.3,0.1

Type RM Length L Ch R = 1 ,75365   ,276,276,276
BEGIN DESCRIPTION:
Mapping XS 1b9ba54c
END DESCRIPTION:
XS GIS Cut Line= 3
      2440692.95     13566878.48       2440580.1     13566175.35
      2440054.93     13564990.45
#Sta/Elev= 30
  4179.2  342.12  4388.7  340.55  4450.7  341.16  4618.2  337.12  4800.9  335.27
  4890.6  334.44  4946.4  334.15  5001.1  330.08    5023  331.78  5077.7  331.53
  5086.2  328.97  5086.7  328.47  5096.9  328.97  5099.5  330.79  5121.4  332.37
    5198  331.17  5242.1  332.54  5439.3  332.19  5569.9  333.69  5607.7   336.2
  5676.6  336.45  5758.3  337.69  5799.4  339.63  5804.9   340.9    5825  341.13
  5919.9  344.02  5978.8  347.23  6101.7  349.29  6152.6   351.2  6187.4  351.06
#Mann= 8 ,-1 , 0
  4179.2    .035       0  4800.9     .05       0  4890.6     .12       0
  5086.2     .05       0  5096.9     .12       0  5676.6     .03       0
    5825     .12       0  6101.7    .035       0
Bank Sta=5086.2,5096.9
XS Rating Curve= 0 ,0
Exp/Cntr=0.3,0.1