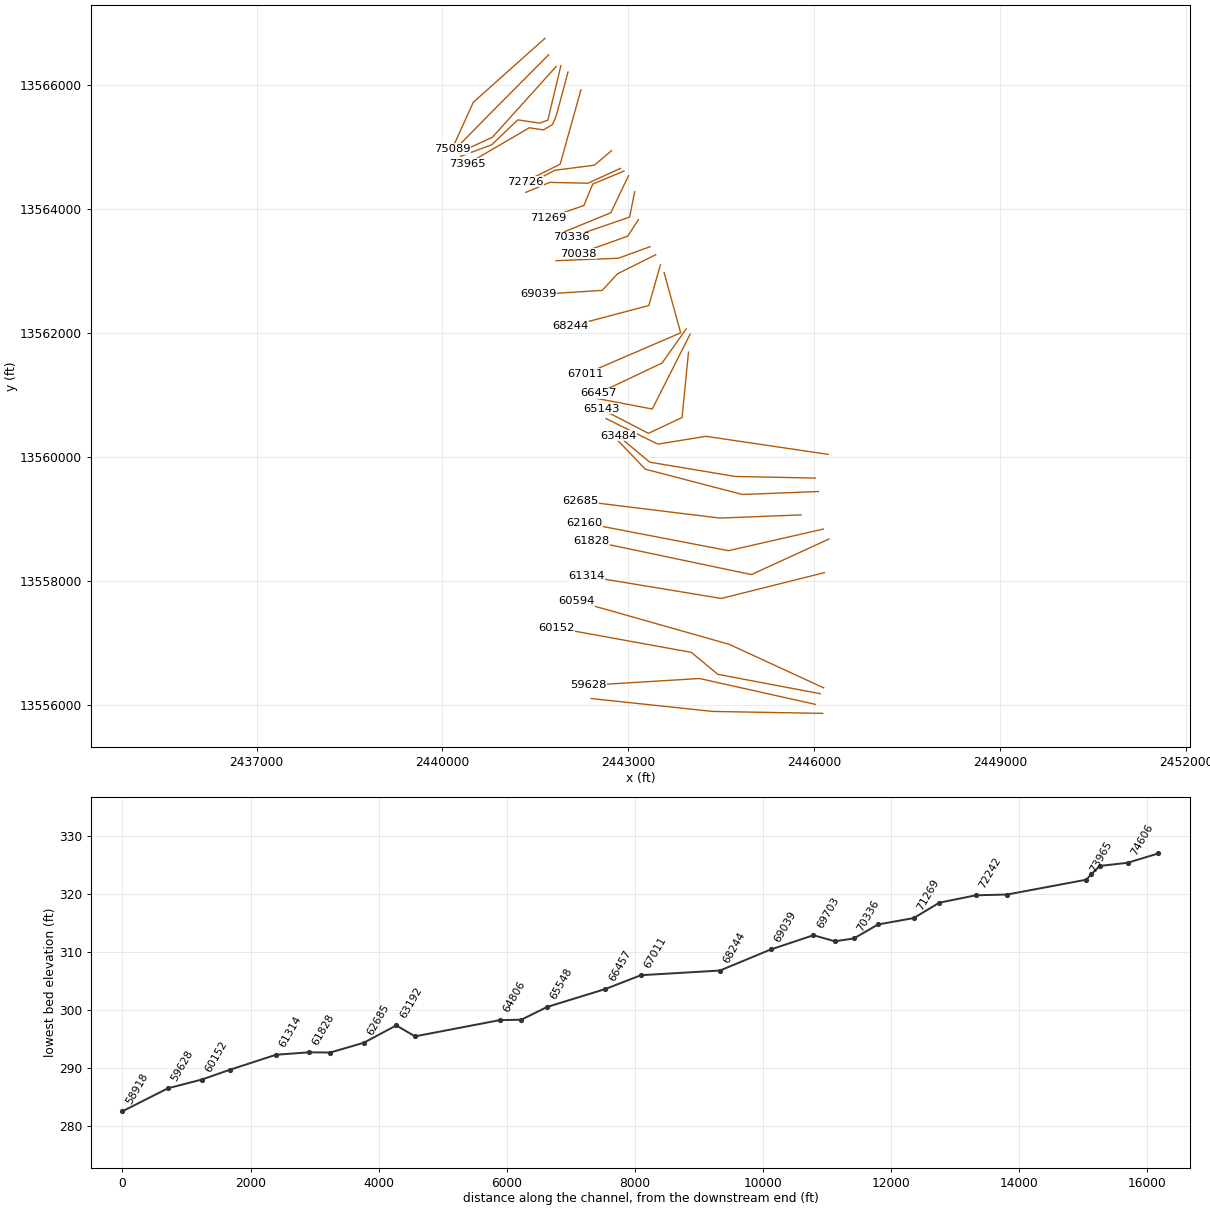
HEC-RAS study YORKTOWN CREEK.prj: YORKTOWN CREEK Base Level Engineering

--- YORKTOWN CREEK.g01 (geometry) --- (continued)

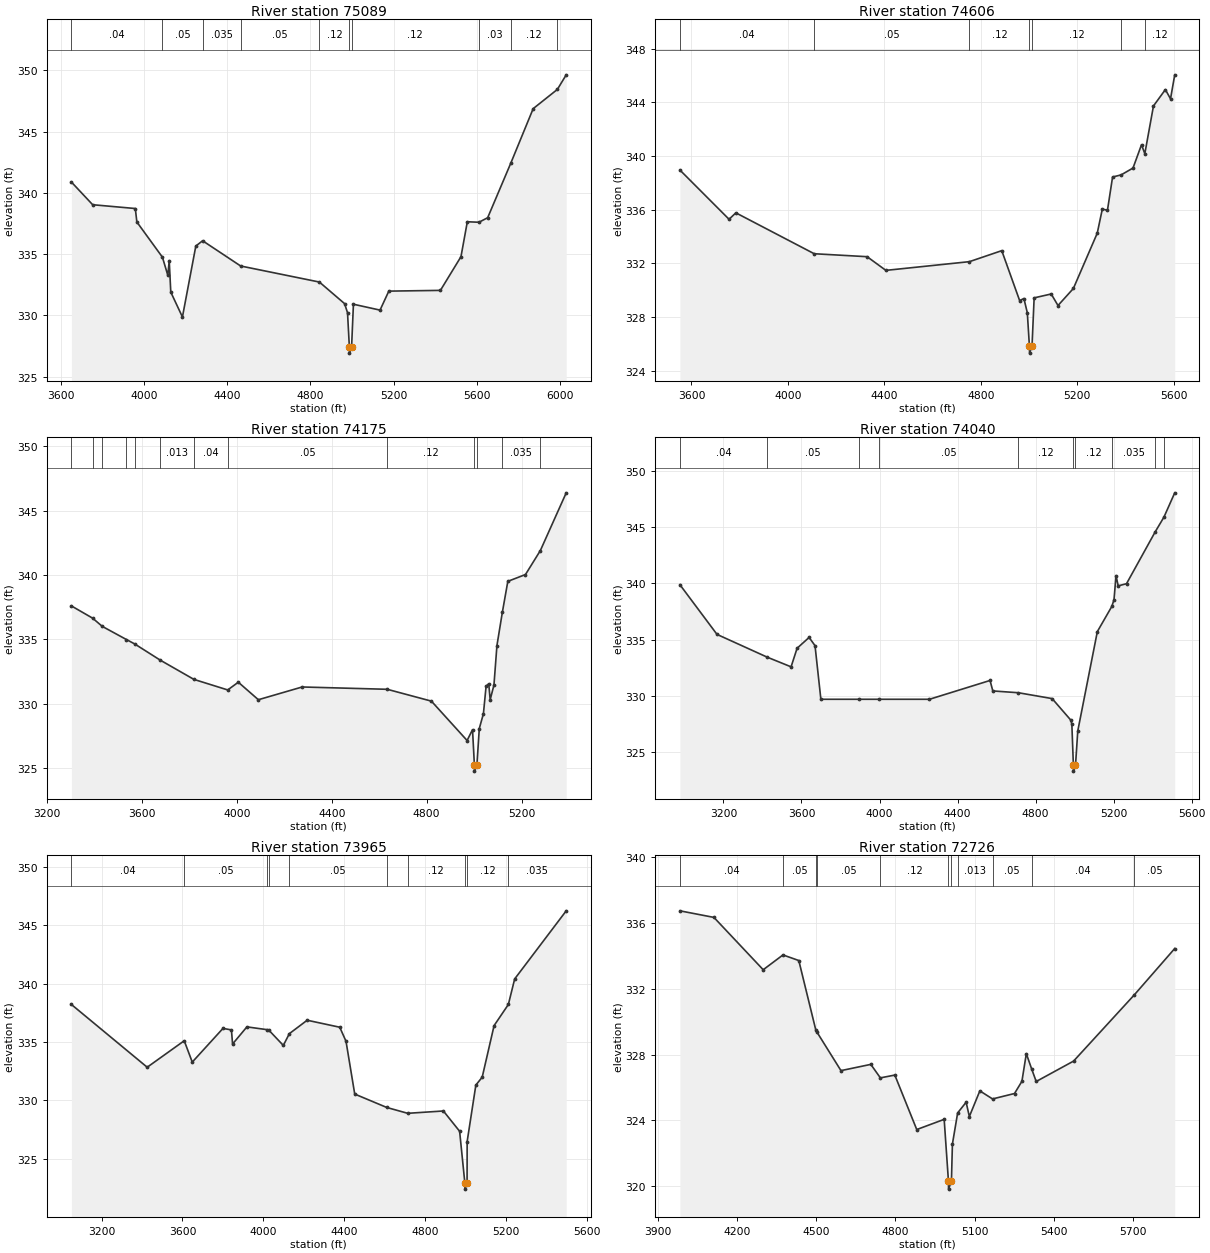
Type RM Length L Ch R = 1 ,75089   ,483,483,483
BEGIN DESCRIPTION:
Mapping XS 63622706
END DESCRIPTION:
XS GIS Cut Line= 3
       2441653.1     13566750.88      2440497.64     13565719.62
      2440154.77     13564964.45
#Sta/Elev= 30
  3651.3  340.88  3753.5  339.03  3958.4  338.72  3965.9  337.62  4088.7  334.75
  4114.7  333.27  4121.4  334.47  4128.9   331.9  4184.9  329.87  4249.3  335.66
  4281.9  336.09  4464.7  334.03  4843.2  332.72  4964.1  330.96  4978.3  330.22
  4987.2  327.42  4987.7  326.92  4997.9  327.42  5006.7  330.91  5134.6  330.43
  5176.8  331.98  5424.8  332.04  5523.6  334.79  5554.1  337.64    5610   337.6
  5651.9  337.97  5764.2  342.47  5870.6  346.87  5986.9  348.44  6029.4  349.63
#Mann= 10 ,-1 , 0
  3651.3     .04       0  4088.7     .05       0  4281.9    .035       0
  4464.7     .05       0  4843.2     .12       0  4987.2     .05       0
  4997.9     .12       0    5610     .03       0  5764.2     .12       0
  5986.9    .035       0
Bank Sta=4987.2,4997.9
XS Rating Curve= 0 ,0
Exp/Cntr=0.3,0.1

Type RM Length L Ch R = 1 ,74606   ,431,431,431
BEGIN DESCRIPTION:
Mapping XS 2c98b258
END DESCRIPTION:
XS GIS Cut Line= 3
      2441713.01     13566485.27      2440718.22     13565485.27
      2440268.82     13565026.42
#Sta/Elev= 30
    3552  338.95  3755.8  335.28  3784.1  335.76  4109.2  332.71  4328.6  332.49
  4406.4  331.47    4753  332.12  4887.2  332.94  4961.3  329.22  4979.1  329.37
  4993.2  328.31    5002   325.8  5002.5   325.3  5012.7   325.8  5021.5  329.42
  5092.3  329.71  5120.5  328.85  5184.3  330.12  5283.3  334.24  5304.4  336.04
  5325.7  335.95  5346.9  338.43  5382.5  338.59  5431.7   339.1    5467  340.84
  5480.7  340.17  5516.6  343.73    5566  344.95  5587.3  344.26  5604.8  346.05
#Mann= 7 ,-1 , 0
    3552     .04       0  4109.2     .05       0    4753     .12       0
    5002     .05       0  5012.7     .12       0  5382.5     .03       0
  5480.7     .12       0
Bank Sta=5002,5012.7
XS Rating Curve= 0 ,0
Exp/Cntr=0.3,0.1

Type RM Length L Ch R = 1 ,74175   ,135,135,135
BEGIN DESCRIPTION:
Mapping XS 0a0dc8ac
END DESCRIPTION:
XS GIS Cut Line= 3
      2441835.38     13566297.74       2440805.8     13565155.38
      2440308.35     13564926.12
#Sta/Elev= 30
  3302.8   337.6  3392.1  336.65  3432.9  336.01  3534.5  334.99  3569.1  334.65
  3676.9  333.39  3819.2  331.89  3961.6  331.07  4006.3  331.67  4090.8  330.31
  4275.4   331.3  4633.9  331.12  4820.2   330.2  4970.6  327.14  4993.5  327.98
  5001.3  325.26  5001.8  324.76  5012.1  325.26    5022  328.07  5039.4  329.22
  5050.7  331.36  5061.8  331.55  5067.9  330.31  5083.8  331.45  5096.4  334.52
  5119.1  337.09  5142.3  339.51  5216.7  340.04  5279.3   341.9  5388.4  346.39
#Mann= 13 ,-1 , 0
  3302.8     .05       0  3392.1    .013       0  3432.9     .05       0
  3534.5    .013       0  3569.1     .05       0  3676.9    .013       0
  3819.2     .04       0  3961.6     .05       0  4633.9     .12       0
  5001.3     .05       0  5012.1     .12       0  5119.1    .035       0
  5279.3     .12       0
Bank Sta=5001.3,5012.1
XS Rating Curve= 0 ,0
Exp/Cntr=0.3,0.1

Type RM Length L Ch R = 1 ,74040   ,75,75,75
BEGIN DESCRIPTION:
Mapping XS 30e98967
END DESCRIPTION:
XS GIS Cut Line= 6
      2441910.56     13566310.19      2441699.62     13565429.97
       2441566.8     13565383.09      2441215.24     13565435.18
      2440795.97     13565034.13      2440293.34     13564846.63
#Sta/Elev= 30
  2976.9  339.88    3167  335.47  3425.5  333.44  3546.7  332.59  3577.5  334.24
  3639.1   335.2  3669.4  334.47  3699.4  329.71  3892.3  329.71    3999  329.71
  4256.1  329.71  4566.6  331.38  4580.8  330.45  4711.9  330.29  4884.9  329.77
    4980  327.87  4985.9  327.51  4993.8  323.83  4994.3  323.33  5004.6  323.83
  5016.3   326.9  5116.6  335.72  5190.7  337.95    5202  338.55  5212.4  340.69
  5223.4  339.78  5266.1  339.97  5413.3  344.58  5457.9  345.88  5513.3  348.04
#Mann= 10 ,-1 , 0
  2976.9     .04       0  3425.5     .05       0  3892.3    .075       0
    3999     .05       0  4711.9     .12       0  4993.8     .05       0
  5004.6     .12       0  5190.7    .035       0  5413.3     .12       0
  5457.9    .035       0
Bank Sta=4993.8,5004.6
XS Rating Curve= 0 ,0
Exp/Cntr=0.3,0.1

Type RM Length L Ch R = 1 ,73965   ,1239,1239,1239
BEGIN DESCRIPTION:
Mapping XS 9f09891c
END DESCRIPTION:
XS GIS Cut Line= 6
      2442025.51     13566206.61      2441835.03     13565500.28
      2441775.14     13565359.65       2441629.3     13565273.72
      2441400.41     13565307.29      2440398.73     13564722.33
#Sta/Elev= 30
  3051.1  338.22  3425.6  332.84  3608.6  335.11  3648.3  333.28  3800.1  336.17
  3841.9  336.04  3847.4  334.83  3918.3   336.3  4018.8  336.06  4028.3  335.99
  4098.2  334.71  4128.1  335.72  4216.1  336.87  4377.1  336.27  4408.1  335.06
  4451.1  330.54  4609.5  329.39  4712.9  328.89  4889.2  329.09  4969.4  327.35
  4995.4  322.89  4995.9  322.39  5006.2  322.89  5006.6  326.47  5049.6  331.31
    5081  331.99  5139.7  336.41  5210.2  338.22  5241.4  340.41  5496.1  346.25
#Mann= 10 ,-1 , 0
  3051.1     .04       0  3608.6     .05       0  4018.8    .075       0
  4028.3    .013       0  4128.1     .05       0  4609.5     .03       0
  4712.9     .12       0  4995.4     .05       0  5006.2     .12       0
  5210.2    .035       0
Bank Sta=4995.4,5006.2
XS Rating Curve= 0 ,0
Exp/Cntr=0.3,0.1

Type RM Length L Ch R = 1 ,72726   ,484,484,484
BEGIN DESCRIPTION:
Mapping XS a3d54166
END DESCRIPTION:
XS GIS Cut Line= 3
      2442233.34     13565918.37      2441899.55     13564721.35
      2441336.05      13564439.6
#Sta/Elev= 30
  3984.3  336.74    4113  336.34  4299.5  333.16  4374.3  334.06  4434.2  333.72
    4499  329.47  4503.3  329.36  4593.8  327.03  4706.7  327.41  4742.9  326.59
  4797.6  326.76  4880.6  323.45  4984.4  324.07  5000.5  320.33    5001  319.83
  5011.9  320.33  5015.6  322.57  5035.4  324.46  5067.5  325.11  5079.7  324.24
  5119.4   325.8  5167.5  325.31  5250.6  325.64  5278.6  326.38  5295.3  328.06
    5316  327.11  5332.7  326.37  5474.2  327.61  5703.8  331.63    5857  334.45
#Mann= 11 ,-1 , 0
  3984.3     .04       0  4374.3     .05       0    4499     .03       0
  4503.3     .05       0  4742.9     .12       0  5000.5     .05       0
  5011.9     .12       0  5035.4    .013       0  5167.5     .05       0
    5316     .04       0  5703.8     .05       0
Bank Sta=5000.5,5011.9
XS Rating Curve= 0 ,0
Exp/Cntr=0.3,0.1

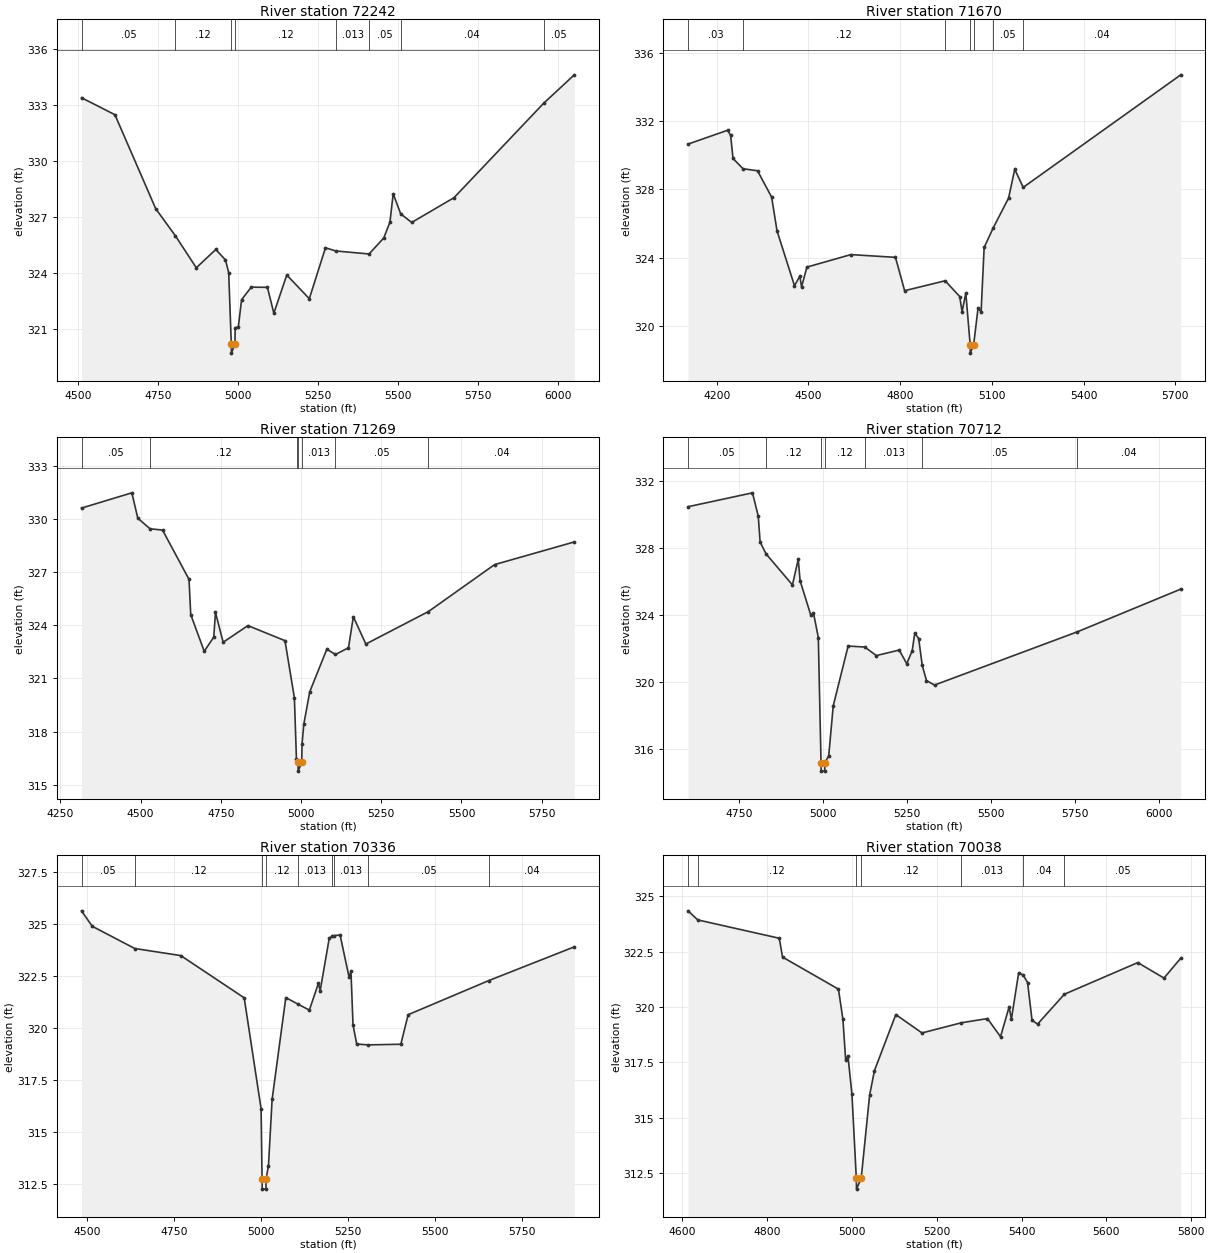
Type RM Length L Ch R = 1 ,72242   ,572,572,572
BEGIN DESCRIPTION:
Mapping XS 21973ba7
END DESCRIPTION:
XS GIS Cut Line= 4
      2442728.51     13564938.34      2442450.76     13564703.99
      2441812.74     13564621.53      2441339.83     13564374.22
#Sta/Elev= 30
  4510.6   333.4  4614.9  332.49  4742.4  327.45  4804.1  325.99  4869.3  324.28
  4930.2  325.26  4960.5   324.7  4970.6  324.01  4978.7   320.2  4979.2   319.7
  4990.2   320.2  4990.7  321.05  5000.8  321.12  5010.9  322.57  5041.1  323.24
  5091.6  323.23  5111.7  321.84  5152.1  323.89  5222.6  322.62  5273.1  325.35
  5305.7  325.18  5409.5  325.02  5455.4  325.88  5474.7  326.73  5484.8  328.25
  5508.3  327.17  5542.6  326.71    5675  328.04  5954.9   333.1    6051  334.63
#Mann= 8 ,-1 , 0
  4510.6     .05       0  4804.1     .12       0  4978.7     .05       0
  4990.2     .12       0  5305.7    .013       0  5409.5     .05       0
  5508.3     .04       0  5954.9     .05       0
Bank Sta=4978.7,4990.2
XS Rating Curve= 0 ,0
Exp/Cntr=0.3,0.1

Type RM Length L Ch R = 1 ,71670   ,401,401,401
BEGIN DESCRIPTION:
Mapping XS 42d8d2cf
END DESCRIPTION:
XS GIS Cut Line= 4
       2442871.8     13564651.92      2442346.59     13564413.19
      2441730.28     13564426.21        2441344.     13564265.63
#Sta/Elev= 30
  4106.1  330.65  4235.7  331.46  4245.4  331.16  4253.3  329.81  4285.9  329.21
  4333.5  329.09  4379.6  327.55  4397.2  325.58  4454.3  322.37  4471.9  322.93
  4477.4   322.3    4495  323.46  4638.9  324.19  4784.6  324.03  4814.6  322.08
  4947.1  322.66  4994.7  321.74  5002.5  320.85  5014.7  321.94  5028.9  318.93
  5029.4  318.43  5040.4  318.93  5054.7  321.06  5064.7  320.85  5074.7  324.61
    5104  325.74  5154.7   327.5  5174.7  329.18  5202.4  328.12  5717.8   334.7
#Mann= 7 ,-1 , 0
  4106.1     .03       0  4285.9     .12       0  4947.1    .013       0
  5028.9     .03       0  5040.4    .013       0    5104     .05       0
  5202.4     .04       0
Bank Sta=5028.9,5040.4
XS Rating Curve= 0 ,0
Exp/Cntr=0.3,0.1

Type RM Length L Ch R = 1 ,71269   ,557,557,557
BEGIN DESCRIPTION:
Mapping XS 446c024b
END DESCRIPTION:
XS GIS Cut Line= 4
      2442928.18      13564608.5      2442424.72     13564400.17
      2442281.49     13564052.95      2441699.97     13563853.32
#Sta/Elev= 30
  4316.3  330.61    4473  331.47  4491.5  330.04  4529.7  329.44  4568.6  329.37
  4651.1  326.59  4656.5   324.6  4698.5  322.53  4728.2  323.33  4733.6  324.72
  4757.5  323.04  4834.6  323.98  4950.1  323.13  4979.4  319.91  4985.8  316.48
  4988.6  316.36  4990.8  316.27  4991.3  315.77  5002.3  316.27  5003.3   317.3
  5008.7  318.41  5027.2  320.24  5080.5  322.65  5107.5  322.35    5148  322.73
  5163.1  324.48  5202.1  322.94  5396.9  324.77  5603.1  327.42  5851.6   328.7
#Mann= 7 ,-1 , 0
  4316.3     .05       0  4529.7     .12       0  4988.6    .013       0
  4990.8     .03       0  5002.3    .013       0  5107.5     .05       0
  5396.9     .04       0
Bank Sta=4990.8,5002.3
XS Rating Curve= 0 ,0
Exp/Cntr=0.3,0.1

Type RM Length L Ch R = 1 ,70712   ,376,376,376
BEGIN DESCRIPTION:
Mapping XS 3d72c43c
END DESCRIPTION:
XS GIS Cut Line= 3
      2443001.97     13564534.71      2442715.52     13563935.76
      2441973.32     13563631.94
#Sta/Elev= 30
  4597.9  330.46  4789.7  331.29  4806.9  329.89  4812.4  328.35  4830.2  327.64
  4908.6  325.79  4925.8  327.32  4931.3  326.04  4963.4  323.97  4971.1  324.12
  4985.5  322.65  4993.6  315.17  4994.1  314.67  5004.6  314.67  5005.1  315.17
  5016.5  315.59  5029.9  318.57  5074.2  322.14  5123.8  322.08    5158  321.57
  5226.1   321.9  5248.7  321.08  5264.8  321.86  5272.4  322.91    5284  322.59
  5294.7  320.99  5307.2  320.08  5331.2  319.81  5756.2  322.99  6063.8  325.54
#Mann= 7 ,-1 , 0
  4597.9     .05       0  4830.2     .12       0  4993.6     .05       0
  5005.1     .12       0  5123.8    .013       0  5294.7     .05       0
  5756.2     .04       0
Bank Sta=4993.6,5005.1
XS Rating Curve= 0 ,0
Exp/Cntr=0.3,0.1

Type RM Length L Ch R = 1 ,70336   ,298,298,298
BEGIN DESCRIPTION:
Mapping XS 71323d90
END DESCRIPTION:
XS GIS Cut Line= 3
      2443100.83     13564274.92      2443019.34     13563866.32
      2442073.12     13563540.78
#Sta/Elev= 30
  4483.6  325.63  4514.1  324.89  4636.7  323.82    4769  323.48  4951.4  321.45
    5000  316.12  5002.8  312.76  5003.3  312.26  5013.9  312.26  5014.4  312.76
  5021.2  313.38  5031.7  316.57  5071.1  321.46    5107  321.14  5138.8  320.86
  5164.8  322.14    5170   321.8    5196  324.31  5205.3  324.42    5211  324.44
  5227.2  324.47  5253.2  322.43  5258.5  322.73  5264.4  320.15    5275  319.23
  5307.9  319.19  5401.9  319.22    5423  320.64  5655.1  322.28  5900.9   323.9
#Mann= 9 ,-1 , 0
  4483.6     .05       0  4636.7     .12       0  5002.8     .05       0
  5014.4     .12       0    5107    .013       0  5205.3     .05       0
    5211    .013       0  5307.9     .05       0  5655.1     .04       0
Bank Sta=5002.8,5014.4
XS Rating Curve= 0 ,0
Exp/Cntr=0.3,0.1

Type RM Length L Ch R = 1 ,70038   ,335,335,335
BEGIN DESCRIPTION:
Mapping XS c63b077e
END DESCRIPTION:
XS GIS Cut Line= 3
      2443161.62     13563825.75      2442988.96     13563558.16
      2442194.72     13563276.05
#Sta/Elev= 30
    4614  324.35  4636.9  323.94  4829.1  323.11  4836.7  322.26  4968.5  320.81
  4979.1  319.44  4985.6  317.59  4990.9  317.79  5000.3  316.06  5010.6  312.27
  5011.1  311.77  5022.2  312.27    5042  316.02  5053.4  317.13  5103.7  319.66
  5165.4  318.83  5258.2  319.29  5319.7  319.48  5350.5  318.66  5370.8  320.01
  5376.1  319.45    5393  321.52  5403.5  321.46  5414.2  321.11  5424.8   319.4
  5437.8  319.23    5501  320.58    5674  322.01  5735.7  321.31  5775.3  322.21
#Mann= 7 ,-1 , 0
    4614     .05       0  4636.9     .12       0  5010.6     .05       0
  5022.2     .12       0  5258.2    .013       0  5403.5     .04       0
    5501     .05       0
Bank Sta=5010.6,5022.2
XS Rating Curve= 0 ,0
Exp/Cntr=0.3,0.1

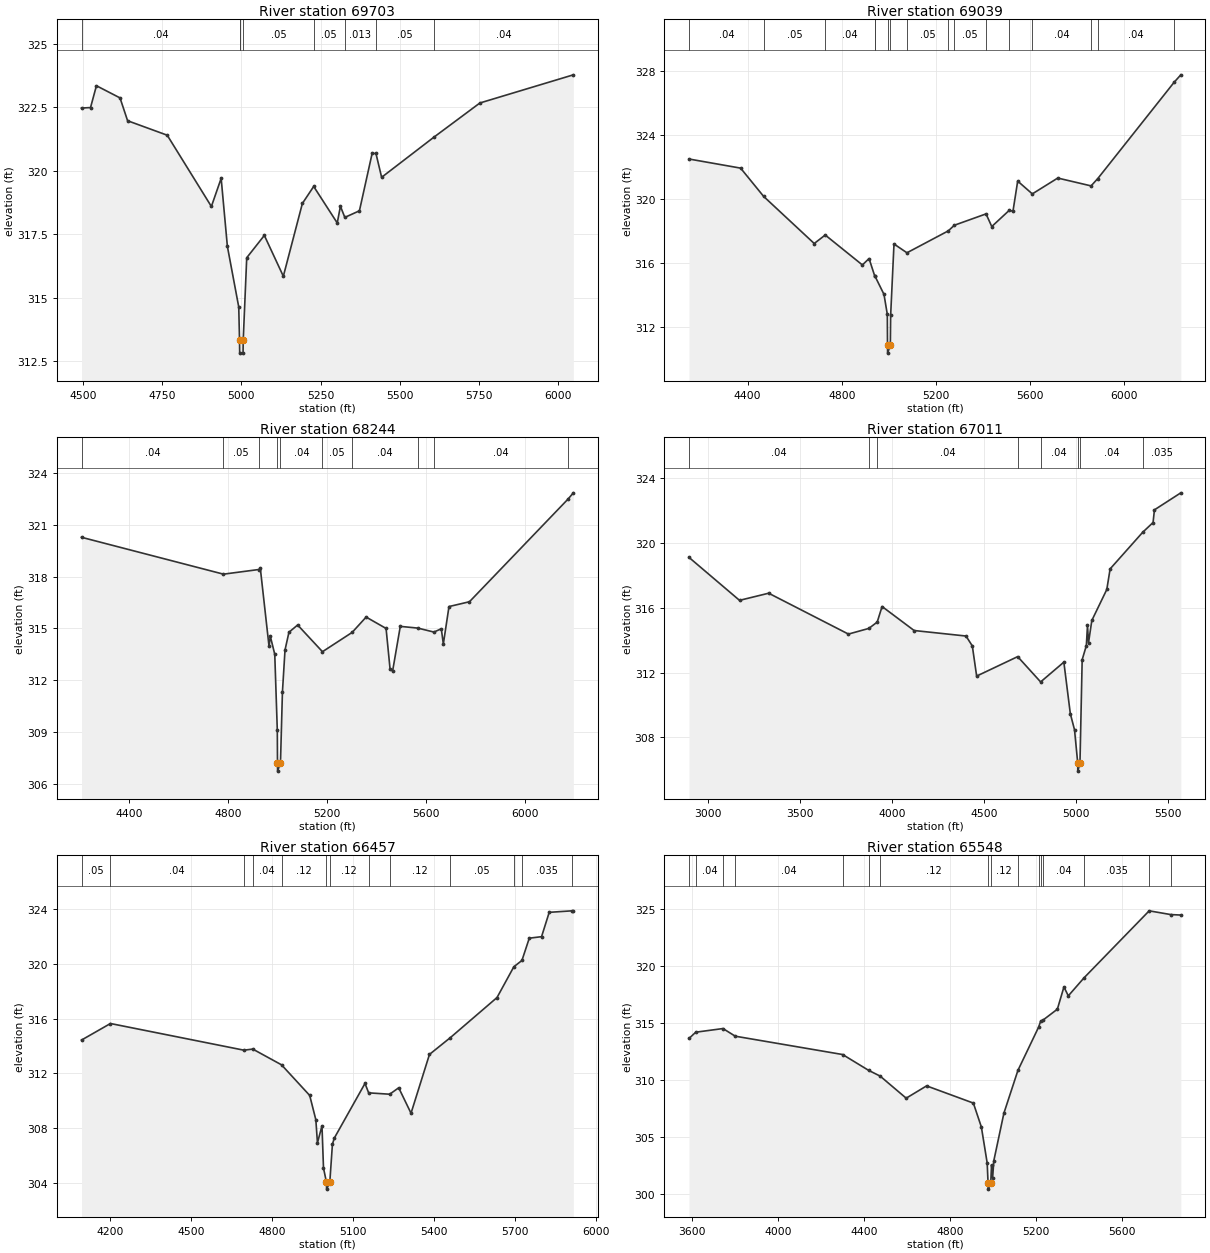
Type RM Length L Ch R = 1 ,69703   ,664,664,664
BEGIN DESCRIPTION:
Mapping XS 98a3d97e
END DESCRIPTION:
XS GIS Cut Line= 3
      2443349.23      13563388.9      2442837.05     13563202.26
      2441830.13     13563163.19
#Sta/Elev= 30
  4495.4  322.47  4523.9  322.49  4542.5  323.35    4617  322.87  4640.9  321.97
    4766   321.4  4905.4  318.59  4936.3   319.7  4955.9  317.02  4991.8  314.63
  4994.2  313.36  4994.3  313.31  4994.8  312.81  5005.4  312.81  5005.9  313.31
    5017  316.57  5072.6  317.45  5132.6  315.84  5192.7  318.71  5228.4  319.38
  5302.8  317.94  5312.8   318.6  5326.7  318.16  5372.8  318.42  5412.9  320.68
    5425  320.68  5442.9  319.74  5607.7  321.32  5753.1  322.67  6048.2  323.78
#Mann= 8 ,-1 , 0
  4495.4     .04       0  4994.2     .05       0  4994.3     .05       0
  5005.9     .05       0  5228.4     .05       0  5326.7    .013       0
    5425     .05       0  5607.7     .04       0
Bank Sta=4994.3,5005.9
XS Rating Curve= 0 ,0
Exp/Cntr=0.3,0.1

Type RM Length L Ch R = 1 ,69039   ,795,795,795
BEGIN DESCRIPTION:
Mapping XS eee2c8bc
END DESCRIPTION:
XS GIS Cut Line= 4
      2443442.04     13563260.39      2442824.03     13562951.39
       2442577.5     13562684.03      2441542.73     13562618.05
#Sta/Elev= 30
  4150.5  322.49  4370.1  321.92  4468.2  320.15  4683.1  317.21  4729.9  317.74
  4887.9  315.87  4916.3  316.27  4939.7  315.21  4940.8  315.19  4979.8  314.03
  4993.9  312.78  4994.7  310.86  4995.2  310.36  5006.8  310.86  5008.1  312.72
  5022.3  317.18  5077.4  316.63  5253.3     318  5278.8  318.35  5413.7  319.06
  5438.1  318.27  5512.2  319.28  5528.3  319.23  5548.3  321.11  5610.5  320.31
  5718.7   321.3  5860.4  320.81    5889  321.27  6213.8  327.29    6242  327.75
#Mann= 16 ,-1 , 0
  4150.5     .04       0  4468.2     .05       0  4729.9     .04       0
  4939.7     .05       0  4940.8     .04       0  4994.7     .04       0
  5006.8     .04       0  5077.4     .05       0  5253.3     .04       0
  5278.8     .05       0  5413.7     .04       0  5512.2    .013       0
  5610.5     .04       0  5860.4     .05       0    5889     .04       0
  6213.8     .05       0
Bank Sta=4994.7,5006.8
XS Rating Curve= 0 ,0
Exp/Cntr=0.3,0.1

Type RM Length L Ch R = 1 ,68244   ,1233,1233,1233
BEGIN DESCRIPTION:
Mapping XS 48578917
END DESCRIPTION:
XS GIS Cut Line= 3
      2443516.95     13563095.99      2443329.46     13562439.76
      2442069.56     13562106.56
#Sta/Elev= 30
  4209.5  320.29  4782.6  318.15  4925.3  318.42  4931.5  318.48  4966.6  313.96
  4971.7  314.55  4989.7   313.5    5000  309.08  5000.7  307.22  5001.2  306.72
  5012.8  307.22  5020.7  311.32  5031.1  313.75    5047  314.78  5082.1   315.2
  5182.3  313.65  5302.1  314.77  5358.6  315.66  5439.1     315  5455.2  312.65
  5465.5  312.53  5496.5  315.12  5567.4  315.02  5632.2  314.79    5662  314.98
  5670.3   314.1  5693.1  316.27  5775.8  316.55  6173.9  322.51  6195.2  322.87
#Mann= 10 ,-1 , 0
  4209.5     .04       0  4782.6     .05       0  4925.3     .04       0
  5000.7     .04       0  5012.8     .04       0  5182.3     .05       0
  5302.1     .04       0  5567.4     .05       0  5632.2     .04       0
  6173.9     .05       0
Bank Sta=5000.7,5012.8
XS Rating Curve= 0 ,0
Exp/Cntr=0.3,0.1

Type RM Length L Ch R = 1 ,67011   ,554,554,554
BEGIN DESCRIPTION:
Mapping XS 9212273c
END DESCRIPTION:
XS GIS Cut Line= 3
        2443576.     13562970.97      2443843.35     13561998.78
      2442313.19     13561339.53
#Sta/Elev= 30
    2895   319.1  3169.9  316.45  3328.3  316.89    3762  314.37    3873  314.72
  3918.5  315.11    3945  316.07  4119.2  314.59  4401.3  314.25  4435.7  313.64
  4459.2  311.78  4682.3  312.98  4807.1  311.42  4933.4  312.64  4968.6  309.46
  4991.4  308.47  5008.8  306.42  5009.3  305.92    5021  306.42    5033  312.79
  5055.7  313.66  5061.9   314.9  5067.4  313.83  5085.5  315.21  5166.9  317.12
    5185  318.39  5362.3  320.65  5418.5  321.25  5425.9  322.03  5569.4  323.08
#Mann= 8 ,-1 , 0
    2895     .04       0    3873     .05       0  3918.5     .04       0
  4682.3     .12       0  4807.1     .04       0  5008.8     .04       0
    5021     .04       0  5362.3    .035       0
Bank Sta=5008.8,5021
XS Rating Curve= 0 ,0
Exp/Cntr=0.3,0.1

Type RM Length L Ch R = 1 ,66457   ,909,909,909
BEGIN DESCRIPTION:
Mapping XS 74f5ed4d
END DESCRIPTION:
XS GIS Cut Line= 3
      2443933.62     13562063.02        2443543.     13561511.81
      2442510.01     13561021.35
#Sta/Elev= 30
  4095.5  314.44  4202.6  315.65  4696.1   313.7  4728.9  313.78  4835.2  312.63
  4939.5  310.39  4962.2  308.61  4968.1  306.92  4984.9  308.17  4990.5  305.08
  5001.5  304.04    5002  303.54  5013.8  304.04  5023.5  306.82  5030.4  307.27
    5144  311.27  5157.5  310.58  5235.3  310.48  5268.7  310.95  5314.2  309.09
  5382.4  313.39  5459.8  314.62  5632.3  317.55  5694.5   319.8  5724.4  320.26
  5751.6  321.89    5797     322  5825.3  323.78  5909.4  323.89  5914.6  323.89
#Mann= 13 ,-1 , 0
  4095.5     .05       0  4202.6     .04       0  4696.1     .12       0
  4728.9     .04       0  4835.2     .12       0  5001.5     .05       0
  5013.8     .12       0  5157.5     .04       0  5235.3     .12       0
  5459.8     .05       0  5694.5     .12       0  5724.4    .035       0
  5909.4     .05       0
Bank Sta=5001.5,5013.8
XS Rating Curve= 0 ,0
Exp/Cntr=0.3,0.1

Type RM Length L Ch R = 1 ,65548   ,405,405,405
BEGIN DESCRIPTION:
Mapping XS 0ba03cbd
END DESCRIPTION:
XS GIS Cut Line= 3
      2443996.12     13561977.95      2443385.01     13560769.62
      2442471.84     13560943.22
#Sta/Elev= 30
  3587.6  313.67  3619.1  314.22  3745.5  314.54  3802.4  313.87  4301.1  312.26
  4421.8  310.87    4475  310.37  4596.1  308.43  4690.8  309.51    4908     308
  4945.2   305.9  4972.2  302.74  4976.3  300.95  4976.8  300.45  4988.6  300.95
  4992.4  302.59  4997.5  301.44  5002.8  302.93  5049.7  307.11  5114.9  310.87
  5210.6  314.65    5221  315.21  5229.1  315.25    5298  316.24  5328.5  318.19
  5348.8  317.41  5422.3     319  5724.3  324.87  5824.9  324.54  5871.2   324.5
#Mann= 16 ,-1 , 0
  3587.6     .05       0  3619.1     .04       0  3745.5     .05       0
  3802.4     .04       0  4301.1     .12       0  4421.8     .04       0
    4475     .12       0  4976.3     .05       0  4988.6     .12       0
  5114.9     .04       0  5210.6     .12       0    5221     .05       0
  5229.1     .04       0  5422.3    .035       0  5724.3     .05       0
  5824.9    .035       0
Bank Sta=4976.3,4988.6
XS Rating Curve= 0 ,0
Exp/Cntr=0.3,0.1

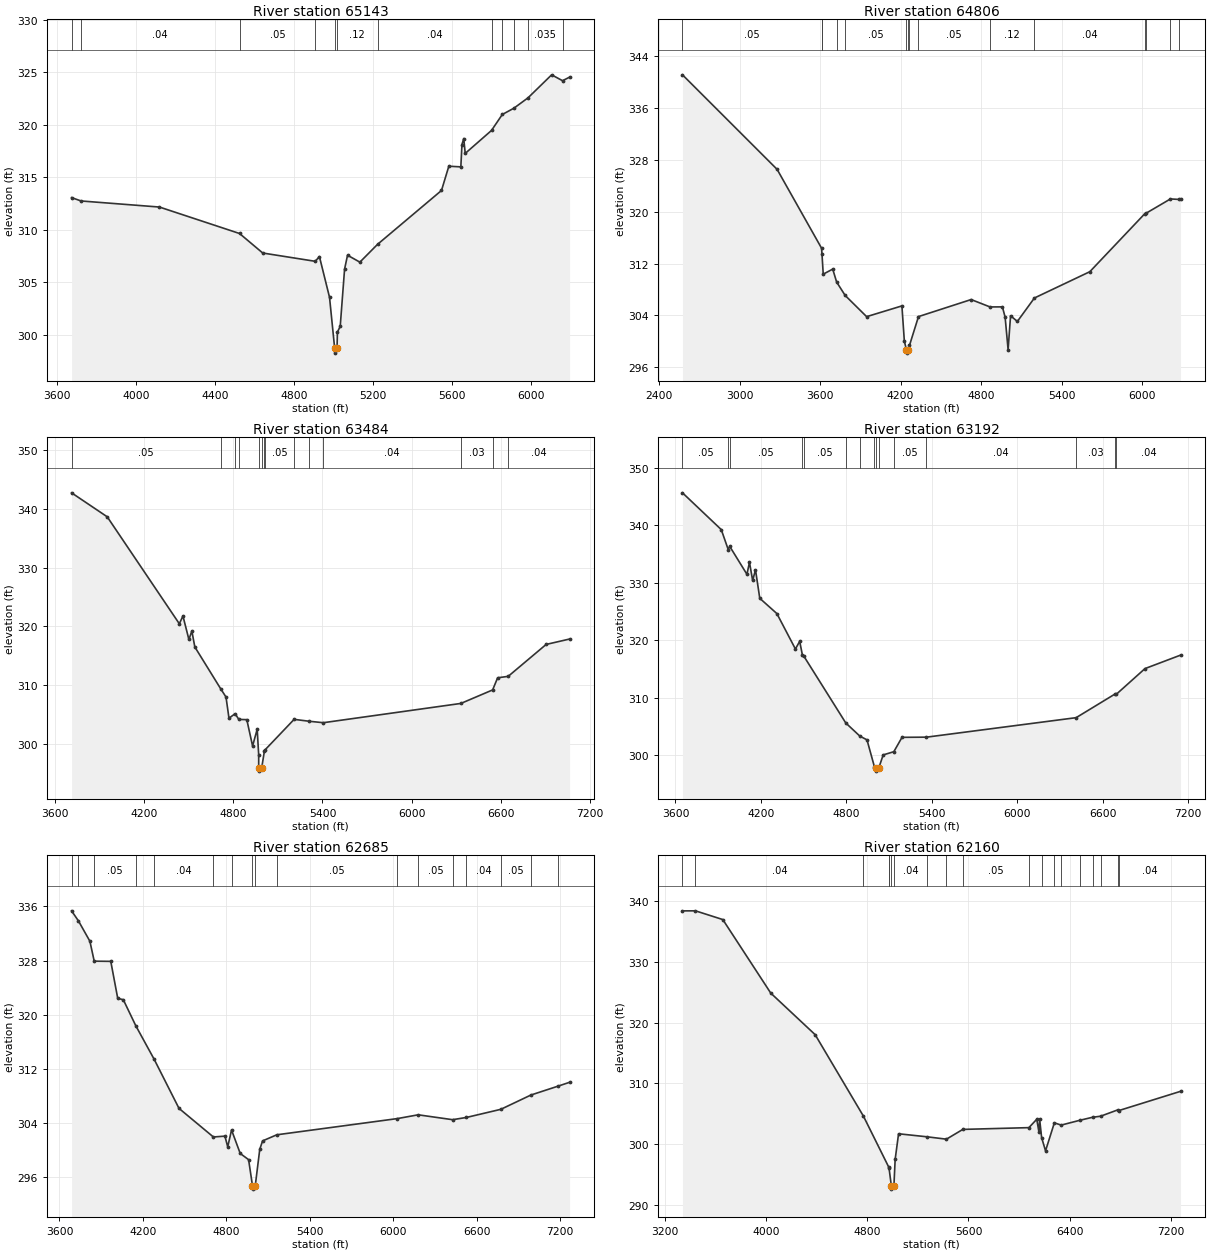
Type RM Length L Ch R = 1 ,65143   ,337,337,337
BEGIN DESCRIPTION:
Mapping XS 471ce7ba
END DESCRIPTION:
XS GIS Cut Line= 4
      2443969.86     13561687.53      2443865.69     13560632.81
      2443323.16     13560376.73       2442559.3     13560771.68
#Sta/Elev= 30
  3675.2  313.06  3723.3  312.74  4119.9  312.16    4525  309.64  4642.4  307.78
  4907.9  306.99  4929.2  307.44  4980.3  303.56  5006.1  298.74  5006.6  298.24
  5018.4  298.74  5020.3  300.25  5034.4  300.79  5056.5  306.25  5071.4  307.57
  5133.9  306.91  5223.5  308.61  5546.8  313.74  5583.9  316.05  5644.7  315.99
  5650.3  318.12  5659.4  318.69  5666.8  317.27  5799.8  319.46  5854.4  320.98
  5913.1  321.58  5984.7  322.57  6104.1  324.76  6159.2   324.2  6194.9  324.54
#Mann= 12 ,-1 , 0
  3675.2     .05       0  3723.3     .04       0    4525     .05       0
  4907.9     .12       0  5006.1     .05       0  5018.4     .12       0
  5223.5     .04       0  5799.8     .05       0  5854.4    .035       0
  5913.1     .05       0  5984.7    .035       0  6159.2     .12       0
Bank Sta=5006.1,5018.4
XS Rating Curve= 0 ,0
Exp/Cntr=0.3,0.1

Type RM Length L Ch R = 1 ,64806   ,1322,1322,1322
BEGIN DESCRIPTION:
Mapping XS fdcef86c
END DESCRIPTION:
XS GIS Cut Line= 4
      2446222.44      13560038.2      2444251.98     13560328.99
      2443475.07     13560203.12      2442638.73     13560614.79
#Sta/Elev= 30
  2574.7  341.13  3279.7  326.54  3610.9  314.37  3614.3  313.43  3623.4  310.36
  3694.1  311.14  3723.4  309.14  3786.6  307.08  3946.8   303.8  4209.7  305.46
  4227.9  300.01  4243.8  298.67  4244.3  298.17  4256.3  298.67  4266.1  299.36
  4333.2  303.81  4725.5  306.44  4866.4   305.3  4958.5  305.31  4978.8  303.72
    5001   298.7  5019.3  303.94    5070  303.06    5197  306.68    5610  310.74
    6020   319.7  6028.8  319.76  6210.6  321.97  6273.1   321.9  6285.7  321.93
#Mann= 15 ,-1 , 0
  2574.7     .05       0  3610.9    .013       0  3614.3     .05       0
  3723.4     .12       0  3786.6     .05       0  4243.8     .05       0
  4256.3     .05       0  4266.1     .12       0  4333.2     .05       0
  4866.4     .12       0    5197     .04       0    6020     .05       0
  6028.8     .04       0  6210.6     .05       0  6273.1    .035       0
Bank Sta=4243.8,4256.3
XS Rating Curve= 0 ,0
Exp/Cntr=0.3,0.1

Type RM Length L Ch R = 1 ,63484   ,292,292,292
BEGIN DESCRIPTION:
Mapping XS 202a46dd
END DESCRIPTION:
XS GIS Cut Line= 4
      2446015.03     13559655.38      2444721.59     13559681.42
      2443345.73     13559911.46      2442833.58      13560336.8
#Sta/Elev= 30
  3710.1  342.73  3950.2  338.65  4435.8  320.45  4460.3  321.77  4500.3  317.78
  4520.3  319.21  4540.3   316.5  4713.3  309.43  4750.3  307.98  4770.3  304.38
  4811.7  305.14  4836.7  304.17  4890.4  304.13  4929.3  299.65  4960.4   302.5
  4970.4  298.14  4970.5  295.87    4971  295.37  4990.3  295.87  5008.7  298.74
  5012.2  298.96  5209.1  304.18  5309.3  303.86  5405.7  303.61  6332.3  306.89
  6546.2  309.19  6579.7  311.25    6651   311.5  6906.6  316.93  7064.5  317.85
#Mann= 14 ,-1 , 0
  3710.1     .05       0  4713.3    .013       0  4811.7     .12       0
  4836.7     .05       0  4970.5     .05       0  4990.3     .05       0
  5008.7     .04       0  5012.2     .05       0  5209.1     .12       0
  5309.3     .05       0  5405.7     .04       0  6332.3     .03       0
  6546.2    .013       0    6651     .04       0
Bank Sta=4970.5,4990.3
XS Rating Curve= 0 ,0
Exp/Cntr=0.3,0.1

Type RM Length L Ch R = 1 ,63192   ,507,507,507
BEGIN DESCRIPTION:
Mapping XS a7e6fe2b
END DESCRIPTION:
XS GIS Cut Line= 4
      2446067.12     13559438.37      2444838.78     13559390.62
      2443271.94     13559798.61      2442824.89     13560267.36
#Sta/Elev= 30
  3649.6  345.68  3921.9  339.28  3970.6  335.81  3981.2  336.36  4102.1   331.5
  4119.8   333.6  4142.1  330.43  4162.1  332.29  4192.1  327.33  4312.2  324.67
  4442.3  318.51  4472.3  319.84    4492  317.39  4500.3  317.31  4795.9  305.64
  4894.8  303.35  4944.8   302.7  4997.2  297.99  5007.2  297.76  5007.7  297.26
    5027  297.76  5058.4  300.08  5133.2  300.64  5190.7  303.14  5362.5  303.17
  6412.9  306.56  6684.3  310.65  6693.7   310.6  6896.3   315.1  7145.7  317.44
#Mann= 15 ,-1 , 0
  3649.6     .05       0  3970.6     .04       0  3981.2     .05       0
    4492     .04       0  4500.3     .05       0  4795.9    .013       0
  4894.8     .05       0  4997.2     .04       0  5007.2     .04       0
    5027     .04       0  5133.2     .05       0  5362.5     .04       0
  6412.9     .03       0  6684.3    .013       0  6693.7     .04       0
Bank Sta=5007.2,5027
XS Rating Curve= 0 ,0
Exp/Cntr=0.3,0.1

Type RM Length L Ch R = 1 ,62685   ,525,525,525
BEGIN DESCRIPTION:
Mapping XS cc7cdb8e
END DESCRIPTION:
XS GIS Cut Line= 3
      2445786.68     13559061.63       2444474.2     13559009.55
      2442224.18     13559285.59
#Sta/Elev= 30
  3687.1  335.35  3736.9  333.85  3818.9  330.86  3849.9  327.92    3969  327.89
    4019  322.43  4059.1  322.23    4149  318.38  4280.8  313.44  4459.4  306.19
  4706.5  301.97  4789.6  302.09  4809.7  300.51  4837.2     303  4899.7  299.53
  4959.8  298.62  4987.8  294.77  4988.3  294.27  5007.7  294.77  5040.1  300.15
  5060.3  301.39  5162.5  302.29  6028.5  304.68  6179.1  305.24  6426.3  304.52
  6525.7  304.85    6773  306.05  6989.4  308.16  7182.9  309.46  7267.5  310.04
#Mann= 17 ,-1 , 0
  3687.1     .05       0  3736.9     .04       0  3849.9     .05       0
    4149    .013       0  4280.8     .04       0  4706.5    .013       0
  4837.2     .04       0  4987.8     .04       0  5007.7     .04       0
  5162.5     .05       0  6028.5     .12       0  6179.1     .05       0
  6426.3    .013       0  6525.7     .04       0    6773     .05       0
  6989.4     .04       0  7182.9     .05       0
Bank Sta=4987.8,5007.7
XS Rating Curve= 0 ,0
Exp/Cntr=0.3,0.1

Type RM Length L Ch R = 1 ,62160   ,332,332,332
BEGIN DESCRIPTION:
Mapping XS 6ed96a15
END DESCRIPTION:
XS GIS Cut Line= 3
      2446146.05     13558832.46      2444614.82     13558483.51
      2442288.38      13558931.1
#Sta/Elev= 30
  3337.8  338.42  3440.3  338.43  3656.8  336.99  4036.3  324.87  4387.1  318.03
  4769.5  304.59    4970  296.18  4971.7  296.04  4990.3  293.08  4990.8  292.58
  5010.2  293.08  5020.1  297.48  5047.1   301.7  5272.3   301.2  5425.7  300.81
  5555.4  302.42  6077.9  302.71  6140.3  304.09  6157.8  301.95  6162.9  304.13
  6178.6  301.07  6209.7  298.89  6279.4   303.5  6333.7  303.13  6480.8  303.92
  6581.5  304.42  6644.9  304.59  6782.9  305.65  6787.7  305.51  7277.4  308.69
#Mann= 19 ,-1 , 0
  3337.8     .05       0  3440.3     .04       0  4769.5     .05       0
    4970    .013       0  4971.7     .04       0  4990.3     .04       0
  5010.2     .04       0  5272.3    .013       0  5425.7     .04       0
  5555.4     .05       0  6077.9     .12       0  6178.6     .05       0
  6279.4    .013       0  6333.7     .05       0  6480.8     .04       0
  6581.5    .013       0  6644.9     .04       0  6782.9    .013       0
  6787.7     .04       0
Bank Sta=4990.3,5010.2
XS Rating Curve= 0 ,0
Exp/Cntr=0.3,0.1

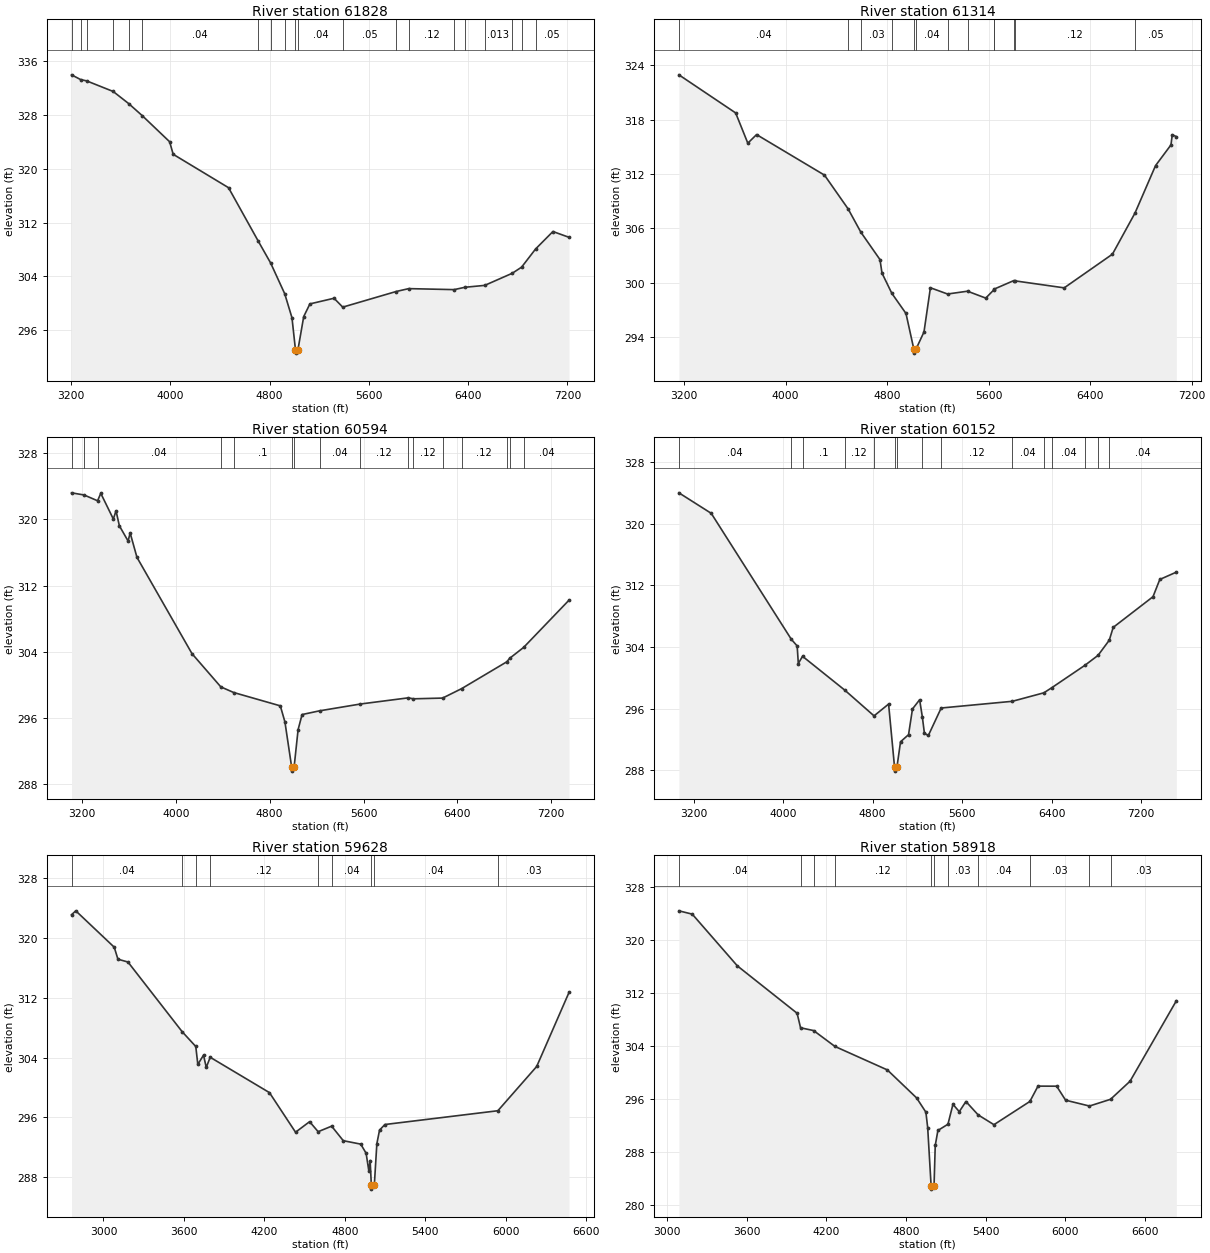
Type RM Length L Ch R = 1 ,61828   ,514,514,514
BEGIN DESCRIPTION:
Mapping XS 1cdef9ff
END DESCRIPTION:
XS GIS Cut Line= 3
      2446234.63     13558671.01      2444984.62     13558098.09
      2442408.22     13558639.39
#Sta/Elev= 30
  3204.9  333.95  3278.5  333.24  3326.6  333.05  3540.2  331.48  3666.5  329.66
  3775.5  327.87  3995.2  324.01  4023.7  322.15  4469.5  317.19  4707.6   309.3
  4808.7  306.01  4922.3  301.44  4980.8  297.87  5008.9  293.12  5009.4  292.62
  5028.9  293.12  5075.4  298.05  5125.2  299.93  5319.6  300.77  5389.7  299.45
  5819.7  301.77  5921.3   302.2  6286.9  302.05  6374.3   302.4  6533.4  302.68
  6755.4  304.48  6830.7  305.39  6943.5  308.09  7083.1  310.68  7212.6  309.82
#Mann= 20 ,-1 , 0
  3204.9     .05       0  3278.5     .04       0  3326.6     .05       0
  3540.2     .04       0  3666.5     .05       0  3775.5     .04       0
  4707.6    .013       0  4808.7     .03       0  4922.3     .04       0
  5008.9     .04       0  5028.9     .04       0  5389.7     .05       0
  5819.7     .12       0  5921.3     .12       0  6286.9    .013       0
  6374.3     .12       0  6533.4    .013       0  6755.4     .05       0
  6830.7     .12       0  6943.5     .05       0
Bank Sta=5008.9,5028.9
XS Rating Curve= 0 ,0
Exp/Cntr=0.3,0.1

Type RM Length L Ch R = 1 ,61314   ,720,720,720
BEGIN DESCRIPTION:
Mapping XS 68d4a4ab
END DESCRIPTION:
XS GIS Cut Line= 3
       2446161.7     13558129.34      2444500.24     13557712.67
      2442323.12     13558072.05
#Sta/Elev= 30
  3159.7  322.94    3607  318.73  3702.7  315.39  3771.7  316.34  4306.9  311.86
  4492.6  308.14  4593.3  305.56    4744  302.53  4759.9  301.04  4837.6   298.8
  4948.9  296.58  5009.8   292.7  5010.3   292.2  5029.8   292.7  5090.8  294.54
  5141.4  299.42  5276.4  298.73  5433.7  299.04  5577.3  298.28  5642.7  299.21
  5645.1  299.28  5796.5   300.2  5808.6  300.18  6195.5  299.41  6575.5  303.13
  6753.2  307.67  6915.1  312.91  7036.7   315.2  7046.9  316.33  7079.2  316.11
#Mann= 13 ,-1 , 0
  3159.7     .04       0  4492.6    .013       0  4593.3     .03       0
  4837.6     .04       0  5009.8     .04       0  5029.8     .04       0
  5276.4     .05       0  5433.7     .12       0  5642.7     .05       0
  5645.1     .12       0  5796.5    .013       0  5808.6     .12       0
  6753.2     .05       0
Bank Sta=5009.8,5029.8
XS Rating Curve= 0 ,0
Exp/Cntr=0.3,0.1

Type RM Length L Ch R = 1 ,60594   ,442,442,442
BEGIN DESCRIPTION:
Mapping XS 57c9052b
END DESCRIPTION:
XS GIS Cut Line= 3
      2446151.24     13556269.98      2444625.24     13556973.09
      2442163.51     13557670.49
#Sta/Elev= 30
  3112.1  323.21  3218.9  322.95    3334  322.25  3361.2  323.15  3468.2  320.05
  3491.2  321.04  3519.6  319.23    3594  317.39  3611.5  318.37  3669.5  315.42
  4138.6  303.79  4384.2  299.78    4494   299.1  4891.1  297.49  4930.3  295.55
  4987.6  290.11  4988.1  289.61  5008.6  290.11  5042.5  294.61  5076.4  296.44
  5225.2  296.89    5572  297.71  5982.4  298.46  6023.7  298.34  6273.8  298.43
    6436  299.57    6821  302.81  6845.2  303.23  6964.5  304.55  7350.9  310.25
#Mann= 16 ,-1 , 0
  3112.1     .04       0  3218.9     .05       0    3334     .04       0
  4384.2    .013       0    4494      .1       0  4987.6     .05       0
  5008.6      .1       0  5225.2     .04       0    5572     .12       0
  5982.4    .013       0  6023.7     .12       0  6273.8     .05       0
    6436     .12       0    6821     .04       0  6845.2     .12       0
  6964.5     .04       0
Bank Sta=4987.6,5008.6
XS Rating Curve= 0 ,0
Exp/Cntr=0.3,0.1

Type RM Length L Ch R = 1 ,60152   ,524,524,524
BEGIN DESCRIPTION:
Mapping XS cfcc1009
END DESCRIPTION:
XS GIS Cut Line= 4
      2446093.98     13556176.22      2444442.95     13556488.71
      2444015.87     13556842.88      2441839.42      13557238.6
#Sta/Elev= 30
  3068.6  324.02  3357.7  321.36  4073.4  305.02    4126  304.15  4136.2  301.87
    4174  302.81  4550.7  298.43  4813.2  295.08  4943.3  296.61  4996.6  288.41
  4997.1  287.91  5017.7  288.41  5050.1  291.72  5121.7  292.64  5156.9  295.98
  5220.7  297.17  5244.5  294.99  5263.7  292.81  5298.8  292.54  5413.5   296.1
  6049.4  296.97  6331.1  298.07  6401.9  298.73  6699.2  301.65  6815.7  302.93
  6916.2   304.9  6951.2  306.56    7307  310.54  7367.9  312.78  7515.9  313.73
#Mann= 15 ,-1 , 0
  3068.6     .04       0  4073.4    .013       0    4174      .1       0
  4550.7     .12       0  4813.2     .05       0  4996.6     .05       0
  5017.7     .05       0  5244.5     .04       0  5413.5     .12       0
  6049.4     .04       0  6331.1     .05       0  6401.9     .04       0
  6699.2     .03       0  6815.7     .05       0  6916.2     .04       0
Bank Sta=4996.6,5017.7
XS Rating Curve= 0 ,0
Exp/Cntr=0.3,0.1

Type RM Length L Ch R = 1 ,59628   ,710,710,710
BEGIN DESCRIPTION:
Mapping XS 074ecfe1
END DESCRIPTION:
XS GIS Cut Line= 3
      2446015.88     13556004.34      2444146.07     13556421.01
      2442354.38     13556311.63
#Sta/Elev= 30
  2762.1  323.07  2793.7  323.59  3080.6  318.73  3108.1  317.13  3183.1  316.75
  3587.5  307.44  3688.9  305.47    3704  303.08  3746.5  304.31    3767  302.68
  3796.4  304.03  4238.3  299.31    4433  294.02  4537.9  295.43  4601.6  294.09
  4702.2  294.83    4789  292.89  4919.3  292.43  4959.4  291.21  4979.4  288.88
  4989.4  290.24  4998.5  286.92    4999  286.42  5020.5  286.92  5039.5  292.49
  5059.5   294.3  5099.6  295.05  5942.2  296.89  6231.7   302.8  6472.8  312.69
#Mann= 9 ,-1 , 0
  2762.1     .04       0  3587.5    .013       0  3688.9     .05       0
  3796.4     .12       0  4601.6     .03       0  4702.2     .04       0
  4998.5     .04       0  5020.5     .04       0  5942.2     .03       0
Bank Sta=4998.5,5020.5
XS Rating Curve= 0 ,0
Exp/Cntr=0.3,0.1

Type RM Length L Ch R = 1 ,58918   ,438,438,438
BEGIN DESCRIPTION:
Mapping XS 90c43823
END DESCRIPTION:
XS GIS Cut Line= 3
      2446135.69      13555858.5      2444359.62     13555889.76
      2442398.08     13556097.88
#Sta/Elev= 30
  3088.9  324.39  3189.6  323.89  3529.7  316.09  3979.7  308.96  4005.7  306.77
  4104.1  306.35  4264.7  303.96  4659.8  300.42    4880  296.21  4950.3  294.05
  4963.9   291.7  4989.6  282.96  4990.1  282.46  5011.7  282.96  5020.7  289.04
  5040.8   291.3  5116.5  292.24  5154.2  295.24  5201.7  294.13    5252  295.66
  5344.3  293.64  5463.2  292.17  5733.9  295.67  5795.1  297.98  5935.8  297.97
  6003.1  295.86  6182.9  294.98  6341.5  295.99  6488.9  298.72  6837.8  310.84
#Mann= 11 ,-1 , 0
  3088.9     .04       0  4005.7    .013       0  4104.1     .05       0
  4264.7     .12       0  4989.6     .05       0  5011.7     .12       0
  5116.5     .03       0  5344.3     .04       0  5733.9     .03       0
  6182.9     .04       0  6341.5     .03       0
Bank Sta=4989.6,5011.7
XS Rating Curve= 0 ,0
Exp/Cntr=0.3,0.1