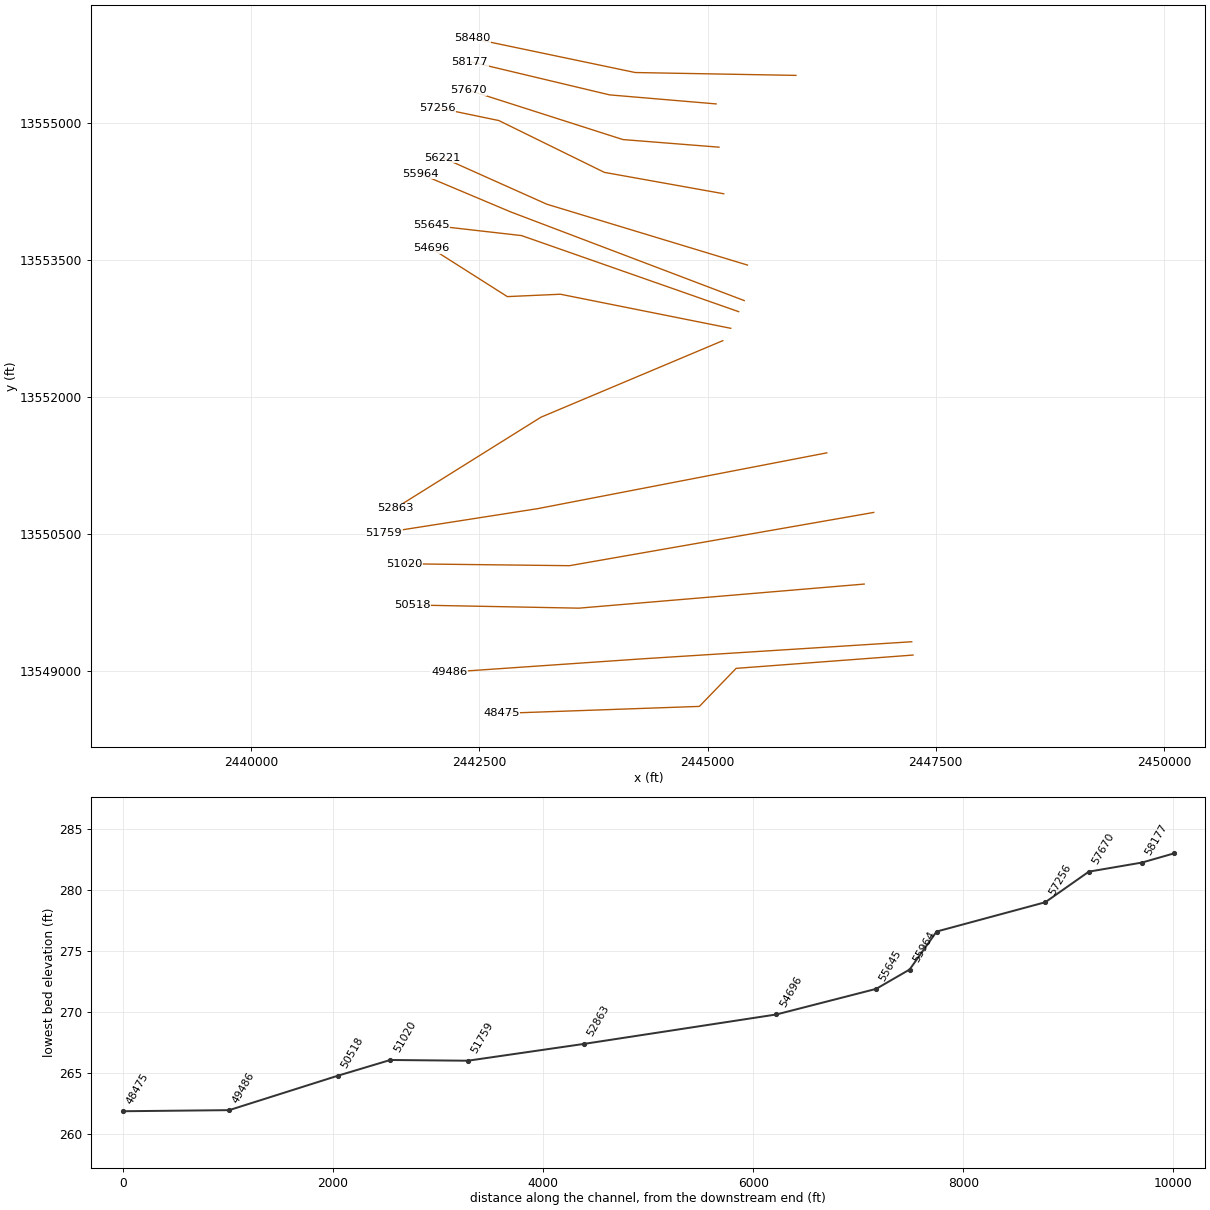
HEC-RAS study YORKTOWN CREEK.prj: YORKTOWN CREEK Base Level Engineering

--- YORKTOWN CREEK.g01 (geometry) --- (continued)

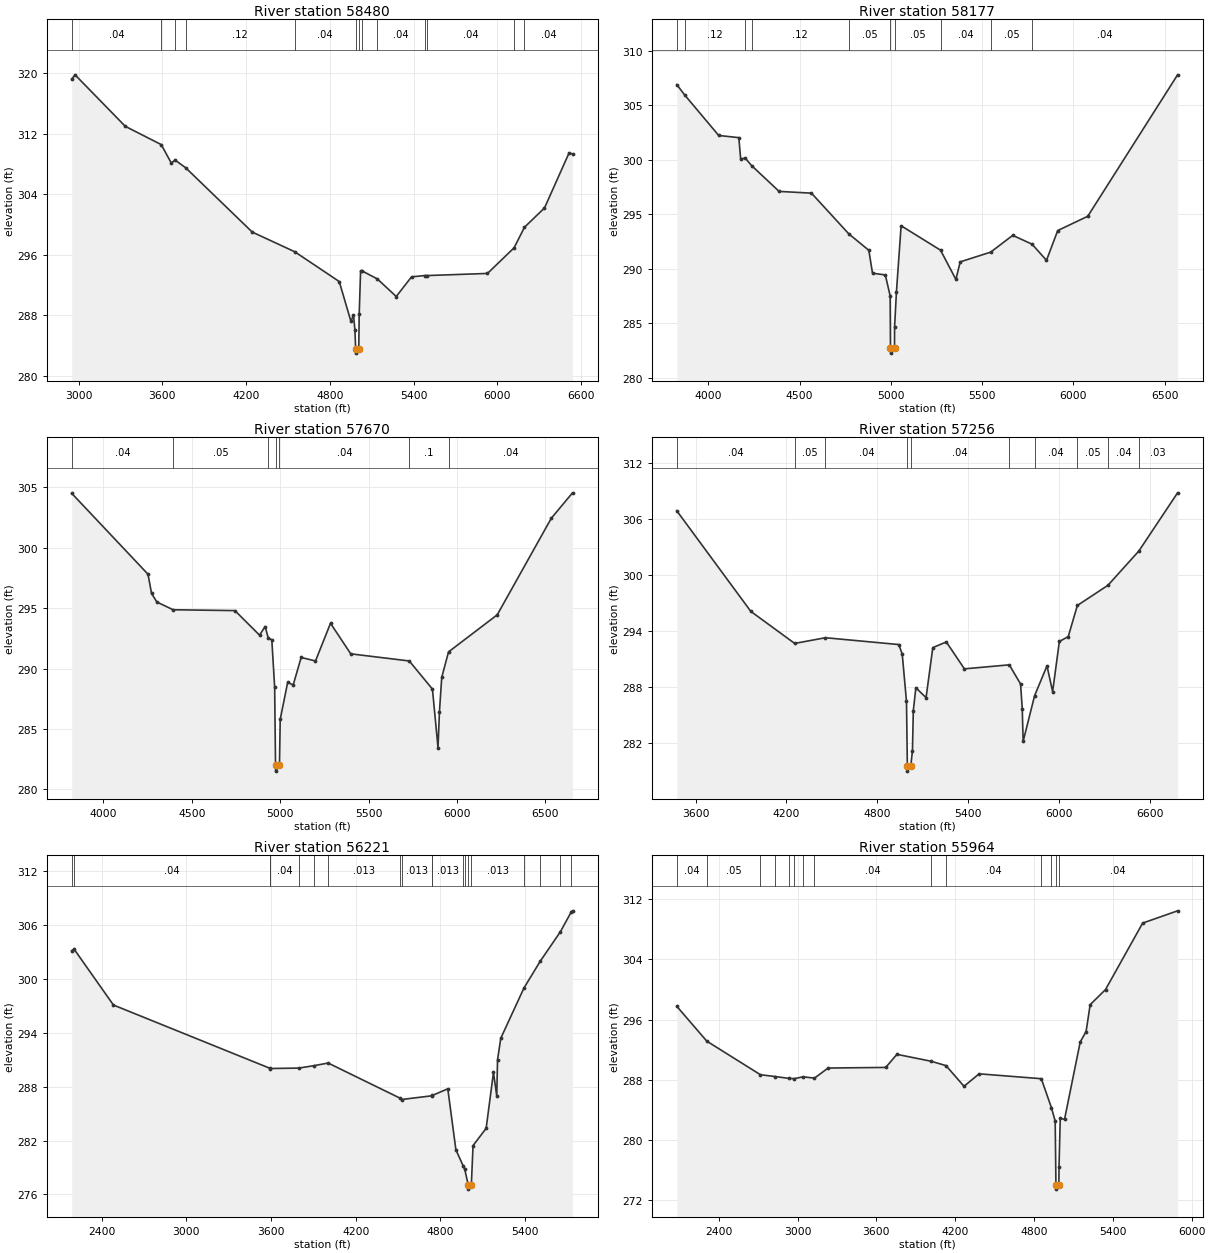
Type RM Length L Ch R = 1 ,58480   ,303,303,303
BEGIN DESCRIPTION:
Mapping XS 722f5d15
END DESCRIPTION:
XS GIS Cut Line= 3
      2445968.95     13555519.96      2444208.57     13555551.21
      2442418.42      13555925.9
#Sta/Elev= 30
  2950.1  319.26  2974.1  319.82  3334.1  313.01  3591.9  310.59  3664.2  308.14
  3690.3  308.55  3766.9  307.53  4244.3  299.02  4548.6  296.42  4867.7  292.48
  4951.7   287.2  4969.8  288.08    4980  286.09  4985.5  283.51    4986  283.01
  5007.6  283.51  5010.7  288.13  5020.9  293.91  5028.2  293.91  5140.4  292.83
  5276.3   290.5  5385.9   293.1    5480  293.27  5499.7  293.27  5930.2  293.55
    6121  296.94  6195.4  299.66  6338.9  302.21  6514.3  309.46  6539.7  309.37
#Mann= 13 ,-1 , 0
  2950.1     .04       0  3591.9    .013       0  3690.3     .05       0
  3766.9     .12       0  4548.6     .04       0  4985.5     .04       0
  5007.6     .04       0  5028.2     .03       0  5140.4     .04       0
    5480     .03       0  5499.7     .04       0    6121     .03       0
  6195.4     .04       0
Bank Sta=4985.5,5007.6
XS Rating Curve= 0 ,0
Exp/Cntr=0.3,0.1

Type RM Length L Ch R = 1 ,58177   ,507,507,507
BEGIN DESCRIPTION:
Mapping XS e8a1e67e
END DESCRIPTION:
XS GIS Cut Line= 3
      2445093.98     13555207.46      2443927.32     13555306.42
      2442396.08     13555671.01
#Sta/Elev= 30
  3826.6  306.89  3870.1  305.93  4056.4  302.22  4166.8  302.02  4176.8  300.05
  4201.6  300.15  4236.5  299.46  4387.6  297.09  4564.9  296.93  4769.9  293.19
  4879.3  291.69  4899.4  289.59  4969.7  289.43  4996.1  287.51  4997.9  282.76
  4998.4  282.26    5020  282.76  5020.4  284.67  5030.7  287.91  5056.2  293.94
  5272.3   291.7  5356.4  289.02  5380.2  290.63    5547  291.52    5668  293.06
  5773.9  292.25    5853  290.77  5914.6   293.5  6079.2  294.81  6571.5  307.78
#Mann= 10 ,-1 , 0
  3826.6     .04       0  3870.1     .12       0  4201.6     .04       0
  4236.5     .12       0  4769.9     .05       0  4997.9     .05       0
    5020     .05       0  5272.3     .04       0    5547     .05       0
  5773.9     .04       0
Bank Sta=4997.9,5020
XS Rating Curve= 0 ,0
Exp/Cntr=0.3,0.1

Type RM Length L Ch R = 1 ,57670   ,414,414,414
BEGIN DESCRIPTION:
Mapping XS 9401bfb0
END DESCRIPTION:
XS GIS Cut Line= 3
      2445125.23     13554733.51      2444073.16     13554816.84
      2442380.48      13555358.5
#Sta/Elev= 30
  3820.5  304.51  4252.1  297.81  4272.1  296.22  4302.2  295.51    4394  294.87
  4743.6   294.8  4882.7  292.77  4914.9  293.48  4931.9  292.53  4952.3  292.39
  4968.4  288.46  4973.4  282.01  4973.9  281.51  4995.5  282.01  4999.9   285.8
  5041.9  288.85  5073.4  288.65  5118.3  290.92  5199.4  290.63  5284.3  293.75
  5398.9  291.22  5729.9  290.63  5860.9   288.3  5892.4  283.45  5900.5  286.43
  5913.4  289.27  5951.8  291.38  6227.3  294.45  6532.9  302.44  6653.1  304.55
#Mann= 7 ,-1 , 0
  3820.5     .04       0    4394     .05       0  4931.9     .04       0
  4973.4     .04       0  4995.5     .04       0  5729.9      .1       0
  5951.8     .04       0
Bank Sta=4973.4,4995.5
XS Rating Curve= 0 ,0
Exp/Cntr=0.3,0.1

Type RM Length L Ch R = 1 ,57256   ,1035,1035,1035
BEGIN DESCRIPTION:
Mapping XS 7d6e0323
END DESCRIPTION:
XS GIS Cut Line= 4
      2445177.33     13554223.09      2443870.03     13554457.46
      2442713.78     13555025.17      2442038.34     13555165.46
#Sta/Elev= 30
  3475.8  306.85  3964.5  296.09  4254.1  292.66  4457.3  293.27  4941.7  292.54
  4964.2  291.51  4992.3  286.46  4998.1   279.5  4998.6     279  5020.3   279.5
  5031.7   281.2  5037.3  285.48  5054.2  287.92  5121.5  286.86    5166  292.21
  5255.2  292.82  5374.5  289.94    5671  290.37  5745.4  288.32  5756.5  285.69
  5762.4  282.19  5838.1  287.07  5919.7  290.26    5957  287.51  6001.6  292.87
  6060.2  293.39  6120.2  296.72  6322.3  298.88  6526.5  302.55  6781.9  308.77
#Mann= 10 ,-1 , 0
  3475.8     .04       0  4254.1     .05       0  4457.3     .04       0
  4998.1     .04       0  5020.3     .04       0    5671      .1       0
  5838.1     .04       0  6120.2     .05       0  6322.3     .04       0
  6526.5     .03       0
Bank Sta=4998.1,5020.3
XS Rating Curve= 0 ,0
Exp/Cntr=0.3,0.1

Type RM Length L Ch R = 1 ,56221   ,257,257,257
BEGIN DESCRIPTION:
Mapping XS 1ae25c5d
END DESCRIPTION:
XS GIS Cut Line= 3
      2445437.76     13553441.83      2443239.82     13554108.51
       2442099.6     13554618.74
#Sta/Elev= 30
    2189  303.14    2206  303.31  2484.5  297.09  3590.2  290.06  3594.9  290.02
  3797.5  290.07  3905.1  290.34  4004.9  290.63  4512.5  286.73  4525.2  286.57
  4741.7  286.99  4743.5  287.03  4851.9  287.76  4909.3  280.97  4961.7  279.15
  4971.7  278.81  4996.3  277.09  4996.8  276.59  5018.7  277.09  5030.7  281.44
  5123.5  283.36  5175.4  289.58  5198.6  286.97  5204.1  290.99  5227.3   293.4
  5391.6     299  5507.4  301.99  5648.7  305.24  5725.7  307.45    5735  307.58
#Mann= 19 ,-1 , 0
    2189     .05       0    2206     .04       0  3590.2    .013       0
  3594.9     .04       0  3797.5    .013       0  3905.1     .05       0
  4004.9    .013       0  4512.5     .04       0  4525.2    .013       0
  4741.7     .04       0  4743.5    .013       0  4961.7     .05       0
  4971.7    .013       0  4996.3     .03       0  5018.7    .013       0
  5391.6     .04       0  5507.4    .013       0  5648.7     .04       0
  5725.7    .013       0
Bank Sta=4996.3,5018.7
XS Rating Curve= 0 ,0
Exp/Cntr=0.3,0.1

Type RM Length L Ch R = 1 ,55964   ,319,319,319
BEGIN DESCRIPTION:
Mapping XS 99d78ea9
END DESCRIPTION:
XS GIS Cut Line= 3
      2445402.19     13553052.93      2442841.39     13554025.17
      2441851.79     13554441.85
#Sta/Elev= 30
  2080.1  297.78  2308.9  293.14  2717.1  288.68    2829  288.44  2935.3  288.19
  2975.2  288.16  3041.6   288.4  3128.6  288.23  3232.3  289.57  3670.9  289.65
  3756.4  291.39  4016.9  290.47  4129.9  289.89    4267  287.14  4382.1   288.8
  4855.5  288.15  4932.7  284.29  4961.2  282.52  4966.9  273.97  4967.4  273.47
  4989.3  273.97  4990.3  276.38  4999.8  282.89  5032.3  282.75  5151.7  293.03
  5196.5  294.42  5227.6     298  5344.3     300  5627.1  308.84    5893  310.47
#Mann= 14 ,-1 , 0
  2080.1     .04       0  2308.9     .05       0  2717.1     .04       0
    2829     .05       0  2935.3     .12       0  2975.2     .04       0
  3041.6     .05       0  3128.6     .04       0  4016.9     .05       0
  4129.9     .04       0  4855.5     .05       0  4932.7     .04       0
  4966.9     .04       0  4989.3     .04       0
Bank Sta=4966.9,4989.3
XS Rating Curve= 0 ,0
Exp/Cntr=0.3,0.1

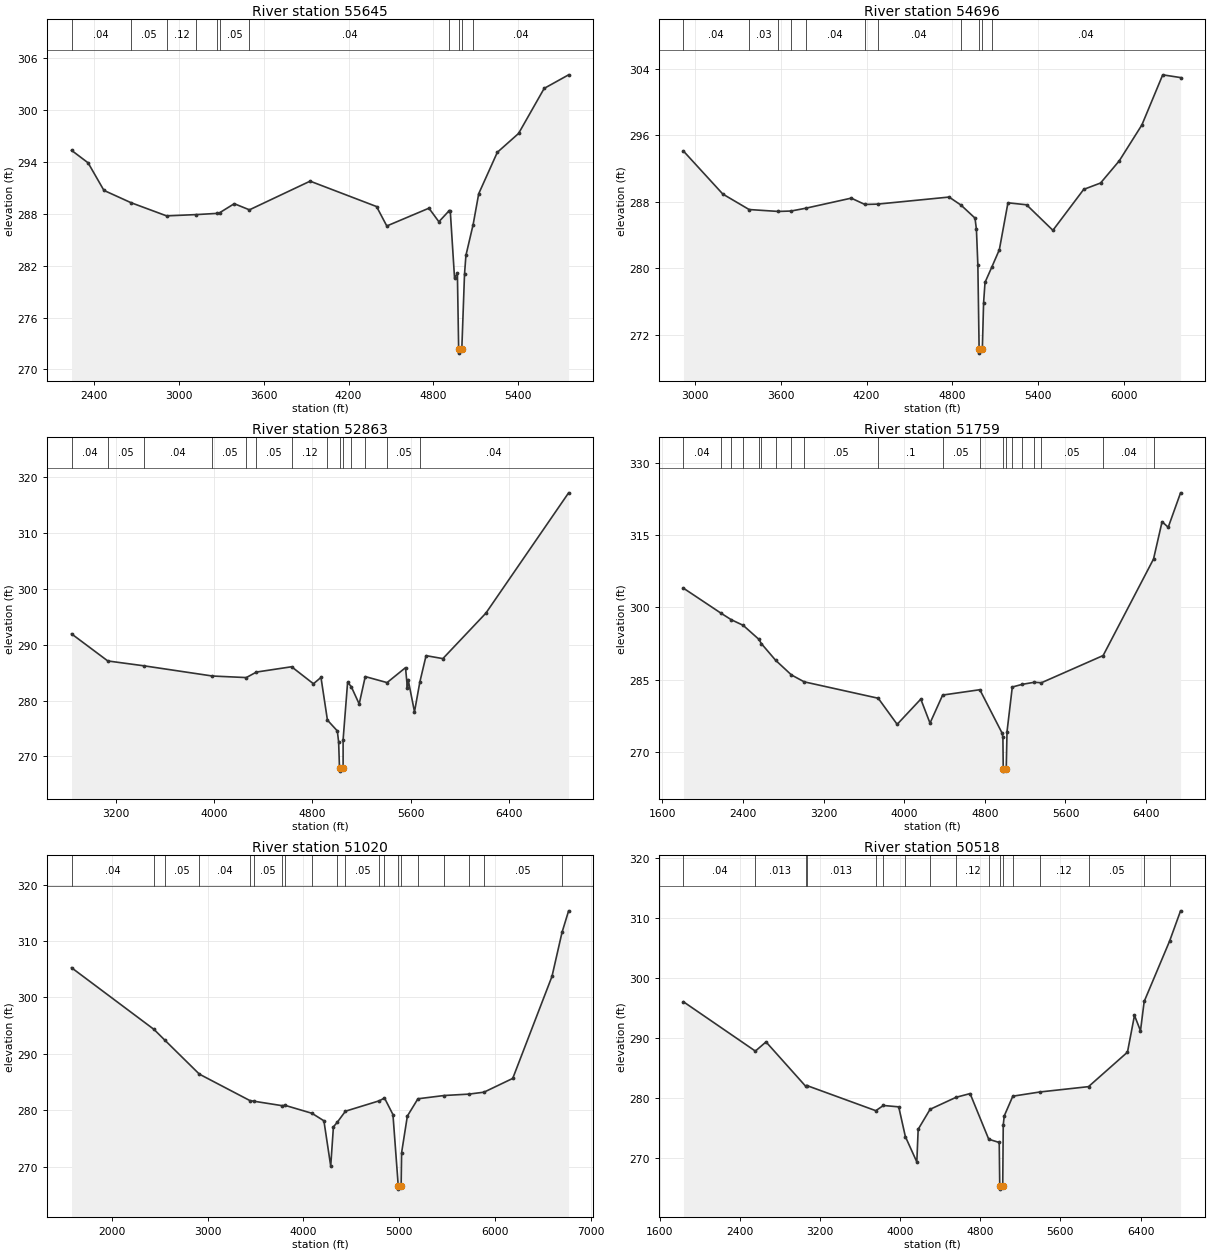
Type RM Length L Ch R = 1 ,55645   ,949,949,949
BEGIN DESCRIPTION:
Mapping XS 39f7fe0b
END DESCRIPTION:
XS GIS Cut Line= 3
      2445341.35     13552931.44      2442962.91     13553764.76
      2441973.32      13553877.6
#Sta/Elev= 30
  2240.5  295.36  2357.8  293.91  2469.7  290.72  2660.9   289.3  2912.8  287.77
  3123.4  287.92  3272.3  288.06  3287.9  288.13  3391.6  289.18  3498.9  288.47
  3928.2  291.79  4398.2  288.85  4470.6   286.6  4768.7  288.66  4839.1  287.09
  4912.2  288.38  4919.6  288.35  4949.8  280.58    4970  281.11  4978.9  272.38
  4979.4  271.88  5001.3  272.38  5020.3  280.99  5030.3  283.19  5081.4  286.77
  5120.9  290.34  5252.5  295.13  5402.7  297.31  5583.9  302.53  5756.7   304.1
#Mann= 11 ,-1 , 0
  2240.5     .04       0  2660.9     .05       0  2912.8     .12       0
  3123.4     .05       0  3272.3     .12       0  3287.9     .05       0
  3498.9     .04       0  4912.2     .12       0  4978.9     .05       0
  5001.3     .12       0  5081.4     .04       0
Bank Sta=4978.9,5001.3
XS Rating Curve= 0 ,0
Exp/Cntr=0.3,0.1

Type RM Length L Ch R = 1 ,54696   ,1833,1833,1833
BEGIN DESCRIPTION:
Mapping XS 69e1c5f9
END DESCRIPTION:
XS GIS Cut Line= 4
      2445254.58     13552749.13      2443388.26     13553122.39
      2442806.66     13553096.35      2441973.32     13553625.87
#Sta/Elev= 30
  2921.2  294.08  3196.1  288.91  3379.7  287.05  3583.3  286.82  3672.9  286.87
  3773.8   287.2  4093.4  288.42  4188.3  287.66  4276.8   287.7  4776.8  288.55
  4860.3  287.58  4957.9  286.02  4967.9  284.65  4977.9  280.36  4986.7  270.28
  4987.2  269.78  5009.2  270.28  5017.9  275.82  5027.9  278.29  5074.1  280.08
    5128  282.22  5188.1  287.86  5318.2  287.62  5502.1  284.55  5717.2  289.47
  5835.2  290.24  5965.5   292.9  6123.7  297.22  6269.4  303.25    6394  302.92
#Mann= 11 ,-1 , 0
  2921.2     .04       0  3379.7     .03       0  3583.3     .05       0
  3672.9     .03       0  3773.8     .04       0  4188.3     .05       0
  4276.8     .04       0  4860.3     .05       0  4986.7     .05       0
  5009.2     .05       0  5074.1     .04       0
Bank Sta=4986.7,5009.2
XS Rating Curve= 0 ,0
Exp/Cntr=0.3,0.1

Type RM Length L Ch R = 1 ,52863   ,1104,1104,1104
BEGIN DESCRIPTION:
YORKTOWN CREEK 70.0
END DESCRIPTION:
XS GIS Cut Line= 3
      2445167.79     13552613.72        2443175.       13551775.
      2441574.99       13550775.
#Sta/Elev= 30
  2837.9  291.97  3133.4  287.11  3427.6  286.24  3985.4  284.41  4261.5  284.13
  4344.2  285.12  4630.5  286.07  4808.4  283.02  4869.8  284.16  4922.4   276.5
  5002.9  274.57  5013.6  272.58  5020.7  267.86  5021.2  267.36    5050  267.86
  5050.1  273.01  5086.7   283.3  5116.5   282.5    5181   279.4  5230.4  284.31
  5408.1  283.23  5558.4  285.91  5573.7  282.29  5579.6  283.78  5631.5     278
  5675.6  283.39  5725.8  288.06  5862.6  287.53  6212.9  295.68  6886.8  317.25
#Mann= 14 ,-1 , 0
  2837.9     .04       0  3133.4     .05       0  3427.6     .04       0
  3985.4     .05       0  4261.5     .04       0  4344.2     .05       0
  4630.5     .12       0  4922.4      .1       0  5020.7     .05       0
    5050      .1       0  5116.5     .05       0  5230.4     .12       0
  5408.1     .05       0  5675.6     .04       0
Bank Sta=5020.7,5050
XS Rating Curve= 0 ,0
Exp/Cntr=0.3,0.1

Type RM Length L Ch R = 1 ,51759   ,739,739,739
BEGIN DESCRIPTION:
Mapping XS 62b7786e
END DESCRIPTION:
XS GIS Cut Line= 3
      2446306.71     13551384.56        2443140.     13550773.44
      2441453.93     13550509.77
#Sta/Elev= 30
  1810.4  303.98  2182.6  298.79  2283.9  297.44  2402.4  296.27  2559.2  293.35
  2582.7  292.48  2724.5  289.01  2881.6  285.96  3008.1  284.53  3742.5  281.12
  3930.5   275.7  4164.8  280.94  4256.4  275.95  4381.7  281.78  4750.7  282.89
  4969.3  273.97  4979.5  273.05    4983  266.48  4983.5  265.98  5012.6  266.48
  5020.3  274.16  5072.7  283.45  5171.8  284.01  5291.4  284.44  5361.6  284.34
    5974  289.99  6473.9  310.04  6558.8  317.79  6619.6  316.63  6742.1  323.79
#Mann= 20 ,-1 , 0
  1810.4     .04       0  2182.6    .013       0  2283.9     .04       0
  2402.4     .12       0  2559.2     .04       0  2582.7     .05       0
  2724.5     .12       0  2881.6     .04       0  3008.1     .05       0
  3742.5      .1       0  4381.7     .05       0  4750.7      .1       0
    4983     .05       0  5012.6      .1       0  5072.7     .12       0
  5171.8     .05       0  5291.4     .12       0  5361.6     .05       0
    5974     .04       0  6473.9    .013       0
Bank Sta=4983,5012.6
XS Rating Curve= 0 ,0
Exp/Cntr=0.3,0.1

Type RM Length L Ch R = 1 ,51020   ,502,502,502
BEGIN DESCRIPTION:
Mapping XS 5cc09f95
END DESCRIPTION:
XS GIS Cut Line= 3
      2446820.58     13550731.77      2443487.22     13550148.44
      2441681.66     13550169.27
#Sta/Elev= 30
  1579.9  305.28  2441.3  294.34  2552.4  292.47  2914.4  286.42  3443.7  281.72
    3480  281.63  3778.4  280.83  3809.1  280.89  4089.9  279.48  4214.9  278.15
    4286  270.12    4314  277.07  4356.1  277.93  4439.8  279.85  4794.3   281.7
  4847.4  282.19  4935.7  279.25  4991.3  266.54  4991.8  266.04    5021  266.54
  5026.1   272.5  5086.1  278.99  5196.4  282.05  5469.8  282.63  5729.6  282.88
  5885.9  283.22  6186.2  285.66  6596.2  303.75  6700.6  311.53  6769.6  315.36
#Mann= 20 ,-1 , 0
  1579.9     .04       0  2441.3    .013       0  2552.4     .05       0
  2914.4     .04       0  3443.7     .04       0    3480     .05       0
  3778.4     .12       0  3809.1     .05       0  4089.9      .1       0
  4356.1     .12       0  4439.8     .05       0  4794.3     .12       0
  4847.4      .1       0  4991.3     .05       0    5021      .1       0
  5196.4     .12       0  5469.8     .05       0  5729.6     .12       0
  5885.9     .05       0  6700.6    .013       0
Bank Sta=4991.3,5021
XS Rating Curve= 0 ,0
Exp/Cntr=0.3,0.1

Type RM Length L Ch R = 1 ,50518   ,1032,1032,1032
BEGIN DESCRIPTION:
Mapping XS df1c8a12
END DESCRIPTION:
XS GIS Cut Line= 3
      2446716.42     13549947.05      2443591.39     13549683.16
      2441764.98     13549717.88
#Sta/Elev= 30
  1836.9  295.98  2554.5  287.76  2661.2  289.29  3056.1  281.91  3067.8  282.02
    3757  277.82  3832.9  278.69  3985.9  278.46  4052.3   273.5  4166.6  269.28
  4180.2  274.72    4299  278.05  4559.5  280.06  4698.5  280.67  4884.7  273.06
  4989.4  272.52  4994.6  265.24  4995.1  264.74  5024.3  265.24  5029.5  275.43
  5039.5  276.95    5125  280.24  5394.9  280.94  5880.7  281.83  6269.7  287.58
  6339.7  293.71  6399.7  291.14  6436.5  296.03  6690.9  306.13  6799.8  311.15
#Mann= 17 ,-1 , 0
  1836.9     .04       0  2554.5    .013       0  3056.1     .05       0
  3067.8    .013       0    3757     .05       0  3832.9     .12       0
  4052.3      .1       0    4299     .05       0  4559.5     .12       0
  4884.7      .1       0  4994.6     .05       0  5024.3      .1       0
    5125     .05       0  5394.9     .12       0  5880.7     .05       0
  6436.5    .013       0  6690.9     .05       0
Bank Sta=4994.6,5024.3
XS Rating Curve= 0 ,0
Exp/Cntr=0.3,0.1

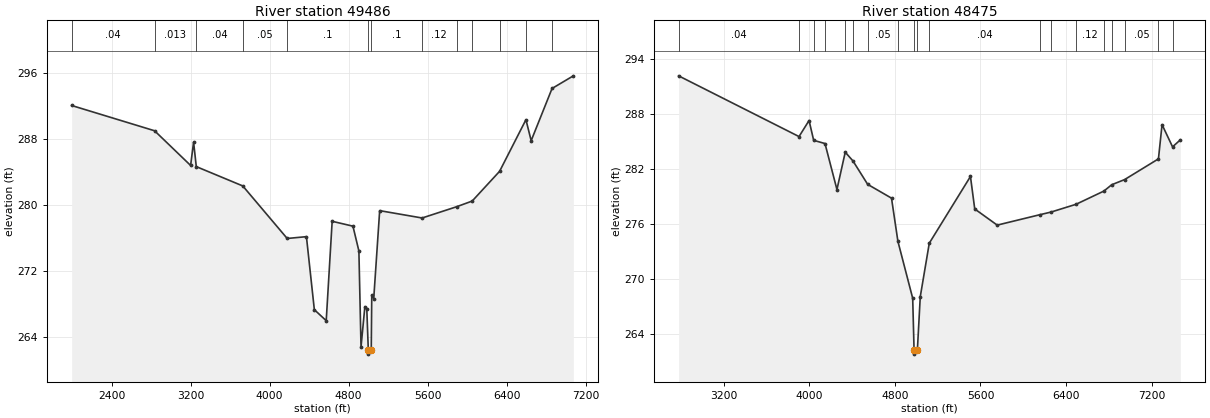
Type RM Length L Ch R = 1 ,49486   ,1011,1011,1011
BEGIN DESCRIPTION:
Mapping XS c94b14d5
END DESCRIPTION:
XS GIS Cut Line= 3
      2447237.23      13549315.1      2444278.89      13549127.6
      2442168.89     13548981.85
#Sta/Elev= 30
  1995.5  292.02    2835  288.96  3200.1  284.76  3230.2  287.58  3257.5  284.62
  3728.1  282.28  4177.8  275.92  4372.5  276.14  4452.6   267.3  4572.9  265.97
    4633     278  4843.4  277.41  4903.6  274.41  4925.2   262.8  4964.2  267.67
  4983.7  267.37  4998.9  262.42  4999.4  261.92  5028.7  262.42  5033.8  269.06
  5053.9  268.65    5114  279.29  5543.6   278.4  5892.2  279.76  6050.5  280.45
    6328  284.05  6594.7   290.3  6647.7  287.76  6859.2  294.08  7074.8  295.61
#Mann= 13 ,-1 , 0
  1995.5     .04       0    2835    .013       0  3257.5     .04       0
  3728.1     .05       0  4177.8      .1       0  4998.9     .05       0
  5028.7      .1       0  5543.6     .12       0  5892.2     .05       0
  6050.5     .12       0    6328     .05       0  6594.7    .013       0
  6859.2     .05       0
Bank Sta=4998.9,5028.7
XS Rating Curve= 0 ,0
Exp/Cntr=0.3,0.1

Type RM Length L Ch R = 1 ,48475   ,997,997,997
BEGIN DESCRIPTION:
Mapping XS df69b110
END DESCRIPTION:
XS GIS Cut Line= 4
      2447251.14     13549169.27      2445313.61     13549023.44
      2444910.83     13548606.77      2442744.21     13548530.38
#Sta/Elev= 30
  2778.2  292.16  3904.1  285.54  3997.8  287.29    4041  285.13  4146.8  284.78
  4258.5  279.77  4336.1  283.84  4408.6  282.88    4546  280.33  4768.6  278.83
  4828.5  274.12  4966.7  267.92  4979.4  262.33  4979.9  261.83  5010.7  262.33
  5037.5  268.09  5121.8  273.92  5506.7  281.19  5546.7  277.65  5756.8  275.89
  6161.1  277.04  6259.4  277.31  6493.9  278.16    6754   279.6  6827.2  280.29
  6947.5  280.85  7264.1  283.11  7297.8  286.84    7396  284.42  7468.7  285.18
#Mann= 19 ,-1 , 0
  2778.2     .04       0  3904.1    .013       0    4041     .04       0
  4146.8     .12       0  4336.1     .04       0  4408.6     .12       0
    4546     .05       0  4828.5      .1       0  4979.4     .05       0
  5010.7      .1       0  5121.8     .04       0  6161.1    .013       0
  6259.4     .05       0  6493.9     .12       0    6754     .05       0
  6827.2     .12       0  6947.5     .05       0  7264.1    .013       0
    7396     .05       0
Bank Sta=4979.4,5010.7
XS Rating Curve= 0 ,0
Exp/Cntr=0.3,0.1