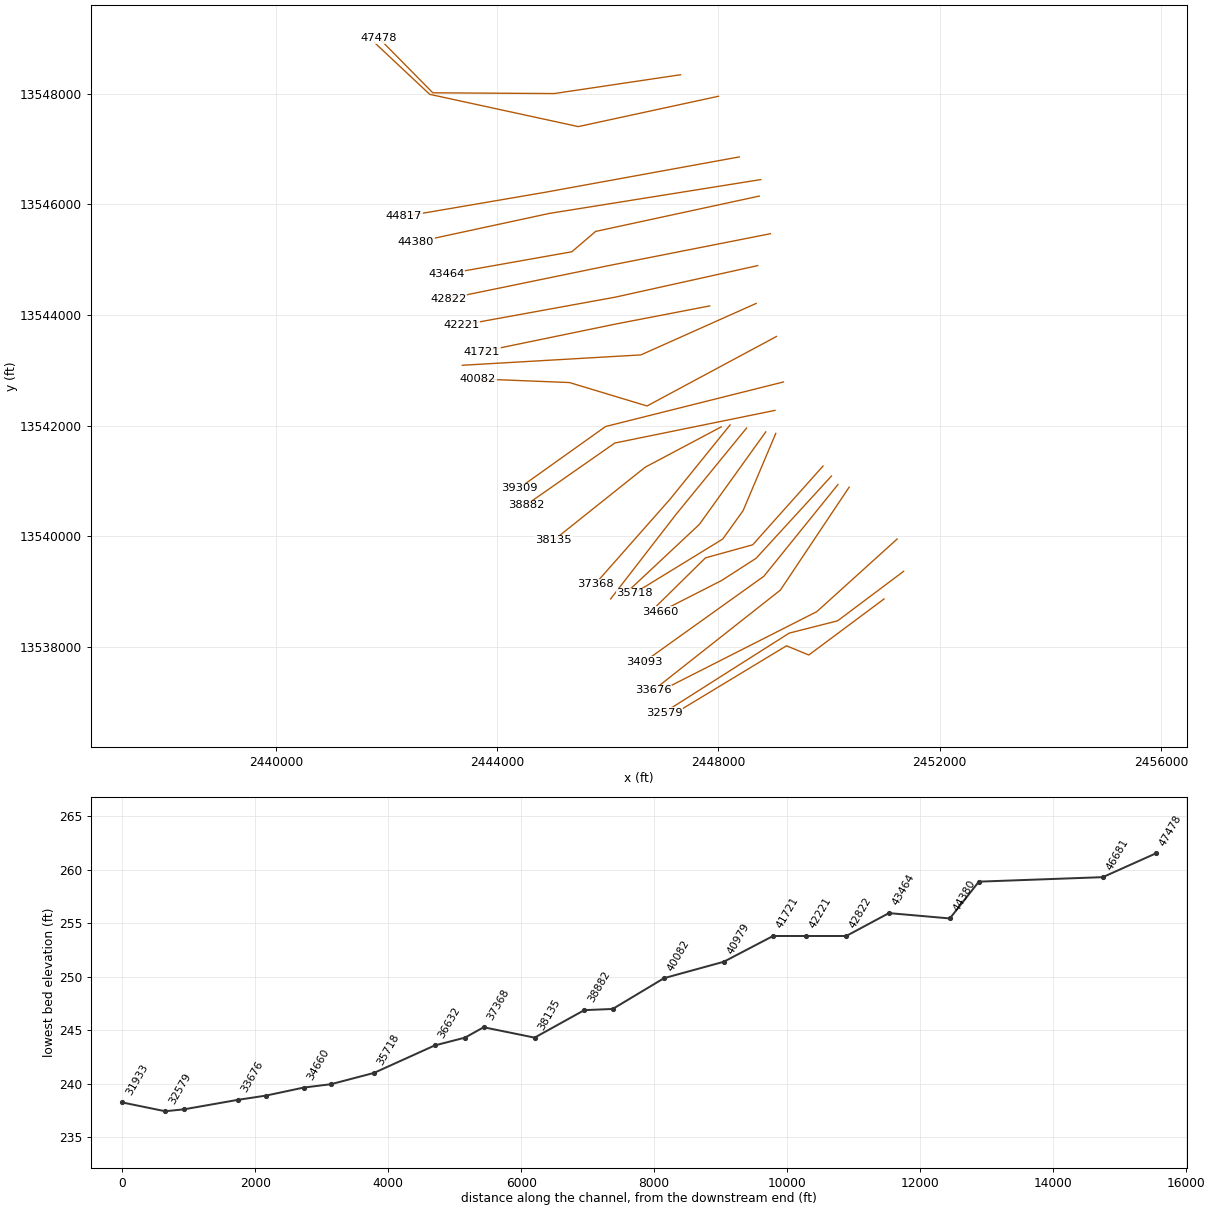
HEC-RAS study YORKTOWN CREEK.prj: YORKTOWN CREEK Base Level Engineering

--- YORKTOWN CREEK.g01 (geometry) --- (continued)

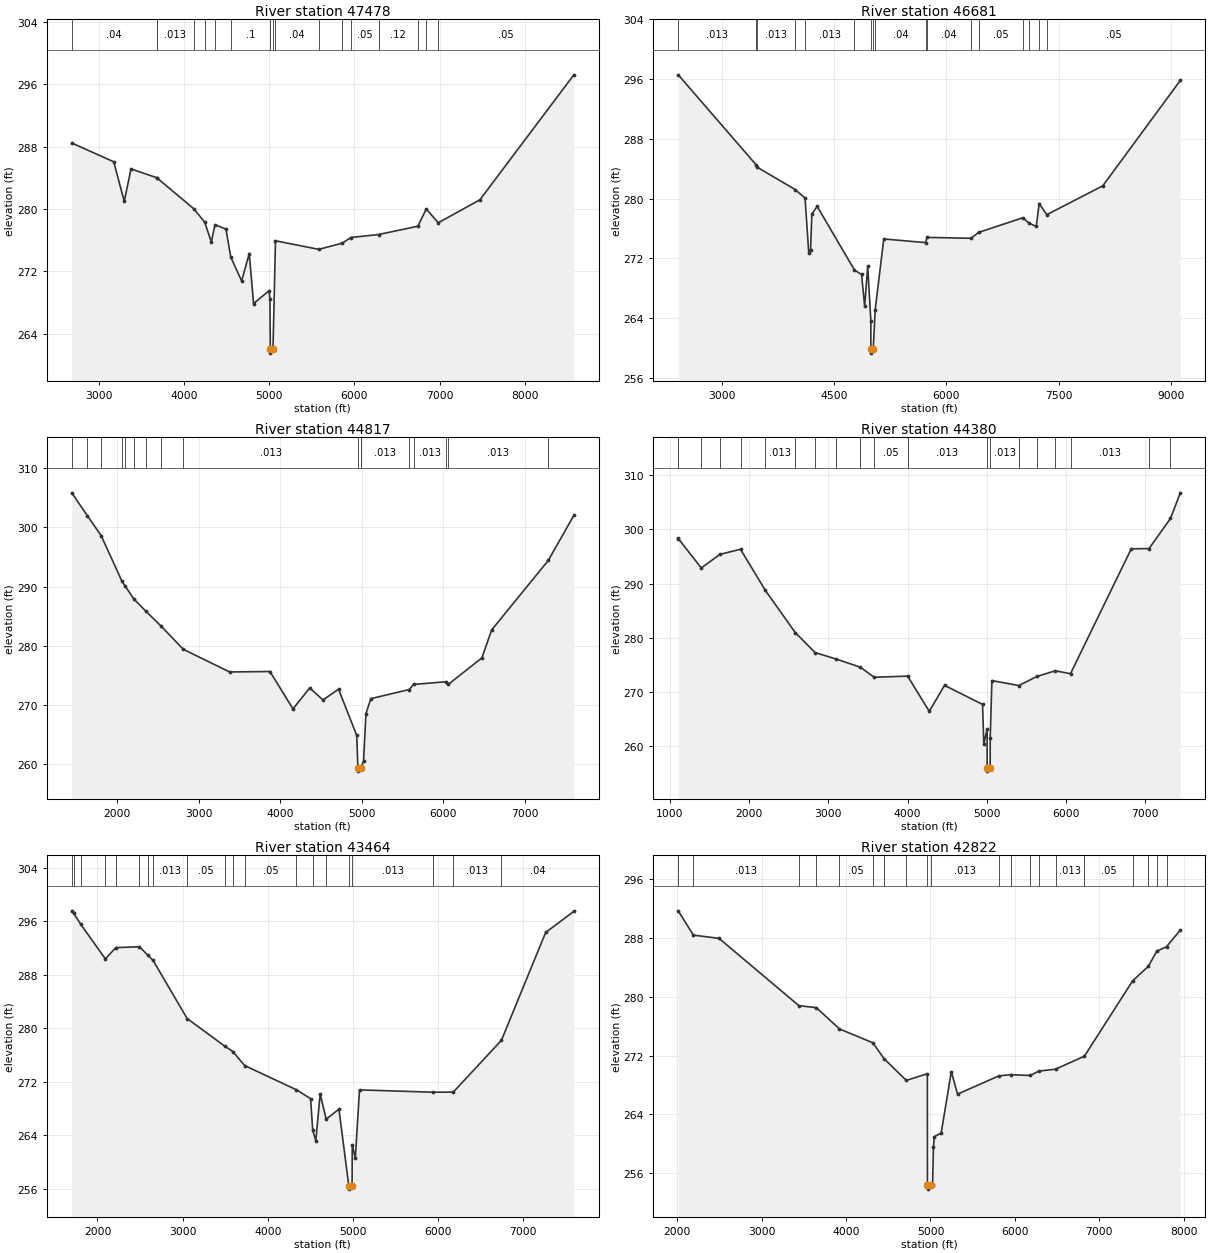
Type RM Length L Ch R = 1 ,47478   ,797,797,797
BEGIN DESCRIPTION:
Mapping XS 47ba3e9c
END DESCRIPTION:
XS GIS Cut Line= 4
      2447313.58     13548342.88      2445028.89      13548002.6
      2442834.44     13548016.49      2441863.53     13549001.27
#Sta/Elev= 30
  2685.8  288.49  3177.6  286.08  3301.1     281  3380.5  285.16  3681.9  284.04
  3686.5     284  4117.7  280.04  4243.5  278.34  4322.2   275.8  4365.5     278
  4494.1  277.44  4550.1  273.84  4677.5  270.79  4767.1   274.3  4817.6  267.88
  5000.1  269.54  5009.6  268.41  5013.9  262.02  5014.4  261.52  5045.2  262.02
  5074.5  275.94  5582.1  274.84    5859  275.64  5957.3  276.36  6282.5  276.74
  6744.2  277.81  6842.6  280.02  6983.3  278.25  7471.5   281.2  8573.1  297.24
#Mann= 17 ,-1 , 0
  2685.8     .04       0  3681.9     .12       0  3686.5    .013       0
  4117.7     .12       0  4243.5    .013       0  4365.5     .12       0
  4550.1      .1       0  5013.9     .05       0  5045.2      .1       0
  5074.5     .04       0  5582.1     .12       0    5859    .013       0
  5957.3     .05       0  6282.5     .12       0  6744.2     .05       0
  6842.6    .013       0  6983.3     .05       0
Bank Sta=5013.9,5045.2
XS Rating Curve= 0 ,0
Exp/Cntr=0.3,0.1

Type RM Length L Ch R = 1 ,46681   ,1864,1864,1864
BEGIN DESCRIPTION:
Mapping XS a30c6690
END DESCRIPTION:
XS GIS Cut Line= 4
      2448001.07     13547953.98      2445466.39     13547405.38
      2442778.89     13547988.71      2441779.46     13548925.68
#Sta/Elev= 30
  2415.1  296.57  3460.7  284.47  3474.4  284.18  3978.1  281.21  4110.9  280.06
  4160.7  272.66  4184.6  273.17  4201.6  277.93  4272.8  278.95  4771.8  270.43
  4866.6  269.83  4907.6  265.59  4948.5  270.93  4990.6  263.63  4990.9   259.8
  4991.4   259.3  5022.3   259.8  5048.8  265.14  5163.4  274.59    5724   274.1
  5740.5   274.8  6330.1  274.68  6431.4  275.47  7021.3  277.42  7104.3  276.73
  7201.9  276.26  7241.4  279.33  7342.7  277.84  8091.4   281.7  9128.5  295.82
#Mann= 17 ,-1 , 0
  2415.1    .013       0  3460.7     .05       0  3474.4    .013       0
  3978.1     .05       0  4110.9    .013       0  4771.8      .1       0
  4990.9     .05       0  5022.3      .1       0  5048.8     .04       0
    5724    .013       0  5740.5     .04       0  6330.1    .013       0
  6431.4     .05       0  7021.3     .12       0  7104.3     .05       0
  7241.4    .013       0  7342.7     .05       0
Bank Sta=4990.9,5022.3
XS Rating Curve= 0 ,0
Exp/Cntr=0.3,0.1

Type RM Length L Ch R = 1 ,44817   ,437,437,437
BEGIN DESCRIPTION:
Mapping XS 56090cd7
END DESCRIPTION:
XS GIS Cut Line= 3
      2448376.06     13546856.76      2444869.16     13546217.88
      2442313.56     13545780.37
#Sta/Elev= 30
  1441.2  305.81  1631.1  301.98  1801.5  298.59  2057.6  290.87  2090.9  290.18
  2204.6  287.87  2353.9   285.8  2530.1  283.43  2809.1  279.42  3377.3   275.6
  3871.6  275.68  4154.1  269.37  4359.5  272.91  4522.1  270.88  4712.6   272.7
    4936   264.9  4950.2  259.38  4951.2  258.88  4988.6  259.38  5020.2  260.65
    5049  268.58  5109.1   271.1  5579.7  272.64  5632.7   273.5    6036  273.96
    6060  273.52  6470.4  277.97  6590.5  282.69  7285.7  294.42  7598.6  302.01
#Mann= 16 ,-1 , 0
  1441.2     .03       0  1631.1     .05       0  1801.5    .013       0
  2057.6     .05       0  2090.9    .013       0  2204.6     .05       0
  2353.9    .013       0  2530.1     .05       0  2809.1    .013       0
  4950.2     .03       0  4988.6    .013       0  5579.7     .05       0
  5632.7    .013       0    6036     .05       0    6060    .013       0
  7285.7     .03       0
Bank Sta=4950.2,4988.6
XS Rating Curve= 0 ,0
Exp/Cntr=0.3,0.1

Type RM Length L Ch R = 1 ,44380   ,916,916,916
BEGIN DESCRIPTION:
Mapping XS 2021864a
END DESCRIPTION:
XS GIS Cut Line= 3
      2448764.96     13546447.04      2444945.55     13545835.94
      2442529.42     13545315.22
#Sta/Elev= 30
  1105.1  298.32  1107.1  298.27  1396.1  292.88  1632.1  295.39  1891.3  296.33
  2205.1  288.75  2583.1  280.97  2833.2  277.29    3101  276.09  3404.7  274.59
  3579.3  272.74  4001.7  272.95  4274.9  266.46  4467.3  271.25  4947.8  267.74
  4963.5  260.42  5005.4  263.24  5005.6  255.94  5006.6  255.44    5044  255.94
  5044.4  261.62  5065.7  272.13  5406.8  271.21  5632.5  272.88  5865.4  273.93
  6058.2   273.4  6825.2  296.41  7050.4  296.46  7320.6  302.01  7444.7  306.73
#Mann= 20 ,-1 , 0
  1105.1     .05       0  1107.1     .12       0  1396.1     .03       0
  1632.1    .013       0  1891.3    .013       0  2205.1    .013       0
  2583.1     .05       0  2833.2    .013       0    3101     .05       0
  3404.7    .013       0  3579.3     .05       0  4001.7    .013       0
  5005.6     .03       0    5044    .013       0  5406.8     .05       0
  5632.5    .013       0  5865.4     .05       0  6058.2    .013       0
  7050.4     .04       0  7320.6     .04       0
Bank Sta=5005.6,5044
XS Rating Curve= 0 ,0
Exp/Cntr=0.3,0.1

Type RM Length L Ch R = 1 ,43464   ,642,642,642
BEGIN DESCRIPTION:
Mapping XS b4374c61
END DESCRIPTION:
XS GIS Cut Line= 4
      2448737.25     13546148.44      2445778.89     13545509.55
      2445348.33     13545141.49      2443078.75     13544738.94
#Sta/Elev= 30
  1697.9  297.55  1721.7  297.18  1800.7  295.58  2092.6  290.36  2215.2  292.05
  2492.6  292.18  2592.5   290.9    2652  290.16  3052.7  281.45  3492.5  277.34
  3592.4  276.49  3727.9  274.42  4337.5  270.79  4503.4  269.46  4528.6  264.72
  4564.8  263.19  4615.9  270.15  4686.4   266.4  4836.5  267.89  4952.2  256.44
  4953.2  255.94  4990.7  256.44  4992.7  262.58  5028.6  260.57    5078  270.78
  5946.2  270.43  6180.1  270.45  6745.2  278.19  7264.6  294.31  7595.9  297.47
#Mann= 20 ,-1 , 0
  1697.9     .03       0  1721.7     .12       0  1800.7     .03       0
  2092.6    .013       0  2215.2     .03       0  2492.6    .013       0
  2592.5     .05       0    2652    .013       0  3052.7     .05       0
  3492.5    .075       0  3592.4    .075       0  3727.9     .05       0
  4337.5    .013       0  4528.6     .05       0  4686.4    .013       0
  4952.2     .03       0  4990.7    .013       0  5946.2     .05       0
  6180.1    .013       0  6745.2     .04       0
Bank Sta=4952.2,4990.7
XS Rating Curve= 0 ,0
Exp/Cntr=0.3,0.1

Type RM Length L Ch R = 1 ,42822   ,601,601,601
BEGIN DESCRIPTION:
Mapping XS e4622287
END DESCRIPTION:
XS GIS Cut Line= 3
      2448938.65     13545467.89        2446015.     13544891.49
      2443112.23     13544294.27
#Sta/Elev= 30
  2014.3  291.71  2193.5   288.4  2497.1  287.96  3442.8  278.79  3649.6  278.52
  3922.8  275.62  4319.2  273.73  4450.5  271.57  4714.4  268.61  4963.6  269.52
  4964.7   254.3  4965.7   253.8  5003.4   254.3  5024.9   254.3  5035.1  259.48
  5045.3  260.95  5126.9  261.44  5247.1   269.8  5320.9  266.74  5810.6  269.23
  5951.9  269.39    6182  269.28  6281.8  269.88  6481.4  270.14  6823.2  271.92
  7393.1  282.17  7579.3  284.15  7679.1  286.21  7794.3  286.82  7957.8  289.09
#Mann= 20 ,-1 , 0
  2014.3    .013       0  2193.5    .013       0  3442.8     .05       0
  3649.6    .013       0  3922.8     .05       0  4319.2    .013       0
  4450.5     .05       0  4714.4    .013       0  4964.7     .03       0
  5003.4    .013       0  5810.6     .05       0  5951.9    .013       0
    6182     .05       0  6281.8    .075       0  6481.4    .013       0
  6823.2     .05       0  7393.1    .013       0  7579.3     .03       0
  7679.1    .013       0  7794.3     .04       0
Bank Sta=4964.7,5003.4
XS Rating Curve= 0 ,0
Exp/Cntr=0.3,0.1

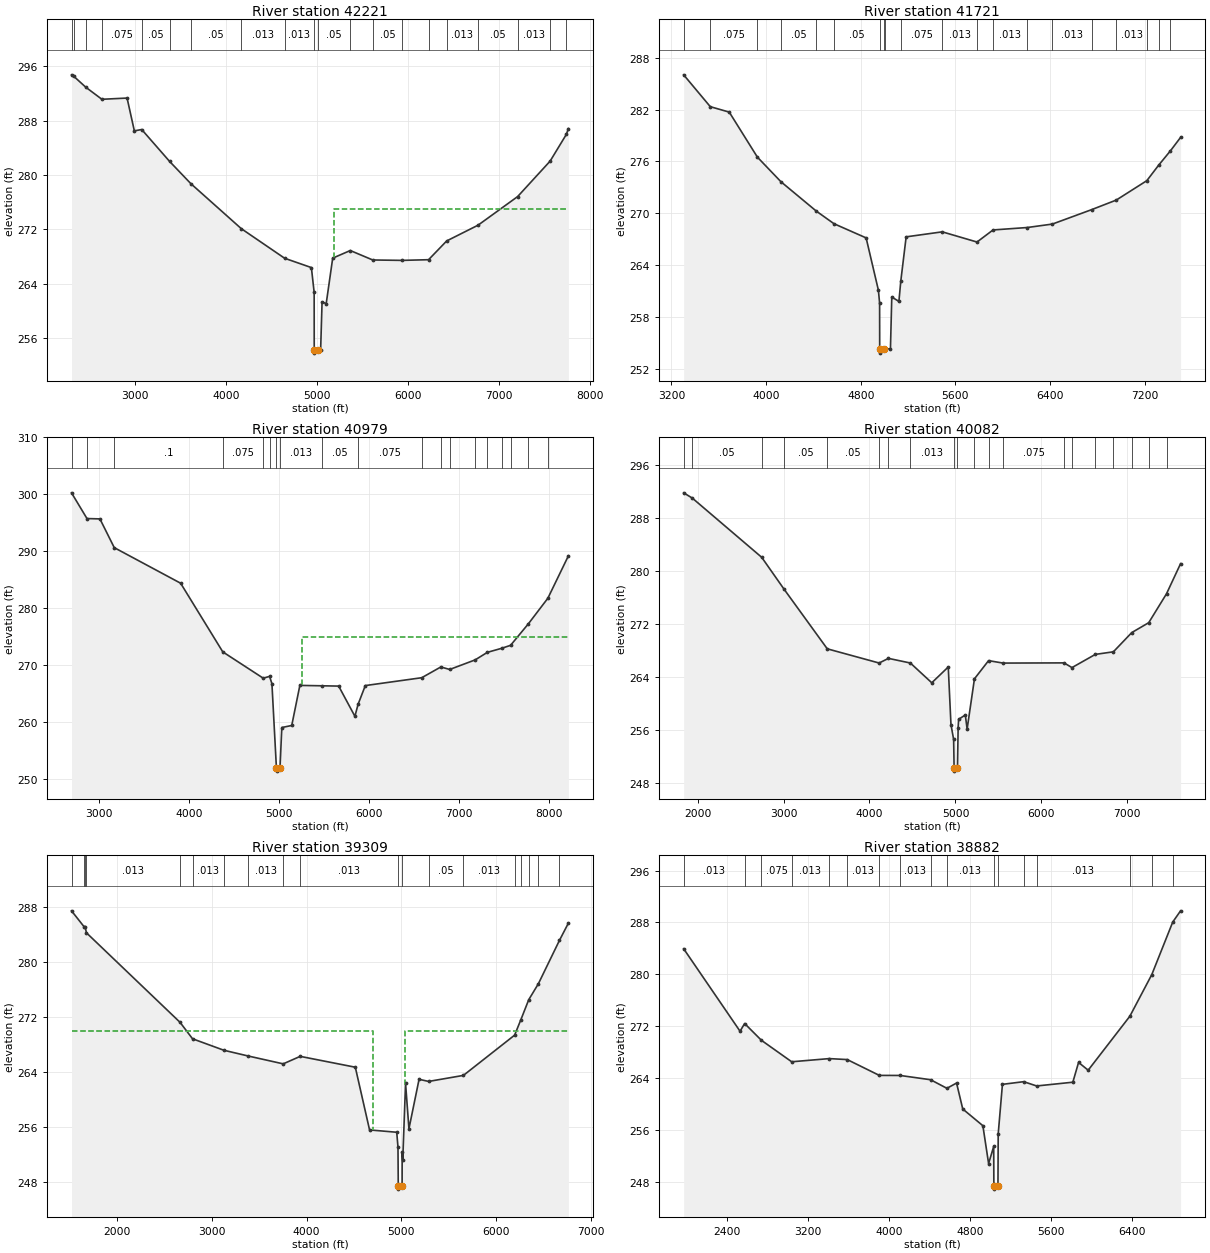
Type RM Length L Ch R = 1 ,42221   ,500,500,500
BEGIN DESCRIPTION:
Mapping XS a42cfec9
END DESCRIPTION:
XS GIS Cut Line= 3
      2448709.41     13544891.48        2446140.     13544322.05
      2443355.32     13543815.11
#Sta/Elev= 30
  2301.6  294.76  2325.8  294.55    2459  292.93  2635.6  291.16  2912.4  291.34
  2992.4  286.51  3073.4  286.71  3378.9  282.03  3612.8  278.75  4167.9  272.12
  4644.8  267.76  4938.4  266.39  4968.9  262.73  4969.7   254.3  4970.7   253.8
  5008.9   254.3  5040.1   254.3  5055.9  261.36  5101.1  261.07  5172.7  267.78
    5366   268.9  5612.8  267.51  5935.3  267.45  6226.6  267.55  6425.4  270.31
  6770.4  272.63  7205.5  276.84  7562.6  282.06  7740.4  285.98  7763.8  286.85
#Mann= 20 ,-1 , 0
  2301.6    .013       0  2325.8     .05       0    2459    .013       0
  2635.6    .075       0  3073.4     .05       0  3378.9    .075       0
  3612.8     .05       0  4167.9    .013       0  4644.8    .013       0
  4969.7     .03       0  5008.9     .05       0    5366    .013       0
  5612.8     .05       0  5935.3    .013       0  6226.6    .075       0
  6425.4    .013       0  6770.4     .05       0  7205.5    .013       0
  7562.6     .05       0  7740.4    .013       0
#XS Ineff= 2 , 0
       0                    5185       0     275
Permanent Ineff=
       F       F
Bank Sta=4969.7,5008.9
XS Rating Curve= 0 ,0
Exp/Cntr=0.3,0.1

Type RM Length L Ch R = 1 ,41721   ,742,742,742
BEGIN DESCRIPTION:
Mapping XS 2e3867c4
END DESCRIPTION:
XS GIS Cut Line= 3
       2447841.4     13544162.33      2446146.94     13543835.94
      2443723.28     13543335.93
#Sta/Elev= 30
  3303.1  286.04  3528.2  282.35  3688.5  281.72  3926.6   276.5  4125.8  273.65
  4424.6  270.25  4573.9  268.79  4845.4  267.15  4949.2  261.09  4959.4   259.6
  4960.2   254.3  4961.2   253.8  4999.4   254.3  5007.5   254.3  5051.1   254.3
  5062.3   260.3  5122.6  259.79  5138.6  262.16  5183.8  267.27  5488.9  267.85
  5782.7  266.67  5918.3  268.07  6206.3  268.35  6419.7  268.75  6751.2  270.42
  6959.8  271.53  7218.2  273.78    7318  275.57  7417.9  277.24  7503.4  278.79
#Mann= 20 ,-1 , 0
  3303.1    .013       0  3528.2    .075       0  3926.6      .1       0
  4125.8     .05       0  4424.6    .075       0  4573.9     .05       0
  4960.2     .05       0  4999.4     .05       0  5007.5    .013       0
  5138.6    .075       0  5488.9    .013       0  5782.7     .05       0
  5918.3    .013       0  6206.3    .075       0  6419.7    .013       0
  6751.2     .05       0  6959.8    .013       0  7218.2    .075       0
    7318      .1       0  7417.9    .075       0
Bank Sta=4960.2,4999.4
XS Rating Curve= 0 ,0
Exp/Cntr=0.3,0.1

Type RM Length L Ch R = 1 ,40979   ,897,897,897
BEGIN DESCRIPTION:
Mapping XS 75720d3c
END DESCRIPTION:
XS GIS Cut Line= 3
       2448680.8     13544207.35      2446597.45     13543276.79
      2443369.12     13543089.34
#Sta/Elev= 30
  2696.3  300.28    2868  295.76  3011.7   295.7  3170.8  290.65  3907.4   284.4
  4375.3  272.34  4823.9  267.72  4894.8  268.03  4920.8  266.75  4970.9  251.89
  4971.9  251.39  5010.2  251.89  5030.6  259.05  5140.8  259.41  5230.9  266.45
  5476.8  266.38  5661.6  266.33  5841.9  261.02  5877.2  263.13  5957.4  266.42
  6583.8   267.8  6795.6  269.69    6894  269.25  7176.3  270.93  7312.5  272.26
  7471.3  272.97  7569.6  273.49  7766.3  277.25  7983.5  281.76  8211.8  289.22
#Mann= 19 ,-1 , 0
  2696.3     .05       0    2868    .075       0  3170.8      .1       0
  4375.3    .075       0  4823.9     .05       0  4894.8    .013       0
  4970.9     .03       0  5010.2    .013       0  5476.8     .05       0
  5877.2    .075       0  6583.8      .1       0  6795.6    .075       0
    6894      .1       0  7176.3     .05       0  7312.5    .013       0
  7471.3    .075       0  7569.6      .1       0  7766.3    .075       0
  7983.5     .05       0
#XS Ineff= 2 , 0
       0                    5260       0     275
Permanent Ineff=
       F       F
Bank Sta=4970.9,5010.2
XS Rating Curve= 0 ,0
Exp/Cntr=0.3,0.1

Type RM Length L Ch R = 1 ,40082   ,773,773,773
BEGIN DESCRIPTION:
Mapping XS 12868af5
END DESCRIPTION:
XS GIS Cut Line= 4
      2449048.84     13543610.12      2446708.56     13542353.18
      2445305.78     13542776.79      2443648.51     13542842.82
#Sta/Elev= 30
  1838.4  291.82  1939.6  291.02  2746.1   282.1  3006.4  277.29  3508.9   268.3
  4112.1  266.16  4220.7  266.86  4475.6  266.16  4724.6  263.18  4916.4  265.56
  4947.8  256.89  4979.1  254.63  4984.3  250.36  4985.3  249.86  5023.6  250.36
  5031.3   256.4    5037  257.67  5114.9  258.33  5135.8   256.2  5221.1  263.78
  5385.4  266.52  5553.4  266.15    6263  266.18  6355.7  265.47  6627.3  267.46
  6837.3  267.85  7051.2  270.75  7248.3  272.24  7455.3   276.6  7618.8  281.14
#Mann= 20 ,-1 , 0
  1838.4    .013       0  1939.6     .05       0  2746.1    .013       0
  3006.4     .05       0  3508.9     .05       0  4112.1    .013       0
  4220.7     .05       0  4475.6    .013       0  4984.3     .03       0
  5023.6    .013       0  5221.1     .05       0  5385.4    .013       0
  5553.4    .075       0    6263     .05       0  6355.7    .013       0
  6627.3    .075       0  6837.3    .013       0  7051.2     .05       0
  7248.3    .013       0  7455.3     .05       0
Bank Sta=4984.3,5023.6
XS Rating Curve= 0 ,0
Exp/Cntr=0.3,0.1

Type RM Length L Ch R = 1 ,39309   ,427,427,427
BEGIN DESCRIPTION:
Mapping XS 0753fa16
END DESCRIPTION:
XS GIS Cut Line= 3
      2449174.72     13542787.33      2445959.44     13541981.77
      2444390.02     13540863.73
#Sta/Elev= 30
  1520.2   287.5  1651.8   285.2  1663.1  285.21  1677.6   284.3  2664.7  271.27
  2796.8  268.87  3127.2   267.2  3384.5  266.36  3753.1  265.22  3932.4  266.31
  4513.8  264.73  4664.2   255.6  4950.8  255.26  4963.9   253.1    4967  247.48
    4968  246.98  5007.5  247.48  5008.2  252.34  5014.3  251.26  5043.8  262.38
  5079.5  255.77  5186.4  262.97  5287.2  262.66  5654.2  263.54  6194.3   269.4
  6259.7  271.63  6343.2  274.56  6444.8  276.88  6667.6  283.21  6761.8  285.72
#Mann= 19 ,-1 , 0
  1520.2     .05       0  1651.8    .013       0  1663.1     .05       0
  1677.6    .013       0  2664.7     .05       0  2796.8    .013       0
  3127.2     .05       0  3384.5    .013       0  3753.1     .05       0
  3932.4    .013       0    4967     .03       0  5007.5    .013       0
  5287.2     .05       0  5654.2    .013       0  6194.3     .04       0
  6259.7    .013       0  6343.2     .04       0  6444.8    .013       0
  6667.6     .04       0
#XS Ineff= 2 , 0
       0    4700     270    5043       0     270
Permanent Ineff=
       F       F
Bank Sta=4967,5007.5
XS Rating Curve= 0 ,0
Exp/Cntr=0.3,0.1

Type RM Length L Ch R = 1 ,38882   ,747,747,747
BEGIN DESCRIPTION:
Mapping XS 2652acce
END DESCRIPTION:
XS GIS Cut Line= 3
      2449021.94     13542273.44      2446126.11     13541683.16
      2444516.31     13540559.07
#Sta/Elev= 30
  1966.7  283.94  2524.9  271.22  2570.3  272.41  2736.6  269.82    3036  266.51
  3407.4     267  3585.8  266.85  3903.7  264.41  4109.5   264.4  4411.1  263.74
  4572.6  262.42  4668.1  263.23  4729.3  259.23  4928.6  256.65  4985.3  250.81
  5035.8  253.46  5037.3  247.37  5038.3  246.87  5077.9  247.37  5080.3  255.38
  5122.2  263.03  5332.6  263.44  5460.9  262.78  5819.1  263.36  5875.8  266.41
  5970.9  265.21  6383.3  273.53  6600.8  279.96    6808  288.06  6885.5  289.79
#Mann= 17 ,-1 , 0
  1966.7    .013       0  2570.3     .05       0  2736.6    .075       0
    3036    .013       0  3407.4     .05       0  3585.8    .013       0
  3903.7     .05       0  4109.5    .013       0  4411.1     .05       0
  4572.6    .013       0  5037.3     .03       0  5077.9    .013       0
  5332.6    .075       0  5460.9    .013       0  6383.3     .05       0
  6600.8    .013       0    6808    .035       0
Bank Sta=5037.3,5077.9
XS Rating Curve= 0 ,0
Exp/Cntr=0.3,0.1

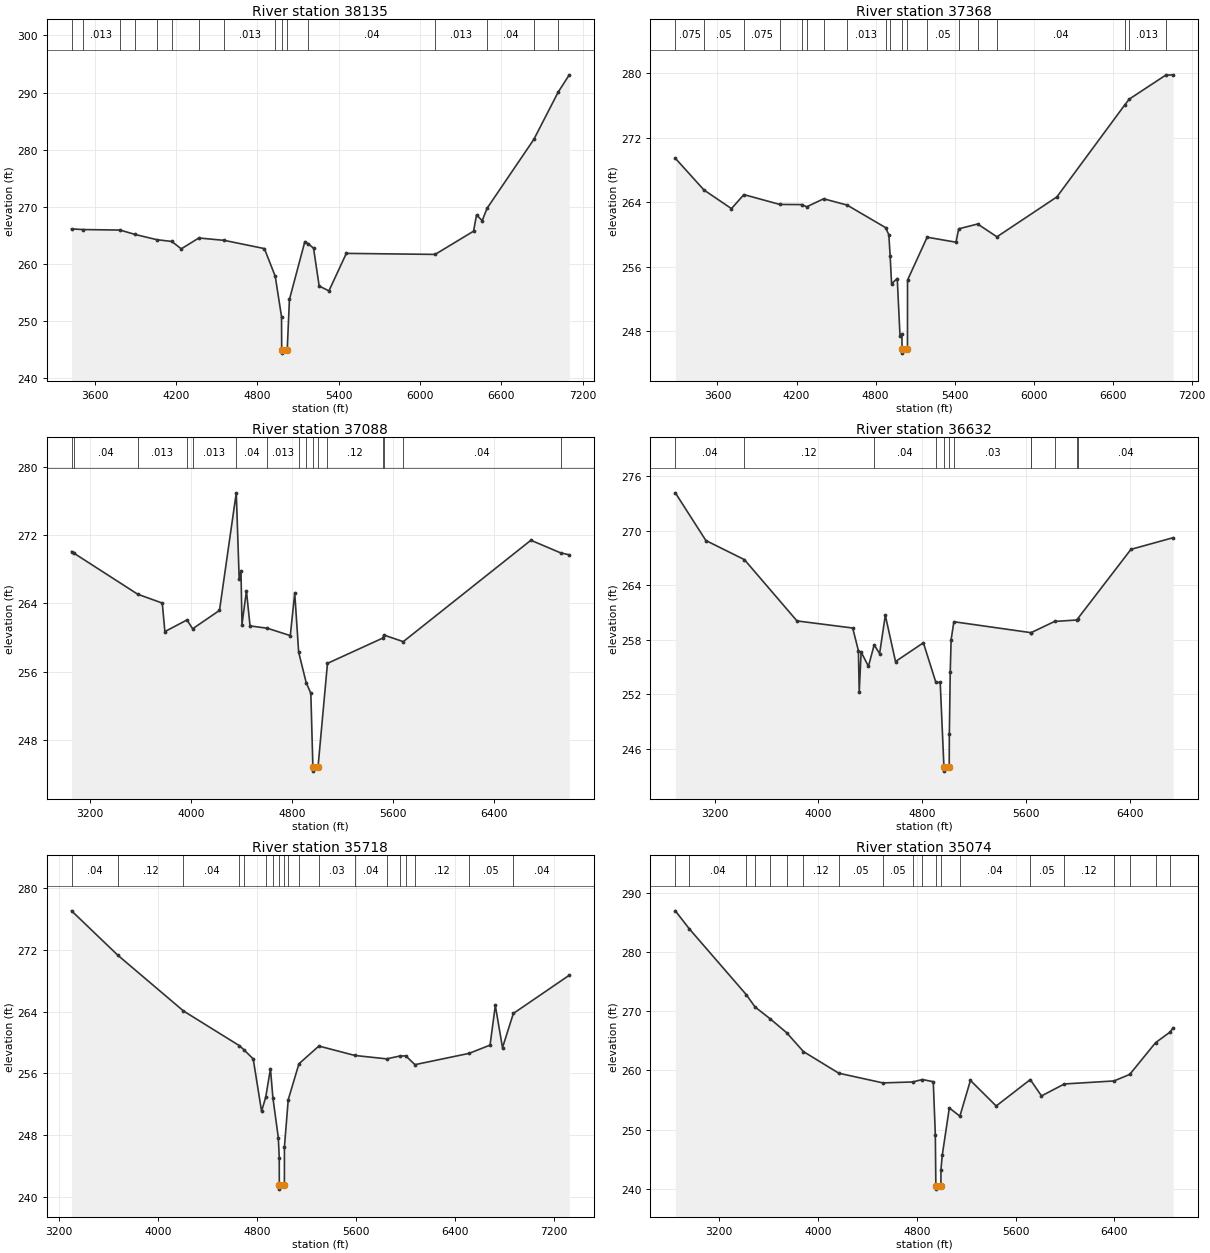
Type RM Length L Ch R = 1 ,38135   ,767,767,767
BEGIN DESCRIPTION:
Mapping XS 6f07b8e3
END DESCRIPTION:
XS GIS Cut Line= 3
      2448049.68     13541974.81      2446674.72     13541245.66
      2445021.93     13539926.21
#Sta/Elev= 30
  3430.1  266.09  3511.5  265.97  3787.8  265.88  3898.6  265.11  4059.8  264.19
  4169.4  263.88  4239.1  262.59  4369.3  264.49  4557.3  264.07  4852.5  262.63
  4932.5  257.77  4978.8   250.7  4980.1   244.8  4981.1   244.3  5020.7   244.8
  5037.2  253.71  5150.9  263.86  5176.9  263.45    5215   262.7  5256.6  256.06
  5328.6  255.22  5456.7  261.79  6111.9  261.61    6395  265.68  6417.4  268.53
    6459  267.53  6494.7  269.69  6839.6  281.77  7019.6  290.08  7101.3   293.1
#Mann= 16 ,-1 , 0
  3430.1    .075       0  3511.5    .013       0  3787.8     .05       0
  3898.6    .075       0  4059.8     .05       0  4169.4    .013       0
  4369.3     .05       0  4557.3    .013       0  4932.5     .12       0
  4980.1     .05       0  5020.7     .12       0  5176.9     .04       0
  6111.9    .013       0  6494.7     .04       0  6839.6     .05       0
  7019.6     .04       0
Bank Sta=4980.1,5020.7
XS Rating Curve= 0 ,0
Exp/Cntr=0.3,0.1

Type RM Length L Ch R = 1 ,37368   ,280,280,280
BEGIN DESCRIPTION:
Mapping XS 3e2aa14e
END DESCRIPTION:
XS GIS Cut Line= 3
      2448209.42     13542009.52      2447126.11     13540669.27
      2445766.03     13539128.77
#Sta/Elev= 30
  3280.2  269.46  3497.8  265.52  3706.3  263.21  3800.6  264.95    4073  263.73
  4243.7  263.71  4276.3  263.43    4406  264.43  4584.2  263.65  4876.3  260.85
  4900.8  259.97  4911.1  257.28  4921.6  253.89  4964.8  254.53  4985.6  247.45
    5000  247.64  5001.4  245.77  5002.4  245.27  5042.3  245.77  5042.8  254.34
  5191.7  259.66  5410.8  259.04  5431.1   260.7  5575.1   261.3  5721.6  259.71
  6176.3  264.66    6692  276.09  6726.4  276.81  7001.5  279.77  7058.5  279.82
#Mann= 19 ,-1 , 0
  3280.2    .075       0  3497.8     .05       0  3800.6    .075       0
    4073     .05       0  4243.7    .013       0  4276.3     .05       0
    4406    .075       0  4584.2    .013       0  4876.3     .12       0
  4911.1      .1       0  5001.4     .05       0  5042.3      .1       0
  5191.7     .05       0  5431.1     .12       0  5575.1     .05       0
  5721.6     .04       0    6692     .05       0  6726.4    .013       0
  7001.5     .04       0
Bank Sta=5001.4,5042.3
XS Rating Curve= 0 ,0
Exp/Cntr=0.3,0.1

Type RM Length L Ch R = 1 ,37088   ,456,456,456
BEGIN DESCRIPTION:
Mapping XS b13de14d
END DESCRIPTION:
XS GIS Cut Line= 3
      2448508.07     13541954.01      2447237.22     13540398.44
      2446049.84     13538863.86
#Sta/Elev= 30
  3051.7  270.09  3068.4  269.92  3576.6  265.08  3771.4  264.04  3792.2  260.69
  3967.6  262.06  4012.5  261.02  4225.5  263.18  4358.6  276.99  4381.6  266.91
    4396  267.76  4403.9  261.52  4439.1  265.48  4467.8  261.36  4606.1  261.08
  4787.2  260.22  4822.4  265.23  4853.6  258.27  4913.6  254.68  4950.2  253.44
  4966.4   244.8  4967.4   244.3  5007.3   244.8  5082.2  256.96  5521.2  259.93
  5528.8  260.29  5683.7  259.51    6696  271.42  6931.7  269.94  7000.7  269.71
#Mann= 16 ,-1 , 0
  3051.7    .013       0  3068.4     .04       0  3576.6    .013       0
  3967.6     .12       0  4012.5    .013       0  4358.6     .04       0
  4606.1    .013       0  4853.6     .04       0  4913.6      .1       0
  4966.4     .05       0  5007.3      .1       0  5082.2     .12       0
  5521.2     .05       0  5528.8     .12       0  5683.7     .04       0
  6931.7    .013       0
Bank Sta=4966.4,5007.3
XS Rating Curve= 0 ,0
Exp/Cntr=0.3,0.1

Type RM Length L Ch R = 1 ,36632   ,914,914,914
BEGIN DESCRIPTION:
Mapping XS d9003122
END DESCRIPTION:
XS GIS Cut Line= 3
      2448855.29     13541884.56      2447653.89     13540210.94
      2446355.24     13538995.63
#Sta/Elev= 30
  2896.3  274.14    3132   268.9  3429.2   266.8  3834.4  260.07  4264.2  259.29
  4308.4  256.79  4314.5  252.24  4329.3  256.65  4385.8  255.08  4429.8  257.44
  4471.7  256.48  4515.9  260.68  4594.5  255.61  4809.4  257.67  4905.9  253.31
  4939.2  253.32  4967.7  244.07  4968.7  243.57  5008.6  244.07  5009.7  247.67
  5016.5  254.46  5023.4  258.02  5044.6  259.98  5639.2  258.78  5639.9  258.78
  5821.3  260.01  5991.4  260.17  5998.9   260.3  6410.2  267.93  6735.1  269.21
#Mann= 12 ,-1 , 0
  2896.3     .04       0  3429.2     .12       0  4429.8     .04       0
  4905.9     .05       0  4967.7     .05       0  5008.6     .05       0
  5044.6     .03       0  5639.2     .05       0  5639.9     .12       0
  5821.3     .04       0  5991.4     .05       0  5998.9     .04       0
Bank Sta=4967.7,5008.6
XS Rating Curve= 0 ,0
Exp/Cntr=0.3,0.1

Type RM Length L Ch R = 1 ,35718   ,644,644,644
BEGIN DESCRIPTION:
Mapping XS 8cd50fa6
END DESCRIPTION:
XS GIS Cut Line= 4
      2449035.84      13541856.8      2448445.55     13540460.94
       2448077.5     13539947.05      2446480.28     13538967.89
#Sta/Elev= 30
  3300.8  277.04  3676.1  271.27  4205.2  264.07  4657.5  259.57    4697  258.99
  4768.5  257.86  4835.9  251.08  4869.7  252.92  4907.7   256.6  4927.5  252.83
  4971.2  247.67  4978.9  245.05  4979.3   241.5  4980.3     241  5020.3   241.5
  5020.7  246.47  5051.3  252.58  5137.8  257.23  5298.9  259.53  5589.3  258.31
  5846.1  257.87  5951.3  258.23  6000.8  258.26  6075.1  257.12  6512.6  258.58
  6681.8  259.65  6724.4  264.78  6782.4  259.32  6870.1  263.75  7321.9   268.7
#Mann= 19 ,-1 , 0
  3300.8     .04       0  3676.1     .12       0  4205.2     .04       0
  4657.5     .05       0    4697     .04       0  4869.7     .05       0
  4927.5     .04       0  4979.3     .04       0  5020.3     .04       0
  5051.3     .12       0  5137.8     .04       0  5298.9     .03       0
  5589.3     .04       0  5846.1     .05       0  5951.3     .03       0
  6000.8     .05       0  6075.1     .12       0  6512.6     .05       0
  6870.1     .04       0
Bank Sta=4979.3,5020.3
XS Rating Curve= 0 ,0
Exp/Cntr=0.3,0.1

Type RM Length L Ch R = 1 ,35074   ,414,414,414
BEGIN DESCRIPTION:
Mapping XS bcb781be
END DESCRIPTION:
XS GIS Cut Line= 4
      2449889.97     13541266.46      2448619.16     13539842.88
        2447765.     13539606.77      2446883.73     13538739.38
#Sta/Elev= 30
  2844.5  286.95  2958.8  283.88  3418.9   272.8  3490.5   270.7  3610.7  268.75
  3746.3  266.36  3881.9  263.18  4168.2  259.53  4525.3  257.89  4767.6  258.05
  4845.3  258.46  4933.5  258.09  4950.1  249.17  4954.4  240.45  4955.4  239.95
  4995.5  240.45  4995.7  243.24  5006.1  245.66  5063.5  253.66    5149  252.27
  5234.3  258.31  5443.1  253.99    5719  258.45  5809.9  255.69    5995  257.71
  6397.2  258.22  6524.8  259.33    6734  264.69  6850.3  266.46  6875.5  267.17
#Mann= 20 ,-1 , 0
  2844.5    .013       0  2958.8     .04       0  3418.9     .05       0
  3490.5     .04       0  3610.7     .05       0  3746.3     .05       0
  3881.9     .12       0  4168.2     .05       0  4525.3     .05       0
  4767.6     .04       0  4845.3     .12       0  4954.4     .05       0
  4995.5      .1       0    5149     .04       0    5719     .05       0
    5995     .12       0  6397.2     .05       0  6524.8     .04       0
    6734     .04       0  6850.3    .013       0
Bank Sta=4954.4,4995.5
XS Rating Curve= 0 ,0
Exp/Cntr=0.3,0.1

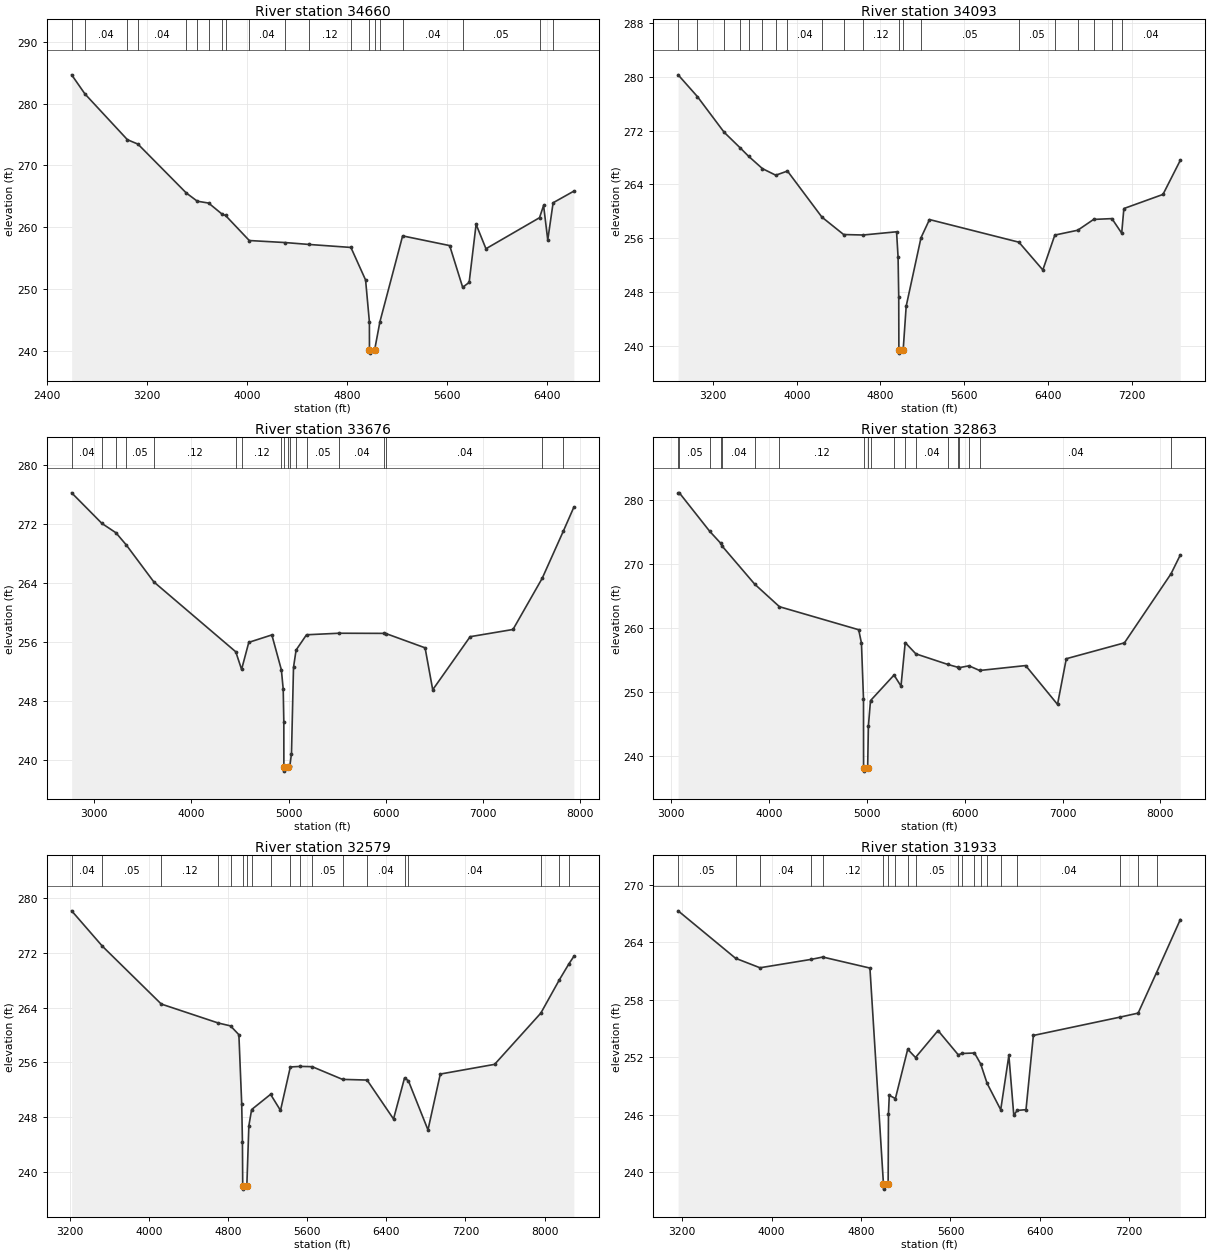
Type RM Length L Ch R = 1 ,34660   ,567,567,567
BEGIN DESCRIPTION:
Mapping XS a5333f94
END DESCRIPTION:
XS GIS Cut Line= 4
      2450042.76     13541085.92      2448681.66     13539599.82
      2448056.66     13539197.05      2446939.29     13538627.95
#Sta/Elev= 30
  2599.8  284.66    2706  281.57  3045.5  274.16  3129.6  273.45  3516.4  265.53
    3604  264.21  3694.3  263.91  3804.2  262.08  3829.2  261.91  4019.1  257.85
  4306.3  257.52  4498.9  257.21  4831.2  256.73  4948.5  251.46  4978.9  244.69
  4979.5  240.13  4980.5  239.63  5020.6  240.13  5062.9   244.7  5244.4   258.6
  5620.3  257.03  5724.2  250.28    5776  251.07  5831.5  260.47  5910.3  256.52
  6338.2  261.54  6370.8  263.52  6404.1  257.94  6446.9  263.96  6612.5  265.84
#Mann= 20 ,-1 , 0
  2599.8     .05       0    2706     .04       0  3045.5     .05       0
  3129.6     .04       0  3516.4     .05       0    3604     .04       0
  3694.3     .05       0  3804.2     .04       0  3829.2     .05       0
  4019.1     .04       0  4306.3     .05       0  4498.9     .12       0
  4831.2      .1       0  4979.5     .05       0  5020.6      .1       0
  5062.9     .12       0  5244.4     .04       0  5724.2     .05       0
  6338.2    .013       0  6446.9     .04       0
Bank Sta=4979.5,5020.6
XS Rating Curve= 0 ,0
Exp/Cntr=0.3,0.1

Type RM Length L Ch R = 1 ,34093   ,417,417,417
BEGIN DESCRIPTION:
Mapping XS 6cfdc242
END DESCRIPTION:
XS GIS Cut Line= 3
      2450160.84     13540933.17      2448820.55     13539273.44
      2446653.91     13537724.84
#Sta/Elev= 30
  2867.3   280.3    3051  277.07    3307  271.75  3458.2  269.46  3540.5  268.18
  3672.7  266.34  3799.9  265.36  3911.7  265.98  4240.9  259.12  4448.4  256.53
  4634.4  256.46  4953.7  256.94  4968.1  253.19  4974.5  247.22  4975.9  239.38
  4976.9  238.88    5017  239.38  5045.7  245.87  5187.1  256.05  5268.1  258.76
  6122.3  255.39  6350.7  251.26  6465.3  256.45    6684  257.17  6835.9  258.78
  7010.7   258.9    7104  256.73  7124.8   260.4  7498.3   262.5  7663.8  267.58
#Mann= 20 ,-1 , 0
  2867.3     .04       0    3051    .013       0    3307     .04       0
  3458.2     .05       0  3540.5     .04       0  3672.7     .12       0
  3799.9     .12       0  3911.7     .04       0  4240.9     .04       0
  4448.4      .1       0  4634.4     .12       0  4975.9     .05       0
    5017     .12       0  5187.1     .05       0  6122.3     .05       0
  6465.3     .04       0    6684     .05       0  6835.9     .04       0
  7010.7    .013       0    7104     .04       0
Bank Sta=4975.9,5017
XS Rating Curve= 0 ,0
Exp/Cntr=0.3,0.1

Type RM Length L Ch R = 1 ,33676   ,813,813,813
BEGIN DESCRIPTION:
Mapping XS 149d2e0c
END DESCRIPTION:
XS GIS Cut Line= 3
      2450362.22     13540884.55      2449119.16     13539023.44
      2446820.56     13537210.94
#Sta/Elev= 30
  2767.3  276.25  3079.4  272.09  3222.9  270.83  3327.9   269.2  3612.9  264.16
  4455.4  254.68  4515.2  252.29  4589.2  255.96  4826.5  256.97  4924.5  252.23
  4943.4   249.6  4949.6  245.14  4950.1  238.99  4951.1  238.49  4991.2  238.99
  5011.7  239.21  5028.4  240.86  5049.2  252.56  5075.8  254.92  5182.9  256.99
  5516.6   257.2  5977.8  257.18    6005  257.13  6402.5  255.22  6481.1  249.53
  6865.9  256.73  7306.8  257.71  7607.4  264.66  7824.8  271.06  7932.6   274.3
#Mann= 18 ,-1 , 0
  2767.3     .04       0  3079.4     .12       0  3222.9    .013       0
  3327.9     .05       0  3612.9     .12       0  4455.4      .1       0
  4515.2     .12       0  4924.5      .1       0  4950.1     .05       0
  4991.2      .1       0  5011.7     .05       0  5075.8      .1       0
  5182.9     .05       0  5516.6     .04       0  5977.8     .05       0
    6005     .04       0  7607.4     .05       0  7824.8     .03       0
Bank Sta=4950.1,4991.2
XS Rating Curve= 0 ,0
Exp/Cntr=0.3,0.1

Type RM Length L Ch R = 1 ,32863   ,284,284,284
BEGIN DESCRIPTION:
Mapping XS abae4d2e
END DESCRIPTION:
XS GIS Cut Line= 3
      2451230.27     13539947.04      2449778.89     13538634.55
      2446945.52     13537197.03
#Sta/Elev= 30
  3069.2  281.08  3081.6   281.1    3392  275.09  3505.6   273.2  3517.3  272.81
  3852.5  266.82  4105.2   263.3  4915.1   259.7  4943.5  257.61  4964.4  248.87
  4965.2   238.1  4966.2   237.6  5006.9   238.1  5014.5  244.65    5036  248.62
  5276.6  252.62  5347.7  250.89  5390.9  257.69  5499.6  255.93  5825.6  254.28
  5934.3  253.81  5945.5  253.78    6043  254.06  6151.7  253.33  6622.2   254.1
  6947.9  248.03  7037.6  255.17  7631.9  257.65  8108.1  268.44  8203.2  271.39
#Mann= 19 ,-1 , 0
  3069.2     .04       0  3081.6     .05       0    3392     .04       0
  3505.6     .05       0  3517.3     .04       0  3852.5     .05       0
  4105.2     .12       0  4965.2     .05       0  5006.9     .12       0
    5036     .04       0  5276.6     .05       0  5390.9     .12       0
  5499.6     .04       0  5825.6     .05       0  5934.3     .12       0
  5945.5     .05       0    6043     .12       0  6151.7     .04       0
  8108.1    .013       0
Bank Sta=4965.2,5006.9
XS Rating Curve= 0 ,0
Exp/Cntr=0.3,0.1

Type RM Length L Ch R = 1 ,32579   ,646,646,646
BEGIN DESCRIPTION:
Mapping XS efc76d25
END DESCRIPTION:
XS GIS Cut Line= 4
       2451348.3     13539363.69      2450153.89     13538467.88
      2449278.89     13538245.66      2447016.45     13536809.08
#Sta/Elev= 30
  3219.3  278.17  3529.9  272.99  4125.3  264.52  4701.9  261.74  4825.3  261.32
  4909.6  260.03  4938.2  249.88  4945.4  244.33  4948.3  237.92  4949.3  237.42
    4990  237.92  5010.4  246.69  5038.3  249.07    5230   251.3  5330.2  248.94
  5429.7  255.31  5530.4  255.39  5650.2  255.35  5956.9  253.49  6205.3  253.39
  6472.6  247.69  6583.8  253.69  6622.8  253.29  6820.8  246.09  6945.3  254.27
  7494.2  255.69  7961.2  263.19    8150   268.1    8245   270.4  8295.1   271.5
#Mann= 19 ,-1 , 0
  3219.3     .04       0  3529.9     .05       0  4125.3     .12       0
  4701.9     .04       0  4825.3     .12       0  4948.3     .05       0
    4990     .12       0  5038.3     .04       0    5230     .05       0
  5429.7     .12       0  5530.4     .04       0  5650.2     .05       0
  5956.9     .12       0  6205.3     .04       0  6583.8     .12       0
  6622.8     .04       0  7961.2     .05       0    8150     .12       0
    8245     .05       0
Bank Sta=4948.3,4990
XS Rating Curve= 0 ,0
Exp/Cntr=0.3,0.1

Type RM Length L Ch R = 1 ,31933   ,750,750,750
BEGIN DESCRIPTION:
Mapping XS ec778b28
END DESCRIPTION:
XS GIS Cut Line= 4
      2450994.14      13538863.7      2449633.05     13537849.82
      2449230.28     13538016.49       2447209.7     13536794.42
#Sta/Elev= 30
  3162.6  267.27  3676.9  262.32  3895.3  261.33  4355.9  262.21  4457.1  262.45
  4879.3   261.3  5000.5  238.74  5001.5  238.24  5042.2  238.74  5045.2  246.11
  5052.5  248.02  5107.3  247.69  5217.4  252.83  5287.2  251.97  5488.9  254.78
  5669.9  252.25  5702.2  252.39  5815.1  252.44  5869.8  251.32  5928.1  249.27
  6049.8  246.52  6122.8  252.19  6166.7  245.96  6197.8  246.45  6276.1  246.53
    6342  254.27  7120.8  256.19  7279.7   256.6  7444.4  260.83  7657.1  266.36
#Mann= 20 ,-1 , 0
  3162.6     .05       0  3676.9     .12       0  3895.3     .04       0
  4355.9     .04       0  4457.1     .12       0  5000.5     .05       0
  5042.2     .12       0  5107.3     .05       0  5217.4     .12       0
  5287.2     .05       0  5669.9     .12       0  5702.2     .05       0
  5815.1     .04       0  5869.8     .12       0  5928.1     .04       0
  6049.8     .12       0  6197.8     .04       0  7120.8     .12       0
  7279.7     .03       0  7444.4     .05       0
Bank Sta=5000.5,5042.2
XS Rating Curve= 0 ,0
Exp/Cntr=0.3,0.1