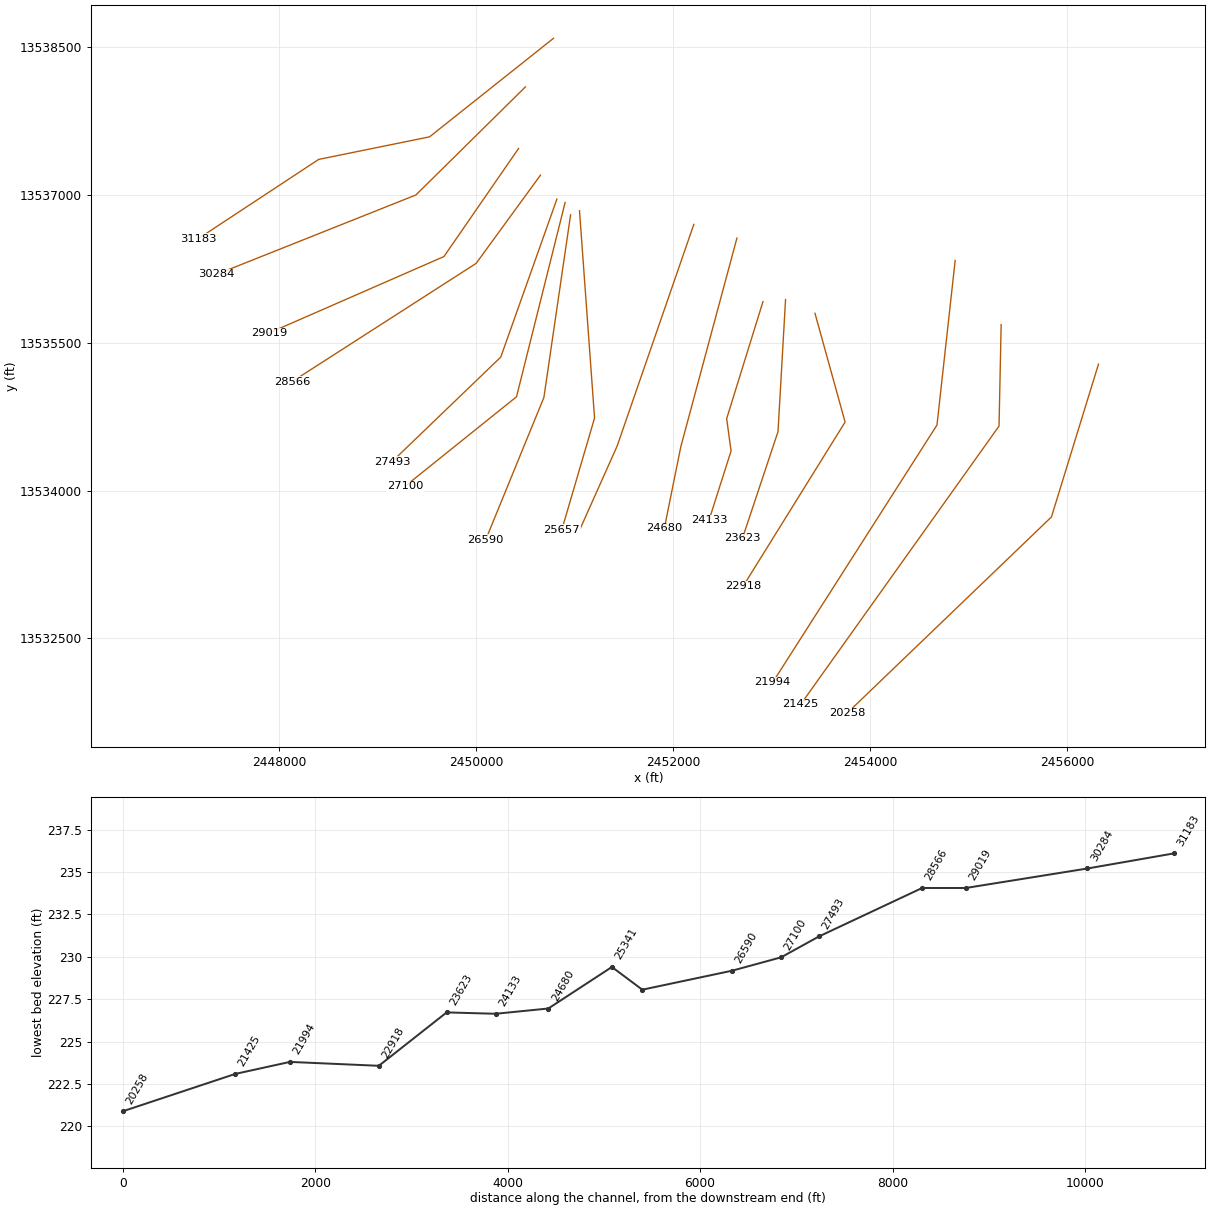
HEC-RAS study YORKTOWN CREEK.prj: YORKTOWN CREEK Base Level Engineering

--- YORKTOWN CREEK.g01 (geometry) --- (continued)

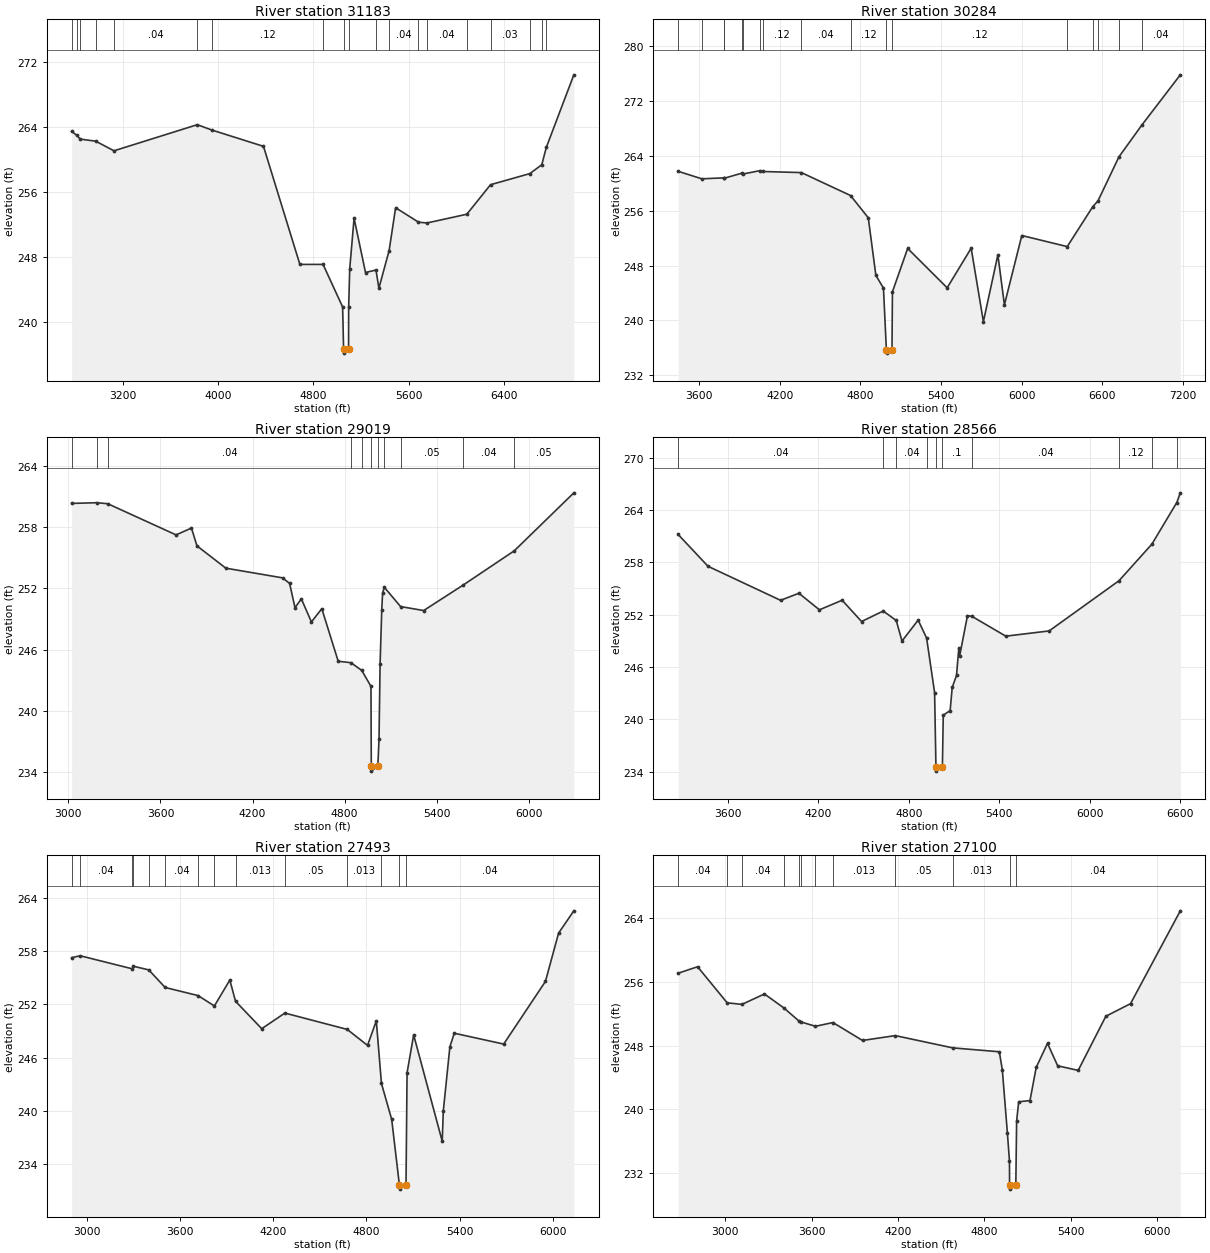
Type RM Length L Ch R = 1 ,31183   ,899,899,899
BEGIN DESCRIPTION:
Mapping XS d1f5751f
END DESCRIPTION:
XS GIS Cut Line= 4
       2450785.8     13538592.86      2449528.89     13537592.88
      2448403.89     13537363.71      2447183.07     13536559.09
#Sta/Elev= 30
  2770.9  263.45  2814.7  262.95  2842.7  262.49  2972.5  262.24  3126.2  261.05
  3825.6  264.27  3948.5  263.61  4381.6   261.6  4687.1  247.04  4881.7  247.04
  5046.1  241.79  5054.1   236.6  5055.1   236.1  5095.9   236.6  5096.7  241.77
  5105.6   246.5  5142.2  252.73  5238.2  246.04  5326.1  246.35  5350.5   244.1
  5436.4  248.75    5491  254.03  5682.9  252.25  5754.3  252.15  6088.9  253.23
  6287.9  256.87    6618  258.24    6718  259.33  6756.4  261.48  6987.3  270.42
#Mann= 19 ,-1 , 0
  2770.9     .05       0  2814.7     .04       0  2842.7     .05       0
  2972.5     .12       0  3126.2     .04       0  3825.6     .05       0
  3948.5     .12       0  4881.7      .1       0  5054.1     .05       0
  5095.9      .1       0  5326.1     .12       0  5436.4     .04       0
  5682.9     .12       0  5754.3     .04       0  6088.9     .12       0
  6287.9     .03       0    6618     .05       0    6718     .04       0
  6756.4     .05       0
Bank Sta=5054.1,5095.9
XS Rating Curve= 0 ,0
Exp/Cntr=0.3,0.1

Type RM Length L Ch R = 1 ,30284   ,1265,1265,1265
BEGIN DESCRIPTION:
Mapping XS 08bfa9c7
END DESCRIPTION:
XS GIS Cut Line= 3
       2450501.1     13538099.82        2449390.      13537002.6
      2447369.56      13536197.2
#Sta/Elev= 30
  3443.7  261.77  3620.2  260.67  3782.9  260.81  3785.9  260.75  3920.3  261.51
  3927.3  261.38  4054.7  261.87  4071.8  261.74  4360.8  261.58  4726.7  258.23
  4858.6  254.98  4915.1  246.57  4971.7   244.7  4993.2  235.71  4994.2  235.21
    5035  235.71  5038.4  244.17  5151.6   250.5  5445.5  244.75  5624.2  250.53
  5715.1  239.81  5822.9  249.56  5871.5  242.26    6001  252.39  6338.9  250.77
  6529.3  256.61  6567.7  257.44  6723.7  263.88  6893.7  268.51  7180.3  275.86
#Mann= 17 ,-1 , 0
  3443.7     .04       0  3620.2     .05       0  3782.9     .12       0
  3785.9     .05       0  3920.3     .04       0  3927.3     .12       0
  4054.7     .05       0  4071.8     .12       0  4360.8     .04       0
  4726.7     .12       0  4993.2     .05       0    5035     .12       0
  6338.9     .05       0  6529.3     .12       0  6567.7     .04       0
  6723.7     .05       0  6893.7     .04       0
Bank Sta=4993.2,5035
XS Rating Curve= 0 ,0
Exp/Cntr=0.3,0.1

Type RM Length L Ch R = 1 ,29019   ,453,453,453
BEGIN DESCRIPTION:
Mapping XS b938e9fc
END DESCRIPTION:
XS GIS Cut Line= 3
      2450431.65      13537474.8      2449674.72      13536377.6
      2447898.71      13535600.6
#Sta/Elev= 30
  3021.4  260.35  3185.2  260.42  3256.6  260.32  3701.5  257.26  3801.9  257.93
  3837.8  256.18  4025.8  253.99  4395.3  253.04  4441.4  252.49  4476.3  250.11
  4517.7  250.98  4583.3  248.71    4651  250.01  4757.9  244.85  4840.7  244.71
  4911.3  243.95  4971.4  242.38  4973.4  234.56  4974.4  234.06  5016.2  234.56
  5023.7  237.19  5030.8  244.61  5041.6  249.92  5047.1  251.55  5058.4  252.11
  5164.4  250.22  5314.6  249.83  5573.7  252.35  5905.1   255.7  6292.9  261.39
#Mann= 11 ,-1 , 0
  3021.4     .12       0  3185.2     .05       0  3256.6     .04       0
  4840.7     .12       0  4911.3      .1       0  4973.4     .05       0
  5016.2      .1       0  5058.4     .12       0  5164.4     .05       0
  5573.7     .04       0  5905.1     .05       0
Bank Sta=4973.4,5016.2
XS Rating Curve= 0 ,0
Exp/Cntr=0.3,0.1

Type RM Length L Ch R = 1 ,28566   ,1073,1073,1073
BEGIN DESCRIPTION:
Mapping XS bee64617
END DESCRIPTION:
XS GIS Cut Line= 3
      2450653.91     13537204.02      2450001.11     13536308.16
      2448133.06     13535106.77
#Sta/Elev= 30
    3270  261.19  3468.2  257.54  3949.3  253.64  4070.8  254.45  4206.8  252.55
  4357.4  253.65  4486.4  251.21  4629.7  252.41  4716.1  251.33  4754.3  248.97
  4861.5  251.37  4917.5  249.31  4970.5  243.06  4979.4  234.56  4980.4  234.06
  5022.2  234.56  5027.9  240.48  5073.5     241  5087.2  243.65  5115.8  245.03
  5130.9  248.15  5136.9   247.3  5188.4  251.88  5217.2  251.81  5442.6  249.53
  5729.9  250.13  6193.4  255.89  6411.2  260.08  6576.3  264.85  6599.5  265.96
#Mann= 10 ,-1 , 0
    3270     .04       0  4629.7     .05       0  4716.1     .04       0
  4917.5      .1       0  4979.4     .05       0  5022.2      .1       0
  5217.2     .04       0  6193.4     .12       0  6411.2     .05       0
  6576.3     .04       0
Bank Sta=4979.4,5022.2
XS Rating Curve= 0 ,0
Exp/Cntr=0.3,0.1

Type RM Length L Ch R = 1 ,27493   ,393,393,393
BEGIN DESCRIPTION:
Mapping XS bb18825a
END DESCRIPTION:
XS GIS Cut Line= 3
      2450820.54     13536960.89      2450251.11     13535356.77
      2449146.97      13534294.3
#Sta/Elev= 30
  2901.7  257.26  2956.9  257.47  3292.8     256  3299.8  256.29  3398.4  255.88
  3504.1   253.9  3715.5  252.99  3821.1  251.82  3920.5  254.74  3957.1  252.35
  4125.9  249.26  4275.2  251.02  4676.7  249.18  4807.4  247.38    4864  250.14
    4897   243.1    4963  239.05  5012.4   231.7  5013.4   231.2  5055.2   231.7
  5062.1  244.29  5104.5  248.56  5288.5  236.59  5295.4     240  5337.9  247.23
  5366.2  248.75  5684.4  247.53  5953.2  254.58  6038.1  260.03  6136.2  262.53
#Mann= 14 ,-1 , 0
  2901.7     .05       0  2956.9     .04       0  3292.8    .013       0
  3299.8     .04       0  3398.4    .013       0  3504.1     .04       0
  3715.5     .12       0  3821.1     .04       0  3957.1    .013       0
  4275.2     .05       0  4676.7    .013       0    4897     .04       0
  5012.4     .04       0  5055.2     .04       0
Bank Sta=5012.4,5055.2
XS Rating Curve= 0 ,0
Exp/Cntr=0.3,0.1

Type RM Length L Ch R = 1 ,27100   ,510,510,510
BEGIN DESCRIPTION:
Mapping XS 18b95341
END DESCRIPTION:
XS GIS Cut Line= 3
      2450903.89     13536926.21      2450410.83     13534953.99
      2449279.45     13534044.72
#Sta/Elev= 30
  2674.2  257.08  2809.1   257.9  3014.4  253.37  3116.8  253.17  3273.3  254.48
  3409.6   252.7  3511.4   251.1  3526.1  250.97  3627.2  250.42  3748.5  250.89
  3953.6  248.64  4180.9  249.25  4579.3  247.71  4902.8  247.22  4923.6  244.96
  4958.9  237.02  4973.3  233.49    4974  230.47    4975  229.97  5017.3  230.47
  5022.9  238.52  5037.2  240.94  5115.6  241.09  5158.8  245.26  5237.2  248.28
  5307.6  245.46    5450  244.88    5642  251.68  5813.2  253.26  6158.6  264.92
#Mann= 12 ,-1 , 0
  2674.2     .04       0  3014.4    .013       0  3116.8     .04       0
  3409.6     .05       0  3511.4     .12       0  3526.1     .05       0
  3627.2     .04       0  3748.5    .013       0  4180.9     .05       0
  4579.3    .013       0    4974     .04       0  5017.3     .04       0
Bank Sta=4974,5017.3
XS Rating Curve= 0 ,0
Exp/Cntr=0.3,0.1

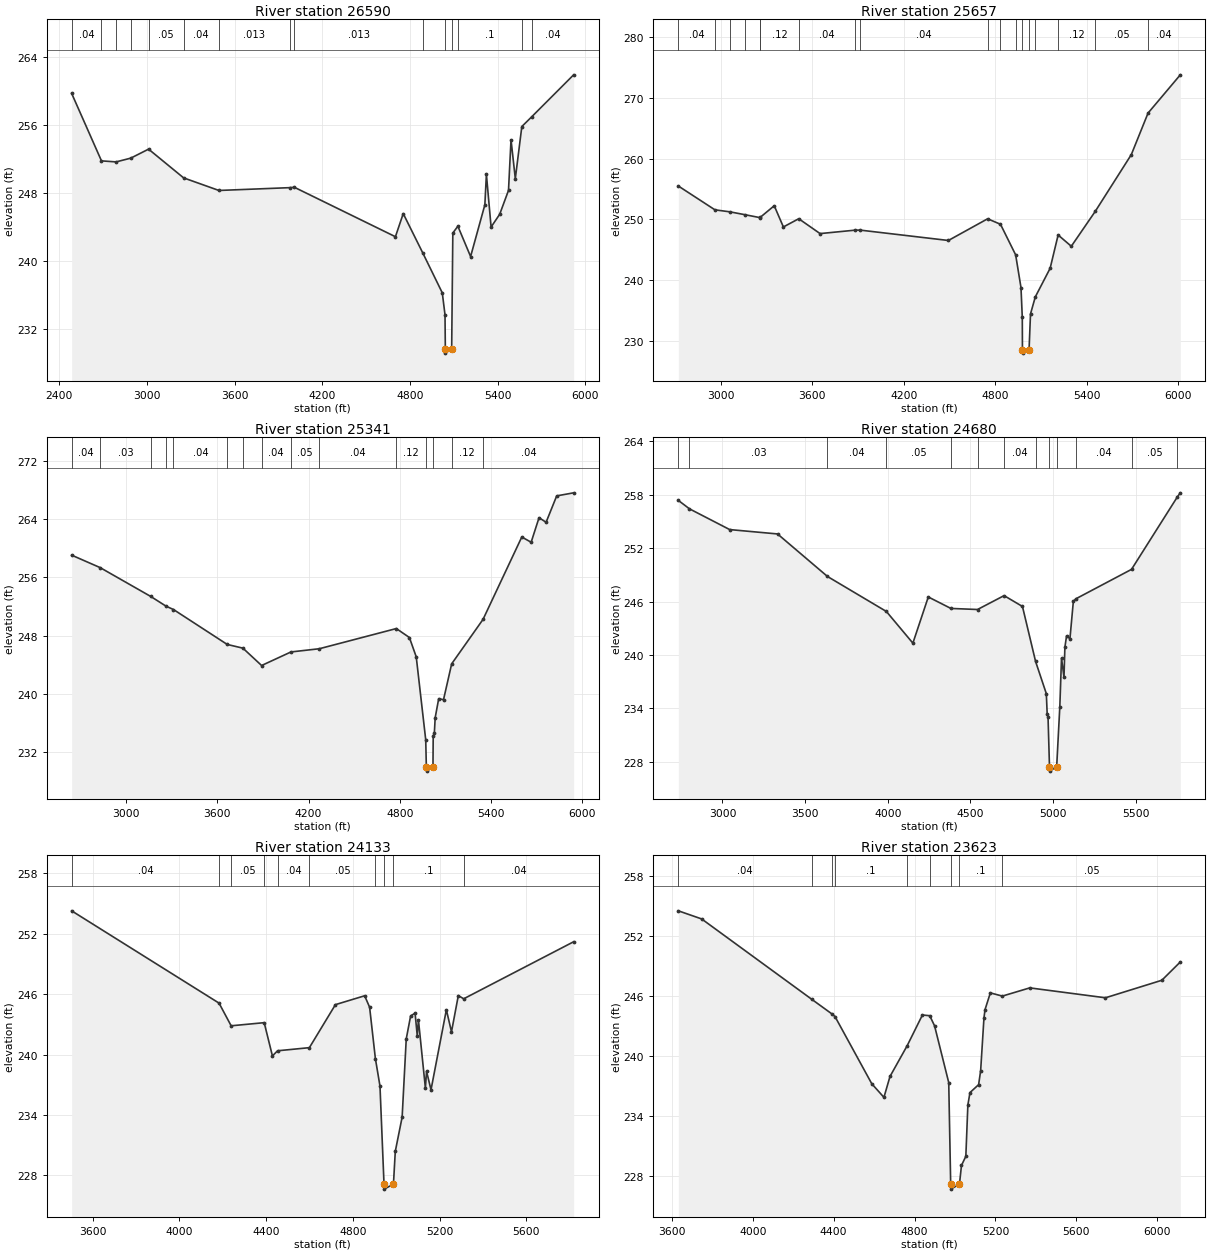
Type RM Length L Ch R = 1 ,26590   ,933,933,933
BEGIN DESCRIPTION:
Mapping XS 1b86beb5
END DESCRIPTION:
XS GIS Cut Line= 3
      2450959.44     13536801.19      2450688.61     13534947.05
      2450098.34     13533502.62
#Sta/Elev= 30
  2485.3  259.73  2689.4  251.79  2789.4  251.67  2889.5  252.11  3011.6  253.17
  3251.4  249.79  3492.9  248.31  3976.6  248.64  4009.6  248.68  4700.4  242.87
  4753.8  245.59  4888.2  240.94    5021  236.27  5039.6  233.69  5041.9  229.68
  5042.9  229.18  5085.2  229.68  5093.1   243.3  5127.6  244.11  5214.7  240.54
  5312.2  246.62  5322.8   250.2  5354.9  244.01  5413.7  245.51    5474  248.32
  5491.2  254.27  5520.6   249.7  5565.2  255.83  5633.1  256.98  5919.5  261.91
#Mann= 15 ,-1 , 0
  2485.3     .04       0  2689.4    .013       0  2789.4     .05       0
  2889.5     .04       0  3011.6     .05       0  3251.4     .04       0
  3492.9    .013       0  3976.6     .05       0  4009.6    .013       0
  4888.2     .04       0  5041.9     .04       0  5085.2     .04       0
  5127.6      .1       0  5565.2     .05       0  5633.1     .04       0
Bank Sta=5041.9,5085.2
XS Rating Curve= 0 ,0
Exp/Cntr=0.3,0.1

Type RM Length L Ch R = 1 ,25657   ,316,316,316
BEGIN DESCRIPTION:
Mapping XS b12908d8
END DESCRIPTION:
XS GIS Cut Line= 3
      2451049.72     13536842.85       2451202.5     13534738.71
       2450869.6     13533601.31
#Sta/Elev= 30
    2720  255.49  2960.3  251.58  3058.9  251.25  3157.6  250.78  3256.2   250.3
  3257.7  250.35  3349.5  252.25  3409.5  248.77  3510.4  250.12  3650.3  247.68
  3882.5  248.25  3914.1  248.25  4492.5  246.55  4750.1  250.11  4834.5  249.21
    4934  244.19    4969  238.83  4977.6  233.91  4978.6  228.56  4979.6  228.06
    5022  228.56  5031.5  234.49    5063  237.29  5160.4  241.99  5212.8  247.45
  5299.3   245.6    5456  251.31  5693.1  260.64    5803  267.46  6014.8  273.74
#Mann= 18 ,-1 , 0
    2720     .04       0  2960.3    .013       0  3058.9     .04       0
  3157.6     .05       0  3256.2     .04       0  3257.7     .12       0
  3510.4     .04       0  3882.5     .12       0  3914.1     .04       0
  4750.1     .12       0  4834.5     .04       0    4934     .12       0
  4978.6     .05       0    5022     .12       0    5063      .1       0
  5212.8     .12       0    5456     .05       0    5803     .04       0
Bank Sta=4978.6,5022
XS Rating Curve= 0 ,0
Exp/Cntr=0.3,0.1

Type RM Length L Ch R = 1 ,25341   ,661,661,661
BEGIN DESCRIPTION:
Mapping XS 9b044708
END DESCRIPTION:
XS GIS Cut Line= 3
      2452209.45     13536704.03      2451431.66     13534453.99
      2451056.68     13533613.75
#Sta/Elev= 30
  2642.4  259.03  2829.9  257.32  3162.8  253.36  3263.2  252.03  3312.1  251.57
  3665.4  246.78  3768.6  246.27  3891.5  243.89  4084.6  245.75  4270.7  246.19
  4777.4  248.96  4863.3  247.73  4908.3  245.08  4970.7   233.7  4974.9   229.9
  4975.9   229.4  5018.3   229.9  5019.9  234.22  5027.3  234.58  5032.9  236.73
    5056  239.34  5087.7   239.2  5141.3  244.12  5347.6  250.22  5602.4  261.52
  5663.9   260.8  5715.8  264.17  5762.2  263.54  5831.9  267.16  5943.2  267.58
#Mann= 15 ,-1 , 0
  2642.4     .04       0  2829.9     .03       0  3162.8     .04       0
  3263.2     .03       0  3312.1     .04       0  3665.4     .03       0
  3768.6     .05       0  3891.5     .04       0  4084.6     .05       0
  4270.7     .04       0  4777.4     .12       0  4974.9     .05       0
  5018.3     .12       0  5141.3     .12       0  5347.6     .04       0
Bank Sta=4974.9,5018.3
XS Rating Curve= 0 ,0
Exp/Cntr=0.3,0.1

Type RM Length L Ch R = 1 ,24680   ,547,547,547
BEGIN DESCRIPTION:
Mapping XS a9f516fc
END DESCRIPTION:
XS GIS Cut Line= 3
      2452646.93     13536565.07       2452077.5     13534447.05
      2451910.82     13533620.63
#Sta/Elev= 30
  2733.2  257.37  2800.7  256.42  3043.9  254.09  3333.2   253.6  3635.4  248.82
  3991.5  244.89  4151.9  241.33  4245.1  246.52  4381.9  245.23  4542.9  245.11
  4703.6  246.67  4814.7  245.45  4894.1  239.27  4959.1  235.65  4964.3  233.33
  4969.4  233.03  4978.2  227.45  4979.2  226.95  5021.7  227.45  5040.7  234.21
  5050.9  239.65  5065.9  237.49  5071.3  240.86  5081.5  242.15  5101.9  241.83
  5122.4  246.01  5137.5  246.31  5474.4  249.62  5751.6  257.76  5769.5  258.22
#Mann= 13 ,-1 , 0
  2733.2     .04       0  2800.7     .03       0  3635.4     .04       0
  3991.5     .05       0  4381.9     .04       0  4542.9     .05       0
  4703.6     .04       0  4894.1      .1       0  4978.2     .05       0
  5021.7      .1       0  5137.5     .04       0  5474.4     .05       0
  5751.6     .12       0
Bank Sta=4978.2,5021.7
XS Rating Curve= 0 ,0
Exp/Cntr=0.3,0.1

Type RM Length L Ch R = 1 ,24133   ,510,510,510
BEGIN DESCRIPTION:
Mapping XS 1a0a4166
END DESCRIPTION:
XS GIS Cut Line= 4
      2452910.83     13535919.25      2452542.78     13534731.77
       2452587.3     13534403.55      2452362.68      13533698.5
#Sta/Elev= 30
  3503.3  254.26  4182.9   245.1  4238.7  242.85  4391.1  243.16    4429  239.86
  4452.8  240.37  4599.4  240.68  4719.5  244.95  4854.3  245.83  4877.1  244.69
  4903.7   239.6  4924.9  236.87  4943.5  227.14  4944.5  226.64    4987  227.14
  4995.5  230.39  5027.1  233.79    5046  241.55  5066.2  243.83  5086.7   244.1
  5096.9  241.84  5102.1  243.45  5134.3  236.67  5139.6  238.33  5160.2   236.5
    5231  244.44  5254.6  242.25  5286.1  245.85  5310.9  245.53  5817.7  251.19
#Mann= 10 ,-1 , 0
  3503.3     .04       0  4182.9     .12       0  4238.7     .05       0
  4391.1     .12       0  4452.8     .04       0  4599.4     .05       0
  4903.7      .1       0  4943.5     .05       0    4987      .1       0
  5310.9     .04       0
Bank Sta=4943.5,4987
XS Rating Curve= 0 ,0
Exp/Cntr=0.3,0.1

Type RM Length L Ch R = 1 ,23623   ,705,705,705
BEGIN DESCRIPTION:
Mapping XS b697295f
END DESCRIPTION:
XS GIS Cut Line= 3
        2453140.     13535940.14      2453063.61     13534599.82
      2452703.07     13533518.22
#Sta/Elev= 30
  3631.7  254.53    3747  253.72  4291.5  245.69  4390.4  244.24  4406.4  243.97
  4588.4  237.25  4648.5  235.89  4678.5  237.98  4763.4  241.05  4838.8  244.12
    4875  244.05  4898.9  243.04    4969  237.37  4978.6  227.22  4979.6  226.72
  5022.1  227.22    5032  229.09  5053.6     230  5063.6  235.13  5074.1  236.37
  5116.8  237.16  5126.8  238.55  5143.2  243.82  5148.5  244.66  5174.8  246.33
  5234.1  246.01  5369.8  246.83    5744  245.84  6022.8  247.59  6114.3  249.42
#Mann= 9 ,-1 , 0
  3631.7     .04       0  4291.5      .1       0  4390.4     .12       0
  4406.4      .1       0  4763.4     .12       0    4875      .1       0
  4978.6     .05       0  5022.1      .1       0  5234.1     .05       0
Bank Sta=4978.6,5022.1
XS Rating Curve= 0 ,0
Exp/Cntr=0.3,0.1

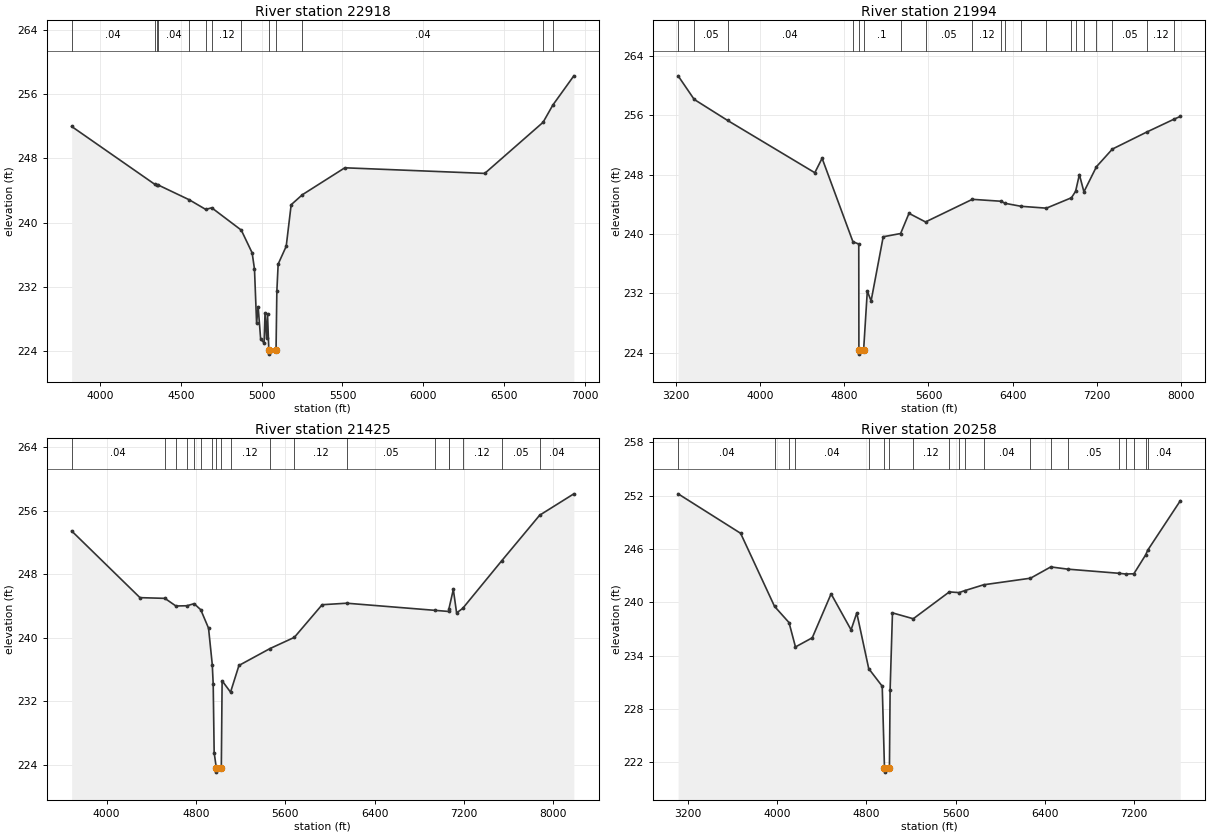
Type RM Length L Ch R = 1 ,22918   ,924,924,924
BEGIN DESCRIPTION:
Mapping XS 9b490311
END DESCRIPTION:
XS GIS Cut Line= 3
       2453438.6     13535801.26      2453744.16     13534697.05
      2452709.74     13533030.85
#Sta/Elev= 30
  3824.7  251.99  4338.2  244.78    4350  244.67  4361.4  244.67  4552.9  242.83
  4654.4  241.63  4691.2  241.84  4874.1  239.05  4941.4  236.21  4955.9  234.17
  4968.9  227.43  4978.5   229.5  4993.9  225.48  5015.1  224.95    5021  228.68
  5030.5   225.6  5036.4  228.56  5044.7  224.07  5045.7  223.57  5089.2  224.07
  5094.2   231.4  5102.3  234.81  5152.1  237.03  5182.8  242.22  5252.2  243.47
  5514.7  246.83  6380.3  246.13  6741.3  252.51  6801.6  254.66  6931.6  258.31
#Mann= 13 ,-1 , 0
  3824.7     .04       0  4338.2     .12       0    4350      .1       0
  4361.4     .04       0  4552.9      .1       0  4654.4     .04       0
  4691.2     .12       0  4874.1      .1       0  5044.7     .05       0
  5089.2      .1       0  5252.2     .04       0  6741.3     .05       0
  6801.6     .04       0
Bank Sta=5044.7,5089.2
XS Rating Curve= 0 ,0
Exp/Cntr=0.3,0.1

Type RM Length L Ch R = 1 ,21994   ,569,569,569
BEGIN DESCRIPTION:
Mapping XS a59c92d6
END DESCRIPTION:
XS GIS Cut Line= 3
      2454860.77     13536338.06      2454676.31      13534667.1
       2453010.1     13532055.23
#Sta/Elev= 30
  3217.3  261.34  3370.2  258.16  3688.4  255.32  4518.2  248.27  4587.5  250.22
    4881  238.96  4936.5  238.65  4937.8   224.3  4938.8   223.8  4982.4   224.3
  5017.7  232.29    5054  230.98  5169.1  239.63  5334.9  240.07  5414.5  242.79
  5571.9  241.63  6017.2  244.68  6293.2  244.42  6326.2  244.15  6481.1  243.74
    6722  243.49  6960.2  244.89    7000  245.76    7036  248.02  7079.3  245.69
  7198.4  249.08    7350  251.46  7674.8  253.74  7939.2  255.51  7996.5  255.86
#Mann= 20 ,-1 , 0
  3217.3     .04       0  3370.2     .05       0  3688.4     .04       0
    4881      .1       0  4937.8     .05       0  4982.4      .1       0
  5334.9     .12       0  5571.9     .05       0  6017.2     .12       0
  6293.2     .05       0  6326.2     .12       0  6481.1     .05       0
    6722     .12       0  6960.2     .05       0    7000    .013       0
  7079.3     .05       0  7198.4     .12       0    7350     .05       0
  7674.8     .12       0  7939.2     .04       0
Bank Sta=4937.8,4982.4
XS Rating Curve= 0 ,0
Exp/Cntr=0.3,0.1

Type RM Length L Ch R = 1 ,21425   ,1167,1167,1167
BEGIN DESCRIPTION:
Mapping XS 08285892
END DESCRIPTION:
XS GIS Cut Line= 3
      2455327.35     13535687.05      2455305.65     13534656.25
      2453293.31     13531830.74
#Sta/Elev= 30
  3686.1  253.43  4298.3  245.04  4521.6  244.95  4620.3  243.99  4719.4  244.02
  4783.2  244.28  4842.9  243.52  4912.7   241.2  4946.2  236.61  4954.5  234.14
  4963.1  225.55  4982.6  223.59  4983.6  223.09  5027.2  223.59  5034.4  234.58
  5109.8  233.15  5185.2  236.51  5464.2  238.64  5681.2  240.04  5930.7  244.15
  6150.9  244.34  6943.1  243.44  7064.9   243.3  7066.7  243.63  7106.1  246.07
  7135.6  243.12  7190.2  243.69  7541.6  249.71  7879.7  255.41    8186   258.1
#Mann= 19 ,-1 , 0
  3686.1     .04       0  4521.6     .12       0  4620.3     .05       0
  4719.4     .12       0  4783.2     .04       0  4842.9     .05       0
  4946.2      .1       0  4982.6     .05       0  5027.2      .1       0
  5109.8     .12       0  5464.2     .05       0  5681.2     .12       0
  6150.9     .05       0  6943.1     .12       0  7064.9    .013       0
  7066.7     .05       0  7190.2     .12       0  7541.6     .05       0
  7879.7     .04       0
Bank Sta=4982.6,5027.2
XS Rating Curve= 0 ,0
Exp/Cntr=0.3,0.1

Type RM Length L Ch R = 1 ,20258   ,909,909,909
BEGIN DESCRIPTION:
Mapping XS dde641bd
END DESCRIPTION:
XS GIS Cut Line= 3
      2456314.76     13535285.57      2455837.34     13533733.94
      2453762.31     13531739.84
#Sta/Elev= 30
  3113.7  252.19    3674  247.75    3978  239.53  4107.8  237.71  4165.6  234.97
  4316.1     236  4484.9  240.94    4664  236.89  4715.1  238.79  4822.2  232.53
  4943.2  230.55  4963.3  221.39  4964.3  220.89  5007.9  221.39  5013.9  230.13
    5035   238.8  5221.4  238.14  5544.7  241.16  5631.4  241.08  5682.5   241.3
  5852.1  241.96  6272.2   242.7  6453.9  243.97  6605.3  243.72  7067.6  243.25
  7126.5  243.17  7198.7   243.2  7304.3  245.32  7322.9  245.85    7615  251.41
#Mann= 20 ,-1 , 0
  3113.7     .04       0    3978     .05       0  4107.8     .12       0
  4165.6     .04       0  4822.2      .1       0  4963.3     .05       0
  5007.9      .1       0  5221.4     .12       0  5544.7     .05       0
  5631.4     .03       0  5682.5     .05       0  5852.1     .04       0
  6272.2     .05       0  6453.9    .013       0  6605.3     .05       0
  7067.6     .12       0  7126.5     .05       0  7198.7     .12       0
  7304.3     .05       0  7322.9     .04       0
Bank Sta=4963.3,5007.9
XS Rating Curve= 0 ,0
Exp/Cntr=0.3,0.1