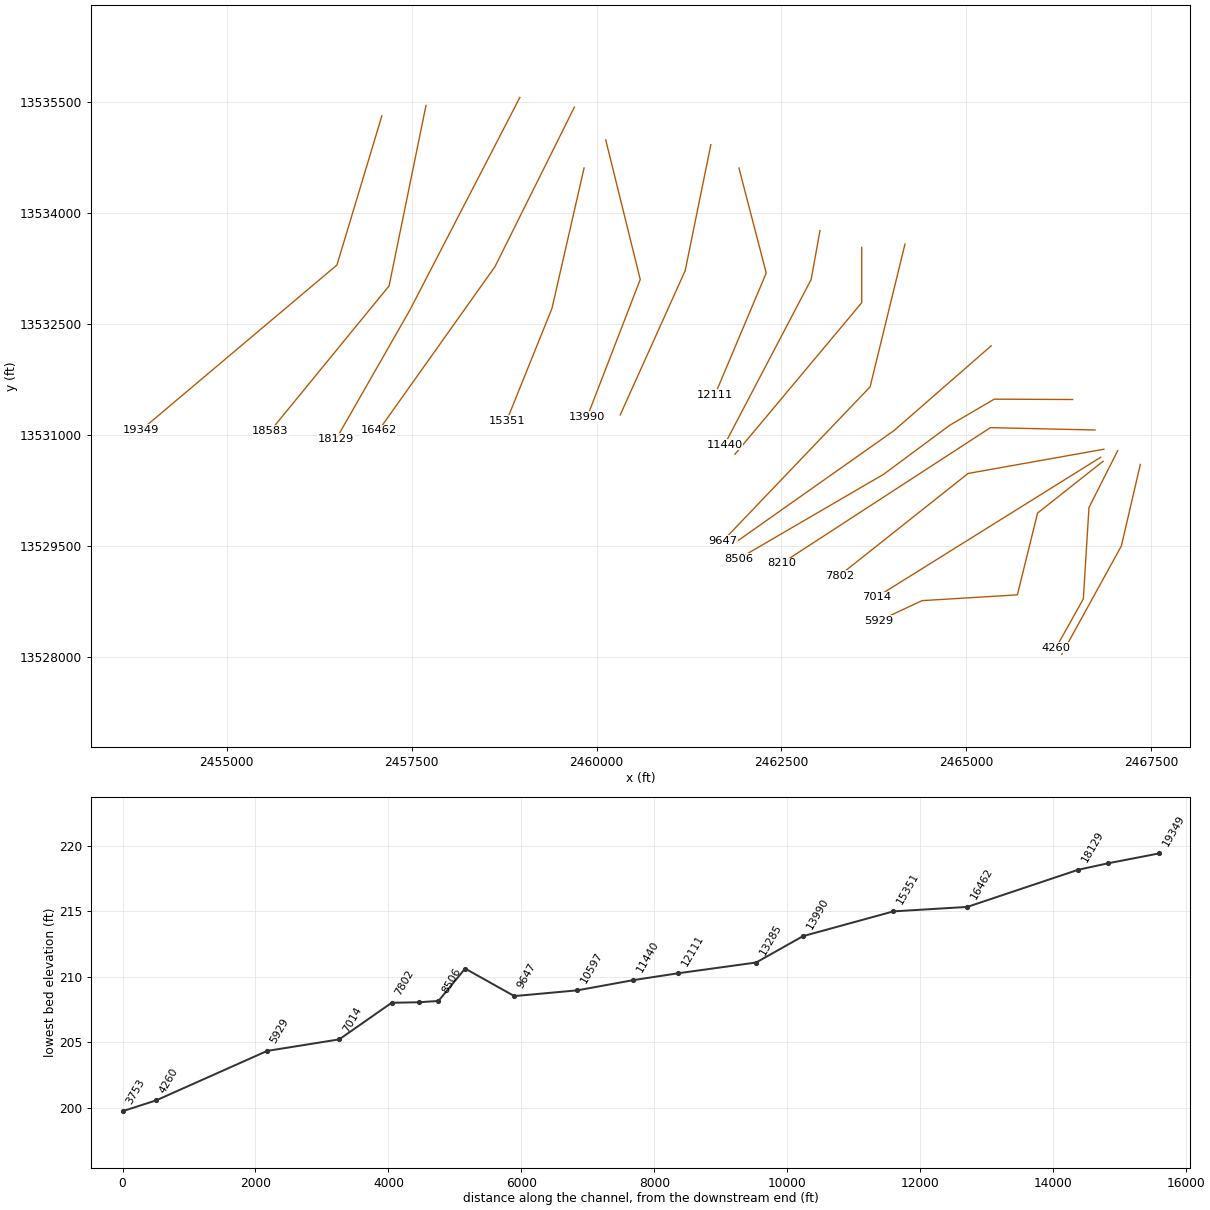
HEC-RAS study YORKTOWN CREEK.prj: YORKTOWN CREEK Base Level Engineering

--- YORKTOWN CREEK.g01 (geometry) --- (continued)

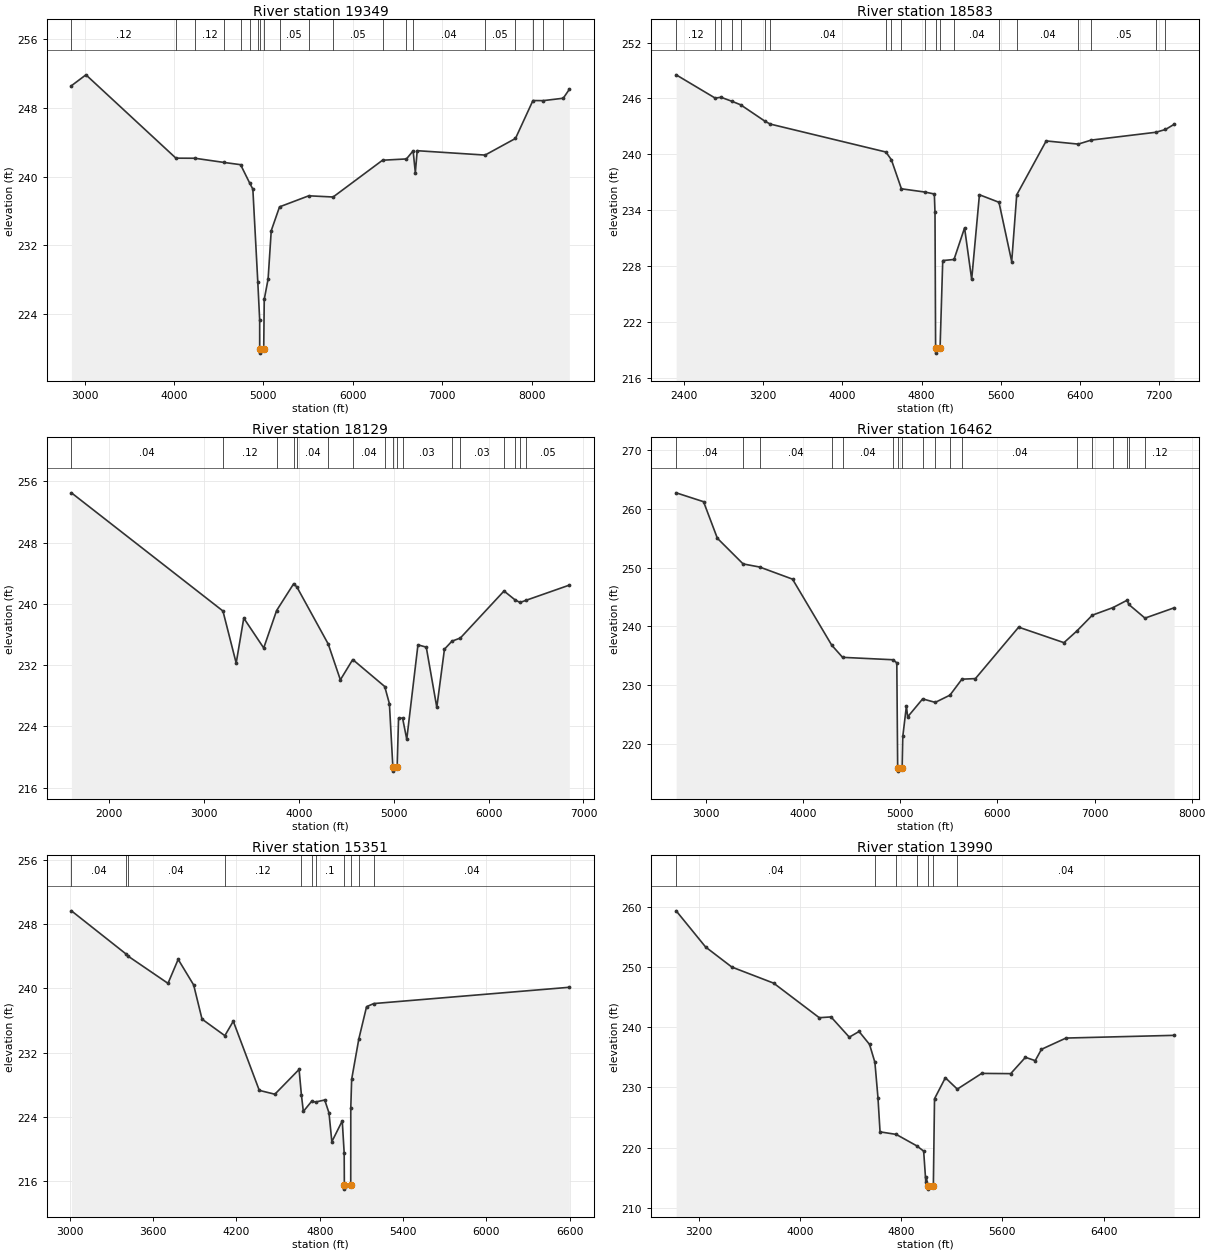
Type RM Length L Ch R = 1 ,19349   ,766,766,766
BEGIN DESCRIPTION:
Mapping XS 54e01c47
END DESCRIPTION:
XS GIS Cut Line= 3
        2457096.      13535318.1      2456488.38     13533299.91
      2453843.93     13531069.54
#Sta/Elev= 30
  2853.5  250.59  3015.8  251.86  4021.8  242.14  4234.1  242.13  4559.5  241.64
  4744.8  241.38  4848.6  239.19  4881.9  238.53  4937.5  227.64  4958.3  223.24
  4958.4   219.9  4959.4   219.4  5003.3   219.9  5009.5  225.68  5052.4  228.04
  5087.5  233.68  5180.2  236.46    5507  237.75  5779.4  237.61  6331.9   241.9
  6599.2  242.05  6673.9  242.99  6698.6  240.44  6719.4  243.01  7478.4   242.5
  7818.4  244.44  8013.5  248.86  8128.2  248.85  8352.2  249.13  8420.6  250.17
#Mann= 20 ,-1 , 0
  2853.5     .12       0  4021.8     .05       0  4234.1     .12       0
  4559.5     .04       0  4744.8     .05       0  4848.6     .12       0
  4937.5      .1       0  4958.4     .05       0  5003.3      .1       0
  5180.2     .05       0    5507     .12       0  5779.4     .05       0
  6331.9     .04       0  6599.2    .013       0  6673.9     .04       0
  7478.4     .05       0  7818.4     .04       0  8013.5     .05       0
  8128.2     .03       0  8352.2     .05       0
Bank Sta=4958.4,5003.3
XS Rating Curve= 0 ,0
Exp/Cntr=0.3,0.1

Type RM Length L Ch R = 1 ,18583   ,454,454,454
BEGIN DESCRIPTION:
Mapping XS bb70c07b
END DESCRIPTION:
XS GIS Cut Line= 3
       2457692.8      13535459.2      2457193.67     13533017.79
      2455588.88     13531055.18
#Sta/Elev= 30
  2322.3  248.54  2716.5  246.04  2774.8  246.13  2887.3  245.69  2973.7  245.32
    3220  243.55  3272.6  243.25  4439.7  240.25  4495.3  239.42  4596.5   236.3
  4833.8  235.95  4929.1  235.74  4935.6  233.76  4941.8  219.15  4942.8  218.65
  4986.7  219.15  5013.8  228.59  5127.7  228.71  5234.2   232.1    5306  226.57
  5384.2  235.66  5581.6  234.85  5710.1  228.48  5760.8  235.65  6058.3  241.44
  6382.1   241.1  6512.9  241.53  7165.3  242.37  7262.7  242.67  7349.4  243.22
#Mann= 20 ,-1 , 0
  2322.3     .12       0  2716.5     .05       0  2774.8     .04       0
  2887.3     .05       0  2973.7     .04       0    3220     .03       0
  3272.6     .04       0  4439.7     .05       0  4495.3     .04       0
  4596.5     .12       0  4833.8     .12       0  4941.8     .05       0
  4986.7      .1       0  5127.7     .04       0  5581.6     .12       0
  5760.8     .04       0  6382.1    .013       0  6512.9     .05       0
  7165.3     .12       0  7262.7     .12       0
Bank Sta=4941.8,4986.7
XS Rating Curve= 0 ,0
Exp/Cntr=0.3,0.1

Type RM Length L Ch R = 1 ,18129   ,1667,1667,1667
BEGIN DESCRIPTION:
Mapping XS dbd5c91b
END DESCRIPTION:
XS GIS Cut Line= 3
      2458962.34     13535567.71      2457475.79     13532692.27
      2456477.54     13530945.34
#Sta/Elev= 30
  1602.7  254.49  3199.8  239.06  3339.4  232.26  3419.5  238.13  3629.7  234.23
  3765.7  239.12  3946.1  242.63  3980.1  242.18  4309.7  234.75  4437.8  230.07
  4568.2  232.72  4905.3   229.2  4954.8  226.95  4991.4  218.65  4992.4  218.15
  5036.3  218.65  5051.2  225.07  5093.8  225.07  5137.6  222.31  5255.7  234.64
  5343.3  234.34  5454.4  226.48    5535  234.07  5614.1  235.12  5702.7  235.53
    6163  241.67  6278.4  240.52    6332  240.17  6393.9  240.45  6851.7  242.44
#Mann= 17 ,-1 , 0
  1602.7     .04       0  3199.8     .12       0  3765.7     .04       0
  3946.1     .05       0  3980.1     .04       0  4309.7     .05       0
  4568.2     .04       0  4905.3      .1       0  4991.4     .05       0
  5036.3      .1       0  5093.8     .03       0  5614.1     .05       0
  5702.7     .03       0    6163    .013       0  6278.4     .05       0
    6332     .12       0  6393.9     .05       0
Bank Sta=4991.4,5036.3
XS Rating Curve= 0 ,0
Exp/Cntr=0.3,0.1

Type RM Length L Ch R = 1 ,16462   ,1111,1111,1111
BEGIN DESCRIPTION:
Mapping XS 51929ac9
END DESCRIPTION:
XS GIS Cut Line= 3
      2459700.17     13535437.48      2458625.96     13533278.21
      2457054.18     13531064.71
#Sta/Elev= 30
  2692.6  262.72  2974.6  261.21  3116.9  254.98    3382  250.61  3552.8  250.08
  3890.5  248.02  4294.5  236.77    4406   234.7    4925  234.29  4964.4  233.76
  4973.3  215.82  4974.3  215.32  5019.2  215.82    5026  221.22  5063.2  226.39
  5076.4  224.56  5230.4  227.62  5360.5  227.03  5511.6  228.26  5634.8  230.98
  5773.8  231.08  6219.1  239.84  6685.3   237.2  6817.6  239.18  6977.3  241.88
  7189.8  243.17    7335  244.42    7353  243.71  7519.6  241.38  7819.1  243.13
#Mann= 18 ,-1 , 0
  2692.6     .04       0    3382     .03       0  3552.8     .04       0
  4294.5     .03       0    4406     .04       0    4925     .12       0
  4973.3     .05       0  5019.2     .12       0  5230.4     .12       0
  5360.5     .04       0  5511.6     .12       0  5634.8     .04       0
  6817.6    .013       0  6977.3     .04       0  7189.8    .013       0
    7335     .04       0    7353    .013       0  7519.6     .12       0
Bank Sta=4973.3,5019.2
XS Rating Curve= 0 ,0
Exp/Cntr=0.3,0.1

Type RM Length L Ch R = 1 ,15351   ,1361,1361,1361
BEGIN DESCRIPTION:
Mapping XS b0e82cd6
END DESCRIPTION:
XS GIS Cut Line= 3
       2459830.4     13534612.87      2459396.36     13532713.97
      2458784.54     13531195.35
#Sta/Elev= 30
  3012.5  249.67  3407.8  244.26    3418  244.05  3707.8  240.63    3781  243.62
  3892.5  240.43  3952.8  236.17  4117.1  234.11  4177.8  235.91  4365.1  227.29
  4477.2  226.81  4651.6   229.9  4668.1  226.77  4682.3  224.66    4742  225.93
  4769.9  225.84  4836.2  226.09    4867  224.48  4887.5  220.89  4962.5  223.49
  4976.4  219.46  4977.6  215.48  4978.6  214.98  5023.5  215.48  5023.9   225.1
  5030.1  228.66  5081.7  233.69  5137.5  237.72  5189.2  238.11  6597.6  240.14
#Mann= 11 ,-1 , 0
  3012.5     .04       0  3407.8     .03       0    3418     .04       0
  4117.1     .12       0  4668.1     .04       0    4742     .12       0
  4769.9      .1       0  4977.6     .05       0  5023.5      .1       0
  5081.7     .12       0  5189.2     .04       0
Bank Sta=4977.6,5023.5
XS Rating Curve= 0 ,0
Exp/Cntr=0.3,0.1

Type RM Length L Ch R = 1 ,13990   ,705,705,705
BEGIN DESCRIPTION:
Mapping XS e363f939
END DESCRIPTION:
XS GIS Cut Line= 3
      2460123.36     13534992.63      2460589.94      13533104.6
      2459873.98      13531249.6
#Sta/Elev= 30
  3023.4  259.31  3256.1   253.3  3463.3  249.97  3793.5   247.3    4154  241.56
  4246.8  241.69    4391  238.33  4468.3  239.27  4551.1  237.12  4593.3  234.15
  4617.6  228.27    4634   222.6  4761.6  222.18  4922.2   220.3  4978.5  219.41
  4995.2  214.35  5000.6  215.08  5009.1  213.59  5010.1  213.09  5055.1  213.59
  5064.3   228.1    5150  231.59  5244.2   229.7  5437.1  232.31  5666.1  232.27
  5782.4  234.98  5859.8  234.43    5909  236.31  6102.7  238.18  6956.6  238.63
#Mann= 7 ,-1 , 0
  3023.4     .04       0  4593.3      .1       0  4761.6     .12       0
  4922.2      .1       0  5009.1     .05       0  5055.1      .1       0
  5244.2     .04       0
Bank Sta=5009.1,5055.1
XS Rating Curve= 0 ,0
Exp/Cntr=0.3,0.1

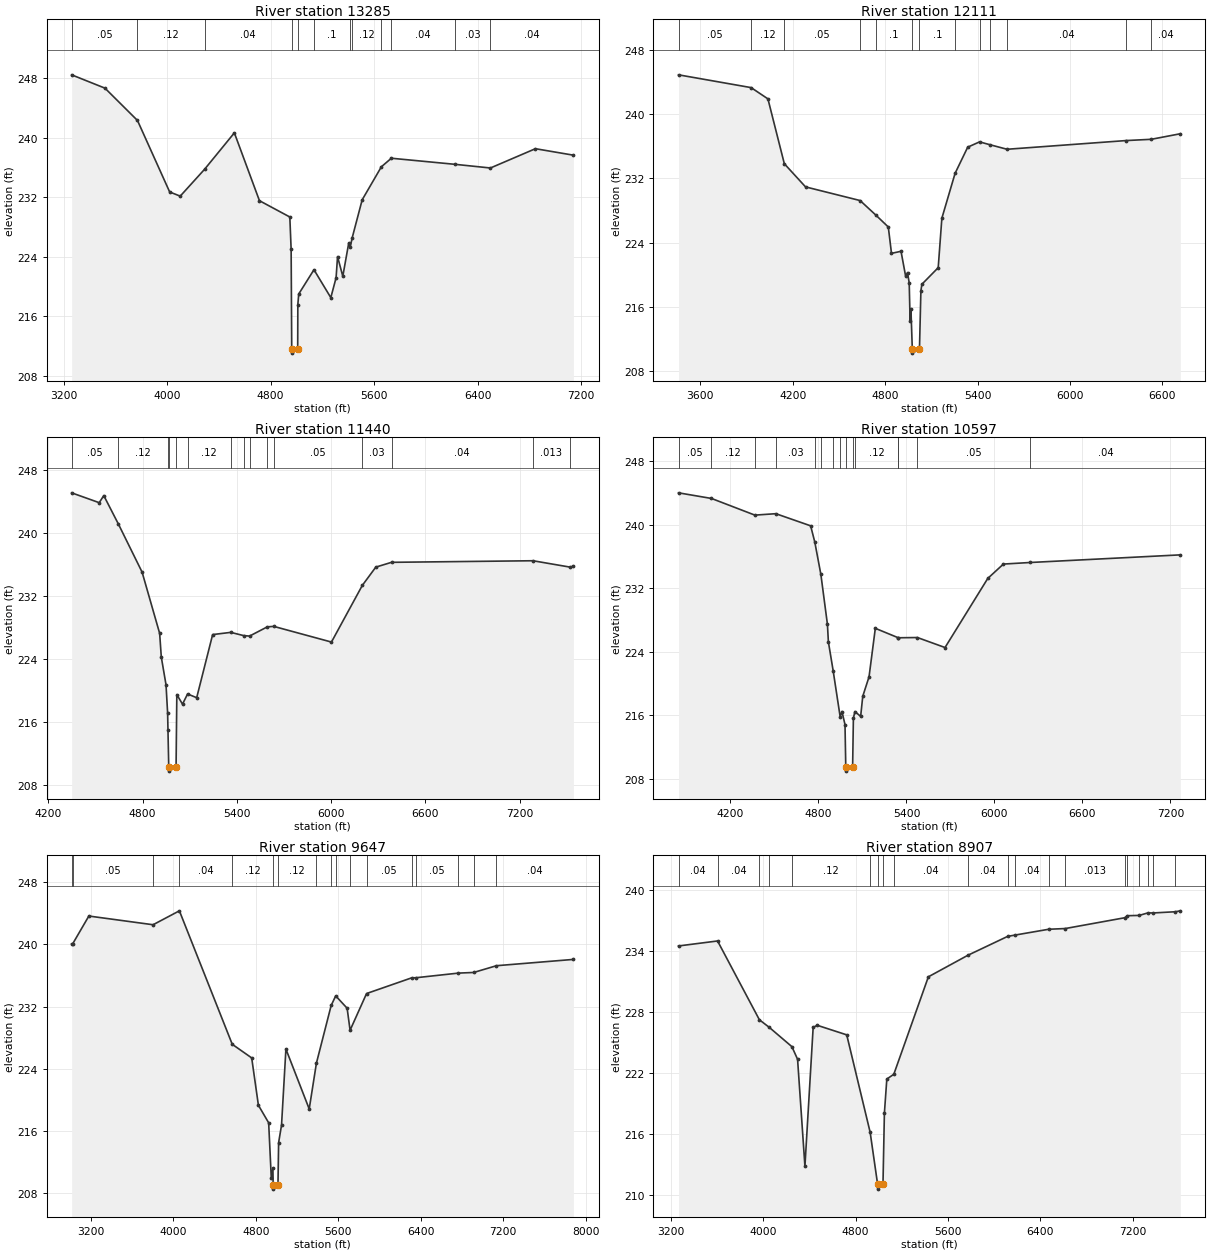
Type RM Length L Ch R = 1 ,13285   ,1174,1174,1174
BEGIN DESCRIPTION:
Mapping XS d28f331b
END DESCRIPTION:
XS GIS Cut Line= 3
       2461544.8     13534927.49      2461197.58     13533223.96
      2460319.34     13531272.32
#Sta/Elev= 30
  3262.8  248.45  3520.5  246.66  3771.8  242.32  4020.6  232.72  4102.2  232.16
  4290.1  235.76  4520.6  240.66  4714.5  231.55  4949.3  229.36  4959.5     225
  4964.1  211.58  4965.1  211.08  5010.2  211.58  5011.2  217.59  5018.2  219.02
  5135.9  222.28  5266.2  218.53    5307  221.21  5318.2  224.04  5358.8   221.4
  5405.1   225.9  5416.4  225.33  5431.6  226.58  5508.7  231.67  5656.9   236.1
  5734.1  237.25  6227.7  236.43  6499.9  235.94  6847.7  238.53  7141.5  237.66
#Mann= 12 ,-1 , 0
  3262.8     .05       0  3771.8     .12       0  4290.1     .04       0
  4964.1     .05       0  5010.2     .04       0  5135.9      .1       0
  5416.4     .05       0  5431.6     .12       0  5656.9     .05       0
  5734.1     .04       0  6227.7     .03       0  6499.9     .04       0
Bank Sta=4964.1,5010.2
XS Rating Curve= 0 ,0
Exp/Cntr=0.3,0.1

Type RM Length L Ch R = 1 ,12111   ,671,671,671
BEGIN DESCRIPTION:
Mapping XS 73cab7c9
END DESCRIPTION:
XS GIS Cut Line= 3
      2461924.58     13534612.83       2462293.5      13533191.4
      2461599.54     13531543.26
#Sta/Elev= 30
  3459.2  244.88  3930.3  243.29  4039.4  241.89  4145.9  233.82  4283.5  230.94
  4637.8  229.24  4738.8  227.45  4820.7  225.95  4841.4  222.67  4903.3  222.93
    4933  219.85  4945.5  220.28  4956.4  218.99  4962.1  214.29  4967.6  215.72
  4976.5  210.76  4977.5  210.26    5023  210.76  5032.3  218.03  5038.8  218.83
  5144.6  220.89  5168.3  227.04  5254.2  232.63  5336.1  235.88    5413  236.54
  5483.3  236.17  5591.5  235.62  6362.3   236.7  6527.7  236.86    6716  237.55
#Mann= 13 ,-1 , 0
  3459.2     .05       0  3930.3     .12       0  4145.9     .05       0
  4637.8     .12       0  4738.8      .1       0  4976.5     .05       0
    5023      .1       0  5254.2     .12       0    5413     .05       0
  5483.3     .12       0  5591.5     .04       0  6362.3     .05       0
  6527.7     .04       0
Bank Sta=4976.5,5023
XS Rating Curve= 0 ,0
Exp/Cntr=0.3,0.1

Type RM Length L Ch R = 1 ,11440   ,843,843,843
BEGIN DESCRIPTION:
Mapping XS f2011c2a
END DESCRIPTION:
XS GIS Cut Line= 3
       2463020.5     13533766.49      2462901.14      13533104.6
      2461729.81      13530870.4
#Sta/Elev= 30
  4347.7  245.06  4523.3  243.81  4552.4  244.71  4645.9  241.08  4796.3     235
  4908.1  227.23  4918.7  224.21  4948.7   220.7  4958.9  217.12  4961.2  214.92
  4966.1  210.24  4967.1  209.74  5012.7  210.24  5017.5  219.45  5053.7  218.24
  5085.9  219.53    5144  219.06  5245.6  227.07    5361  227.35  5443.3  226.94
  5480.7  226.88  5593.7  228.05  5634.5  228.11  6002.1  226.12  6198.6  233.31
  6284.4  235.63  6384.7  236.24  7285.5  236.44  7518.9  235.64  7542.9  235.73
#Mann= 15 ,-1 , 0
  4347.7     .05       0  4645.9     .12       0  4961.2      .1       0
  4966.1     .05       0  5012.7      .1       0  5085.9     .12       0
    5361     .05       0  5443.3     .12       0  5480.7     .05       0
  5593.7     .12       0  5634.5     .05       0  6198.6     .03       0
  6384.7     .04       0  7285.5    .013       0  7518.9     .05       0
Bank Sta=4966.1,5012.7
XS Rating Curve= 0 ,0
Exp/Cntr=0.3,0.1

Type RM Length L Ch R = 1 ,10597   ,950,950,950
BEGIN DESCRIPTION:
Mapping XS d1fb4e0b
END DESCRIPTION:
XS GIS Cut Line= 3
      2463584.73     13533538.64      2463584.73     13532789.93
      2461870.71     13530739.61
#Sta/Elev= 30
  3845.9  244.04  4070.7  243.33  4366.4  241.23  4509.4  241.41  4746.6  239.88
  4774.9  237.84  4816.4  233.75  4861.1  227.46  4867.6  225.25    4900  221.63
    4948   215.8    4960  216.47  4980.9  214.83  4986.2  209.46  4987.2  208.96
  5032.8  209.46  5038.1  215.62  5048.3  216.47  5087.6  215.86  5101.9  218.39
  5144.8  220.85  5187.6  226.96  5342.9  225.78  5344.8  225.77  5474.5   225.8
  5662.8  224.54  5954.2  233.25  6060.8  235.06  6245.1  235.26    7267  236.22
#Mann= 15 ,-1 , 0
  3845.9     .05       0  4070.7     .12       0  4366.4     .05       0
  4509.4     .03       0  4774.9     .12       0  4816.4     .05       0
    4900     .12       0    4948     .05       0  4986.2     .05       0
  5032.8     .05       0  5048.3     .12       0  5342.9     .05       0
  5344.8     .12       0  5474.5     .05       0  6245.1     .04       0
Bank Sta=4986.2,5032.8
XS Rating Curve= 0 ,0
Exp/Cntr=0.3,0.1

Type RM Length L Ch R = 1 ,9647    ,740,740,740
BEGIN DESCRIPTION:
Mapping XS 71e68db1
END DESCRIPTION:
XS GIS Cut Line= 3
      2464169.62     13533582.47      2463698.01     13531651.53
      2461707.57     13529567.29
#Sta/Elev= 30
  3012.3  240.08  3024.1  240.11  3179.4  243.65  3802.6  242.53    4058  244.32
  4571.1  227.15  4759.7   225.4  4824.8  219.31  4924.4  217.05  4949.8  209.95
  4965.5  211.18  4968.1  209.02  4969.1  208.52  5014.7  209.02    5021   214.5
  5049.3  216.75  5091.8  226.54  5317.9  218.83  5387.9  224.73  5531.1  232.15
    5575  233.38  5685.9  231.79  5714.6  228.96  5874.5  233.68  6312.4   235.7
  6351.3  235.71  6766.4  236.31  6913.7  236.39    7135  237.26    7882  238.07
#Mann= 17 ,-1 , 0
  3012.3     .12       0  3024.1     .05       0  3802.6     .03       0
    4058     .04       0  4571.1     .12       0  4968.1     .05       0
  5014.7     .12       0  5387.9     .05       0  5531.1     .12       0
    5575     .05       0  5714.6     .12       0  5874.5     .05       0
  6312.4     .04       0  6351.3     .05       0  6766.4    .013       0
  6913.7     .05       0    7135     .04       0
Bank Sta=4968.1,5014.7
XS Rating Curve= 0 ,0
Exp/Cntr=0.3,0.1

Type RM Length L Ch R = 1 ,8907    ,401,401,401
BEGIN DESCRIPTION:
Mapping XS 22b1a173
END DESCRIPTION:
XS GIS Cut Line= 3
      2465336.27     13532207.47      2464023.79     13531061.66
       2461899.4     13529562.09
#Sta/Elev= 30
  3267.9   234.5  3605.7  234.99  3967.8  227.25  4052.7  226.51  4249.1  224.61
  4298.2  223.37  4361.8  212.86    4433   226.5  4468.1  226.71  4723.5  225.77
  4926.3   216.2  4990.5  211.12  4991.5  210.62  5037.3  211.12  5049.6  218.09
  5070.5  221.43    5131   221.9  5430.1  231.47  5772.8  233.59  6116.1  235.44
  6175.8  235.56  6471.6  236.14  6614.5  236.21    7129  237.27  7152.5  237.47
  7254.8   237.5  7330.6  237.75  7372.8  237.74  7568.4  237.86  7610.5  237.95
#Mann= 20 ,-1 , 0
  3267.9     .04       0  3605.7     .04       0  3967.8     .12       0
  4052.7     .04       0  4249.1     .12       0  4926.3      .1       0
  4990.5     .05       0  5037.3      .1       0    5131     .04       0
  5772.8     .04       0  6116.1     .05       0  6175.8     .04       0
  6471.6     .05       0  6614.5    .013       0    7129     .04       0
  7152.5    .013       0  7254.8     .04       0  7330.6    .013       0
  7372.8     .04       0  7568.4    .013       0
Bank Sta=4990.5,5037.3
XS Rating Curve= 0 ,0
Exp/Cntr=0.3,0.1

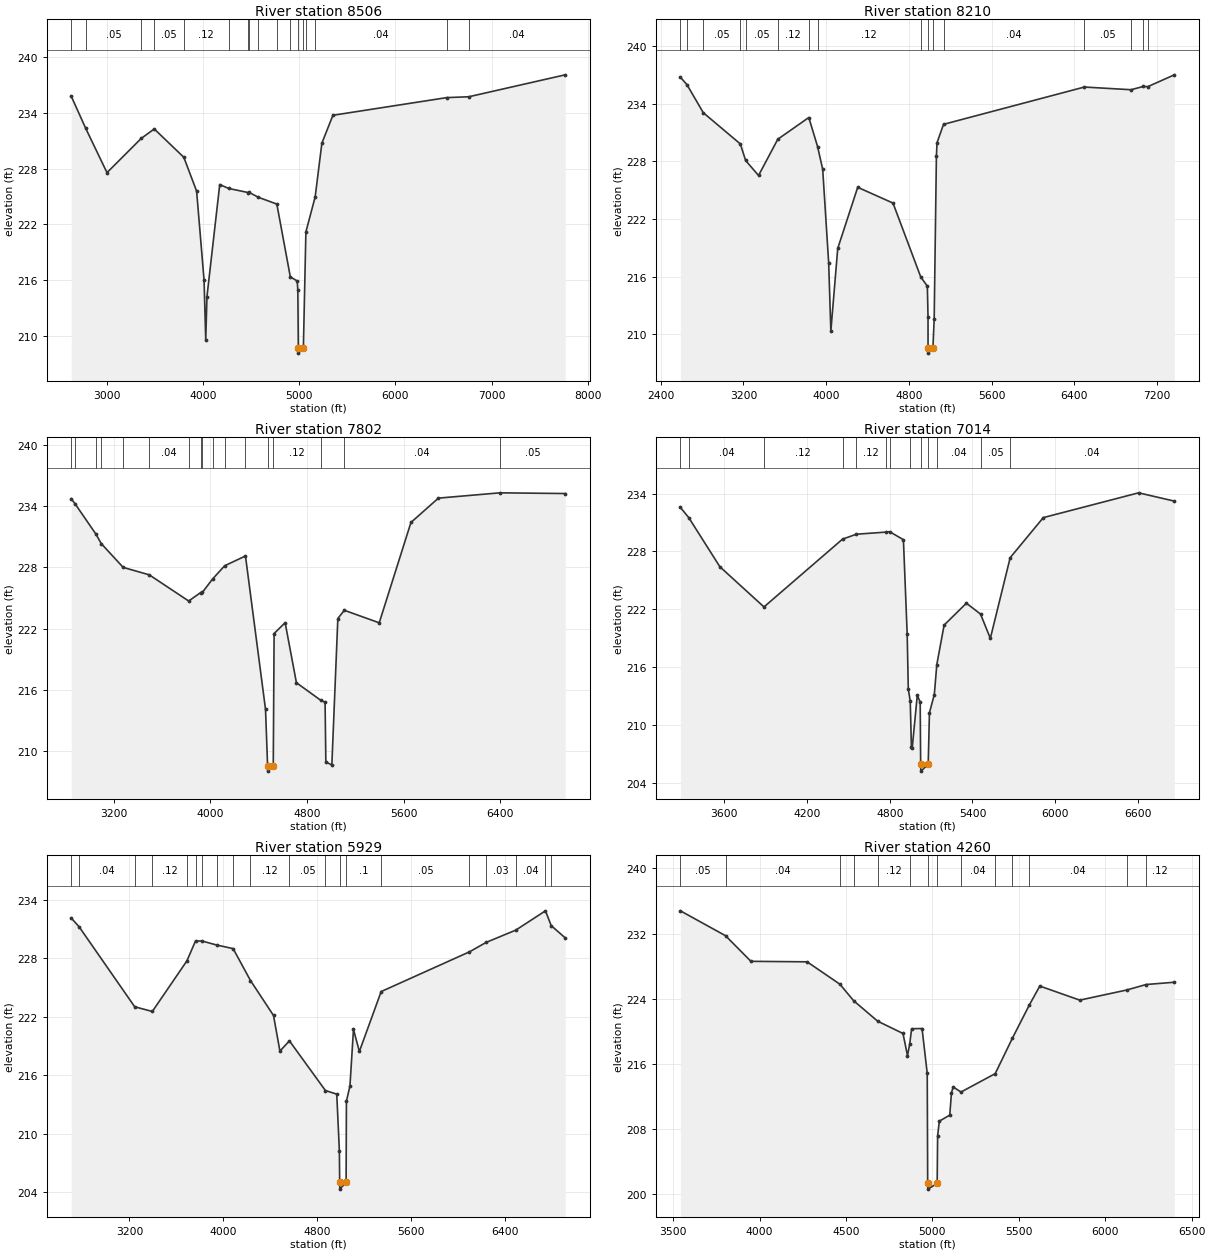
Type RM Length L Ch R = 1 ,8506    ,296,296,296
BEGIN DESCRIPTION:
Mapping XS bec9f888
END DESCRIPTION:
XS GIS Cut Line= 5
      2466436.52     13531480.41      2465377.01     13531485.08
      2464772.84     13531130.91      2463882.22     13530469.46
       2461925.2     13529329.01
#Sta/Elev= 30
  2629.9  235.78  2780.9  232.31  3001.4  227.56  3357.2  231.24  3492.8  232.26
  3800.1  229.21  3933.1  225.57  4010.5  215.99  4027.9  209.55  4040.5  214.22
  4173.4  226.28  4266.6  225.86  4469.2  225.42  4477.6  225.45  4574.6  224.91
  4766.9  224.18  4907.1  216.35  4978.5  215.91    4985  214.95  4990.6  208.65
  4991.6  208.15  5037.4  208.65  5043.2  208.95  5068.9  221.18  5165.4  224.96
  5235.1  230.73  5349.8  233.73  6533.4  235.63  6761.1  235.72  7764.2  238.08
#Mann= 17 ,-1 , 0
  2629.9     .03       0  2780.9     .05       0  3357.2     .12       0
  3492.8     .05       0  3800.1     .12       0  4266.6     .05       0
  4469.2     .12       0  4477.6     .05       0  4574.6     .12       0
  4766.9     .05       0  4907.1     .12       0  4990.6     .05       0
  5037.4     .12       0  5068.9     .05       0  5165.4     .04       0
  6533.4     .05       0  6761.1     .04       0
Bank Sta=4990.6,5037.4
XS Rating Curve= 0 ,0
Exp/Cntr=0.3,0.1

Type RM Length L Ch R = 1 ,8210    ,408,408,408
BEGIN DESCRIPTION:
Mapping XS b045a84d
END DESCRIPTION:
XS GIS Cut Line= 3
      2466740.34     13531068.08      2465324.92     13531099.66
      2462508.64     13529267.26
#Sta/Elev= 30
  2590.7  236.76    2655  235.96  2811.8  233.06  3170.2  229.81  3221.3  228.09
  3346.2  226.53  3532.4   230.3  3832.2  232.56  3916.8  229.54  3966.4  227.18
  4024.2  217.45  4045.3  210.34  4111.8  218.94  4304.9   225.3  4646.1  223.66
  4914.2  215.98  4978.2  215.01  4984.7  211.85    4985  208.55    4986  208.05
  5031.9  208.55  5044.3  211.59  5065.8  228.54  5071.7  229.94  5134.7  231.85
  6496.6  235.73    6947  235.45  7066.4  235.79  7109.4  235.77  7366.4     237
#Mann= 16 ,-1 , 0
  2590.7     .04       0    2655     .03       0  2811.8     .05       0
  3170.2     .12       0  3221.3     .05       0  3532.4     .12       0
  3832.2     .05       0  3916.8     .12       0  4914.2     .05       0
    4985     .05       0  5031.9     .05       0  5134.7     .04       0
  6496.6     .05       0    6947     .04       0  7066.4     .05       0
  7109.4     .04       0
Bank Sta=4985,5031.9
XS Rating Curve= 0 ,0
Exp/Cntr=0.3,0.1

Type RM Length L Ch R = 1 ,7802    ,788,788,788
BEGIN DESCRIPTION:
Mapping XS 6e4b06b0
END DESCRIPTION:
XS GIS Cut Line= 3
      2466859.64     13530807.66      2465022.84     13530479.87
      2463279.03     13529095.23
#Sta/Elev= 30
  2847.2  234.76    2882   234.2  3051.5  231.28  3095.7  230.35  3277.5  228.01
  3493.5  227.28  3820.2  224.71  3919.6  225.54  3934.3  225.57    4019  226.88
  4118.3  228.17  4290.7  229.13  4456.9  214.07  4474.1  208.51  4475.1  208.01
    4521  208.51    4528  221.52  4619.4  222.58  4712.7  216.69  4913.5  214.97
  4950.3  214.78  4956.6  208.92  5006.3  208.61    5056  222.99  5109.6   223.8
  5398.9  222.57  5661.6  232.42  5889.1  234.81  6398.8  235.33  6939.7  235.26
#Mann= 17 ,-1 , 0
  2847.2     .05       0    2882     .04       0  3051.5     .05       0
  3095.7     .04       0  3277.5     .05       0  3493.5     .04       0
  3820.2     .05       0  3919.6     .04       0  3934.3     .05       0
    4019     .03       0  4118.3     .04       0  4290.7     .12       0
  4474.1     .05       0    4521     .12       0  4913.5      .1       0
  5109.6     .04       0  6398.8     .05       0
Bank Sta=4474.1,4521
XS Rating Curve= 0 ,0
Exp/Cntr=0.3,0.1

Type RM Length L Ch R = 1 ,7014    ,1085,1085,1085
BEGIN DESCRIPTION:
Mapping XS b9bda6d0
END DESCRIPTION:
XS GIS Cut Line= 2
       2466816.3     13530699.18        2463779.     13528803.38
#Sta/Elev= 30
  3282.9  232.56  3343.4   231.5  3568.9  226.41  3888.7  222.24  4458.1  229.27
  4558.7  229.78    4775     230  4799.8  230.04  4899.4  229.21  4926.6  219.46
  4934.8  213.72  4948.9  212.47  4957.3  207.72  4963.2  207.62  4999.8  213.07
    5021  212.38  5024.3  205.92  5025.5  205.22  5079.1  205.92    5088  211.27
  5123.4  213.16  5141.4  216.26  5194.4  220.36    5356  222.63  5458.4   221.5
  5529.4  218.98  5673.3  227.35  5913.2   231.5    6604  234.07  6863.3  233.21
#Mann= 13 ,-1 , 0
  3282.9     .05       0  3343.4     .04       0  3888.7     .12       0
  4458.1     .05       0  4558.7     .12       0    4775     .05       0
  4799.8     .12       0  4948.9      .1       0  5024.3     .05       0
  5079.1      .1       0  5141.4     .04       0  5458.4     .05       0
  5673.3     .04       0
Bank Sta=5024.3,5079.1
XS Rating Curve= 0 ,0
Exp/Cntr=0.3,0.1

Type RM Length L Ch R = 1 ,5929    ,1669,1669,1669
BEGIN DESCRIPTION:
Mapping XS 38f0d812
END DESCRIPTION:
XS GIS Cut Line= 5
       2466848.8     13530644.88      2465962.79     13529944.09
      2465689.35     13528837.32      2464400.29      13528759.2
      2463814.48     13528485.07
#Sta/Elev= 30
  2704.6  232.11    2772  231.21  3245.3  223.02  3395.3  222.54  3690.3  227.73
  3763.2  229.76  3818.2  229.76  3942.5  229.35  4083.5  228.98  4231.5  225.71
  4427.6  222.13  4482.3  218.48  4563.1  219.53  4869.9  214.44  4966.4  214.07
  4988.7  208.29  4991.3  205.04  4992.5  204.34  5046.1  205.04  5048.8  213.35
  5078.8   214.9  5108.9   220.7    5159  218.44  5344.8  224.58  6097.1  228.65
  6239.9  229.62    6491  230.87  6744.3  232.85  6793.4  231.33  6912.5  230.08
#Mann= 20 ,-1 , 0
  2704.6     .05       0    2772     .04       0  3245.3     .05       0
  3395.3     .12       0  3690.3     .05       0  3763.2     .12       0
  3818.2     .05       0  3942.5     .12       0  4083.5     .05       0
  4231.5     .12       0  4563.1     .05       0  4869.9     .12       0
  4991.3     .05       0  5046.1      .1       0  5344.8     .05       0
  6097.1     .04       0  6239.9     .03       0    6491     .04       0
  6744.3     .03       0  6793.4     .04       0
Bank Sta=4991.3,5046.1
XS Rating Curve= 0 ,0
Exp/Cntr=0.3,0.1

Type RM Length L Ch R = 1 ,4260    ,507,507,507
BEGIN DESCRIPTION:
Mapping XS 5d86d4bb
END DESCRIPTION:
XS GIS Cut Line= 4
      2467046.72     13530789.39      2466657.85      13530018.6
      2466581.46     13528782.49      2466212.69     13528122.65
#Sta/Elev= 30
  3542.3  234.79  3803.4  231.73  3950.4  228.58  4275.3  228.52  4464.9  225.77
  4544.4  223.74  4683.6  221.22    4830  219.71  4856.1  216.99  4868.8   218.4
  4880.1  220.29  4940.3  220.32  4970.3   214.8  4972.9  201.27  4974.1  200.57
  5027.8  201.27  5030.4  207.14  5040.4  208.93  5100.6  209.67  5110.6  212.44
  5120.6  213.13  5165.6  212.51  5363.5  214.77  5462.5  219.11  5561.4  223.23
  5621.5  225.54  5852.6  223.81  6123.5  225.05  6236.8  225.73    6400  226.01
#Mann= 14 ,-1 , 0
  3542.3     .05       0  3803.4     .04       0  4464.9     .05       0
  4544.4     .04       0  4683.6     .12       0  4868.8      .1       0
  4972.9     .05       0  5027.8      .1       0  5165.6     .04       0
  5363.5     .12       0  5462.5     .05       0  5561.4     .04       0
  6123.5     .05       0  6236.8     .12       0
Bank Sta=4972.9,5027.8
XS Rating Curve= 0 ,0
Exp/Cntr=0.3,0.1

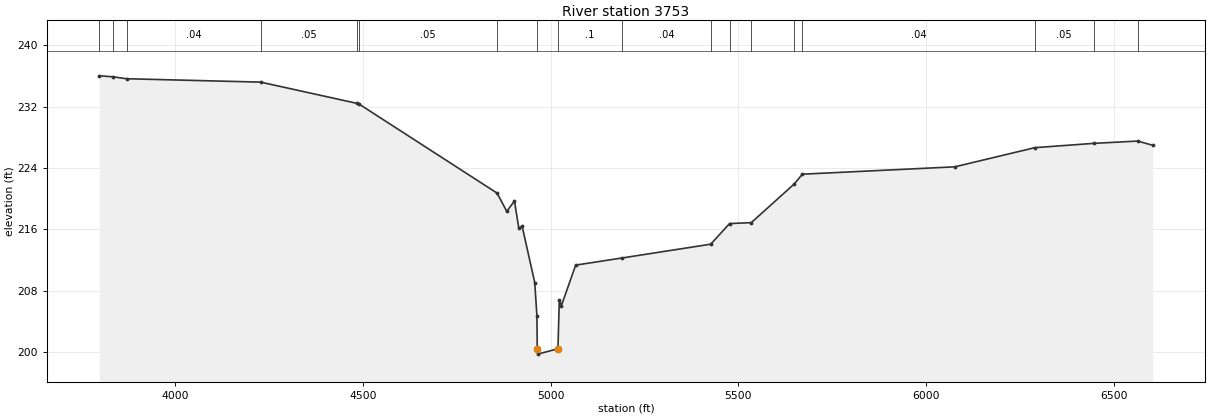
Type RM Length L Ch R = 1 ,3753    ,0,0,0
BEGIN DESCRIPTION:
Mapping XS 8ef51f55
END DESCRIPTION:
XS GIS Cut Line= 3
       2467352.3     13530601.97      2467095.35     13529497.77
      2466289.54     13528033.22
#Sta/Elev= 30
  3797.9  236.04  3833.6  235.92  3870.8  235.66  4227.6  235.22  4485.1  232.44
  4490.1  232.35  4857.4  220.74  4883.1  218.36  4903.6  219.71  4915.1  216.19
  4924.2  216.39  4957.6  209.08  4963.4  204.75  4964.3  200.44  4965.5  199.74
  5019.4  200.44    5023  206.78  5028.7  206.08  5066.6  211.35  5191.2  212.29
  5426.2  214.08  5476.4  216.77  5534.2  216.89  5648.5  221.93  5670.3  223.21
  6076.1  224.17  6289.3  226.67  6446.1  227.23    6563  227.53  6603.2  226.98
#Mann= 18 ,-1 , 0
  3797.9     .04       0  3833.6     .05       0  3870.8     .04       0
  4227.6     .05       0  4485.1     .04       0  4490.1     .05       0
  4857.4      .1       0  4964.3     .05       0  5019.4      .1       0
  5191.2     .04       0  5426.2     .03       0  5476.4     .04       0
  5534.2     .03       0  5648.5     .05       0  5670.3     .04       0
  6289.3     .05       0  6446.1     .12       0    6563    .013       0
Bank Sta=4964.3,5019.4
XS Rating Curve= 0 ,0
Exp/Cntr=0.3,0.1

Chan Stop Cuts=-1
Use User Specified Reach Order=0
Composite Channel Slope=5