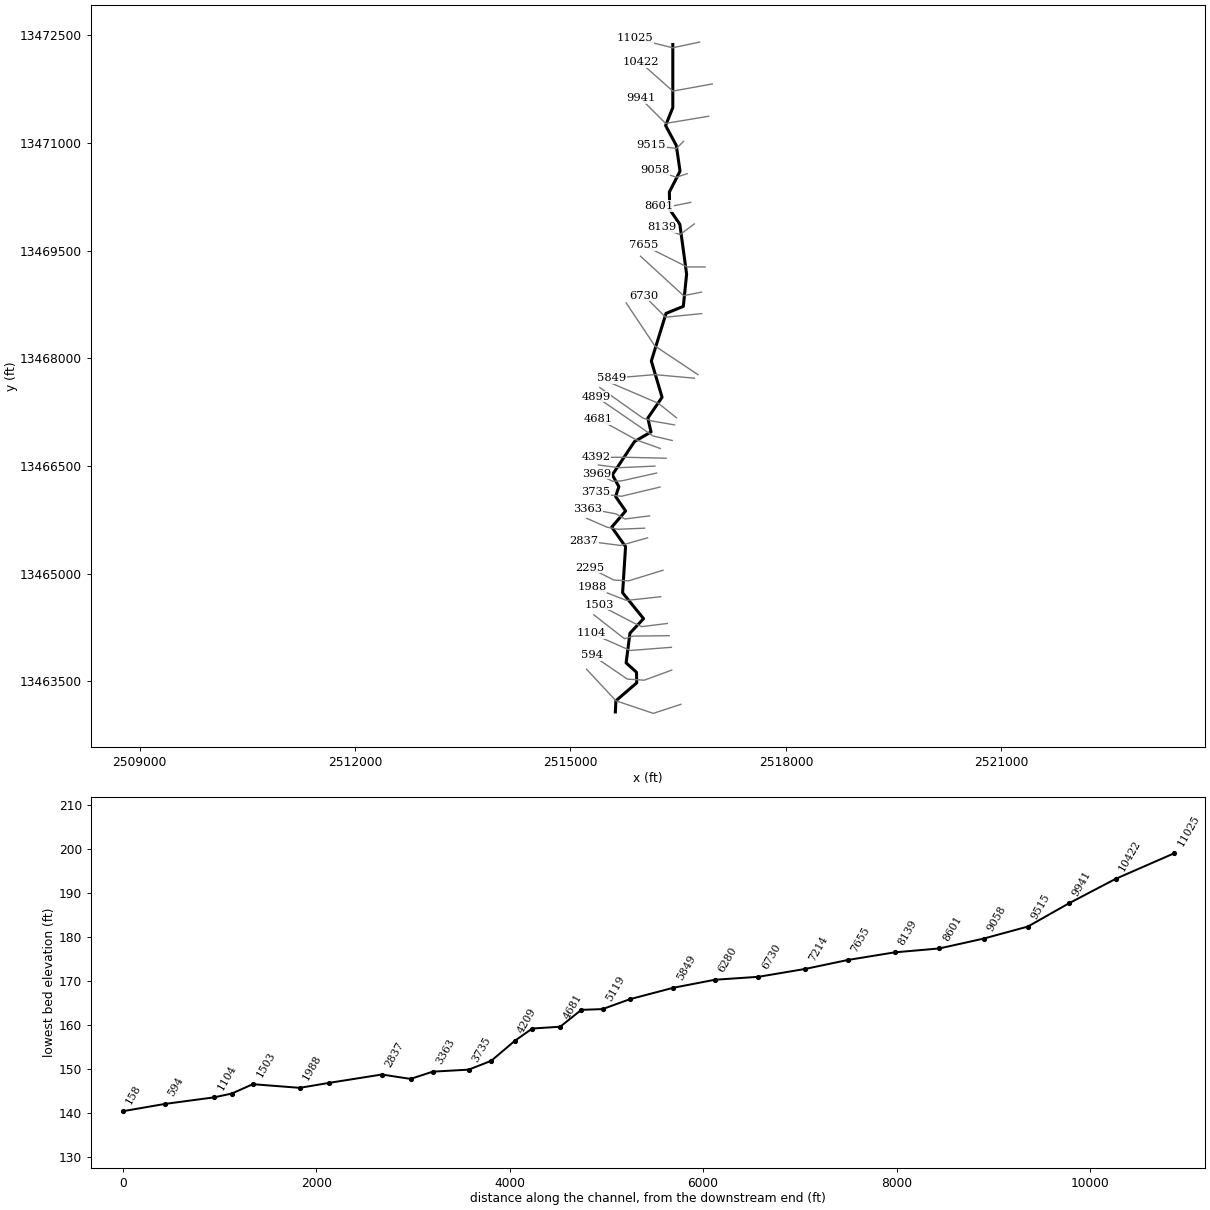
--- BLUE BRANCH.prj (project) ---

Proj Title=BLUE BRANCH Base Level Engineering
Current Plan=p01
Default Exp/Contr=0.3,0.1
English Units
Geom File=g01
Flow File=f01
Plan File=p01
Y Axis Title=Elevation
X Axis Title(PF)=Main Channel Distance
X Axis Title(XS)=Station
BEGIN DESCRIPTION:
BLUE BRANCH
END DESCRIPTION:
DSS Export Rating Curves= 0
DSS Export Rating Curve Sorted= 0
DSS Export Volume Flow Curves= 0
DXF OffsetX= 0
DXF OffsetY= 0
DXF ScaleX= 1
DXF ScaleY= 10

--- BLUE BRANCH.p01 (plan) ---

Plan Title=Multiple Run
Short Identifier=Multiple
Geom File=g01
Flow File=f01
Subcritical Flow
K Sum by GR= 0
Std Step Tol= 0.01
Critical Tol= 0.01
Num of Std Step Trials= 20
Max Error Tol= 0.3
Flow Tol Ratio= 0.001
Split Flow NTrial= 30
Split Flow Tol= 0.02
Split Flow Ratio= 0.02
Log Output Level= 0
Friction Slope Method= 1
Unsteady Friction Slope Method= 2
Unsteady Bridges Friction Slope Method= 1
Parabolic Critical Depth
Global Vel Dist=  1 , 1 , 1
Global Log Level= 0
CheckData=True
Encroach Param= -1, 0, 0, 0
BEGIN DESCRIPTION:
Multiple Run
END DESCRIPTION:

--- BLUE BRANCH.f01 (steady flow) ---

Flow Title=Multiple
Number of Profiles=7
Profile Names=10-year,25-year,50-year,1pct_min,100-year,1pct_plu,500-year
River Rch & RM= BLUE BRANCH,Reach-1,11025
     448     701     923     589    1175    2344    1881
River Rch & RM= BLUE BRANCH,Reach-1,5849
    1007    1650    2241    1471    2934    5854    4977
Boundary for River Rch & Prof#=BLUE BRANCH,Reach-1,1
Up Type=0
Dn Type=3
Dn Slope=0.005
Boundary for River Rch & Prof#=BLUE BRANCH,Reach-1,2
Up Type=0
Dn Type=3
Dn Slope=0.005
Boundary for River Rch & Prof#=BLUE BRANCH,Reach-1,3
Up Type=0
Dn Type=3
Dn Slope=0.005
Boundary for River Rch & Prof#=BLUE BRANCH,Reach-1,4
Up Type=0
Dn Type=3
Dn Slope=0.005
Boundary for River Rch & Prof#=BLUE BRANCH,Reach-1,5
Up Type=0
Dn Type=3
Dn Slope=0.005
Boundary for River Rch & Prof#=BLUE BRANCH,Reach-1,6
Up Type=0
Dn Type=3
Dn Slope=0.005
Boundary for River Rch & Prof#=BLUE BRANCH,Reach-1,7
Up Type=0
Dn Type=3
Dn Slope=0.005

--- BLUE BRANCH.g01 (geometry) ---

Geom Title=Existing Conditions
Program Version=4.10

River Reach=BLUE BRANCH     ,Reach-1
Reach XY= 30
        2516425.       13472375.      2516424.93     13471495.03
      2516324.72     13471245.18      2516473.39     13470969.12
      2516525.71     13470609.94      2516376.97     13470319.11
      2516382.56       13470075.      2516522.93     13469869.14
      2516617.21      13469175.1      2516571.57     13468726.22
       2516330.4     13468627.71       2516126.1     13467964.45
      2516275.49      13467459.8      2516076.97     13467169.11
      2516121.88     13466976.62      2515891.45     13466842.13
      2515582.77     13466378.41      2515674.25     13466214.31
      2515628.34     13466076.72       2515767.7     13465875.08
      2515574.46     13465650.12      2515767.21     13465378.42
      2515726.09     13464735.54      2516017.93       13464375.
      2515828.54     13464173.54      2515775.01     13463759.52
      2515919.65      13463627.7      2515922.95     13463480.86
      2515632.78     13463231.22        2515625.       13463075.

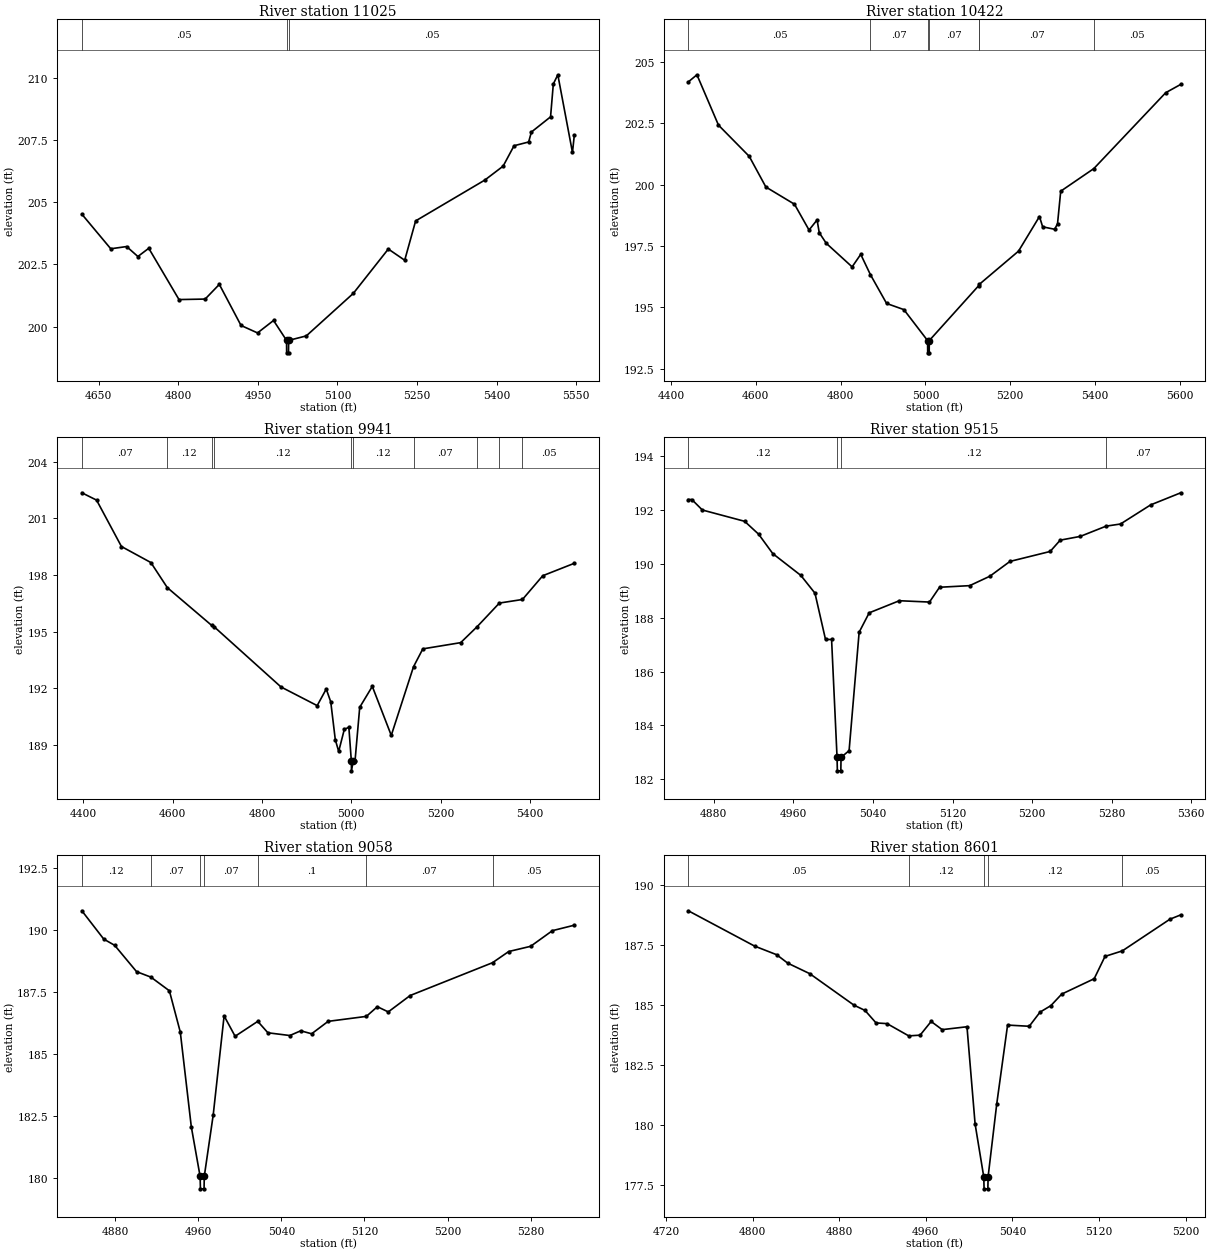
Type RM Length L Ch R = 1 ,11025   ,603,603,603
BEGIN DESCRIPTION:
BLUE BRANCH 24.0
END DESCRIPTION:
XS GIS Cut Line= 3
      2516798.26     13472408.65        2516425.     13472328.36
      2515894.79     13472460.38
#Sta/Elev= 30
  4618.2  204.52  4672.7  203.13  4702.6  203.22  4723.8  202.82  4744.3  203.15
  4801.3  201.09  4850.6  201.11  4877.3   201.7  4918.2  200.05  4949.3  199.75
  4979.5  200.25    5004  199.45  5004.2  198.95  5007.7  198.95    5008  199.45
  5041.2  199.63  5129.9  201.34  5195.8  203.12  5226.7  202.67  5247.3  204.25
  5377.7  205.89  5412.2  206.45  5432.8  207.27  5460.3  207.42  5465.5  207.82
  5501.6  208.43  5506.8  209.75  5515.3  210.12  5542.9     207  5546.4   207.7
#Mann= 3 ,-1 , 0
  4618.2     .05       0    5004     .05       0    5008     .05       0
Bank Sta=5004,5008
XS Rating Curve= 0 ,0
Exp/Cntr=0.3,0.1

Type RM Length L Ch R = 1 ,10422   ,481,481,481
BEGIN DESCRIPTION:
BLUE BRANCH 23.0
END DESCRIPTION:
XS GIS Cut Line= 3
      2516974.99       13471825.        2516425.       13471725.
      2515974.99     13472125.01
#Sta/Elev= 30
    4441  204.18  4461.3  204.47  4512.1  202.42  4584.6  201.15  4623.9   199.9
  4691.3   199.2  4725.6  198.15  4744.6  198.56  4749.7  198.04  4766.2  197.61
  4827.2  196.65  4847.5  197.16  4870.4  196.33  4908.5  195.16  4949.2  194.91
  5005.1  193.65  5005.4  193.15  5008.9  193.15  5009.1  193.65  5125.9  195.89
  5127.2  195.94  5219.5  197.29  5268.9   198.7  5276.4  198.28  5304.8  198.18
  5311.5  198.41    5319  199.73    5397  200.65  5566.5  203.74  5602.1  204.08
#Mann= 7 ,-1 , 0
    4441     .05       0  4870.4     .07       0  5005.1     .05       0
  5009.1     .07       0  5125.9     .05       0  5127.2     .07       0
    5397     .05       0
Bank Sta=5005.1,5009.1
XS Rating Curve= 0 ,0
Exp/Cntr=0.3,0.1

Type RM Length L Ch R = 1 ,9941    ,426,426,426
BEGIN DESCRIPTION:
BLUE BRANCH 22.0
END DESCRIPTION:
XS GIS Cut Line= 3
      2516925.04     13471375.01        2516325.       13471275.
      2515974.99     13471625.01
#Sta/Elev= 30
  4396.4  202.36  4429.4  201.97  4485.1  199.51    4551  198.66  4587.8  197.33
    4687  195.33  4692.4  195.26  4842.5  192.06  4923.6  191.07  4943.9  191.95
    4954  191.27  4964.2  189.26  4971.8  188.64  4984.4  189.81  4994.6  189.92
  5000.2  188.11  5000.4  187.61  5004.2  188.11  5008.3  188.11  5018.9  190.98
  5047.1  192.09  5089.6  189.49  5139.4  193.13  5160.3  194.08  5245.1  194.41
  5282.1  195.26  5331.8  196.51  5383.5   196.7    5429  197.96  5499.7  198.62
#Mann= 10 ,-1 , 0
  4396.4     .07       0  4587.8     .12       0    4687     .07       0
  4692.4     .12       0  5000.2     .05       0  5004.2     .12       0
  5139.4     .07       0  5282.1     .05       0  5331.8     .07       0
  5383.5     .05       0
Bank Sta=5000.2,5004.2
XS Rating Curve= 0 ,0
Exp/Cntr=0.3,0.1

Type RM Length L Ch R = 1 ,9515    ,457,457,457
BEGIN DESCRIPTION:
BLUE BRANCH 21.0
END DESCRIPTION:
XS GIS Cut Line= 3
        2516575.       13471025.        2516475.       13470925.
      2516124.98       13470975.
#Sta/Elev= 30
  4854.4  192.39  4857.9  192.39  4868.5     192    4911  191.58  4925.1   191.1
  4939.3  190.38  4967.5  189.57  4981.7  188.91  4992.3  187.19  4998.4  187.19
  5003.9  182.81  5004.2  182.31  5007.7  182.31  5007.9  182.81    5016  183.06
  5026.1  187.46  5036.2  188.18  5066.5  188.63  5096.8  188.58  5106.9  189.13
  5137.2  189.19  5157.5  189.54  5177.7  190.09  5218.1  190.46  5228.2  190.88
  5248.4  191.02  5274.3   191.4  5288.8  191.48  5319.1  192.19  5349.4  192.64
#Mann= 4 ,-1 , 0
  4854.4     .12       0  5003.9     .05       0  5007.9     .12       0
  5274.3     .07       0
Bank Sta=5003.9,5007.9
XS Rating Curve= 0 ,0
Exp/Cntr=0.3,0.1

Type RM Length L Ch R = 1 ,9058    ,457,457,457
BEGIN DESCRIPTION:
BLUE BRANCH 20.0
END DESCRIPTION:
XS GIS Cut Line= 3
      2516624.98     13470574.99        2516475.       13470525.
      2516175.02     13470624.99
#Sta/Elev= 30
  4847.8  190.77  4868.9  189.63  4879.4  189.38  4900.5  188.32  4914.3   188.1
  4932.1  187.55  4942.6  185.89  4953.2  182.08  4961.7  180.08    4962  179.58
  4965.5  179.58  4965.7  180.08  4974.3  182.55  4984.8  186.54  4995.4  185.72
  5017.2  186.32    5027  185.86  5048.1  185.75  5058.6  185.94  5069.1  185.82
    5085  186.32  5121.8  186.52  5132.4  186.91  5142.9   186.7    5164  187.36
  5243.3  188.68  5258.9  189.13    5280  189.34    5301  189.97  5322.1  190.19
#Mann= 7 ,-1 , 0
  4847.8     .12       0  4914.3     .07       0  4961.7     .05       0
  4965.7     .07       0  5017.2      .1       0  5121.8     .07       0
  5243.3     .05       0
Bank Sta=4961.7,4965.7
XS Rating Curve= 0 ,0
Exp/Cntr=0.3,0.1

Type RM Length L Ch R = 1 ,8601    ,462,462,462
BEGIN DESCRIPTION:
BLUE BRANCH 19.0
END DESCRIPTION:
XS GIS Cut Line= 3
      2516674.99       13470175.        2516425.       13470125.
      2516225.04       13470125.
#Sta/Elev= 30
  4740.6  188.92  4801.8  187.45  4822.2  187.09  4832.4  186.74  4852.8   186.3
  4893.6  184.99  4903.8  184.77    4914  184.25  4924.2  184.22  4944.2  183.71
  4954.7  183.74  4964.9  184.31  4975.1  183.97    4998  184.09  5005.5  180.04
  5013.5  177.84  5013.8  177.34  5017.3  177.34  5017.5  177.84  5025.5  180.88
  5035.5  184.16  5055.5  184.11  5065.5   184.7  5075.5  184.97  5085.5  185.45
  5115.5  186.09  5125.5  187.02  5141.5  187.25  5185.5  188.57  5195.5  188.75
#Mann= 5 ,-1 , 0
  4740.6     .05       0  4944.2     .12       0  5013.5     .05       0
  5017.5     .12       0  5141.5     .05       0
Bank Sta=5013.5,5017.5
XS Rating Curve= 0 ,0
Exp/Cntr=0.3,0.1

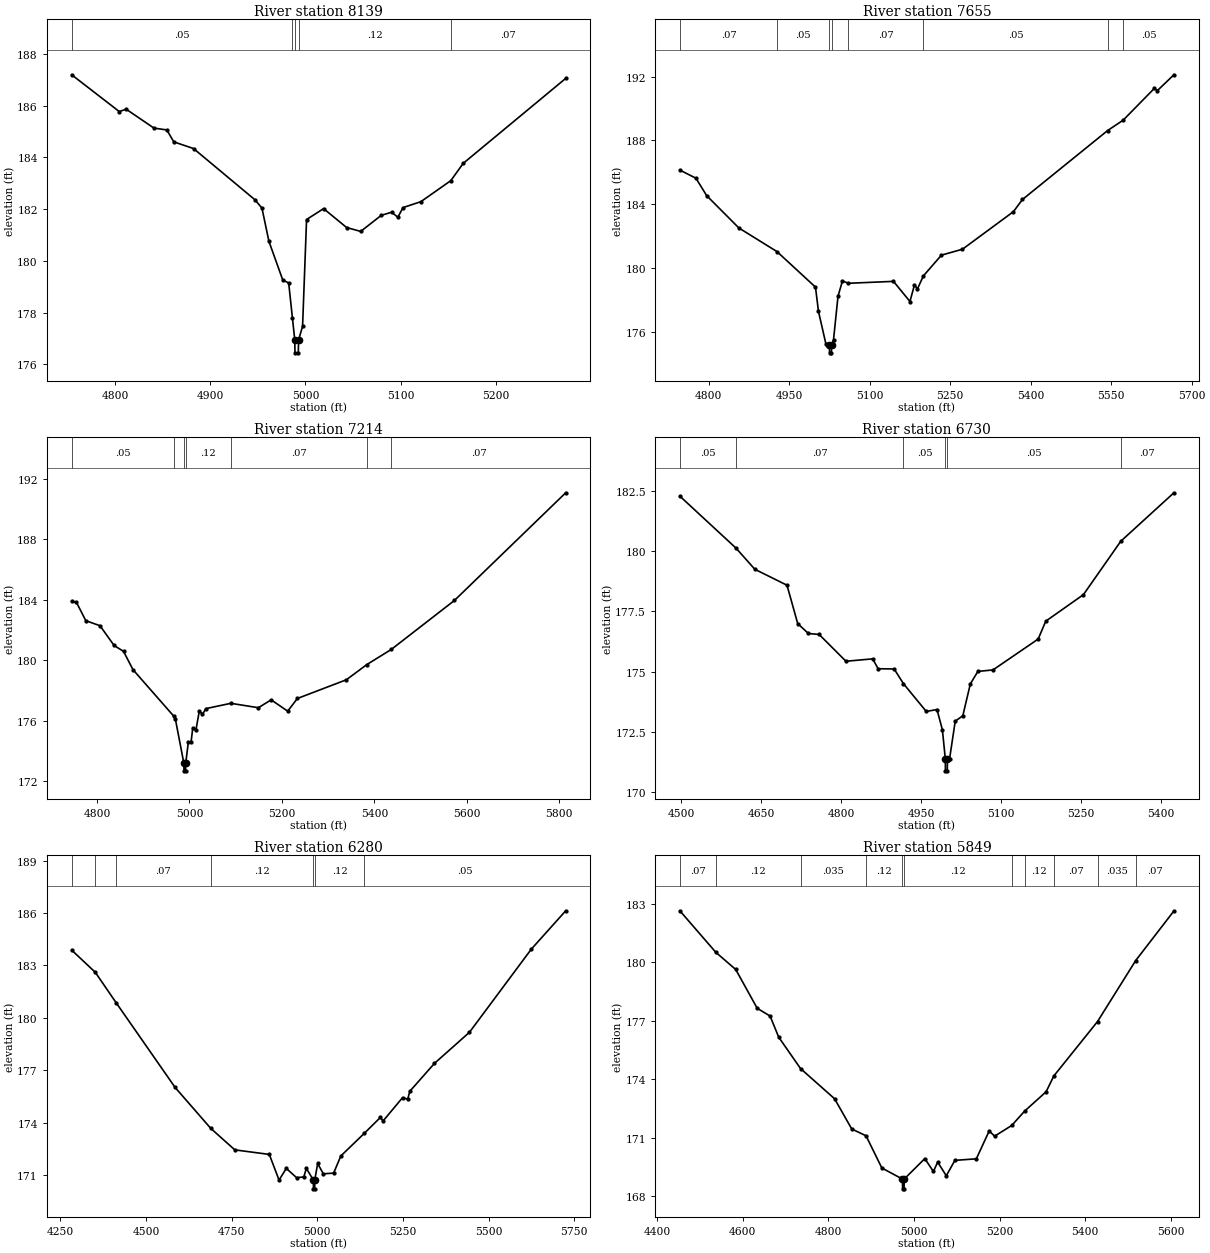
Type RM Length L Ch R = 1 ,8139    ,484,484,484
BEGIN DESCRIPTION:
BLUE BRANCH 18.0
END DESCRIPTION:
XS GIS Cut Line= 3
        2516725.       13469875.        2516525.       13469725.
      2516274.96     13469825.02
#Sta/Elev= 30
  4754.3  187.19  4804.3  185.77  4811.6  185.86  4840.8  185.13  4854.3  185.06
  4861.6   184.6  4882.4  184.34    4947  182.36  4954.3  182.04  4961.6  180.76
  4976.2  179.26  4982.4  179.15  4986.3  177.81  4988.8  176.95    4989  176.45
  4992.5  176.45  4992.8  176.95    4997  177.47  5001.2   181.6  5019.1  182.02
  5043.3  181.29  5058.1  181.14  5079.7  181.76  5090.5  181.88  5097.2  181.69
  5102.6  182.06  5121.4  182.29  5152.8   183.1  5165.9  183.77  5273.6  187.05
#Mann= 5 ,-1 , 0
  4754.3     .05       0  4986.3     .12       0  4988.8     .05       0
  4992.8     .12       0  5152.8     .07       0
Bank Sta=4988.8,4992.8
XS Rating Curve= 0 ,0
Exp/Cntr=0.3,0.1

Type RM Length L Ch R = 1 ,7655    ,441,441,441
BEGIN DESCRIPTION:
BLUE BRANCH 17.0
END DESCRIPTION:
XS GIS Cut Line= 3
      2516875.04       13469275.        2516625.       13469275.
      2516024.96     13469575.02
#Sta/Elev= 30
    4746  186.15    4776  185.64    4796  184.55    4856  182.53  4927.1  181.05
  4998.8  178.83  5004.4  177.31  5018.4  175.25  5024.8  175.22    5025  174.72
  5028.5  174.72  5028.8  175.22  5032.4  175.53  5040.8  178.26  5049.1  179.22
  5059.9  179.07  5144.2  179.19  5174.9  177.93  5183.3  178.97  5188.9  178.72
  5199.9  179.53  5233.6  180.83  5272.8   181.2  5367.8  183.55  5384.6  184.31
  5543.3  188.62  5572.3  189.27  5630.5  191.26  5636.1  191.12  5666.9  192.11
#Mann= 8 ,-1 , 0
    4746     .07       0  4927.1     .05       0  5024.8     .05       0
  5028.8     .05       0  5059.9     .07       0  5199.9     .05       0
  5543.3     .12       0  5572.3     .05       0
Bank Sta=5024.8,5028.8
XS Rating Curve= 0 ,0
Exp/Cntr=0.3,0.1

Type RM Length L Ch R = 1 ,7214    ,484,484,484
BEGIN DESCRIPTION:
BLUE BRANCH 16.0
END DESCRIPTION:
XS GIS Cut Line= 3
      2516824.99       13468925.        2516575.       13468875.
      2515974.99     13469425.01
#Sta/Elev= 30
  4745.1   183.9  4755.3  183.84  4775.7  182.62  4806.3  182.29  4836.9  180.98
  4857.3  180.59  4877.7  179.38  4965.4  176.32  4969.4  176.12  4987.8  173.18
  4988.1  172.68  4991.6  172.68  4991.8  173.18  4997.5  174.58  5003.4  174.58
  5007.1  175.52  5013.9  175.38  5021.3  176.65  5028.1  176.42  5035.5   176.8
  5089.4  177.15    5149  176.86  5176.7  177.38  5212.5  176.63  5233.4  177.47
  5339.5  178.71  5383.4  179.71  5436.7  180.72  5573.2  183.96    5814  191.09
#Mann= 7 ,-1 , 0
  4745.1     .05       0  4965.4     .12       0  4987.8     .05       0
  4991.8     .12       0  5089.4     .07       0  5383.4     .05       0
  5436.7     .07       0
Bank Sta=4987.8,4991.8
XS Rating Curve= 0 ,0
Exp/Cntr=0.3,0.1

Type RM Length L Ch R = 1 ,6730    ,450,450,450
BEGIN DESCRIPTION:
BLUE BRANCH 15.0
END DESCRIPTION:
XS GIS Cut Line= 3
      2516825.01       13468625.        2516325.       13468575.
      2516024.98     13468875.02
#Sta/Elev= 30
  4497.4  182.27  4602.6  180.12  4638.1  179.24  4698.4  178.58  4718.5  176.99
  4738.6  176.58  4758.7  176.54    4809  175.43  4859.2  175.53  4869.3  175.12
  4899.4  175.11  4916.9   174.5  4959.7  173.35  4979.8  173.43  4989.9  172.59
  4995.4  171.39  4995.6  170.89  4999.1  170.89  4999.4  171.39  5003.4  171.39
    5014  172.95  5028.2  173.17  5042.3  174.49  5056.5  175.01  5084.8  175.07
  5169.6  176.35  5183.8  177.09  5254.5  178.19  5324.5   180.4  5424.2  182.41
#Mann= 6 ,-1 , 0
  4497.4     .05       0  4602.6     .07       0  4916.9     .05       0
  4995.4     .05       0  4999.4     .05       0  5324.5     .07       0
Bank Sta=4995.4,4999.4
XS Rating Curve= 0 ,0
Exp/Cntr=0.3,0.1

Type RM Length L Ch R = 1 ,6280    ,431,431,431
BEGIN DESCRIPTION:
BLUE BRANCH 14.0
END DESCRIPTION:
XS GIS Cut Line= 3
      2516775.01     13467774.99        2516175.       13468175.
      2515775.02     13468774.97
#Sta/Elev= 30
  4283.1  183.88    4352  182.61  4412.5  180.88  4585.1  176.02  4689.1  173.68
  4759.3  172.45    4860  172.19  4888.5  170.72  4909.6  171.39  4939.6  170.86
  4960.7   170.9  4968.2  171.39  4988.7  170.72    4989  170.22  4992.5  170.22
  4992.7  170.72  5001.2  171.67  5017.7  171.08  5047.8  171.12  5068.8   172.1
    5137  173.39  5184.5  174.31    5192   174.1  5249.1  175.44  5264.1  175.35
  5270.1   175.8  5342.2   177.4  5444.4  179.18  5624.7  183.93  5725.3  186.13
#Mann= 7 ,-1 , 0
  4283.1     .07       0    4352    .035       0  4412.5     .07       0
  4689.1     .12       0  4988.7     .05       0  4992.7     .12       0
    5137     .05       0
Bank Sta=4988.7,4992.7
XS Rating Curve= 0 ,0
Exp/Cntr=0.3,0.1

Type RM Length L Ch R = 1 ,5849    ,449,449,449
BEGIN DESCRIPTION:
BLUE BRANCH 13.0
END DESCRIPTION:
XS GIS Cut Line= 3
      2516724.99       13467725.        2516175.       13467775.
      2515575.04       13467725.
#Sta/Elev= 30
    4453  182.65    4537  180.52  4583.5  179.64  4633.7  177.65  4663.9  177.25
  4683.9  176.17  4734.9  174.56  4814.5  173.01  4854.6  171.46    4888  171.11
  4924.9  169.46  4973.1  168.89  4973.4  168.39  4976.9  168.39  4977.1  168.89
  5025.3  169.94  5045.4  169.28  5055.4  169.76  5075.5  169.06  5095.6  169.85
  5145.7  169.93  5175.8  171.36  5188.4  171.09  5228.4  171.64  5258.7  172.38
  5308.8  173.37  5326.8  174.18  5428.9  176.97  5518.1   180.1  5607.3  182.64
#Mann= 11 ,-1 , 0
    4453     .07       0    4537     .12       0  4734.9    .035       0
    4888     .12       0  4973.1     .05       0  4977.1     .12       0
  5228.4     .05       0  5258.7     .12       0  5326.8     .07       0
  5428.9    .035       0  5518.1     .07       0
Bank Sta=4973.1,4977.1
XS Rating Curve= 0 ,0
Exp/Cntr=0.3,0.1

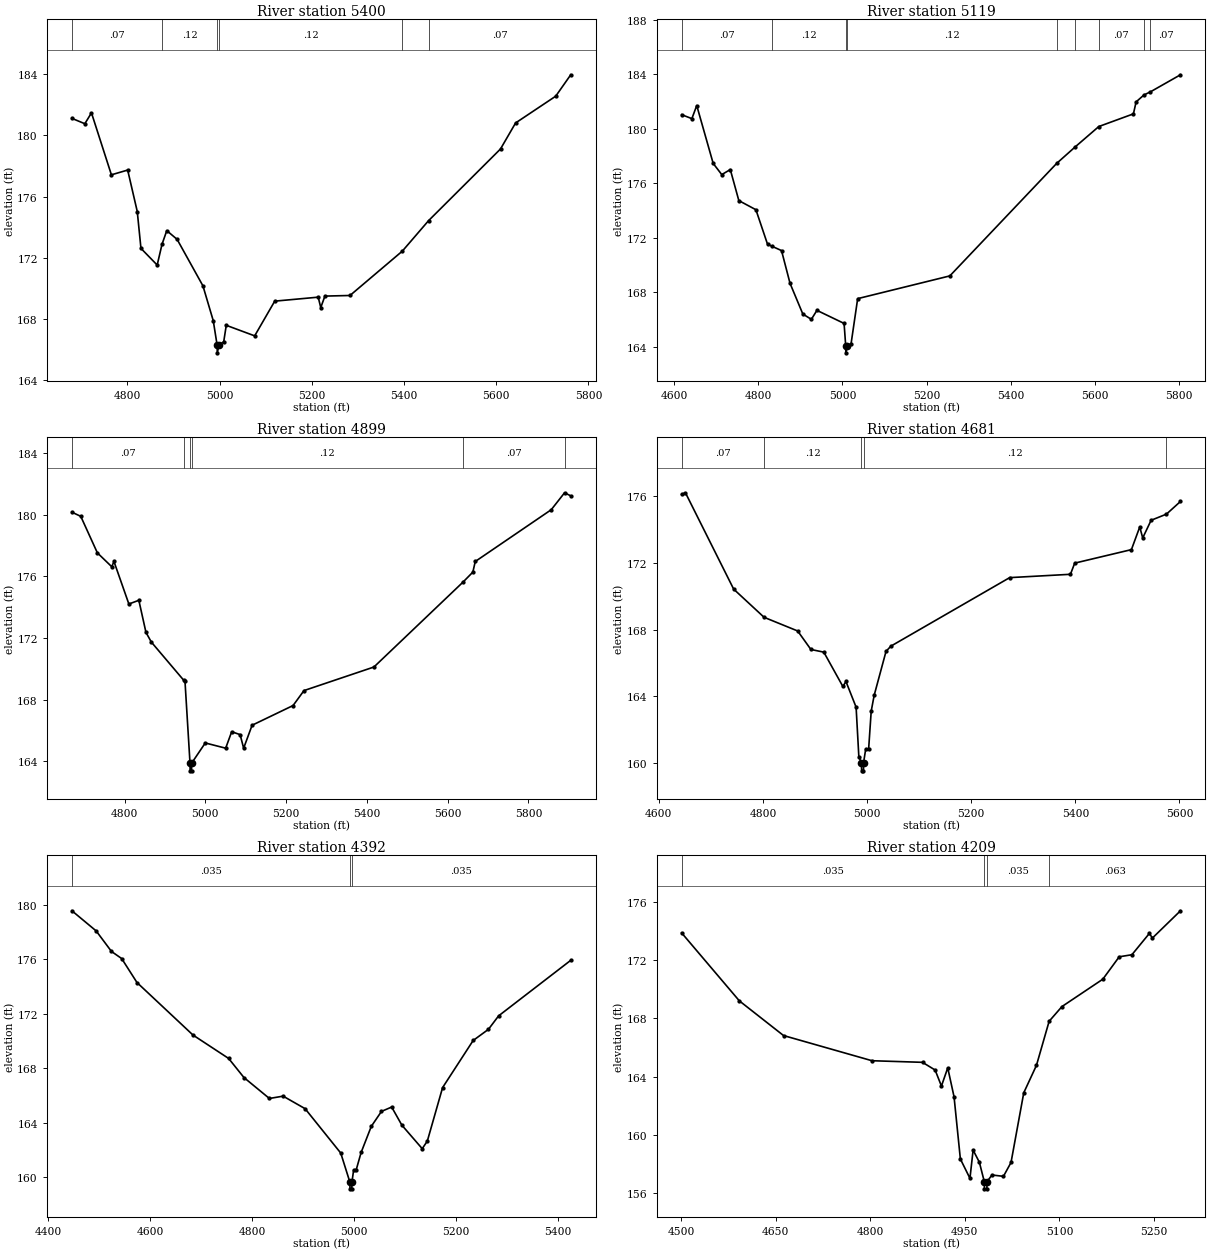
Type RM Length L Ch R = 1 ,5400    ,281,281,281
BEGIN DESCRIPTION:
BLUE BRANCH 12.0
END DESCRIPTION:
XS GIS Cut Line= 3
        2516475.       13467175.        2516225.       13467375.
      2515525.02     13467674.99
#Sta/Elev= 30
  4679.9  181.12  4707.9  180.77  4722.3  181.48  4765.5  177.43  4800.8  177.74
  4821.6  175.03  4829.6  172.62  4864.8  171.53  4875.2  172.88  4885.6  173.78
    4908  173.21    4964  170.17  4986.4  167.89  4994.8  166.29  4995.1  165.79
  4998.8  166.29  5009.1  166.52  5014.6  167.59  5076.2   166.9  5119.7  169.17
    5214  169.43  5219.5  168.75  5228.5   169.5  5282.9  169.54  5396.4  172.44
  5453.2  174.43  5609.3  179.12    5642  180.82    5729  182.57  5761.6  183.97
#Mann= 6 ,-1 , 0
  4679.9     .07       0  4875.2     .12       0  4994.8     .05       0
  4998.8     .12       0  5396.4    .035       0  5453.2     .07       0
Bank Sta=4994.8,4998.8
XS Rating Curve= 0 ,0
Exp/Cntr=0.3,0.1

Type RM Length L Ch R = 1 ,5119    ,220,220,220
BEGIN DESCRIPTION:
Mapping XS 481f6cbe
END DESCRIPTION:
XS GIS Cut Line= 4
      2516448.93     13467074.45      2516138.56     13467128.71
      2516008.36     13467169.94      2515408.65     13467594.28
#Sta/Elev= 30
  4617.7  181.04    4642  180.75  4653.6  181.71  4692.7  177.46  4713.1  176.64
  4733.4  177.01  4753.7  174.73  4794.3  174.06  4821.9  171.53  4833.7  171.36
  4855.2  171.06  4875.5  168.65  4905.9   166.4  4926.2  166.01  4939.4  166.67
    5004  165.71  5007.9  164.05  5008.1  163.55    5012  164.05  5020.4  164.17
  5036.3  167.53  5255.5   169.2  5509.5  177.46  5553.1  178.66  5609.8  180.17
  5692.1   181.1  5698.5  181.98  5717.3  182.49  5732.7  182.72    5804  183.97
#Mann= 9 ,-1 , 0
  4617.7     .07       0  4833.7     .12       0  5007.9     .05       0
    5012     .12       0  5509.5     .07       0  5553.1    .035       0
  5609.8     .07       0  5717.3    .035       0  5732.7     .07       0
Bank Sta=5007.9,5012
XS Rating Curve= 0 ,0
Exp/Cntr=0.3,0.1

Type RM Length L Ch R = 1 ,4899    ,218,218,218
BEGIN DESCRIPTION:
Mapping XS 715a2ca5
END DESCRIPTION:
XS GIS Cut Line= 4
      2516416.32     13466857.45      2516149.42     13466920.38
      2516004.02     13467022.37      2515358.69      13467466.3
#Sta/Elev= 30
  4669.6  180.16  4691.5  179.89  4732.6  177.52  4768.2  176.62  4773.7  176.96
  4810.6   174.2  4835.3  174.44  4852.9  172.36  4866.2  171.73  4946.1  169.26
  4949.6  169.17    4962  163.87  4962.3  163.37  4965.9  163.37  4966.1  163.87
  4999.8  165.18  5050.3  164.84  5065.2  165.91  5086.1  165.72  5094.8  164.84
  5115.7  166.33  5217.2  167.61  5244.2  168.58  5417.4  170.11  5637.9  175.62
  5662.3  176.27  5668.3  176.96  5856.4  180.32  5889.4  181.42  5904.7  181.22
#Mann= 6 ,-1 , 0
  4669.6     .07       0  4946.1     .12       0    4962     .05       0
  4966.1     .12       0  5637.9     .07       0  5889.4     .12       0
Bank Sta=4962,4966.1
XS Rating Curve= 0 ,0
Exp/Cntr=0.3,0.1

Type RM Length L Ch R = 1 ,4681    ,289,289,289
BEGIN DESCRIPTION:
Mapping XS 9cdf7a9e
END DESCRIPTION:
XS GIS Cut Line= 3
       2516251.9     13466745.48      2515918.52     13466865.28
      2515389.98     13467156.89
#Sta/Elev= 30
    4644  176.12  4651.3  176.22  4743.9  170.44  4802.3  168.75  4866.8  167.93
  4892.2  166.82    4917  166.66  4953.6   164.6  4959.5   164.9    4979  163.36
  4984.3  160.37  4989.3  160.04  4989.6  159.54  4993.2  159.54  4993.4  160.04
  4997.5  160.86  5003.1  160.86    5008  163.12  5013.7  164.07  5036.5  166.71
  5045.8  167.02  5273.9  171.13  5390.6  171.33  5398.8     172  5507.7  172.81
  5523.7  174.17  5529.4  173.51  5545.5  174.57    5575  174.94  5601.9   175.7
#Mann= 5 ,-1 , 0
    4644     .07       0  4802.3     .12       0  4989.3     .05       0
  4993.4     .12       0    5575     .07       0
Bank Sta=4989.3,4993.4
XS Rating Curve= 0 ,0
Exp/Cntr=0.3,0.1

Type RM Length L Ch R = 1 ,4392    ,183,183,183
BEGIN DESCRIPTION:
BLUE BRANCH 10.0
END DESCRIPTION:
XS GIS Cut Line= 3
      2516332.63     13466610.07      2515779.19     13466623.26
      2515353.39      13466623.1
#Sta/Elev= 30
  4446.4  179.56    4494  178.08  4524.1  176.57  4544.1  176.05  4574.1  174.29
  4684.1  170.43  4754.1  168.71  4784.1  167.31  4834.1  165.77  4861.1  165.94
  4904.2  165.02  4974.2  161.76  4992.1  159.63  4992.4  159.13    4996  159.13
  4996.2  159.63  4999.6  160.53  5004.6  160.53  5014.2   161.8  5034.2  163.72
  5054.2  164.82  5074.2  165.14  5094.2  163.81  5134.2  162.08  5144.2  162.64
  5174.2  166.57  5234.2  170.03  5264.2  170.85  5284.2  171.84  5425.8  175.92
#Mann= 3 ,-1 , 0
  4446.4    .035       0  4992.1    .035       0  4996.2    .035       0
Bank Sta=4992.1,4996.2
XS Rating Curve= 0 ,0
Exp/Cntr=0.3,0.1

Type RM Length L Ch R = 1 ,4209    ,240,240,240
BEGIN DESCRIPTION:
BLUE BRANCH 9.0
END DESCRIPTION:
XS GIS Cut Line= 3
      2516176.38      13466500.7      2515678.09     13466478.11
      2515388.68     13466516.14
#Sta/Elev= 30
  4501.2  173.87  4592.7   169.2  4662.7  166.82  4802.9  165.09    4883  164.98
    4903  164.45    4913  163.35    4923   164.6    4933  162.61    4943  158.34
  4958.2  157.01  4963.2  158.95  4973.1  158.12  4980.9  156.79  4981.2  156.29
    4985  156.29  4985.3  156.79  4993.1  157.24  5011.3  157.15  5023.3   158.1
  5043.5  162.89  5063.6  164.77  5083.7   167.8    5104  168.81  5168.8  170.69
  5194.8  172.23  5214.9  172.37  5242.5  173.83  5247.5  173.52  5291.9  175.39
#Mann= 4 ,-1 , 0
  4501.2    .035       0  4980.9    .035       0  4985.3    .035       0
  5083.7    .063       0
Bank Sta=4980.9,4985.3
XS Rating Curve= 0 ,0
Exp/Cntr=0.3,0.1

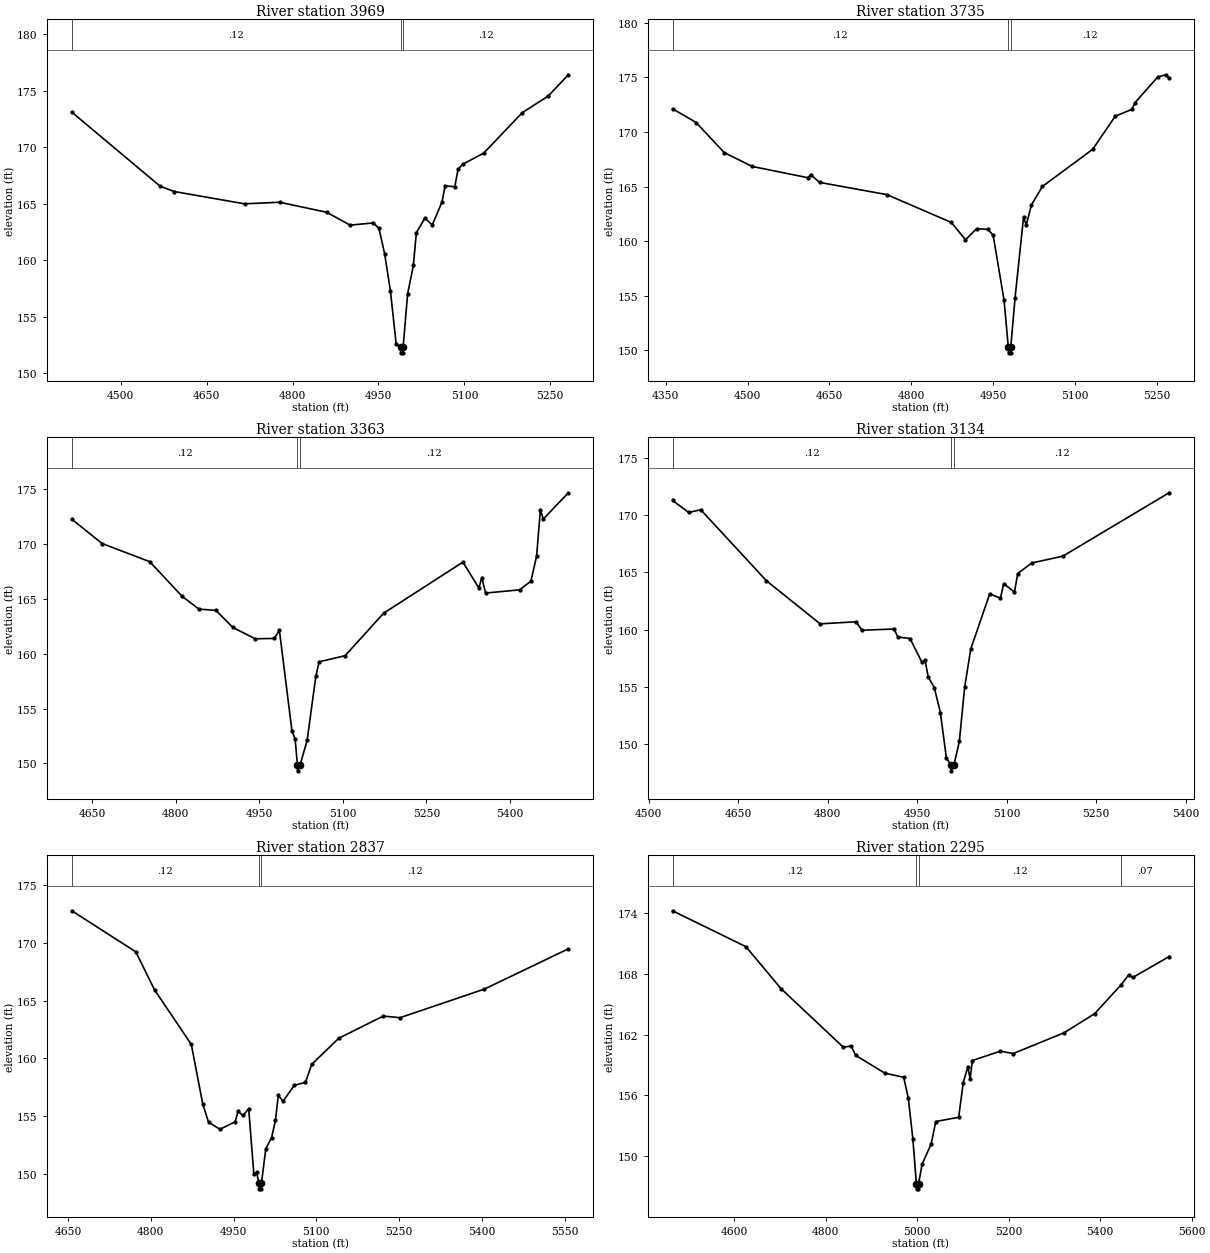
Type RM Length L Ch R = 1 ,3969    ,234,234,234
BEGIN DESCRIPTION:
Mapping XS cbd45136
END DESCRIPTION:
XS GIS Cut Line= 4
      2516199.33     13466403.88      2515715.39     13466295.38
      2515587.35     13466288.87      2515369.32     13466396.25
#Sta/Elev= 30
  4414.4  173.12  4568.4  166.57  4593.1  166.09    4716     165  4777.5  165.14
  4859.5  164.25  4900.5  163.11  4940.8  163.31  4950.8  162.82  4960.8  160.56
  4970.8   157.3  4980.8  152.61  4988.6   152.3  4988.9   151.8  4992.7   151.8
    4993   152.3  5000.9  157.03  5010.9  159.54  5016.1  162.43  5030.9  163.73
  5043.9  163.13  5060.8  165.14  5066.4  166.59  5083.3  166.51  5088.9  168.05
  5096.9   168.5  5133.8  169.49  5201.2  173.08  5246.1  174.53  5281.6  176.43
#Mann= 3 ,-1 , 0
  4414.4     .12       0  4988.6     .05       0    4993     .12       0
Bank Sta=4988.6,4993
XS Rating Curve= 0 ,0
Exp/Cntr=0.3,0.1

Type RM Length L Ch R = 1 ,3735    ,372,372,372
BEGIN DESCRIPTION:
Mapping XS eee4e69f
END DESCRIPTION:
XS GIS Cut Line= 4
      2516247.09     13466208.58      2515711.05     13466080.53
      2515563.48     13466095.72      2515358.91     13466144.59
#Sta/Elev= 30
  4362.6  172.12  4405.9  170.86  4457.3  168.11  4508.7  166.84  4610.5  165.81
  4615.7  166.09  4632.1  165.38  4755.4  164.26  4873.3  161.72  4899.4  160.13
  4919.8  161.14  4939.9  161.08    4950  160.57  4970.1  154.58  4977.9  150.28
  4978.2  149.78    4982  149.78  4982.3  150.28  4990.2  154.81  5005.7  162.17
  5010.7  161.49  5020.3  163.33  5040.4  165.01  5132.5  168.41  5173.6  171.43
  5204.5  172.07  5209.6  172.66  5251.7  175.03  5266.1  175.23  5272.4  174.92
#Mann= 3 ,-1 , 0
  4362.6     .12       0  4977.9     .05       0  4982.3     .12       0
Bank Sta=4977.9,4982.3
XS Rating Curve= 0 ,0
Exp/Cntr=0.3,0.1

Type RM Length L Ch R = 1 ,3363    ,229,229,229
BEGIN DESCRIPTION:
Mapping XS 2afc5675
END DESCRIPTION:
XS GIS Cut Line= 4
      2516101.67     13465807.09      2515756.62     13465763.69
      2515632.92     13465835.31      2515238.94     13465908.91
#Sta/Elev= 30
  4613.5  172.26    4668  170.04  4753.4  168.39  4811.7  165.22    4842  164.06
  4872.2  163.95  4902.4   162.4  4942.7  161.36  4977.2  161.39  4986.2  162.13
  5008.7  152.97  5014.5  152.21  5018.6  149.82  5018.9  149.32  5023.2  149.82
    5036   152.1  5051.7  157.97  5057.5  159.26  5104.2  159.82  5173.3  163.69
  5315.7  168.35  5344.4  165.98  5349.5  166.94  5356.4  165.53  5417.4  165.82
  5437.8  166.61    5448  168.91  5454.8  173.12  5459.9  172.27    5505  174.67
#Mann= 3 ,-1 , 0
  4613.5     .12       0  5018.6     .05       0  5023.2     .12       0
Bank Sta=5018.6,5023.2
XS Rating Curve= 0 ,0
Exp/Cntr=0.3,0.1

Type RM Length L Ch R = 1 ,3134    ,297,297,297
BEGIN DESCRIPTION:
Mapping XS 02fb3987
END DESCRIPTION:
XS GIS Cut Line= 4
      2516032.22     13465635.65      2515661.13     13465620.46
      2515511.39     13465648.67      2515228.58     13465771.73
#Sta/Elev= 30
  4540.1  171.27  4567.3  170.22  4587.4  170.46  4697.5  164.26  4787.5   160.5
  4847.6  160.68  4857.6  159.94  4911.5  160.05  4917.7  159.35  4938.1  159.22
  4958.2  157.14  4963.3  157.34  4968.6  155.87  4978.8  154.94    4989  152.76
  4999.1  148.78  5006.9  148.17  5007.3  147.67  5011.7  148.17  5020.8  150.24
  5029.7  154.96  5039.9  158.29  5071.7  163.12  5089.7  162.74  5095.2  164.01
  5113.2  163.27  5118.6  164.89  5142.1  165.81  5194.4  166.41  5372.3  171.94
#Mann= 3 ,-1 , 0
  4540.1     .12       0  5006.9     .05       0  5011.7     .12       0
Bank Sta=5006.9,5011.7
XS Rating Curve= 0 ,0
Exp/Cntr=0.3,0.1

Type RM Length L Ch R = 1 ,2837    ,542,542,542
BEGIN DESCRIPTION:
Mapping XS 13adb6a6
END DESCRIPTION:
XS GIS Cut Line= 3
      2516073.43      13465501.1      2515698.03     13465394.77
      2515192.37     13465459.88
#Sta/Elev= 30
  4656.9  172.78  4772.9  169.22  4806.8  165.93  4873.5  161.19  4894.3  156.01
  4904.7  154.45  4925.5  153.83    4953  154.49  4958.2  155.39  4967.1  155.03
  4977.5  155.61  4986.9  149.94  4992.1  150.09  4995.8  149.17  4996.2  148.67
  5000.3  148.67  5000.6  149.17  5008.6  152.16    5019  153.11    5026  154.61
  5031.2  156.78  5039.8  156.26  5060.2  157.65  5080.4   157.9  5091.8  159.47
  5140.9  161.73  5221.5  163.65  5251.8  163.51  5404.7  165.99  5556.9  169.48
#Mann= 3 ,-1 , 0
  4656.9     .12       0  4995.8     .05       0  5000.6     .12       0
Bank Sta=4995.8,5000.6
XS Rating Curve= 0 ,0
Exp/Cntr=0.3,0.1

Type RM Length L Ch R = 1 ,2295    ,307,307,307
BEGIN DESCRIPTION:
Mapping XS fdb3c65e
END DESCRIPTION:
XS GIS Cut Line= 4
      2516288.32     13465049.72      2515810.87     13464902.15
      2515602.54       13464913.      2515266.16     13465084.44
#Sta/Elev= 30
  4464.7  174.21  4625.2  170.67  4702.2  166.52    4838  160.76  4855.5  160.86
  4865.4  159.94  4928.7   158.2  4970.3  157.78  4980.3  155.73  4990.3  151.71
    4998  147.28  4998.3  146.78  5002.4  146.78  5002.8  147.28  5010.4  149.19
  5030.4  151.22  5040.4  153.42  5090.5  153.84  5100.5  157.27  5110.5   158.8
  5115.5  157.65  5120.5  159.44  5181.5  160.36    5210  160.13  5321.2  162.18
  5387.9  164.06  5445.6  166.91  5462.1  167.87  5471.2  167.63  5550.6  169.69
#Mann= 4 ,-1 , 0
  4464.7     .12       0    4998     .05       0  5002.8     .12       0
  5445.6     .07       0
Bank Sta=4998,5002.8
XS Rating Curve= 0 ,0
Exp/Cntr=0.3,0.1

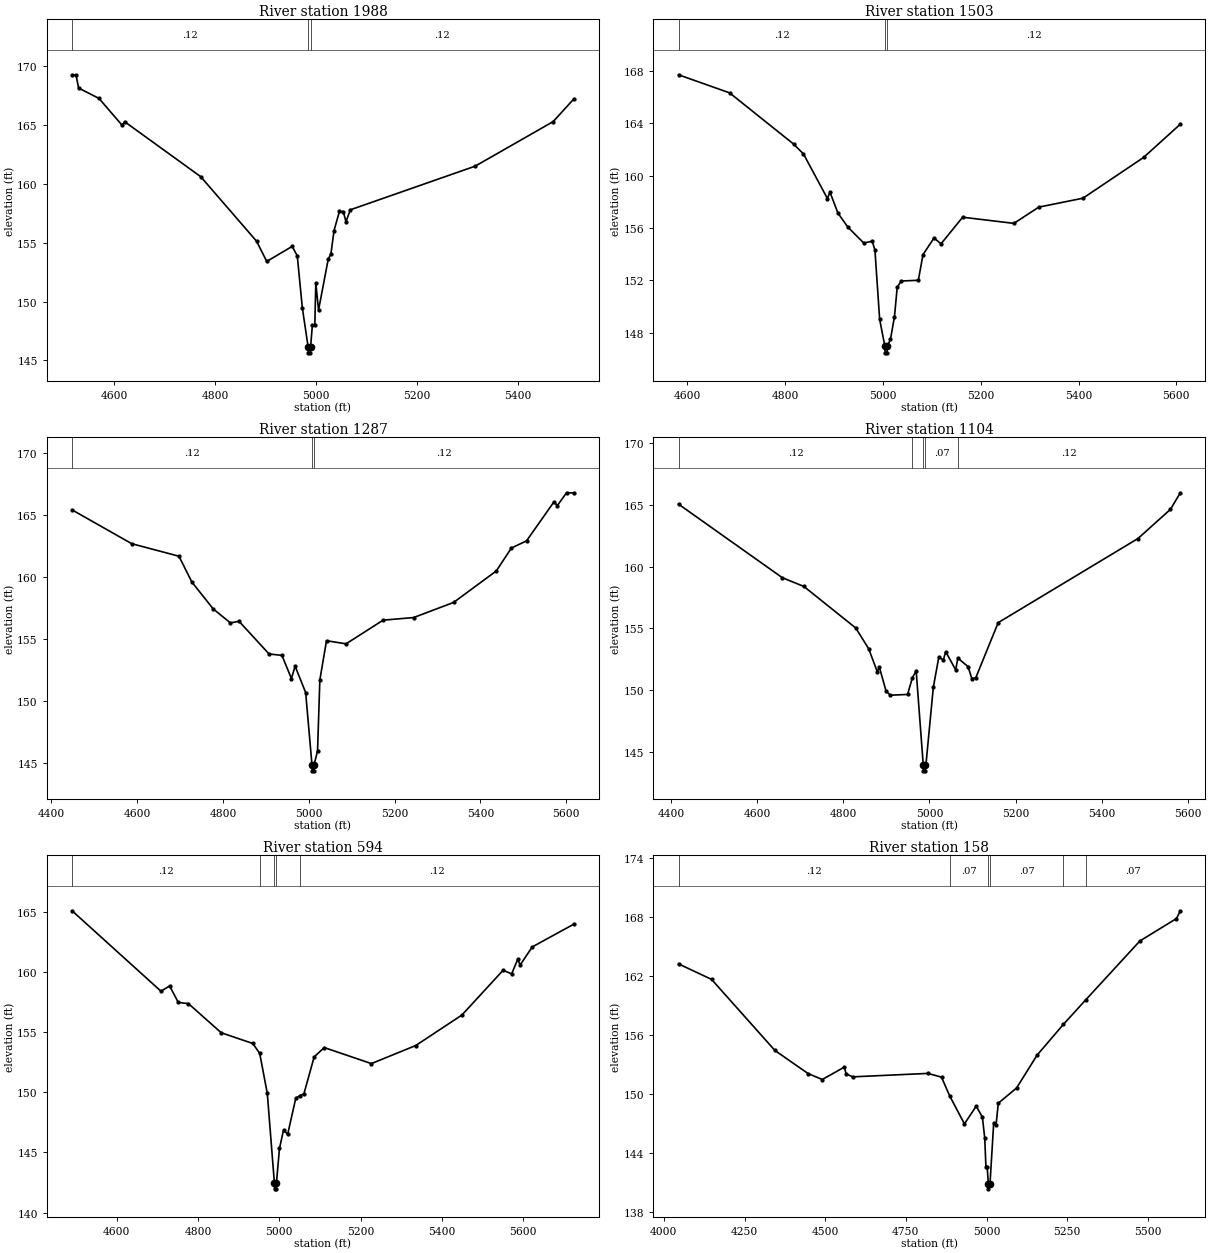
Type RM Length L Ch R = 1 ,1988    ,485,485,485
BEGIN DESCRIPTION:
Mapping XS 4c68c578
END DESCRIPTION:
XS GIS Cut Line= 3
      2516257.95      13464680.8      2515780.49     13464628.71
      2515303.07     13464815.34
#Sta/Elev= 30
  4517.2  169.25  4524.9  169.28  4530.2  168.15  4570.5  167.27  4616.2  164.99
  4621.3  165.29  4771.7  160.62  4882.3  155.13  4902.4  153.41  4952.7  154.69
  4962.8  153.89  4972.8  149.47  4984.3  146.14  4984.7  145.64  4988.9  145.64
  4989.2  146.14  4992.7  147.99  4997.5  147.99  4999.5  151.59  5004.9  149.28
    5024  153.59  5029.4  154.06  5035.6  156.04  5046.3  157.68  5053.8  157.65
  5059.2  156.79  5067.8   157.8  5314.8  161.51  5469.2   165.3  5510.1  167.23
#Mann= 3 ,-1 , 0
  4517.2     .12       0  4984.3     .05       0  4989.2     .12       0
Bank Sta=4984.3,4989.2
XS Rating Curve= 0 ,0
Exp/Cntr=0.3,0.1

Type RM Length L Ch R = 1 ,1503    ,216,216,216
BEGIN DESCRIPTION:
Mapping XS b6c622dc
END DESCRIPTION:
XS GIS Cut Line= 4
      2516348.59     13464307.96      2515991.86     13464263.69
      2515873.37     13464319.68      2515398.38     13464567.56
#Sta/Elev= 30
  4581.9  167.69  4686.3  166.31  4817.3   162.4  4837.4  161.65  4886.5  158.24
  4891.5  158.74    4908  157.13  4928.1  156.07  4960.8  154.85  4978.1  154.99
  4983.6  154.31  4993.2  149.04  5003.9  146.97  5004.3  146.47  5008.5  146.47
  5008.8  146.97  5015.3  147.49  5023.6  149.24  5029.1  151.47  5037.4  151.95
  5072.4  152.01  5081.9  153.97  5104.4  155.23  5118.8  154.79    5163  156.82
  5267.8  156.35  5318.7  157.59    5409  158.27    5533  161.38  5608.2  163.92
#Mann= 3 ,-1 , 0
  4581.9     .12       0  5003.9     .05       0  5008.8     .12       0
Bank Sta=5003.9,5008.8
XS Rating Curve= 0 ,0
Exp/Cntr=0.3,0.1

Type RM Length L Ch R = 1 ,1287    ,183,183,183
BEGIN DESCRIPTION:
Mapping XS 57006779
END DESCRIPTION:
XS GIS Cut Line= 4
      2516374.06     13464137.39      2515874.02     13464132.18
      2515751.63     13464095.72      2515324.58     13464429.03
#Sta/Elev= 30
  4448.4  165.41  4587.5  162.68  4697.5  161.67  4727.5  159.59  4777.5  157.41
  4817.5  156.29  4837.5  156.42  4907.5  153.78  4937.5  153.67  4959.6   151.8
  4968.3  152.79  4992.8  150.67  5007.5  144.85  5007.9  144.35  5012.1  144.35
  5012.5  144.85  5020.5  145.95  5025.9  151.69  5041.4  154.85    5087   154.6
  5173.4  156.51  5244.4  156.72  5337.6  157.94  5437.1  160.48  5472.3  162.33
  5507.6  162.91  5571.8  166.07  5579.3  165.75  5600.8  166.79  5617.9  166.78
#Mann= 3 ,-1 , 0
  4448.4     .12       0  5007.5     .05       0  5012.5     .12       0
Bank Sta=5007.5,5012.5
XS Rating Curve= 0 ,0
Exp/Cntr=0.3,0.1

Type RM Length L Ch R = 1 ,1104    ,510,510,510
BEGIN DESCRIPTION:
Mapping XS bac4f483
END DESCRIPTION:
XS GIS Cut Line= 3
      2516405.28     13463975.93      2515832.36     13463931.66
      2515292.08     13464170.63
#Sta/Elev= 30
  4417.4  165.06  4658.4  159.11  4708.5   158.4  4828.9  155.04    4859  153.36
  4878.9  151.51  4883.9  151.85  4899.1  149.97  4909.1   149.6  4949.3  149.66
  4960.6  151.02  4969.3  151.57  4985.7  143.98    4986  143.48  4990.3  143.48
  4990.7  143.98    4992  143.98  5009.1  150.23  5021.9  152.69  5032.4  152.45
  5037.9  153.12  5061.1  151.65  5066.1   152.6  5089.9  151.91  5098.5  150.95
  5107.7  151.01  5159.8  155.47  5484.5  162.28  5559.9  164.64  5582.8  165.98
#Mann= 5 ,-1 , 0
  4417.4     .12       0  4960.6     .07       0  4985.7     .05       0
  4990.7     .07       0  5066.1     .12       0
Bank Sta=4985.7,4990.7
XS Rating Curve= 0 ,0
Exp/Cntr=0.3,0.1

Type RM Length L Ch R = 1 ,594     ,436,436,436
BEGIN DESCRIPTION:
Mapping XS 9cdc3433
END DESCRIPTION:
XS GIS Cut Line= 4
      2516410.48     13463658.22      2516027.67      13463517.6
      2515790.69     13463533.22      2515303.68     13463866.58
#Sta/Elev= 30
  4489.8  165.07  4708.7  158.39    4730  158.83  4751.3  157.46  4776.3  157.36
  4857.1  154.94  4934.8  154.05  4951.8  153.23  4970.5   149.9  4987.9  142.48
  4988.3  141.98  4992.6  141.98    4993  142.48  5000.5  145.34  5010.5  146.87
  5020.6   146.5  5040.6  149.51  5050.5  149.71  5060.6  149.87  5085.9  152.94
  5110.8  153.71  5226.8  152.38  5335.9  153.88  5449.6  156.41  5551.1  160.13
  5572.1  159.83    5587  161.03  5593.1  160.57  5622.9  162.07  5725.3  163.96
#Mann= 5 ,-1 , 0
  4489.8     .12       0  4951.8     .07       0  4987.9     .05       0
    4993     .07       0  5050.5     .12       0
Bank Sta=4987.9,4993
XS Rating Curve= 0 ,0
Exp/Cntr=0.3,0.1

Type RM Length L Ch R = 1 ,158     ,0,0,0
BEGIN DESCRIPTION:
BLUE BRANCH 1.0
END DESCRIPTION:
XS GIS Cut Line= 4
       2516538.1     13463181.66       2516152.9     13463055.39
      2515632.78     13463231.22      2515223.59     13463670.59
#Sta/Elev= 30
  4045.6   163.2    4148  161.62  4344.3  154.39  4447.2  152.04    4491  151.44
  4559.3   152.7  4564.9     152  4585.5  151.71  4818.2  152.06  4860.4  151.68
  4885.6  149.78  4931.4  146.93  4968.1  148.73  4987.1  147.61  4994.3   145.5
  4998.1  142.54    5002  142.54  5005.5  140.82  5005.9  140.32  5010.6  140.82
  5022.2  147.05  5029.5  146.83  5036.4  149.03  5093.1  150.58  5156.6  153.92
  5238.2  157.05  5307.3  159.54  5475.1  165.53  5588.5  167.81  5600.4   168.6
#Mann= 6 ,-1 , 0
  4045.6     .12       0  4885.6     .07       0  5005.5     .05       0
  5010.6     .07       0  5238.2     .12       0  5307.3     .07       0
Bank Sta=5005.5,5010.6
XS Rating Curve= 0 ,0
Exp/Cntr=0.3,0.1

Chan Stop Cuts=-1
Use User Specified Reach Order=0
Composite Channel Slope=5