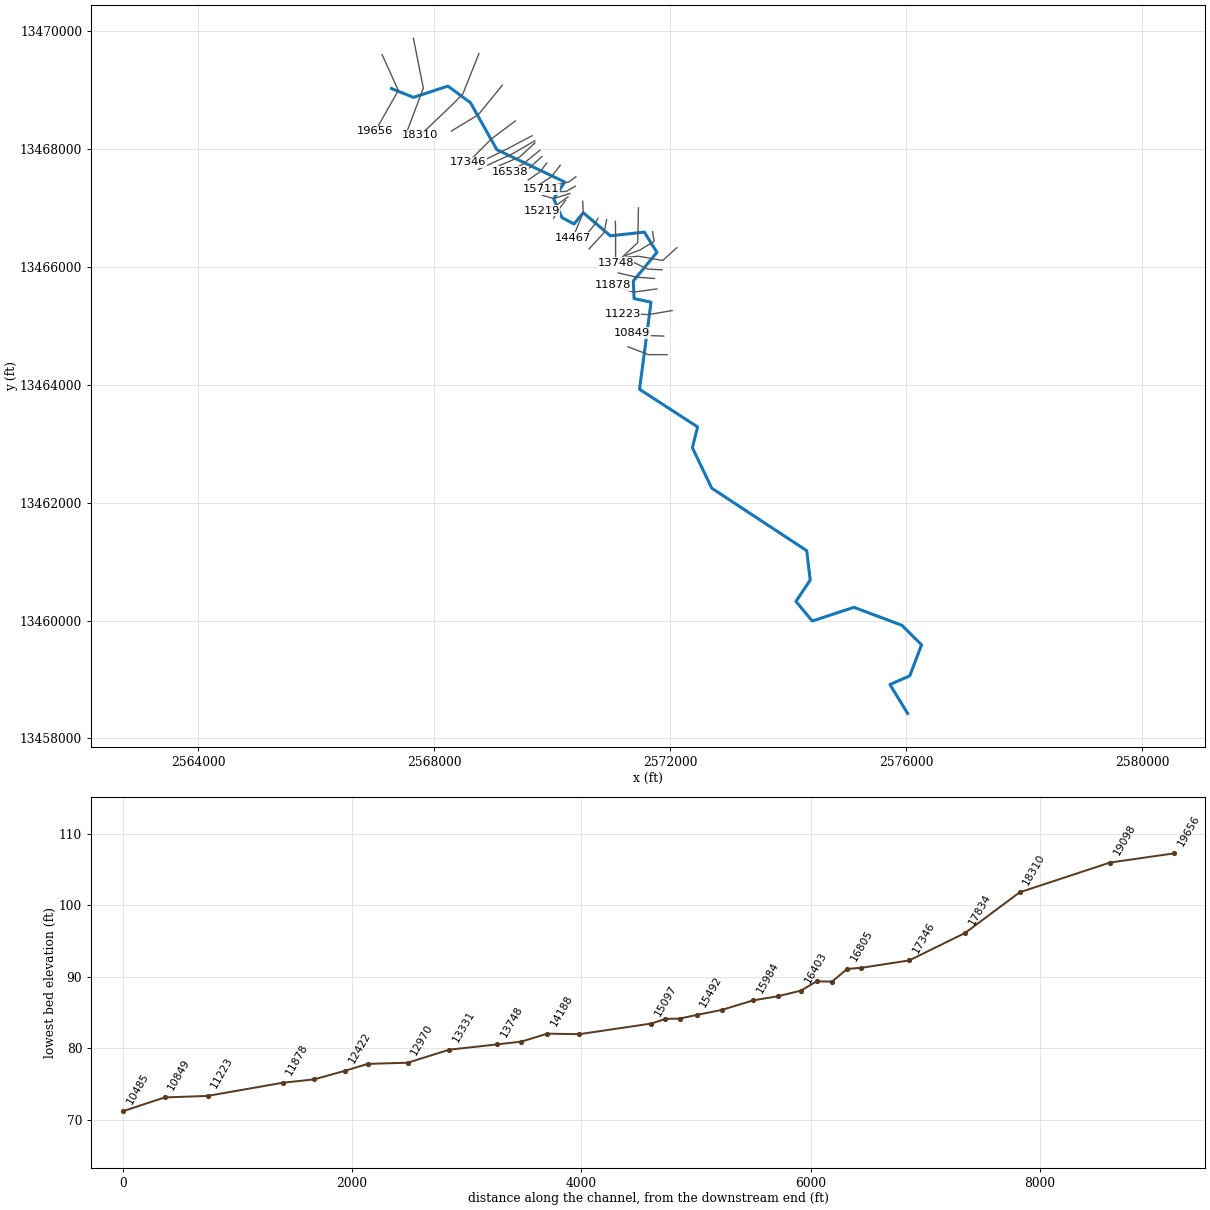
--- BOGGY CREEK.prj (project) ---

Proj Title=BOGGY CREEK Base Level Engineering
Current Plan=p01
Default Exp/Contr=0.3,0.1
English Units
Geom File=g01
Flow File=f01
Plan File=p01
Y Axis Title=Elevation
X Axis Title(PF)=Main Channel Distance
X Axis Title(XS)=Station
BEGIN DESCRIPTION:
BOGGY CREEK
END DESCRIPTION:
DSS Export Rating Curves= 0
DSS Export Rating Curve Sorted= 0
DSS Export Volume Flow Curves= 0
DXF OffsetX= 0
DXF OffsetY= 0
DXF ScaleX= 1
DXF ScaleY= 10

--- BOGGY CREEK.p01 (plan) ---

Plan Title=Multiple Run
Program Version=4.10
Short Identifier=Multiple
Geom File=g01
Flow File=f01
Subcritical Flow
K Sum by GR= 0
Std Step Tol= 0.01
Critical Tol= 0.01
Num of Std Step Trials= 20
Max Error Tol= 0.3
Flow Tol Ratio= 0.001
Split Flow NTrial= 30
Split Flow Tol= 0.02
Split Flow Ratio= 0.02
Log Output Level= 0
Friction Slope Method= 1
Unsteady Friction Slope Method= 2
Unsteady Bridges Friction Slope Method= 1
Parabolic Critical Depth
Global Vel Dist= 1 , 1 , 1
Global Log Level= 0
CheckData=True
Encroach Param=-1 ,0,0, 0
BEGIN DESCRIPTION:
Multiple Run
END DESCRIPTION:
Computation Interval=1HOUR
Output Interval=1HOUR
Run HTab= 0
Run UNet= 0
Run PostProcess= 0
Run WQNet= 0
UNET Theta= 1
UNET Theta Warmup= 1
UNET ZTol= 0.02
UNET ZSATol= 0.05
UNET MxIter= 20
UNET MaxInSteps= 0
UNET DtIC= 0
UNET DtMin= 0
UNET MaxCRTS= 20
UNET WFStab= 2
UNET SFStab= 1
UNET WFX= 1
UNET SFX= 1
UNET DSS MLevel= 4
UNET DZMax Abort= 100
UNET Convert EG Bridges= 0
UNET Use Existing IB Tables=-1
UNET Froude Reduction=False
UNET Froude Limit= 1
UNET Froude Power= 10
UNET Time Slicing=0,0, 5
UNET Junction Losses=0
Instantaneous Interval=1HOUR
Write IC File= 0
Write IC File at Sim End=0
Echo Input=False
Echo Parameters=False
Echo Output=False
Write Detailed= 0
WQ AD Non Conservative
WQ ULTIMATE=-1
WQ Max Comp Step=1HOUR
WQ Output Interval=15MIN
WQ Output Selected Increments= 0
WQ Output face flow=0
WQ Output face velocity=0
WQ Output face area=0
WQ Output face dispersion=0
WQ Output cell volume=0
WQ Output cell surface area=0
WQ Output cell continuity=0
WQ Output cumulative cell continuity=0
WQ Output face conc=0
WQ Output face dconc_dx=0
WQ Output face courant=0
WQ Output face peclet=0
WQ Output face adv mass=0
WQ Output face disp mass=0
WQ Output cell mass=0
WQ Output cell source sink temp=0
WQ Output cell source sink nsm=0
WQ Output MaxMinRange=-1
WQ Daily Max Min Mean=-1
WQ Daily Range=0
WQ Daily Time=0
WQ Create Restart=0
WQ Fixed Restart=0
WQ System Summary=0
WQ Use Fixed Temperature=0
Sorting and Armoring Iterations= 10
XS Update Threshold= 0.02
Hydraulics Update Threshold= 0.02
Energy Slope Method= 1
Volume Change Method= 0
XS Weighting Method= 0
Number of US Weighted Cross Sections= 1
Number of DS Weighted Cross Sections= 1
Upstream XS Weight=0.25
Main XS Weight=0.5
Downstream XS Weight=0.25
Number of DS XS's Weighted with US Boundary= 1
Upstream Boundary Weight= 1
Weight of XSs Associated with US Boundary= 0
Number of US XS's Weighted with DS Boundary= 1
Downstream Boundary Weight= 0.5
Weight of XSs Associated with DS Boundary= 0.5
Sediment Output Level= 4
Mass or Volume Output= 0
Output Increment Type= 1
Profile and TS Output Increment= 10
XS Output Flag= 0
XS Output Increment= 10
Disregard all LS=0
Disregard all Conn=0
Disregard all Breaches=0
Disregard all Pumps=0

--- BOGGY CREEK.f01 (steady flow) ---

Flow Title=Multiple
Number of Profiles=7
Profile Names=10-year,25-year,50-year,1pct_min,100-year,1pct_plu,500-year
River Rch & RM= BOGGY CREEK,Reach-1,19656
     494     754     974     609    1215    2424    1865
River Rch & RM= BOGGY CREEK,Reach-1,18310
    1060    1701    2275    1468    2928    5843    4800
River Rch & RM= BOGGY CREEK,Reach-1,13331
    1345    2185    2947    1916    3823    7629    6366
River Rch & RM= BOGGY CREEK,Reach-1,12422
    1380    2245    3030    1972    3934    7850    6560
River Rch & RM= BOGGY CREEK,Reach-1,10252
    1546    2526    3421    2232    4454    8886    7469
River Rch & RM= BOGGY CREEK,Reach-1,7281
    2451    4099    5636    3731    7444   14853   12850
Boundary for River Rch & Prof#=BOGGY CREEK,Reach-1,1
Up Type=0
Dn Type=3
Dn Slope=0.005
Boundary for River Rch & Prof#=BOGGY CREEK,Reach-1,2
Up Type=0
Dn Type=3
Dn Slope=0.005
Boundary for River Rch & Prof#=BOGGY CREEK,Reach-1,3
Up Type=0
Dn Type=3
Dn Slope=0.005
Boundary for River Rch & Prof#=BOGGY CREEK,Reach-1,4
Up Type=0
Dn Type=3
Dn Slope=0.005
Boundary for River Rch & Prof#=BOGGY CREEK,Reach-1,5
Up Type=0
Dn Type=3
Dn Slope=0.005
Boundary for River Rch & Prof#=BOGGY CREEK,Reach-1,6
Up Type=0
Dn Type=3
Dn Slope=0.005
Boundary for River Rch & Prof#=BOGGY CREEK,Reach-1,7
Up Type=0
Dn Type=3
Dn Slope=0.005

--- BOGGY CREEK.g01 (geometry) ---

Geom Title=Existing Conditions
Program Version=4.10

River Reach=BOGGY CREEK     ,Reach-1
Reach XY= 30
        2567275.       13469025.      2567649.85     13468874.42
      2568231.67     13469065.71      2568614.39     13468785.06
      2569061.26     13467988.38      2570212.07     13467438.61
       2570024.7     13467154.83       2570165.3     13466835.77
      2570369.13      13466726.5      2570528.32     13466917.42
       2570985.5      13466526.2       2571561.8     13466588.74
       2571775.5     13466245.23      2571375.38     13465759.85
      2571388.19     13465461.26      2571675.44     13465400.41
      2571480.46     13463922.55      2572464.25      13463284.7
      2572376.59     13462931.05      2572704.91     13462244.78
      2574314.37       13461185.       2574373.8      13460685.5
      2574132.28     13460325.09      2574408.32     13459991.22
      2575114.56     13460223.94      2575927.55     13459919.27
      2576261.63     13459588.32      2576061.56     13459061.36
      2575725.54     13458914.37        2576025.       13458425.

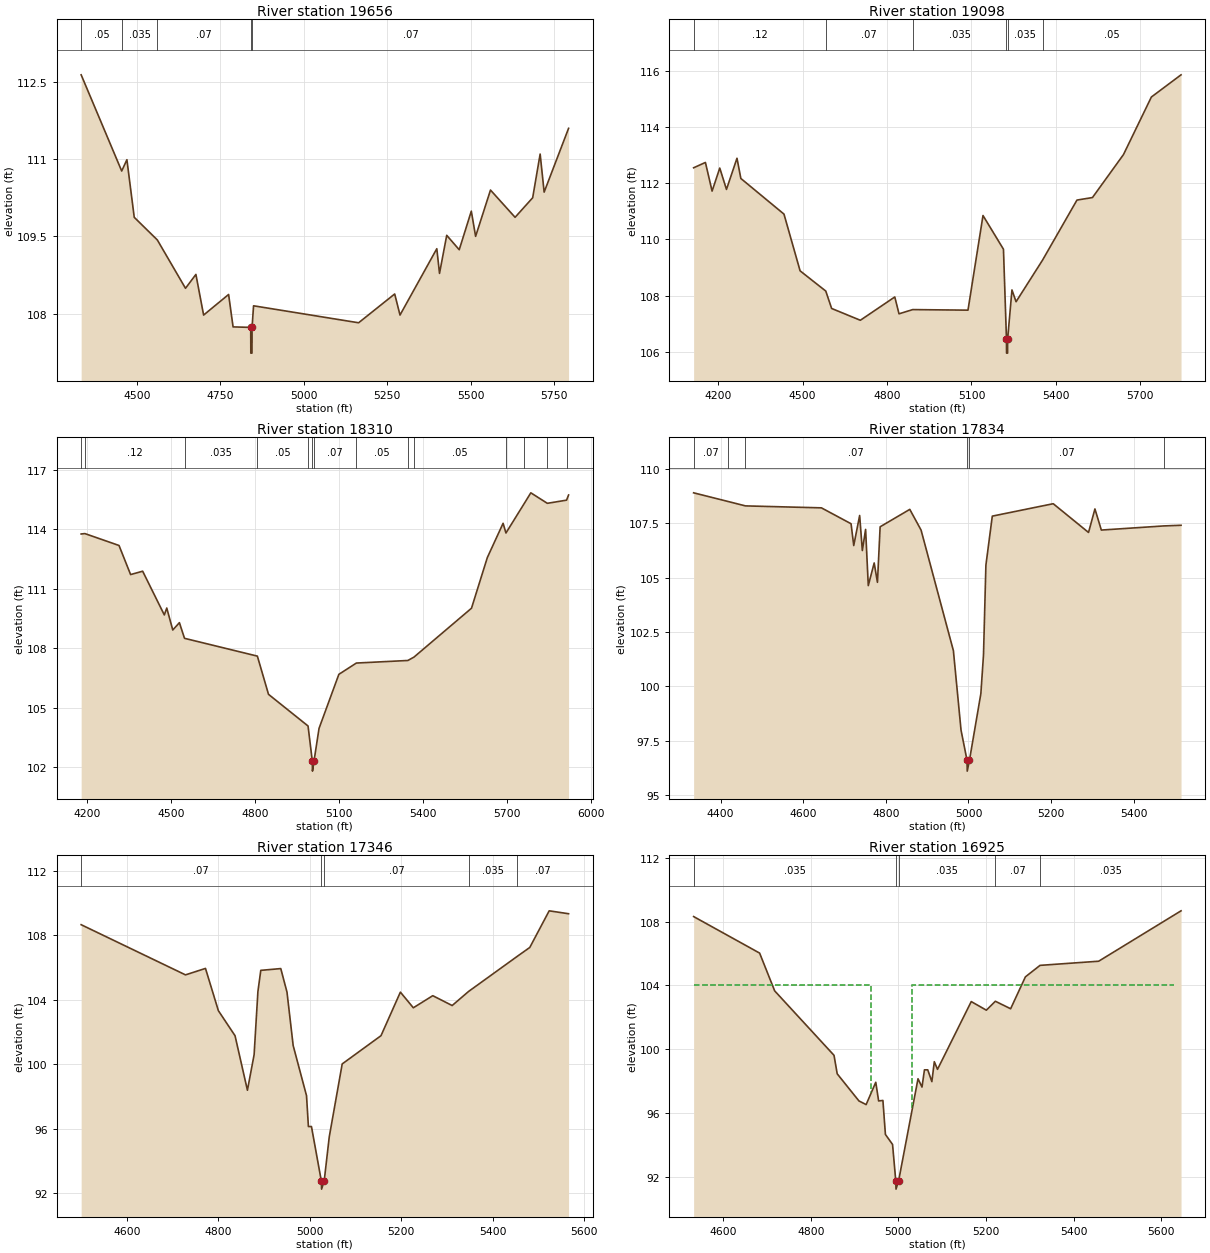
Type RM Length L Ch R = 1 ,19656   ,558,558,558
BEGIN DESCRIPTION:
BOGGY CREEK 41.0
END DESCRIPTION:
XS GIS Cut Line= 3
      2567116.88     13469599.99      2567391.53     13468991.83
      2567000.56     13468301.33
#Sta/Elev= 30
  4332.7  112.64  4454.2  110.77  4469.8  110.99  4491.8  109.87    4561  109.43
  4645.4  108.49  4676.6  108.76  4699.7  107.97  4774.6  108.37    4788  107.74
  4840.9  107.73  4841.2  107.23  4844.7  107.23  4844.9  107.73  4849.4  108.15
  5164.2  107.82  5272.4  108.38  5288.3  107.97  5398.6  109.26  5406.7  108.78
  5428.3  109.52  5465.8  109.24    5502  109.99  5514.9   109.5  5559.5   110.4
  5633.2  109.87  5685.9  110.25  5708.3   111.1  5720.3  110.36  5793.5   111.6
#Mann= 5 ,-1 , 0
  4332.7     .05       0  4454.2    .035       0    4561     .07       0
  4840.9     .05       0  4844.9     .07       0
Bank Sta=4840.9,4844.9
XS Rating Curve= 0 ,0
Exp/Cntr=0.3,0.1

Type RM Length L Ch R = 1 ,19098   ,788,788,788
BEGIN DESCRIPTION:
Mapping XS 4e851601
END DESCRIPTION:
XS GIS Cut Line= 3
      2567647.54      13469876.1      2567815.68     13469031.39
      2567508.65     13468216.38
#Sta/Elev= 30
  4112.6  112.55  4154.5  112.74  4178.2  111.72  4205.5  112.54  4229.3  111.78
  4266.7  112.89  4280.4  112.17  4433.7   110.9    4491  108.88  4582.2  108.16
  4603.1  107.54  4705.1  107.12  4827.5  107.95  4842.5  107.35  4891.2   107.5
  5087.6  107.48    5141  110.85  5213.7  109.65  5224.4  106.45  5224.7  105.95
  5228.3  105.95  5228.5  106.45  5243.9   108.2  5258.5  107.78  5352.5  109.26
  5474.9   111.4    5530  111.49  5640.2  113.02  5739.4  115.07  5844.8  115.86
#Mann= 6 ,-1 , 0
  4112.6     .12       0  4582.2     .07       0  4891.2    .035       0
  5224.4    .035       0  5228.5    .035       0  5352.5     .05       0
Bank Sta=5224.4,5228.5
XS Rating Curve= 0 ,0
Exp/Cntr=0.3,0.1

Type RM Length L Ch R = 1 ,18310   ,476,476,476
BEGIN DESCRIPTION:
Mapping XS b599a840
END DESCRIPTION:
XS GIS Cut Line= 4
      2568758.66     13469619.19      2568487.82      13468938.6
      2568331.57     13468775.41      2567765.63     13468233.77
#Sta/Elev= 30
  4177.8  113.77  4191.2  113.79  4313.1  113.19  4354.5  111.72  4397.6  111.89
    4475  109.68  4483.7  110.03  4505.2  108.92  4528.9  109.29  4547.1   108.5
  4807.5   107.6  4847.3  105.67  4988.6  104.07  5003.9  102.29  5004.4  101.79
  5009.8  102.29  5027.9  103.95  5098.7  106.68  5161.3  107.25  5345.3  107.38
  5367.1  107.55  5572.7  110.02  5629.3  112.58  5685.6  114.31  5695.8  113.82
  5759.4  115.27  5784.7  115.85  5843.7  115.32  5912.4  115.48  5919.6  115.74
#Mann= 14 ,-1 , 0
  4177.8     .07       0  4191.2     .12       0  4547.1    .035       0
  4807.5     .05       0  4988.6     .07       0  5003.9     .05       0
  5009.8     .07       0  5161.3     .05       0  5345.3    .035       0
  5367.1     .05       0  5695.8     .07       0  5759.4     .05       0
  5843.7     .07       0  5912.4     .05       0
Bank Sta=5003.9,5009.8
XS Rating Curve= 0 ,0
Exp/Cntr=0.3,0.1

Type RM Length L Ch R = 1 ,17834   ,488,488,488
BEGIN DESCRIPTION:
Mapping XS 6c25ec82
END DESCRIPTION:
XS GIS Cut Line= 3
      2569154.48     13469080.96      2568744.76     13468577.49
      2568289.97     13468303.23
#Sta/Elev= 30
  4334.5  108.89  4418.4  108.49  4459.9  108.29  4643.9   108.2  4715.7  107.47
  4722.2  106.47  4736.5  107.85    4743  106.24  4750.9  107.21  4757.4  104.63
  4771.7  105.67  4779.6  104.78  4786.1  107.33  4857.9  108.13  4885.2  107.18
  4963.5  101.64    4982   97.99  4996.5   96.61    4997   96.11  5002.4   96.61
    5030   99.67  5036.4  101.46  5042.2  105.57  5057.7  107.82  5205.2  108.39
  5290.7  107.07  5306.2  108.15  5321.7  107.18  5473.2  107.37  5514.7   107.4
#Mann= 6 ,-1 , 0
  4334.5     .07       0  4418.4     .12       0  4459.9     .07       0
  4996.5     .05       0  5002.4     .07       0  5473.2    .035       0
Bank Sta=4996.5,5002.4
XS Rating Curve= 0 ,0
Exp/Cntr=0.3,0.1

Type RM Length L Ch R = 1 ,17346   ,421,421,421
BEGIN DESCRIPTION:
BOGGY CREEK 37.0
END DESCRIPTION:
XS GIS Cut Line= 3
      2569374.97     13468474.98        2568975.       13468175.
      2568575.03     13467775.03
#Sta/Elev= 30
  4500.1  108.66  4728.2  105.55  4771.9  105.95  4800.1  103.33  4836.5  101.78
  4863.6    98.4  4878.2   100.6  4886.5  104.51  4892.8  105.83  4936.5  105.94
  4950.1  104.48  4963.6  101.17  4992.8   98.06  4996.9   96.15  5003.6   96.15
  5025.2   92.77  5025.7   92.27  5031.4   92.77  5042.5   95.51  5070.8  100.03
  5155.6  101.78    5198  104.48  5226.3  103.51  5268.8  104.26  5311.2  103.65
    5347  104.52  5453.6   106.7  5480.9  107.25  5523.3  109.52  5565.7  109.34
#Mann= 5 ,-1 , 0
  4500.1     .07       0  5025.2     .05       0  5031.4     .07       0
    5347    .035       0  5453.6     .07       0
Bank Sta=5025.2,5031.4
XS Rating Curve= 0 ,0
Exp/Cntr=0.3,0.1

Type RM Length L Ch R = 1 ,16925   ,120,120,120
BEGIN DESCRIPTION:
BOGGY CREEK 36.0
END DESCRIPTION:
XS GIS Cut Line= 3
      2569658.13      13468224.1      2569245.15     13468005.42
      2568666.33     13467720.61
#Sta/Elev= 30
  4532.7  108.32  4683.3  106.03  4717.7  103.66  4853.1   99.62  4860.4   98.46
    4910   96.76  4926.4   96.53  4948.4   97.93  4954.9   96.76  4964.7   96.79
  4970.4   94.66  4986.7   94.03  4994.1   91.73  4994.6   91.23  5000.4   91.73
  5044.8   98.15  5053.9   97.63  5059.5   98.71    5067   98.71  5076.4   97.97
    5082   99.22  5089.3   98.74  5166.3  102.99  5200.8  102.45  5221.3  103.01
  5256.2  102.54  5289.9  104.54  5323.3  105.26  5457.1  105.52  5645.1  108.68
#Mann= 5 ,-1 , 0
  4532.7    .035       0  4994.1    .035       0  5000.4    .035       0
  5221.3     .07       0  5323.3    .035       0
#XS Ineff= 2 ,-1
    4532    4938     104    5032    5628     104
Permanent Ineff=
       F       F
Bank Sta=4994.1,5000.4
XS Rating Curve= 0 ,0
Exp/Cntr=0.3,0.1

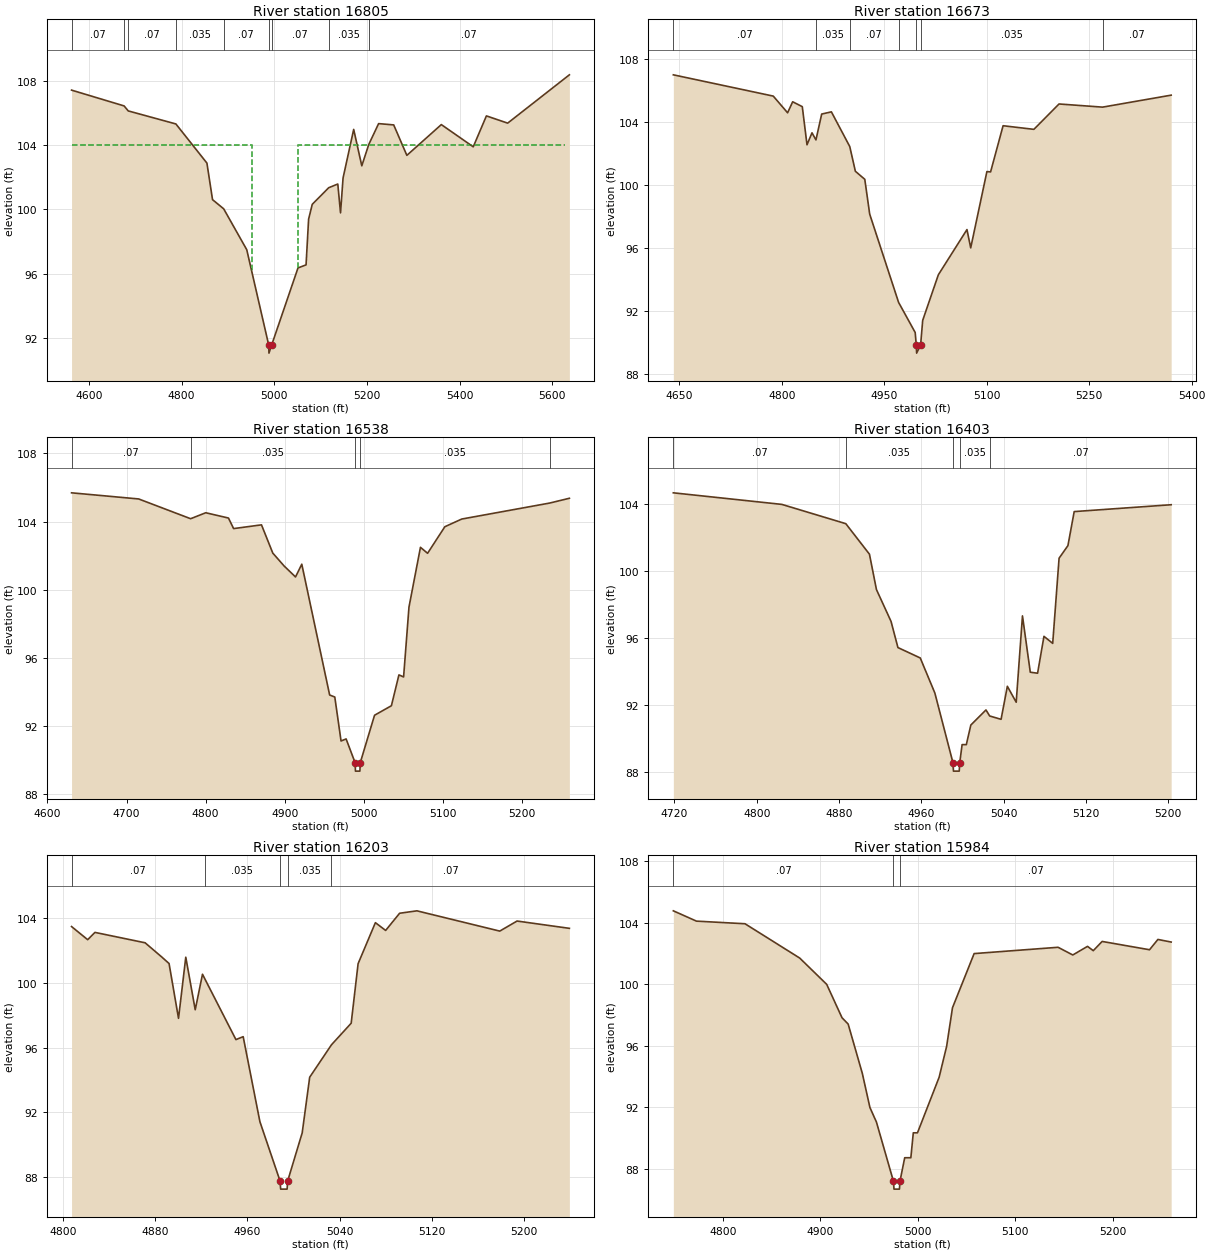
Type RM Length L Ch R = 1 ,16805   ,132,132,132
BEGIN DESCRIPTION:
Mapping XS 1424a38e
END DESCRIPTION:
XS GIS Cut Line= 3
      2569708.06     13468139.48      2569334.78     13467922.45
        2568751.     13467653.35
#Sta/Elev= 30
  4562.5  107.41  4675.9  106.43  4684.8  106.12  4787.7  105.31  4854.7  102.88
  4866.8  100.61  4890.9  100.04  4940.7    97.5  4988.1   91.58  4988.6   91.08
  4994.4   91.58  5051.3   96.37  5068.7   96.56  5074.2    99.4  5082.1  100.32
  5117.6  101.35  5137.2  101.58  5143.1   99.79  5148.6  101.96  5171.5  104.97
    5189  102.71    5204  104.03  5225.3  105.33  5257.9  105.25  5286.3  103.36
  5360.7  105.27  5429.6  103.89    5458  105.81  5503.9  105.36  5637.1  108.36
#Mann= 9 ,-1 , 0
  4562.5     .07       0  4675.9    .035       0  4684.8     .07       0
  4787.7    .035       0  4890.9     .07       0  4988.1     .05       0
  4994.4     .07       0  5117.6    .035       0    5204     .07       0
#XS Ineff= 2 ,-1
    4562    4952     104    5052    5628     104
Permanent Ineff=
       F       F
Bank Sta=4988.1,4994.4
XS Rating Curve= 0 ,0
Exp/Cntr=0.3,0.1

Type RM Length L Ch R = 1 ,16673   ,135,135,135
BEGIN DESCRIPTION:
Mapping XS ae4f97b6
END DESCRIPTION:
XS GIS Cut Line= 3
      2569705.71     13468100.94      2569448.76     13467863.08
      2569099.91     13467715.56
#Sta/Elev= 30
  4641.1  106.97  4787.4  105.62  4808.4  104.56  4815.8  105.26  4829.9  104.95
  4836.8  102.53  4844.1  103.29  4849.9  102.84  4858.3  104.48  4872.5  104.62
  4899.4  102.42  4907.6  100.85  4921.4  100.34  4928.6   98.13  4970.9   92.53
  4995.2   90.62  4996.8   89.81  4997.3   89.31  5003.1   89.81  5006.2   91.39
  5029.1   94.28    5071   97.15  5076.5   95.99  5100.2  100.83  5105.6  100.81
  5123.9  103.74    5169  103.51  5205.8  105.12  5269.6  104.92    5370  105.68
#Mann= 7 ,-1 , 0
  4641.1     .07       0  4849.9    .035       0  4899.4     .07       0
  4970.9    .035       0  4996.8    .035       0  5003.1    .035       0
  5269.6     .07       0
Bank Sta=4996.8,5003.1
XS Rating Curve= 0 ,0
Exp/Cntr=0.3,0.1

Type RM Length L Ch R = 1 ,16538   ,135,135,135
BEGIN DESCRIPTION:
Mapping XS 9945c60b
END DESCRIPTION:
XS GIS Cut Line= 3
      2569790.75     13467977.65      2569516.46     13467753.71
      2569282.45     13467609.83
#Sta/Elev= 30
  4630.6  105.69  4715.4  105.33    4781  104.17  4800.1  104.52  4828.8  104.21
  4835.3  103.59  4870.5  103.81  4884.8  102.15  4899.2  101.39  4913.5  100.75
  4921.4   101.5  4956.6   93.82  4963.1    93.7    4971   91.12  4977.4   91.24
  4988.7   89.85  4989.2   89.35  4994.8   89.35  4995.3   89.85  5013.3   92.63
  5034.6   93.19  5044.1      95    5050   94.88  5056.8   98.98  5071.3  102.49
  5080.3  102.14  5102.1   103.7  5123.4  104.15  5234.6  105.09  5259.4  105.37
#Mann= 5 ,-1 , 0
  4630.6     .07       0    4781    .035       0  4988.7    .035       0
  4995.3    .035       0  5234.6     .07       0
Bank Sta=4988.7,4995.3
XS Rating Curve= 0 ,0
Exp/Cntr=0.3,0.1

Type RM Length L Ch R = 1 ,16403   ,200,200,200
BEGIN DESCRIPTION:
Mapping XS 27d61993
END DESCRIPTION:
XS GIS Cut Line= 3
       2569827.2     13467871.74      2569617.16     13467682.53
      2569453.97     13467564.48
#Sta/Elev= 30
  4718.9  104.66  4824.4  103.97  4886.6  102.82  4909.6     101  4916.4   98.89
  4930.6   96.99  4937.3   95.43    4959   94.81  4973.2   92.72  4990.8   88.56
  4991.3   88.06  4996.9   88.06  4997.4   88.56  4999.7   89.64  5003.8   89.64
  5008.2   90.81  5022.9   91.71  5026.5   91.35  5037.6   91.15  5043.7   93.12
  5052.3   92.17  5058.4   97.32    5066   93.96  5073.1    93.9  5079.3    96.1
  5087.8   95.68    5094  100.76  5102.6  101.51  5108.7  103.54    5203  103.95
#Mann= 5 ,-1 , 0
  4718.9     .07       0  4886.6    .035       0  4990.8    .035       0
  4997.4    .035       0  5026.5     .07       0
Bank Sta=4990.8,4997.4
XS Rating Curve= 0 ,0
Exp/Cntr=0.3,0.1

Type RM Length L Ch R = 1 ,16203   ,219,219,219
BEGIN DESCRIPTION:
Mapping XS da4f2a98
END DESCRIPTION:
XS GIS Cut Line= 3
      2569908.85     13467760.68      2569790.77     13467607.88
      2569592.89     13467474.22
#Sta/Elev= 30
  4807.5  103.46  4821.5  102.65  4827.8   103.1  4871.3  102.46  4885.8  101.58
  4892.1  101.18  4900.3    97.8  4906.6  101.57  4914.8   98.33  4921.1  100.52
  4923.1  100.24  4950.1   96.49  4956.4   96.67  4970.9   91.43  4988.4   87.77
  4988.9   87.27  4994.5   87.27    4995   87.77  5007.6   90.74  5014.1   94.17
    5033   96.17  5050.1    97.5  5056.1  101.17  5071.1   103.7    5080  103.22
  5092.1  104.28  5107.1  104.43    5179  103.18    5194   103.8  5239.4  103.35
#Mann= 5 ,-1 , 0
  4807.5     .07       0  4923.1    .035       0  4988.4    .035       0
    4995    .035       0    5033     .07       0
Bank Sta=4988.4,4995
XS Rating Curve= 0 ,0
Exp/Cntr=0.3,0.1

Type RM Length L Ch R = 1 ,15984   ,273,273,273
BEGIN DESCRIPTION:
Mapping XS 0a2e399c
END DESCRIPTION:
XS GIS Cut Line= 3
      2570138.01     13467724.22      2569986.95     13467529.75
      2569766.46     13467383.92
#Sta/Elev= 30
  4749.2  104.78  4772.9  104.11  4822.7  103.94  4878.8  101.71  4906.5     100
  4922.2   97.83  4928.5   97.42    4943   94.22  4950.8      92  4957.5   91.05
    4975   87.19  4975.5   86.69  4981.1   86.69  4981.6   87.19  4986.5   88.73
  4992.8   88.73  4995.3   90.35  4999.6   90.35  5021.8   93.96  5029.5   95.97
  5035.5   98.48  5057.7     102  5143.8  102.41  5158.9  101.91    5174  102.47
  5179.9  102.19    5189  102.79  5237.6  102.25  5246.2  102.92  5259.8  102.75
#Mann= 3 ,-1 , 0
  4749.2     .07       0    4975     .05       0  4981.6     .07       0
Bank Sta=4975,4981.6
XS Rating Curve= 0 ,0
Exp/Cntr=0.3,0.1

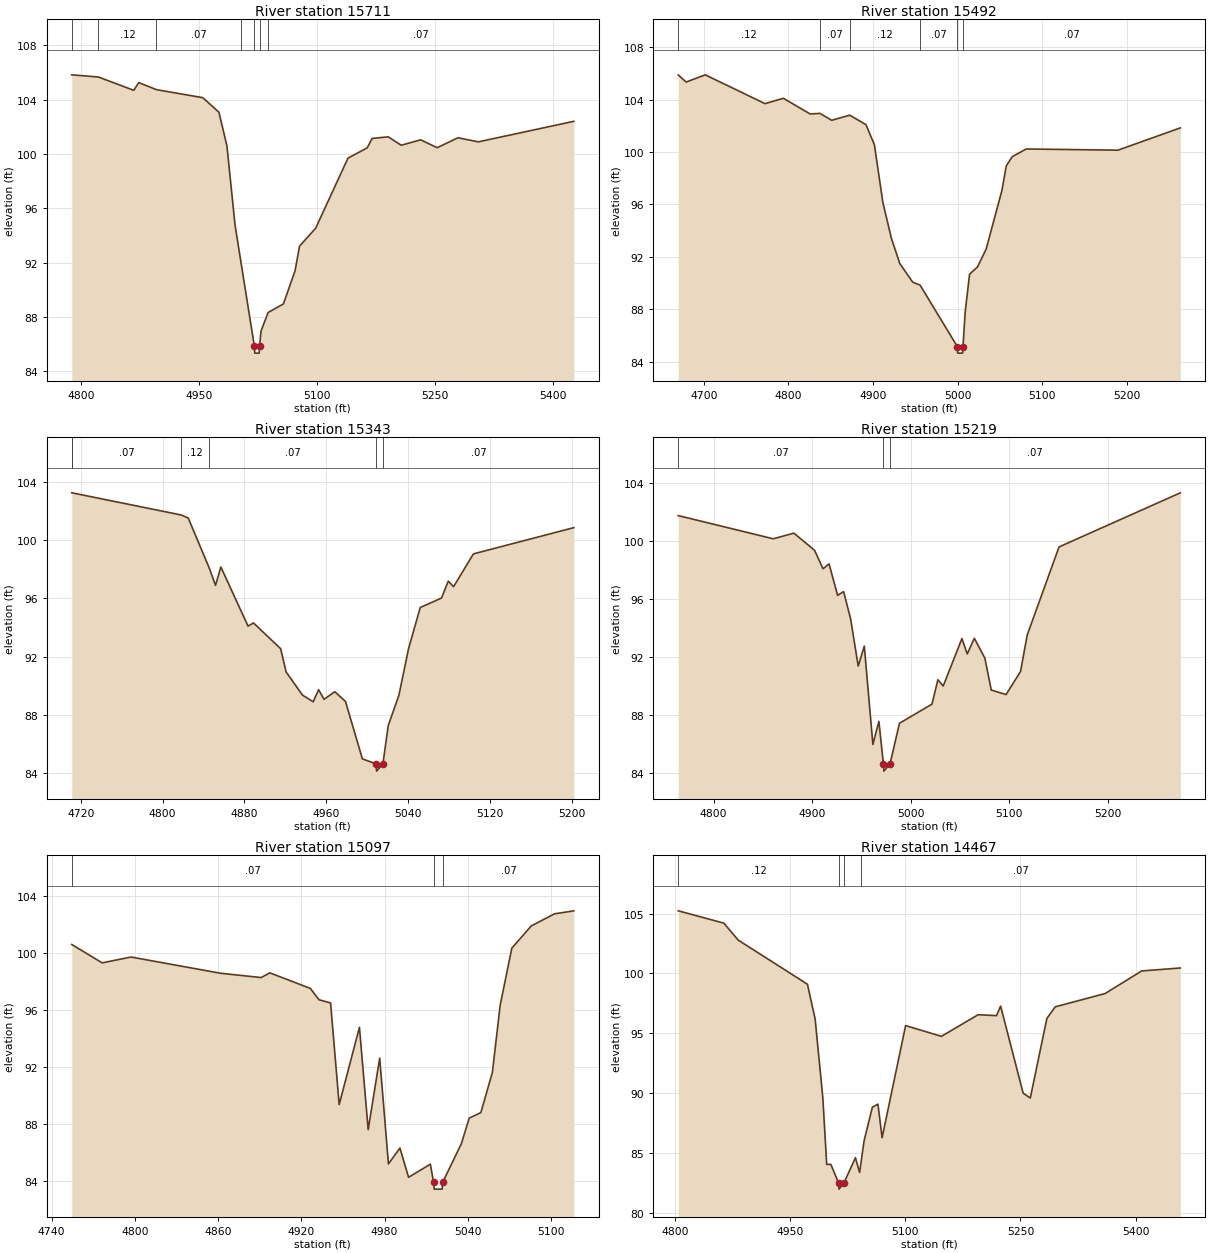
Type RM Length L Ch R = 1 ,15711   ,219,219,219
BEGIN DESCRIPTION:
Mapping XS fe5682eb
END DESCRIPTION:
XS GIS Cut Line= 4
      2570401.87       13467528.      2570282.09     13467439.47
      2570004.31     13467376.97      2569809.03     13467316.49
#Sta/Elev= 30
  4788.4  105.82  4822.3  105.66  4867.2  104.68  4873.5  105.25    4896  104.73
  4954.9  104.14  4975.4  103.07  4985.6   100.6  4995.9   94.78  5002.9   92.23
  5020.5   85.85    5021   85.35  5026.6   85.35  5027.1   85.85  5028.9   86.97
    5038   88.34  5057.4   88.97  5072.2   91.41  5077.9   93.22  5098.4   94.54
  5139.4   99.69  5163.9  100.45  5170.1  101.14  5190.6  101.26  5207.1  100.64
  5231.8  101.04  5252.8  100.46  5279.2  101.19  5305.1  100.89  5426.5   102.4
#Mann= 7 ,-1 , 0
  4788.4    .035       0  4822.3     .12       0    4896     .07       0
  5002.9     .12       0  5020.5     .05       0  5027.1     .12       0
    5038     .07       0
Bank Sta=5020.5,5027.1
XS Rating Curve= 0 ,0
Exp/Cntr=0.3,0.1

Type RM Length L Ch R = 1 ,15492   ,149,149,149
BEGIN DESCRIPTION:
Mapping XS ad3ffc08
END DESCRIPTION:
XS GIS Cut Line= 5
      2570393.18     13467368.28      2570233.48     13467278.01
      2570139.73     13467276.28      2570007.78     13467305.79
      2569832.42     13467260.65
#Sta/Elev= 30
  4669.7  105.88  4679.1  105.34  4701.6  105.89  4772.3  103.69    4794   104.1
  4825.7   102.9  4837.2  102.95  4851.1  102.42  4872.4  102.81  4891.6  102.09
  4901.6  100.55  4911.6   96.15  4921.6   93.43  4931.6   91.49  4946.8   90.07
  4955.6   89.84  4999.6   85.15  5000.1   84.65  5005.8   84.65  5006.3   85.15
  5008.9   87.79  5014.1   90.68  5023.5   91.23  5033.7   92.59  5052.3   97.06
  5057.5   98.94  5064.5   99.64    5081  100.23  5189.5  100.14  5263.2  101.84
#Mann= 6 ,-1 , 0
  4669.7     .12       0  4837.2     .07       0  4872.4     .12       0
  4955.6     .07       0  4999.6     .05       0  5006.3     .07       0
Bank Sta=4999.6,5006.3
XS Rating Curve= 0 ,0
Exp/Cntr=0.3,0.1

Type RM Length L Ch R = 1 ,15343   ,124,124,124
BEGIN DESCRIPTION:
Mapping XS ebb00c95
END DESCRIPTION:
XS GIS Cut Line= 3
      2570299.46     13467245.03      2570028.62     13467156.49
      2569830.69     13467213.78
#Sta/Elev= 30
  4711.2  103.24  4711.4  103.24  4818.2  101.72  4825.1  101.51  4845.3   98.14
  4851.8   96.89    4857   98.15  4883.6   94.09  4888.9   94.31  4915.5   92.54
  4920.8   90.95  4936.8   89.36  4947.3    88.9  4952.6   89.73  4957.9   89.07
  4968.4   89.59  4978.9   88.92  4995.4   84.98  5008.8   84.64  5009.3   84.14
  5015.5   84.64  5020.7   87.27  5031.1   89.34  5040.5   92.53    5052   95.37
  5072.8   96.02  5079.4   97.18  5084.6    96.8    5104   99.05  5202.2  100.85
#Mann= 6 ,-1 , 0
  4711.2     .12       0  4711.4     .07       0  4818.2     .12       0
  4845.3     .07       0  5008.8     .05       0  5015.5     .07       0
Bank Sta=5008.8,5015.5
XS Rating Curve= 0 ,0
Exp/Cntr=0.3,0.1

Type RM Length L Ch R = 1 ,15219   ,122,122,122
BEGIN DESCRIPTION:
Mapping XS ef693d9b
END DESCRIPTION:
XS GIS Cut Line= 3
       2570268.2       13467186.      2570075.49     13467050.58
      2569820.45     13466949.96
#Sta/Elev= 30
  4764.1  101.72  4860.6  100.12  4881.5  100.51  4902.5   99.33  4911.1   98.05
  4917.2   98.39  4925.9   96.22    4932   96.48  4939.1    94.6  4946.8   91.35
    4953   92.72  4961.7   85.94  4967.8   87.53  4972.4    84.6  4972.9    84.1
  4979.1    84.6  4988.7    87.4  5021.7   88.72  5027.7    90.4  5033.1   89.97
  5052.1   93.24  5057.5   92.18  5064.7   93.26  5075.4   91.89  5081.9   89.69
  5096.9   89.38  5111.6   90.97  5118.4   93.49  5150.7   99.56  5273.8  103.29
#Mann= 3 ,-1 , 0
  4764.1     .07       0  4972.4     .05       0  4979.1     .07       0
Bank Sta=4972.4,4979.1
XS Rating Curve= 0 ,0
Exp/Cntr=0.3,0.1

Type RM Length L Ch R = 1 ,15097   ,630,630,630
BEGIN DESCRIPTION:
BOGGY CREEK 32.0
END DESCRIPTION:
XS GIS Cut Line= 3
      2570225.02     13467125.03        2570075.       13466925.
      2570025.02     13466825.04
#Sta/Elev= 30
  4754.6  100.61  4776.5   99.32  4797.3   99.73  4861.9   98.59  4891.1   98.29
  4897.3   98.62  4926.5   97.53  4932.8   96.73  4941.1   96.51  4947.3   89.38
  4961.9    94.8  4968.2   87.62  4976.5   92.64  4982.8   85.22  4991.1   86.33
  4997.3   84.28    5013    85.2  5015.3   83.95  5015.8   83.45  5021.5   83.45
    5022   83.95  5035.4   86.65    5041   88.43  5049.4   88.82  5057.7   91.64
  5063.3   96.34  5071.7  100.35  5085.7  101.91  5102.5  102.76  5116.4  102.97
#Mann= 3 ,-1 , 0
  4754.6     .07       0  5015.3     .05       0    5022     .07       0
Bank Sta=5015.3,5022
XS Rating Curve= 0 ,0
Exp/Cntr=0.3,0.1

Type RM Length L Ch R = 1 ,14467   ,279,279,279
BEGIN DESCRIPTION:
Mapping XS 6716817a
END DESCRIPTION:
XS GIS Cut Line= 3
       2570517.5     13467113.02      2570526.18     13466919.85
       2570350.4      13466494.5
#Sta/Elev= 30
  4804.5  105.24  4863.9  104.21  4882.6  102.79  4972.7    99.1  4982.7    96.2
  4992.7   89.63  4997.8   84.03  5003.2   84.03  5013.3   82.46  5013.8   81.96
  5020.1   82.46  5035.2   84.59  5040.6   83.35  5042.4   84.17  5046.4   85.99
  5057.2   88.81  5064.5   89.07  5069.9   86.26  5100.5   95.64  5147.1   94.74
  5194.9   96.55  5218.8   96.47  5224.2   97.27  5253.5   89.99  5262.8   89.58
  5284.4   96.24  5295.3   97.21  5360.2   98.32  5407.8  100.21  5458.1  100.46
#Mann= 4 ,-1 , 0
  4804.5     .12       0  5013.3     .05       0  5020.1     .12       0
  5042.4     .07       0
Bank Sta=5013.3,5020.1
XS Rating Curve= 0 ,0
Exp/Cntr=0.3,0.1

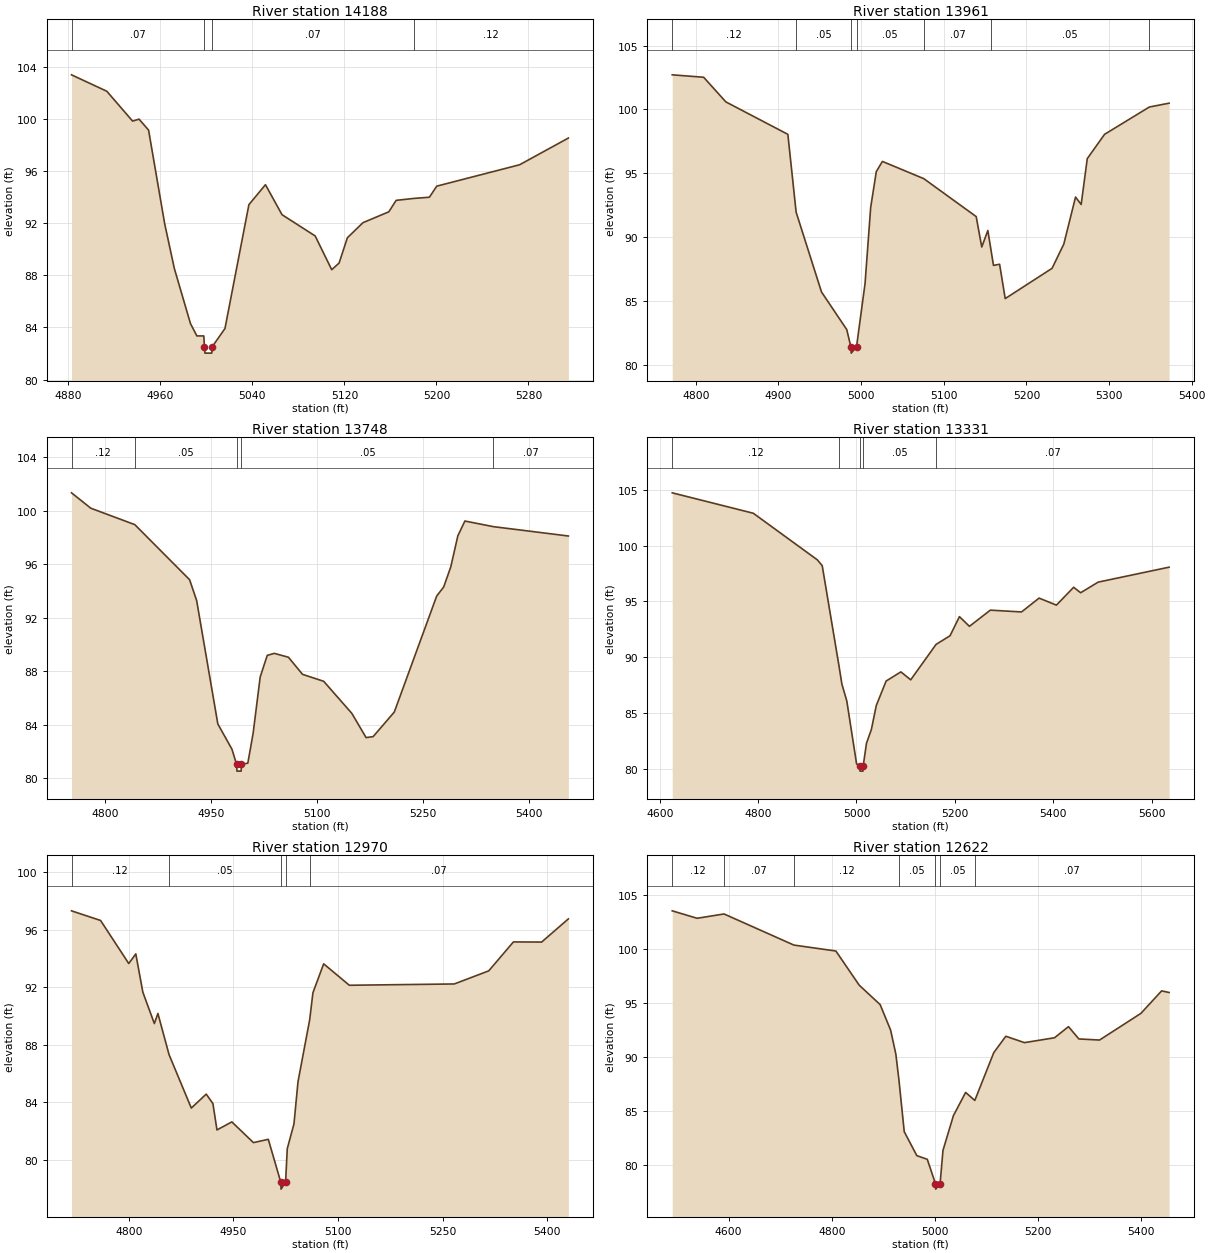
Type RM Length L Ch R = 1 ,14188   ,227,227,227
BEGIN DESCRIPTION:
BOGGY CREEK 30.0
END DESCRIPTION:
XS GIS Cut Line= 3
      2570774.98     13466824.96        2570725.       13466725.
      2570525.01     13466475.01
#Sta/Elev= 30
  4882.8  103.38  4913.5  102.12  4935.9   99.83  4941.5   99.98  4949.8   99.14
  4963.8   91.95  4972.2   88.52  4986.2    84.3  4991.8   83.35  4997.8   83.35
  4998.3   82.53  4998.8   82.03  5004.7   82.03  5005.2   82.53  5016.2   83.92
    5037   93.42  5051.4   94.95  5065.8   92.65  5094.6   91.02    5109   88.43
  5115.4   88.94  5122.6   90.88  5136.2   92.04  5158.6   92.87    5165   93.75
  5180.6    93.9  5193.9   93.99  5200.3   94.84  5272.3   96.48  5314.7   98.53
#Mann= 4 ,-1 , 0
  4882.8     .07       0  4998.3     .05       0  5005.2     .07       0
  5180.6     .12       0
Bank Sta=4998.3,5005.2
XS Rating Curve= 0 ,0
Exp/Cntr=0.3,0.1

Type RM Length L Ch R = 1 ,13961   ,213,213,213
BEGIN DESCRIPTION:
Mapping XS aa8a4c85
END DESCRIPTION:
XS GIS Cut Line= 3
      2570922.71     13466802.29      2570879.31      13466580.1
      2570625.81     13466304.02
#Sta/Elev= 30
  4771.5  102.71  4809.5  102.52  4836.4  100.59  4911.4   98.05  4921.4   91.96
  4952.1   85.71  4982.7   82.76  4987.6   81.42  4988.1   80.92  4994.5   81.42
  5004.8   86.37  5011.6   92.32  5018.4   95.13  5025.8   95.93  5075.9   94.58
  5139.3   91.61    5146   89.23  5153.4   90.52  5157.2   88.99  5160.2   87.79
  5167.6   87.88  5174.4   85.19  5231.1   87.56  5245.3   89.46  5259.5   93.14
  5266.3   92.56  5273.7   96.15  5294.6   98.05  5348.8  100.19  5372.7  100.49
#Mann= 7 ,-1 , 0
  4771.5     .12       0  4921.4     .05       0  4987.6     .05       0
  4994.5     .05       0  5075.9     .07       0  5157.2     .05       0
  5348.8     .12       0
Bank Sta=4987.6,4994.5
XS Rating Curve= 0 ,0
Exp/Cntr=0.3,0.1

Type RM Length L Ch R = 1 ,13748   ,417,417,417
BEGIN DESCRIPTION:
BOGGY CREEK 29.0
END DESCRIPTION:
XS GIS Cut Line= 3
      2571070.89     13466772.31        2571075.       13466525.
      2571075.23     13466068.45
#Sta/Elev= 30
  4752.5  101.35  4779.8   100.2  4842.2   98.97  4919.8   94.85  4929.8   93.29
  4959.8   84.06  4979.8   82.17  4986.4   81.03  4986.9   80.53  4992.8   80.53
  4993.3   81.03  5002.3   81.13  5009.8   83.36  5019.8   87.57  5029.8   89.19
  5039.8   89.34  5059.8   89.05  5079.8   87.77  5109.8   87.25  5149.8   84.84
  5169.8   83.04  5179.8   83.11  5209.8   84.95  5269.8   93.62  5279.8   94.31
  5289.8   95.81  5299.8   98.13  5309.8   99.24  5350.1   98.82  5456.4   98.12
#Mann= 5 ,-1 , 0
  4752.5     .12       0  4842.2     .05       0  4986.4     .05       0
  4993.3     .05       0  5350.1     .07       0
Bank Sta=4986.4,4993.3
XS Rating Curve= 0 ,0
Exp/Cntr=0.3,0.1

Type RM Length L Ch R = 1 ,13331   ,361,361,361
BEGIN DESCRIPTION:
Mapping XS 70313ac1
END DESCRIPTION:
XS GIS Cut Line= 3
      2571461.91     13466999.92      2571451.06     13466411.78
      2571142.86     13466123.12
#Sta/Elev= 30
  4625.3  104.72  4790.2  102.89  4920.3   98.72  4930.3    98.2  4964.7   89.15
  4970.3   87.59  4980.3   86.08  5000.3   80.42  5006.8   80.29  5007.3   79.79
  5013.3   79.79  5013.8   80.29  5020.3   82.28  5030.3   83.52  5040.3   85.67
  5060.3   87.86  5090.3   88.68  5110.3   87.97  5161.8   91.14  5190.3   91.92
  5209.4   93.63  5229.7   92.76  5272.2   94.21  5335.7   94.05  5371.4   95.29
  5406.6   94.66  5441.7   96.26  5455.9   95.77  5491.5   96.72  5635.8   98.06
#Mann= 5 ,-1 , 0
  4625.3     .12       0  4964.7     .05       0  5006.8     .05       0
  5013.8     .05       0  5161.8     .07       0
Bank Sta=5006.8,5013.8
XS Rating Curve= 0 ,0
Exp/Cntr=0.3,0.1

Type RM Length L Ch R = 1 ,12970   ,348,348,348
BEGIN DESCRIPTION:
Mapping XS de6c095f
END DESCRIPTION:
XS GIS Cut Line= 4
      2571702.79     13466596.27      2571726.66     13466431.31
      2571487.95     13466285.91      2571239.22     13466190.75
#Sta/Elev= 30
  4717.9    97.3  4759.6   96.63    4800   93.64  4810.1   94.31  4820.2   91.65
  4836.7   89.47  4841.8   90.17  4857.8   87.31  4889.7    83.6  4911.1   84.57
  4920.7   83.91  4926.5   82.08  4947.8   82.64  4978.8    81.2  5000.1   81.43
  5017.9   78.47  5018.4   77.97  5024.9   78.47  5027.3   80.78  5036.9    82.5
  5042.7   85.43  5059.5   89.75  5064.1   91.61  5079.5   93.62  5116.3   92.13
  5266.8   92.22  5316.2   93.13  5351.6   95.14  5392.1   95.13  5430.4   96.74
#Mann= 5 ,-1 , 0
  4717.9     .12       0  4857.8     .05       0  5017.9     .05       0
  5024.9     .05       0  5059.5     .07       0
Bank Sta=5017.9,5024.9
XS Rating Curve= 0 ,0
Exp/Cntr=0.3,0.1

Type RM Length L Ch R = 1 ,12622   ,200,200,200
BEGIN DESCRIPTION:
Mapping XS 1e4ece8e
END DESCRIPTION:
XS GIS Cut Line= 4
      2572112.92     13466324.95      2571874.23     13466107.96
      2571464.08     13466179.58      2571240.59     13466162.22
#Sta/Elev= 30
  4490.7  103.57  4538.9  102.88  4591.1  103.28  4726.5   100.4  4807.9   99.85
  4853.1   96.69  4893.7   94.89    4914   92.53  4924.2   90.29  4930.4    87.8
  4940.4   83.13  4964.8   80.91  4985.1   80.57  5000.9   78.31  5001.4   77.81
  5009.9   78.31  5015.5    81.4  5035.8   84.62  5059.4   86.76  5077.2   86.02
  5113.9   90.44  5137.3   91.96  5173.4   91.37  5231.7   91.82  5258.8   92.85
  5278.9   91.71    5319   91.61  5399.2   94.08  5439.3   96.16  5453.8   96.01
#Mann= 7 ,-1 , 0
  4490.7     .12       0  4591.1     .07       0  4726.5     .12       0
  4930.4     .05       0  5000.9     .05       0  5009.9     .05       0
  5077.2     .07       0
Bank Sta=5000.9,5009.9
XS Rating Curve= 0 ,0
Exp/Cntr=0.3,0.1

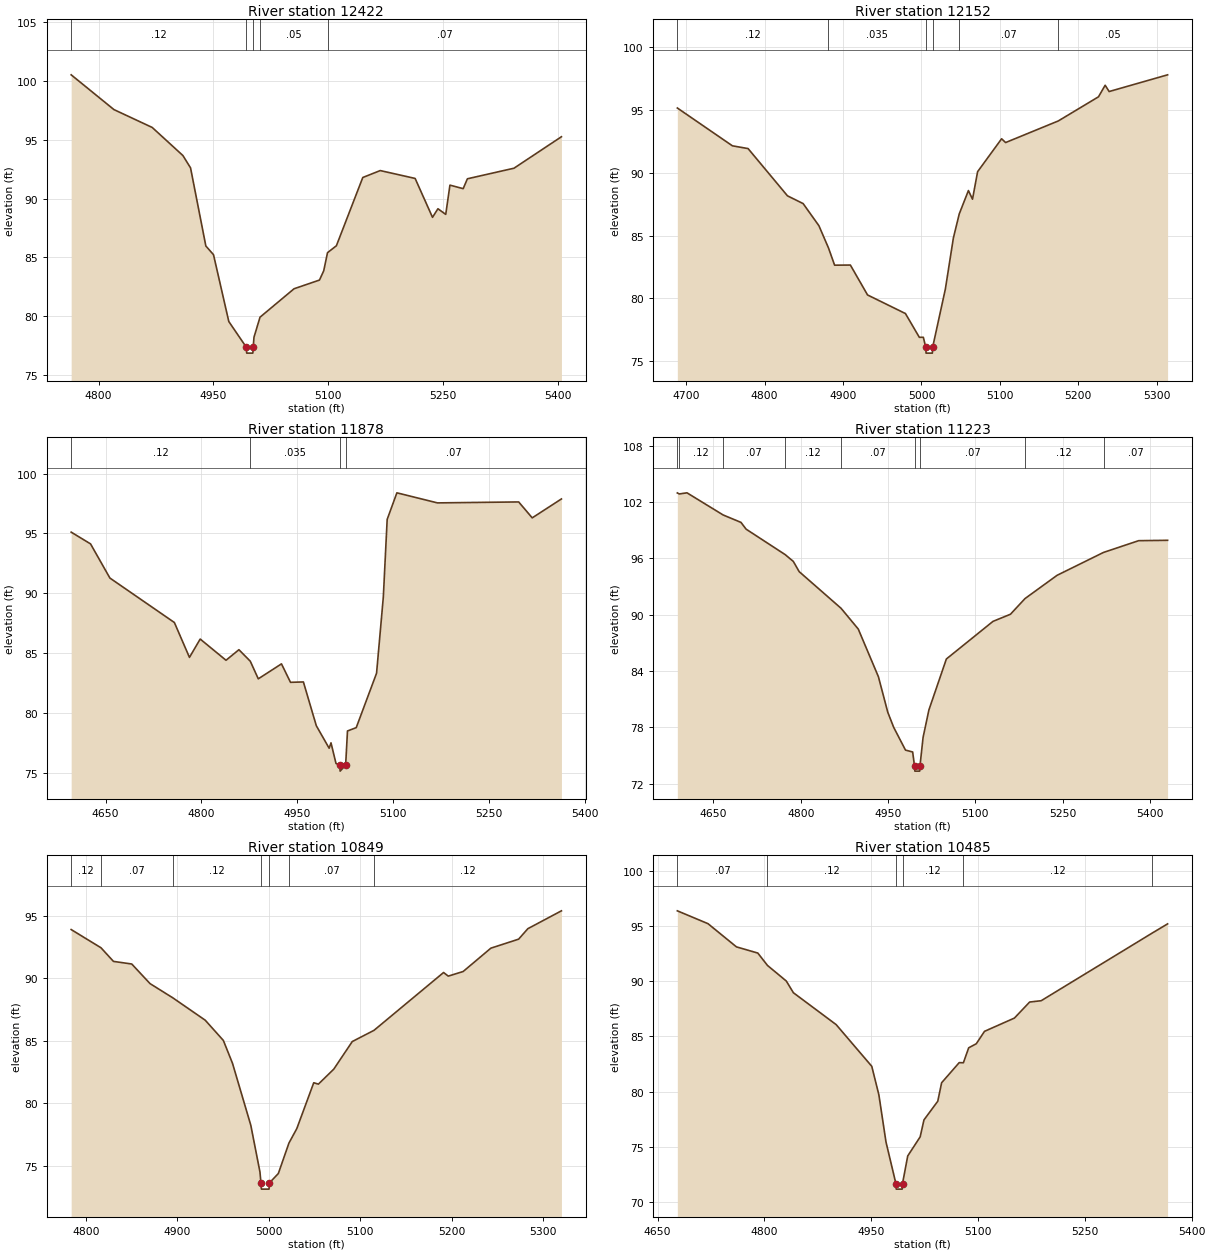
Type RM Length L Ch R = 1 ,12422   ,270,270,270
BEGIN DESCRIPTION:
Mapping XS b8cd69f7
END DESCRIPTION:
XS GIS Cut Line= 3
      2571860.82     13465949.79      2571625.24     13465959.85
      2571258.95     13466132.43
#Sta/Elev= 30
  4764.2  100.53  4820.1   97.57  4870.1   96.05  4910.2   93.66  4920.2   92.61
  4940.2   85.96  4950.2   85.22  4970.2   79.53  4993.1   77.34  4993.6   76.84
  5001.6   76.84  5002.1   77.34  5003.1   78.19    5011    79.9  5055.5   82.32
  5088.7   83.06  5094.2   83.84  5099.2   85.39  5110.8   85.98  5145.3   91.79
  5168.1   92.38  5213.7   91.71  5236.4    88.4  5243.5   89.13  5253.7   88.65
  5259.2   91.14  5276.5   90.84    5282   91.68  5342.9   92.58  5404.9   95.26
#Mann= 5 ,-1 , 0
  4764.2     .12       0  4993.1    .035       0  5002.1     .12       0
    5011     .05       0  5099.2     .07       0
Bank Sta=4993.1,5002.1
XS Rating Curve= 0 ,0
Exp/Cntr=0.3,0.1

Type RM Length L Ch R = 1 ,12152   ,274,274,274
BEGIN DESCRIPTION:
BOGGY CREEK 26.0
END DESCRIPTION:
XS GIS Cut Line= 3
      2571734.99     13465802.22      2571424.65     13465825.34
      2571119.28     13465897.56
#Sta/Elev= 30
  4688.8   95.15    4759   92.14    4779   91.92  4829.2   88.16  4849.2   87.54
  4869.3   85.78  4881.5   84.01  4889.3   82.64  4909.4   82.65  4931.3   80.27
  4979.6   78.79  4997.3    76.9  5002.4    76.9  5005.4   76.14  5005.9   75.64
  5013.9   75.64  5014.4   76.14  5030.5   80.74  5040.7    84.8  5048.2   86.72
  5059.9   88.58  5065.1   87.89  5071.6   90.08  5102.2    92.7  5107.3    92.4
  5174.5   94.12  5225.7   96.04  5234.2   96.96  5239.3   96.46  5313.8   97.79
#Mann= 6 ,-1 , 0
  4688.8     .12       0  4881.5    .035       0  5005.4    .035       0
  5014.4    .035       0  5048.2     .07       0  5174.5     .05       0
Bank Sta=5005.4,5014.4
XS Rating Curve= 0 ,0
Exp/Cntr=0.3,0.1

Type RM Length L Ch R = 1 ,11878   ,655,655,655
BEGIN DESCRIPTION:
BOGGY CREEK 25.0
END DESCRIPTION:
XS GIS Cut Line= 3
      2571775.03       13465625.       2571374.9     13465569.96
      2571031.79     13465689.39
#Sta/Elev= 30
  4596.1   95.11  4626.4   94.13  4656.7   91.28  4757.6   87.57  4781.2   84.66
    4798   86.19  4838.4   84.42  4858.6    85.3  4876.4   84.34  4888.9   82.87
  4925.2   84.12  4939.3   82.58  4959.5   82.61  4979.7   78.96  4999.8   77.08
  5002.7   77.53  5010.5   75.81  5016.5   75.67    5017   75.17  5025.6   75.67
  5028.5   78.52  5042.2    78.8    5074   83.34  5084.6   89.71  5090.6   96.17
  5105.8   98.39  5169.3   97.55  5296.4   97.63  5317.6    96.3  5363.3   97.88
#Mann= 4 ,-1 , 0
  4596.1     .12       0  4876.4    .035       0  5016.5    .035       0
  5025.6     .07       0
Bank Sta=5016.5,5025.6
XS Rating Curve= 0 ,0
Exp/Cntr=0.3,0.1

Type RM Length L Ch R = 1 ,11223   ,374,374,374
BEGIN DESCRIPTION:
Mapping XS a223856e
END DESCRIPTION:
XS GIS Cut Line= 3
      2572031.38     13465257.71      2571632.91     13465189.99
      2571195.38     13465208.22
#Sta/Elev= 30
    4588  102.98  4591.4  102.87  4604.6  102.99  4666.7  100.63  4697.3   99.84
  4706.1   99.12  4773.1   96.41  4787.2   95.68  4797.3   94.59  4869.3   90.68
  4898.8   88.47  4933.4   83.39  4949.5    79.6  4959.6      78  4979.9   75.57
  4992.2   75.37  4995.5   73.83    4996   73.33  5004.2   73.33  5004.7   73.83
  5010.1   76.92  5020.1   79.85  5050.1   85.28  5130.2   89.29  5160.2   90.05
  5185.2   91.72  5240.3    94.2  5320.1   96.64  5380.4   97.89  5430.1   97.93
#Mann= 9 ,-1 , 0
    4588     .07       0  4591.4     .12       0  4666.7     .07       0
  4773.1     .12       0  4869.3     .07       0  4995.5     .05       0
  5004.7     .07       0  5185.2     .12       0  5320.1     .07       0
Bank Sta=4995.5,5004.7
XS Rating Curve= 0 ,0
Exp/Cntr=0.3,0.1

Type RM Length L Ch R = 1 ,10849   ,364,364,364
BEGIN DESCRIPTION:
Mapping XS 93b3f4a1
END DESCRIPTION:
XS GIS Cut Line= 3
      2571891.21     13464825.66      2571678.53     13464832.17
      2571358.71     13464877.55
#Sta/Elev= 30
    4784   93.91  4816.6   92.45  4830.2   91.36  4850.2   91.15  4870.2   89.58
  4895.1   88.44  4930.5   86.65  4950.3   85.03  4960.3    83.2  4980.3   78.24
  4990.3    74.5  4991.4   73.62  4991.9   73.12  5000.2   73.12  5000.7   73.62
  5010.4   74.37    5022   76.81  5030.6   77.97  5049.1   81.64  5054.2   81.53
    5071   82.73  5091.2   84.94    5115   85.84    5191   90.47  5196.1   90.18
  5212.4   90.55  5242.7   92.42    5273   93.14  5283.1   93.98  5319.8   95.41
#Mann= 7 ,-1 , 0
    4784     .12       0  4816.6     .07       0  4895.1     .12       0
  4991.4     .05       0  5000.7     .12       0    5022     .07       0
    5115     .12       0
Bank Sta=4991.4,5000.7
XS Rating Curve= 0 ,0
Exp/Cntr=0.3,0.1

Type RM Length L Ch R = 1 ,10485   ,233,233,233
BEGIN DESCRIPTION:
Mapping XS e3eb578e
END DESCRIPTION:
XS GIS Cut Line= 3
      2571947.98     13464510.31      2571632.91     13464510.31
        2571284.      13464643.1
#Sta/Elev= 30
  4677.8   96.36  4720.8    95.2  4760.8    93.1  4790.8   92.54  4804.4   91.42
  4830.8   90.01  4840.8   88.95  4900.8   86.07  4950.8    82.3  4960.8   79.72
  4970.8   75.45  4984.7   71.69  4985.2   71.19  4993.5   71.19    4994   71.69
  5001.3   74.19  5018.8   75.92  5024.1   77.45  5043.5   79.14  5048.9   80.81
  5073.6   82.63  5079.5   82.62  5086.9   83.97  5097.6   84.34  5109.1   85.46
  5151.1   86.66  5172.5   88.11  5188.7   88.23  5344.9   94.36  5366.2   95.18
#Mann= 6 ,-1 , 0
  4677.8     .07       0  4804.4     .12       0  4984.7     .05       0
    4994     .12       0  5079.5     .12       0  5344.9     .07       0
Bank Sta=4984.7,4994
XS Rating Curve= 0 ,0
Exp/Cntr=0.3,0.1