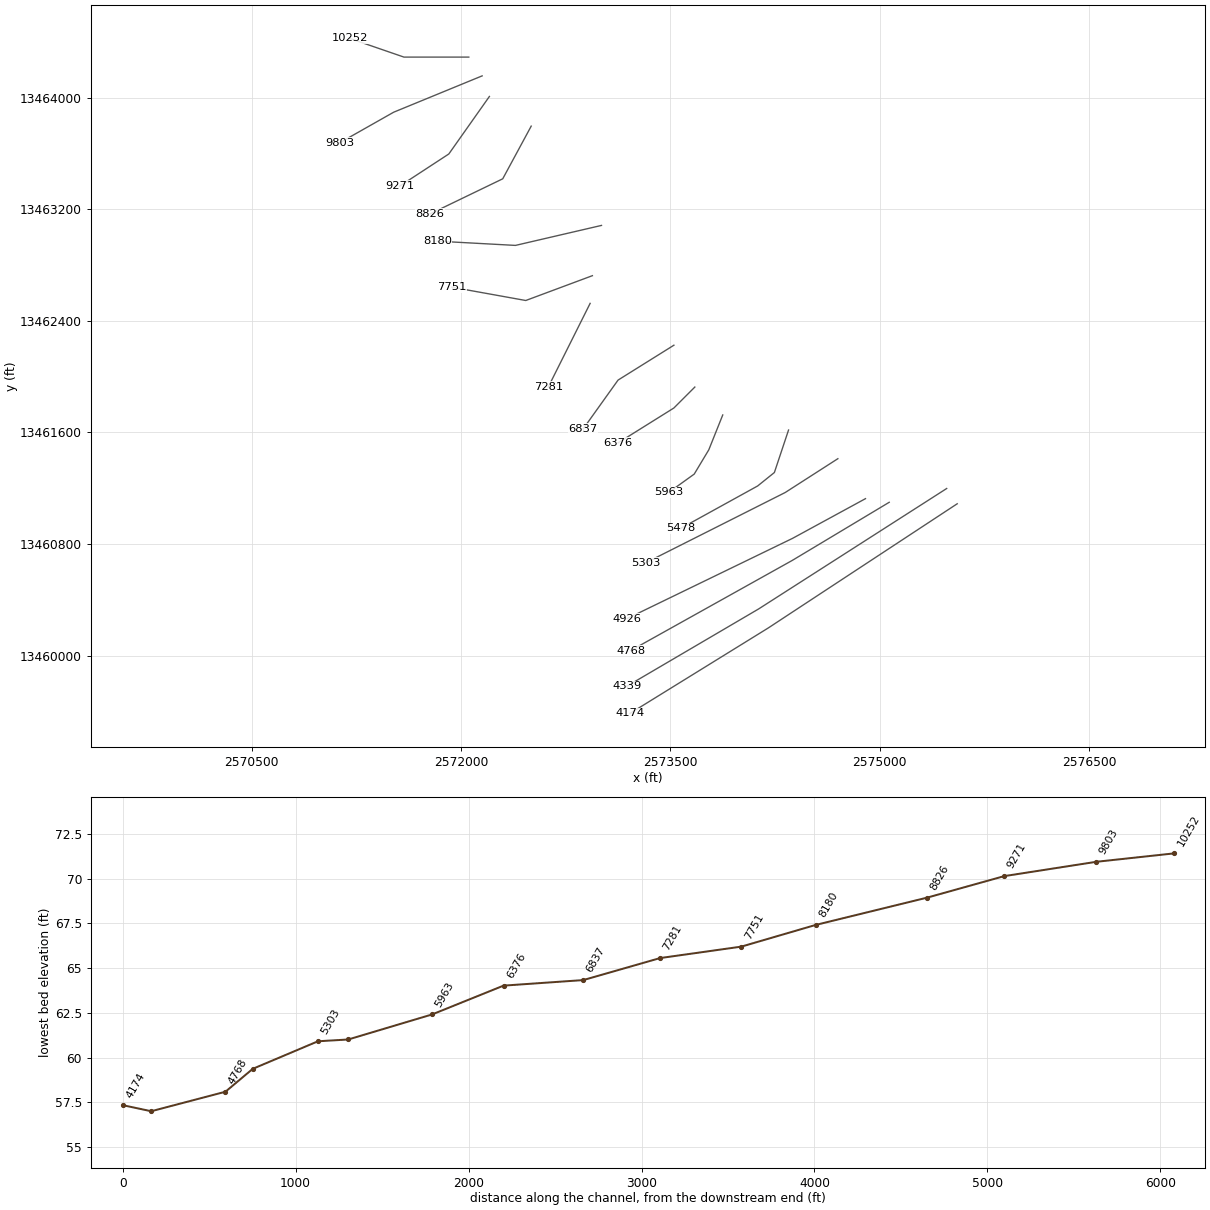
HEC-RAS study BOGGY CREEK.prj: BOGGY CREEK Base Level Engineering

--- BOGGY CREEK.g01 (geometry) --- (continued)

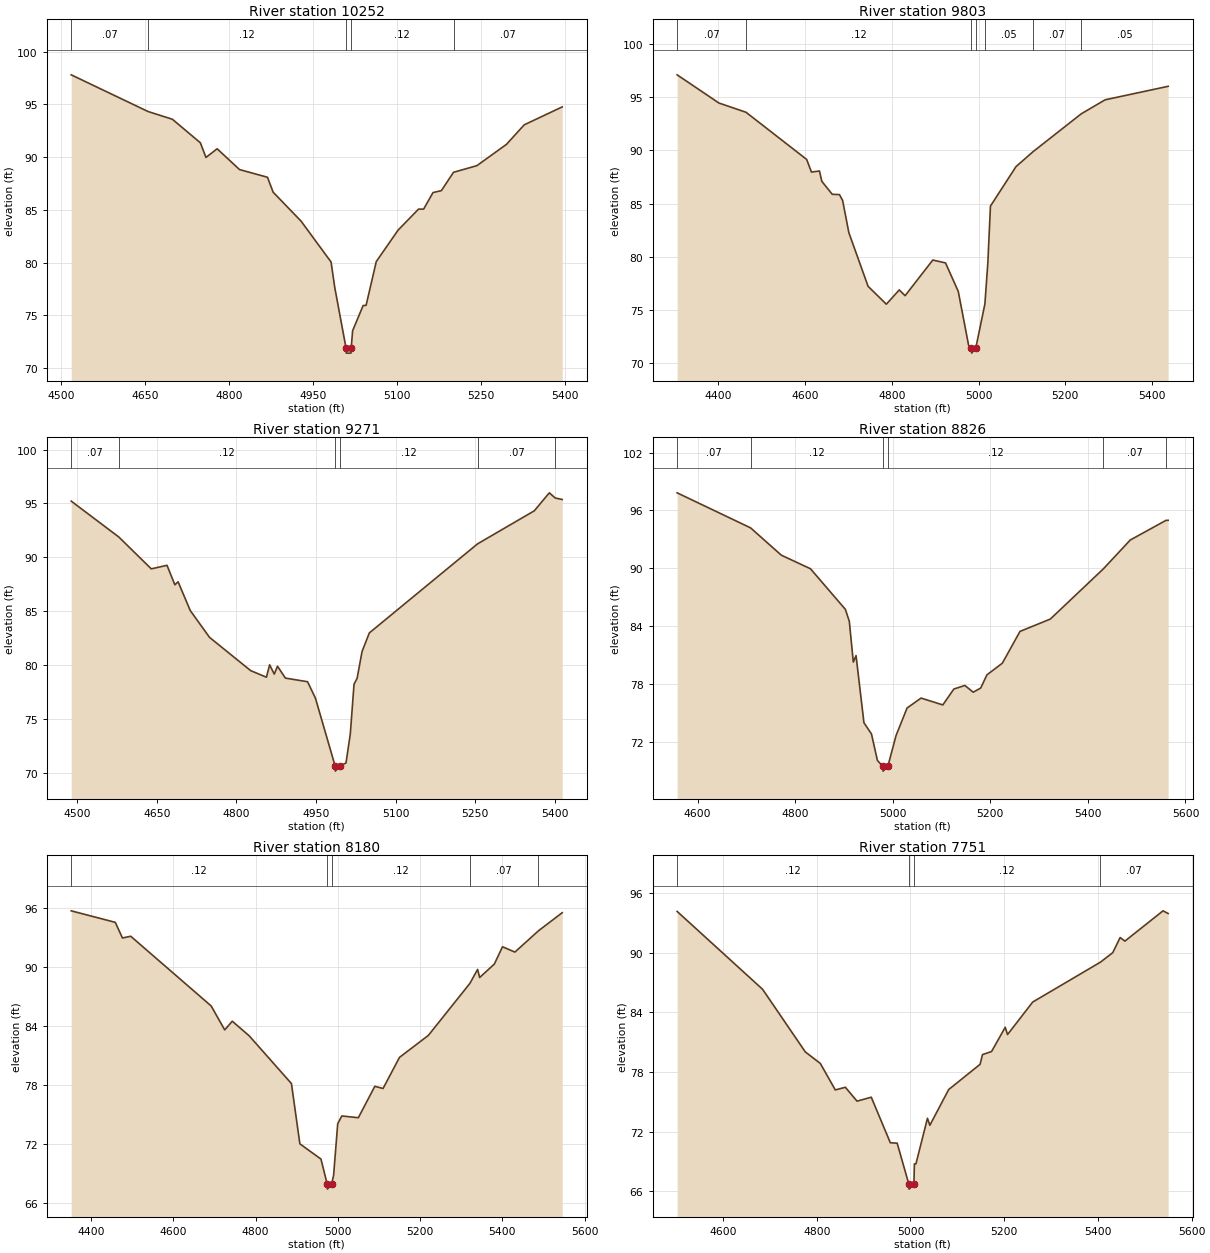
Type RM Length L Ch R = 1 ,10252   ,449,449,449
BEGIN DESCRIPTION:
Mapping XS db02cd54
END DESCRIPTION:
XS GIS Cut Line= 3
      2572055.76     13464290.34       2571591.4     13464290.34
      2571200.78     13464424.89
#Sta/Elev= 30
  4518.1   97.79  4655.5   94.31  4698.9   93.58  4748.9   91.35  4758.9   89.96
  4778.9   90.78  4818.9   88.81  4868.9   88.08  4878.9   86.67  4928.9   83.92
  4982.5   80.05  4989.2    77.6  5009.2   71.91  5009.7   71.41    5018   71.41
  5018.5   71.91    5021   73.53  5039.8   75.92  5045.1   75.94  5063.3   80.09
  5102.3   83.07  5138.8   85.06  5147.9   85.06  5164.7   86.63  5179.6   86.81
  5201.3   88.55  5243.1   89.18    5296    91.2  5327.7   93.05  5395.6   94.75
#Mann= 5 ,-1 , 0
  4518.1     .07       0  4655.5     .12       0  5009.2     .05       0
  5018.5     .12       0  5201.3     .07       0
Bank Sta=5009.2,5018.5
XS Rating Curve= 0 ,0
Exp/Cntr=0.3,0.1

Type RM Length L Ch R = 1 ,9803    ,532,532,532
BEGIN DESCRIPTION:
Mapping XS 0ca18fb1
END DESCRIPTION:
XS GIS Cut Line= 3
       2572151.3     13464155.79      2571517.62     13463895.38
      2571128.46     13463674.86
#Sta/Elev= 30
  4304.9    97.1  4401.3   94.45  4463.8   93.58  4603.6   89.15  4614.7   87.96
  4633.2   88.06  4638.6   87.09  4662.6   85.87  4679.3   85.84  4686.6   85.29
  4700.9   82.27  4745.3   77.22  4787.4   75.54  4817.2   76.88  4830.7   76.34
  4894.5   79.69  4923.9   79.42  4953.3   76.74  4977.2   71.67  4983.7   71.44
  4984.2   70.94  4993.8   71.44  5014.7   75.56  5021.5   79.43  5027.5   84.76
  5086.4   88.47  5125.9   89.88  5237.1   93.44  5291.9   94.75  5437.3   96.02
#Mann= 7 ,-1 , 0
  4304.9     .07       0  4463.8     .12       0  4983.7     .05       0
  4993.8     .12       0  5014.7     .05       0  5125.9     .07       0
  5237.1     .05       0
Bank Sta=4983.7,4993.8
XS Rating Curve= 0 ,0
Exp/Cntr=0.3,0.1

Type RM Length L Ch R = 1 ,9271    ,445,445,445
BEGIN DESCRIPTION:
Mapping XS fd7f12f1
END DESCRIPTION:
XS GIS Cut Line= 3
      2572203.38     13464008.22      2571912.58      13463595.9
      2571561.01     13463365.86
#Sta/Elev= 30
    4489   95.21  4578.6   91.88  4639.8   88.92  4669.4   89.25  4684.2   87.44
  4690.3   87.72  4713.2   85.05  4749.5   82.56    4827   79.47  4856.6   78.86
  4862.7   80.01  4871.4   79.15  4877.5   79.88  4892.3   78.78  4934.1   78.44
  4948.9   76.92  4985.9   70.64  4986.4   70.14  4996.1   70.64  5006.5    70.9
  5014.6   73.59  5021.6    78.2  5027.5   78.77  5036.7   81.24  5050.4   82.97
  5254.2   91.24  5361.1   94.31  5389.4   95.98  5400.5    95.5  5413.7   95.36
#Mann= 6 ,-1 , 0
    4489     .07       0  4578.6     .12       0  4985.9     .05       0
  4996.1     .12       0  5254.2     .07       0  5400.5     .05       0
Bank Sta=4985.9,4996.1
XS Rating Curve= 0 ,0
Exp/Cntr=0.3,0.1

Type RM Length L Ch R = 1 ,8826    ,646,646,646
BEGIN DESCRIPTION:
Mapping XS 5620b3e2
END DESCRIPTION:
XS GIS Cut Line= 3
      2572502.86     13463795.55      2572298.87     13463417.95
      2571778.98     13463166.67
#Sta/Elev= 30
  4557.9   97.82  4708.6   94.18  4771.5   91.35  4831.3   89.94  4902.9   85.72
  4910.9   84.48  4919.1   80.25  4924.7   80.93  4940.9   73.96  4956.3    72.8
  4968.5   70.05  4979.6   69.44  4980.1   68.94  4989.9   69.44  5006.7   72.63
  5029.3   75.49    5058   76.52  5102.6   75.81  5125.2   77.46  5147.8   77.83
  5164.9   77.13  5180.2   77.56    5193   78.93  5224.6   80.14  5260.8   83.44
    5323   84.72  5431.9   89.94  5486.8   92.92    5560   94.96  5564.5   94.97
#Mann= 6 ,-1 , 0
  4557.9     .07       0  4708.6     .12       0  4979.6     .05       0
  4989.9     .12       0  5431.9     .07       0    5560     .05       0
Bank Sta=4979.6,4989.9
XS Rating Curve= 0 ,0
Exp/Cntr=0.3,0.1

Type RM Length L Ch R = 1 ,8180    ,429,429,429
BEGIN DESCRIPTION:
Mapping XS 4521e358
END DESCRIPTION:
XS GIS Cut Line= 3
      2573006.37     13463083.76      2572390.01     13462940.52
      2571830.12      13462970.9
#Sta/Elev= 30
    4352   95.67  4459.1    94.5  4476.6   92.91  4496.6   93.09  4692.2   86.01
  4725.1   83.58  4743.5   84.46  4784.6   82.98  4887.3   78.13  4907.8   72.01
  4959.1   70.46  4974.3   67.91  4974.8   67.41    4985   67.91  4989.8   68.82
  4999.8   74.06  5009.8   74.84  5049.9   74.66    5090   77.85    5110   77.63
    5150   80.79  5220.1   83.02  5321.2   88.31  5339.8   89.72  5344.8    88.9
  5380.4   90.26  5400.4   92.02  5430.5   91.48  5487.7   93.64  5545.5   95.48
#Mann= 5 ,-1 , 0
    4352     .12       0  4974.3     .05       0    4985     .12       0
  5321.2     .07       0  5487.7     .05       0
Bank Sta=4974.3,4985
XS Rating Curve= 0 ,0
Exp/Cntr=0.3,0.1

Type RM Length L Ch R = 1 ,7751    ,470,470,470
BEGIN DESCRIPTION:
Mapping XS 9e8cf329
END DESCRIPTION:
XS GIS Cut Line= 3
      2572941.23      13462723.5       2572463.8     13462545.55
      2571934.26     13462641.04
#Sta/Elev= 30
  4502.2   94.17  4684.5   86.33  4775.7   80.02  4807.7   78.86  4839.7   76.19
  4861.1   76.46  4886.1   75.06  4916.4   75.46  4957.1   70.87  4971.7   70.83
  4996.6    66.7  4997.1    66.2  5007.4    66.7  5008.4   68.74  5011.7   68.74
  5036.3   73.34  5041.4   72.63  5081.6   76.23  5148.6   78.77  5153.7   79.75
  5173.1   80.06  5202.2    82.5  5207.2   81.77  5260.8   85.04  5405.4   89.06
  5431.7   90.02  5447.4   91.54  5457.6   91.18  5538.9   94.23  5549.8   93.96
#Mann= 4 ,-1 , 0
  4502.2     .12       0  4996.6     .05       0  5007.4     .12       0
  5405.4     .07       0
Bank Sta=4996.6,5007.4
XS Rating Curve= 0 ,0
Exp/Cntr=0.3,0.1

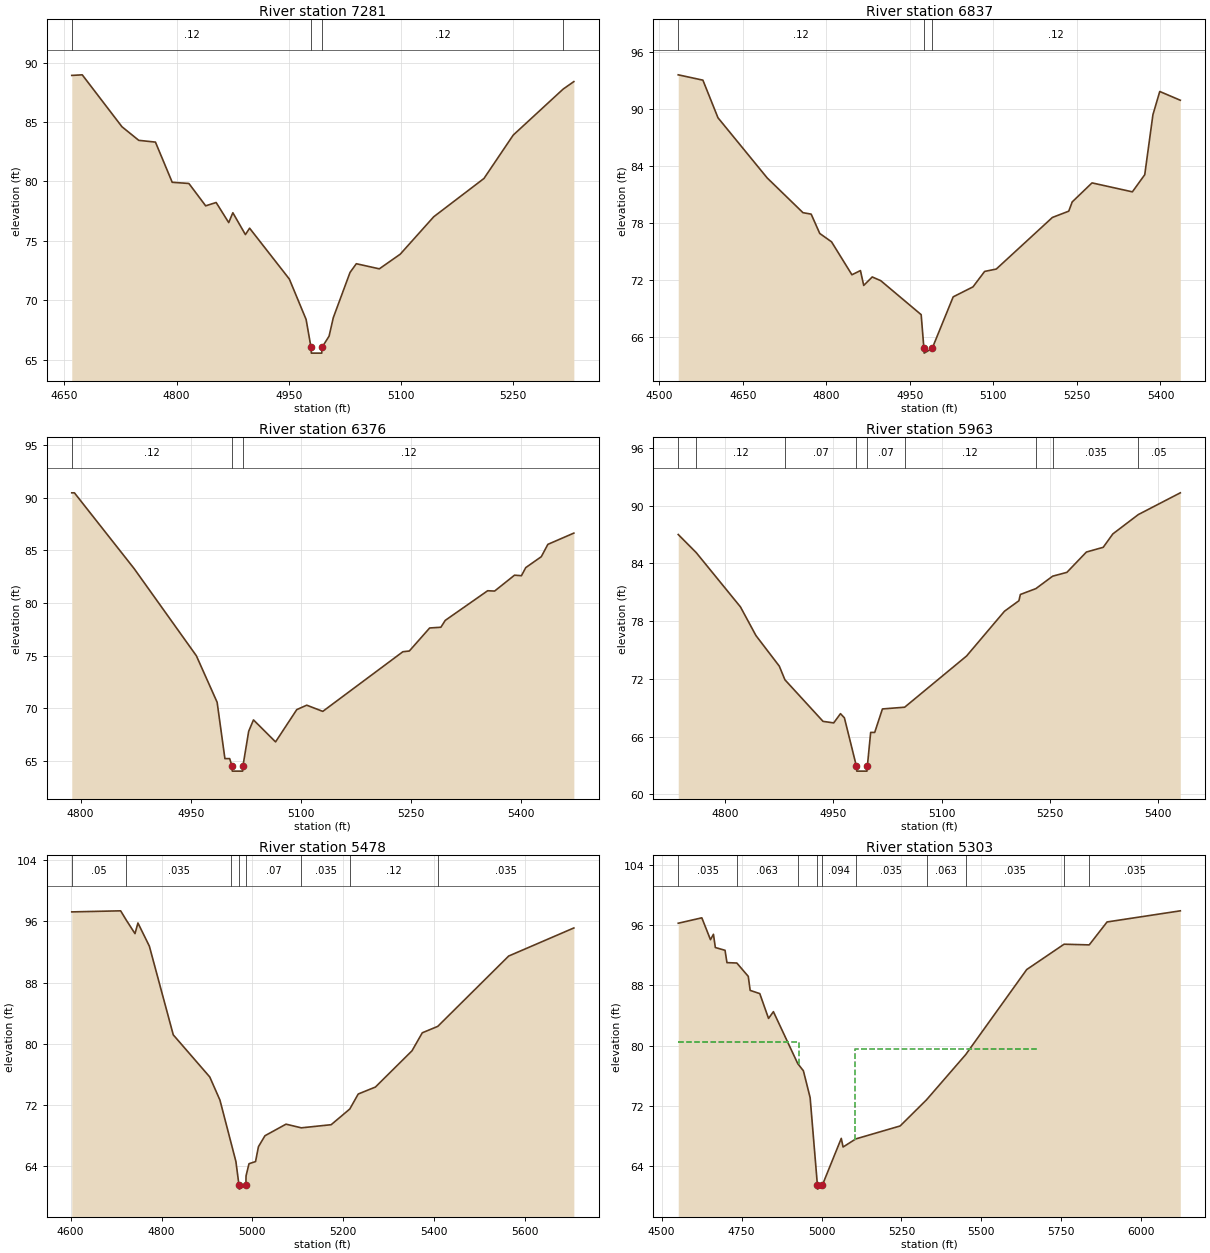
Type RM Length L Ch R = 1 ,7281    ,444,444,444
BEGIN DESCRIPTION:
BOGGY CREEK 15.0
END DESCRIPTION:
XS GIS Cut Line= 3
      2572925.01     13462525.02        2572775.       13462225.
      2572625.02     13461925.04
#Sta/Elev= 30
    4660   88.92    4674   88.97  4727.1    84.6  4749.5   83.46  4771.8   83.31
  4794.2   79.93  4816.5   79.83  4838.9   77.95  4852.9   78.23  4869.7   76.54
  4875.2   77.37    4892   75.53  4897.6   76.07  4950.7   71.79  4973.1   68.39
  4979.6   66.06  4980.1   65.56    4994   65.56  4994.5   66.06  5003.8   66.99
  5009.4   68.54  5031.8   72.35  5040.2   73.08  5070.9   72.65  5098.8   73.88
  5143.6   77.03  5210.7   80.25  5249.8    83.9  5316.5   87.77  5330.8    88.4
#Mann= 4 ,-1 , 0
    4660     .12       0  4979.6     .05       0  4994.5     .12       0
  5316.5     .05       0
Bank Sta=4979.6,4994.5
XS Rating Curve= 0 ,0
Exp/Cntr=0.3,0.1

Type RM Length L Ch R = 1 ,6837    ,461,461,461
BEGIN DESCRIPTION:
BOGGY CREEK 14.0
END DESCRIPTION:
XS GIS Cut Line= 3
      2573525.04     13462225.02        2573125.       13461975.
      2572874.98     13461624.97
#Sta/Elev= 30
  4533.8   93.56  4578.1      93  4605.2   89.05  4693.6   82.73  4757.9   79.08
  4772.6   78.93    4788    76.9  4809.2   76.02  4845.8   72.56  4861.1      73
    4867   71.44  4882.3   72.33  4897.6   71.94  4970.2   68.37  4975.1   64.83
  4975.6   64.33    4990   64.83  5027.7   70.24  5063.3   71.29  5084.2   72.91
  5105.1   73.16  5205.9   78.58  5235.3   79.24  5241.5   80.21  5277.1   82.21
  5349.6   81.27  5371.8   83.07  5386.5   89.37  5398.8   91.81  5435.7   90.89
#Mann= 3 ,-1 , 0
  4533.8     .12       0  4975.1     .05       0    4990     .12       0
Bank Sta=4975.1,4990
XS Rating Curve= 0 ,0
Exp/Cntr=0.3,0.1

Type RM Length L Ch R = 1 ,6376    ,413,413,413
BEGIN DESCRIPTION:
BOGGY CREEK 13.0
END DESCRIPTION:
XS GIS Cut Line= 3
      2573675.01     13461925.01        2573525.       13461775.
      2573124.96     13461524.97
#Sta/Elev= 30
  4788.1   90.48  4791.7   90.48    4873   83.28  4957.8   74.99  4986.1   70.57
  4996.7   65.21  5003.2   65.21  5006.3   64.52  5006.8   64.02  5020.8   64.02
  5021.3   64.52  5029.1   67.81  5035.6   68.89  5065.7    66.8  5094.6   69.87
  5108.2   70.29    5130    69.7  5239.1   75.37  5247.9   75.44  5275.6   77.63
  5290.9    77.7  5296.8   78.35  5354.6   81.17  5364.1   81.14  5391.2   82.65
  5400.6    82.6  5406.5   83.37  5427.7   84.41  5436.6   85.58    5472   86.65
#Mann= 3 ,-1 , 0
  4788.1     .12       0  5006.3     .05       0  5021.3     .12       0
Bank Sta=5006.3,5021.3
XS Rating Curve= 0 ,0
Exp/Cntr=0.3,0.1

Type RM Length L Ch R = 1 ,5963    ,485,485,485
BEGIN DESCRIPTION:
BOGGY CREEK 12.0
END DESCRIPTION:
XS GIS Cut Line= 4
        2573875.     13461724.99        2573775.       13461475.
       2573670.7     13461301.17      2573489.12     13461170.63
#Sta/Elev= 30
  4734.9   86.99  4759.7   85.12  4821.1   79.47  4842.6   76.49  4874.9   73.32
  4882.7    71.9  4935.5   67.58  4950.3   67.42  4959.7   68.38  4965.1   67.95
  4981.8   62.91  4982.3   62.41  4996.4   62.41  4996.9   62.91  5001.5   66.43
  5007.1   66.43  5017.8   68.87  5048.6   69.05  5134.4   74.37  5186.9   79.02
  5206.9   80.11  5208.9   80.76  5230.4   81.37  5253.6   82.66  5273.4   83.06
  5300.4   85.17  5323.7   85.66    5337   87.05  5372.3   89.06  5430.5   91.32
#Mann= 9 ,-1 , 0
  4734.9     .07       0  4759.7     .12       0  4882.7     .07       0
  4981.8     .05       0  4996.9     .07       0  5048.6     .12       0
  5230.4     .05       0  5253.6    .035       0  5372.3     .05       0
Bank Sta=4981.8,4996.9
XS Rating Curve= 0 ,0
Exp/Cntr=0.3,0.1

Type RM Length L Ch R = 1 ,5478    ,175,175,175
BEGIN DESCRIPTION:
Mapping XS 7964838f
END DESCRIPTION:
XS GIS Cut Line= 4
      2574346.44     13461617.03      2574244.89     13461312.39
       2574125.1     13461216.03      2573573.05     13460911.37
#Sta/Elev= 30
  4602.4   97.24    4710   97.38  4722.6   96.15  4741.6    94.4  4748.1   95.79
  4773.2   92.77  4825.9   81.17  4906.2   75.67  4928.6   72.65  4953.1   67.06
  4963.8   64.61  4970.6   61.51  4971.1   61.01  4985.7   61.51  4986.1   62.74
  4992.6   64.33    5007   64.61  5013.4   66.56  5027.8   67.99  5074.1    69.5
  5107.8   69.02  5173.5   69.43  5214.5   71.48  5233.1   73.44  5270.9   74.35
  5351.5   79.09  5374.1   81.44  5408.2   82.28  5564.3   91.47  5707.8   95.14
#Mann= 8 ,-1 , 0
  4602.4     .05       0  4722.6    .035       0  4953.1     .07       0
  4970.6     .05       0  4985.7     .07       0  5107.8    .035       0
  5214.5     .12       0  5408.2    .035       0
Bank Sta=4970.6,4985.7
XS Rating Curve= 0 ,0
Exp/Cntr=0.3,0.1

Type RM Length L Ch R = 1 ,5303    ,377,377,377
BEGIN DESCRIPTION:
BOGGY CREEK 11.0
END DESCRIPTION:
XS GIS Cut Line= 3
      2574699.61     13461411.49      2574322.58     13461169.15
      2573320.41     13460663.95
#Sta/Elev= 30
  4551.8   96.27  4625.6   96.99  4652.7   94.08  4661.9    94.8  4667.9   93.04
  4698.2   92.67  4704.2   91.03  4735.1   90.98  4770.9    89.2  4776.8   87.34
  4806.9   86.91  4834.3   83.61  4849.5   84.51  4925.8   77.59  4943.3   76.65
  4964.4   73.07  4987.2   61.41  4987.7   60.91  5002.3   61.41  5061.8   67.66
  5067.4   66.51  5107.4   67.59  5245.9   69.31  5328.5   72.79  5451.2   78.81
  5641.8   90.11  5758.7   93.48  5837.4   93.39  5893.2   96.44  6122.3   97.92
#Mann= 10 ,-1 , 0
  4551.8    .035       0  4735.1    .063       0  4925.8    .094       0
  4987.2     .05       0  5002.3    .094       0  5107.4    .035       0
  5328.5    .063       0  5451.2    .035       0  5758.7    .063       0
  5837.4    .035       0
#XS Ineff= 2 ,-1
    4552  4928.4    80.5    5104    5679    79.5
Permanent Ineff=
       F       F
Bank Sta=4987.2,5002.3
XS Rating Curve= 0 ,0
Exp/Cntr=0.3,0.1

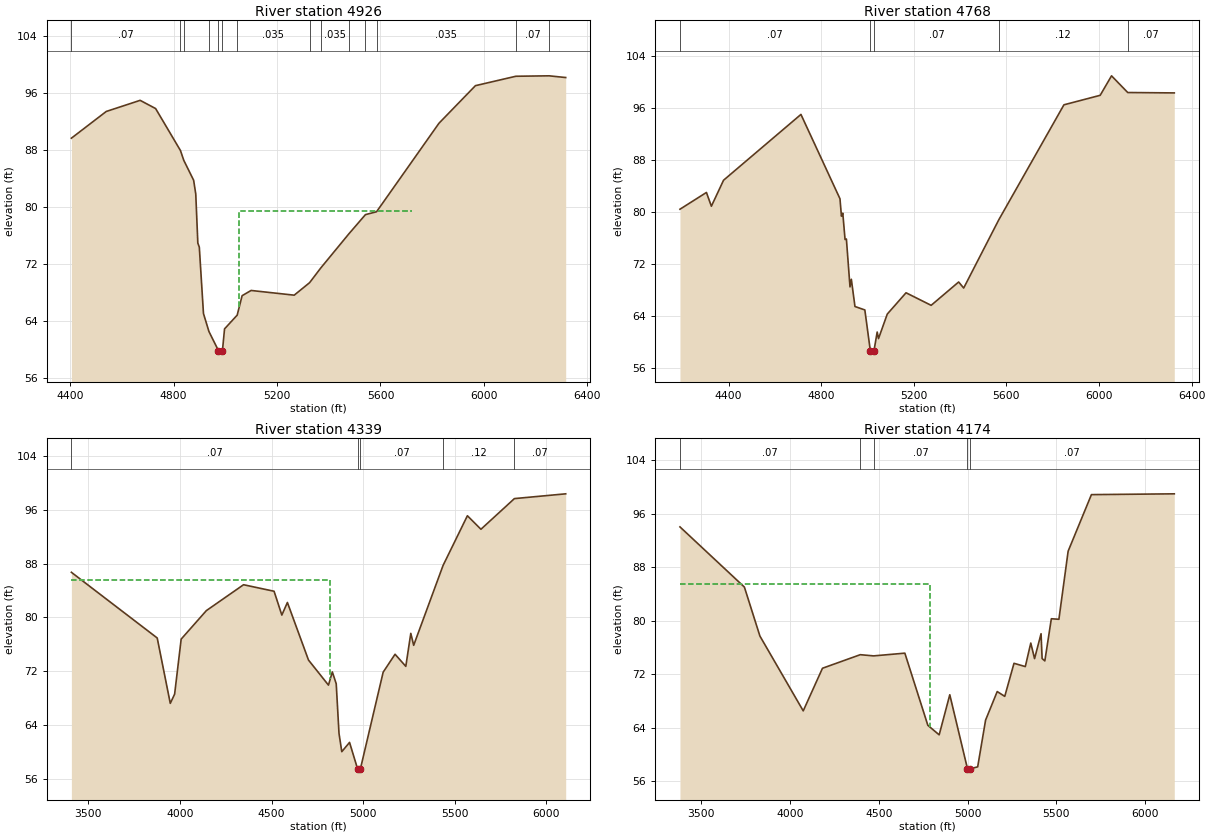
Type RM Length L Ch R = 1 ,4926    ,158,158,158
BEGIN DESCRIPTION:
BOGGY CREEK 9.0
END DESCRIPTION:
XS GIS Cut Line= 3
      2574897.53     13461125.03      2574374.58     13460840.18
      2573190.23     13460265.53
#Sta/Elev= 30
  4404.5   89.66  4539.4   93.41  4670.4   94.97  4730.3   93.82  4826.4   87.93
  4839.3   86.55  4877.4   83.76  4885.6   81.83  4893.6   74.94  4899.3   74.38
  4915.4   65.06  4936.6   62.54  4973.2   59.87  4973.7   59.37  4988.8   59.87
  4996.9   62.91  5045.8   64.84  5064.9   67.57  5099.6    68.3  5266.3   67.64
  5325.8   69.39  5369.2   71.46    5477   76.21  5541.9   78.94  5584.8   79.34
  5826.3   91.76  5967.3   97.03  6123.7   98.35  6252.5   98.41  6316.4   98.17
#Mann= 14 ,-1 , 0
  4404.5     .07       0  4826.4    .094       0  4839.3     .07       0
  4936.6    .094       0  4973.2     .05       0  4988.8    .094       0
  5045.8    .035       0  5325.8     .07       0  5369.2    .035       0
    5477    .063       0  5541.9     .07       0  5584.8    .035       0
  6123.7     .07       0  6252.5    .035       0
#XS Ineff= 2 ,-1
    4404    4833    80.5    5054    5723    79.5
Permanent Ineff=
       F       F
Bank Sta=4973.2,4988.8
XS Rating Curve= 0 ,0
Exp/Cntr=0.3,0.1

Type RM Length L Ch R = 1 ,4768    ,429,429,429
BEGIN DESCRIPTION:
Mapping XS 4a28d8e0
END DESCRIPTION:
XS GIS Cut Line= 3
      2575067.65     13461099.07      2574373.23     13460682.42
      2573216.23     13460036.34
#Sta/Elev= 30
    4190   80.39  4304.3   82.97  4325.7   80.85  4378.2   84.85  4712.5   94.98
  4881.1      82  4887.4   79.32  4893.3   79.78    4903   75.73  4908.8   75.81
  4924.4   68.44  4930.2   69.61  4945.8   65.42  4988.5   64.89  5012.3   58.59
  5012.8   58.09  5027.9   58.59  5041.8   61.49  5047.6   60.48  5085.3   64.25
  5166.4   67.53  5274.9    65.6  5393.7   69.19  5415.4   68.26  5567.4   78.79
  5848.4   96.46  6004.9   97.92    6054  100.92    6124   98.35    6325   98.29
#Mann= 5 ,-1 , 0
    4190     .07       0  5012.3     .05       0  5027.9     .07       0
  5567.4     .12       0    6124     .07       0
Bank Sta=5012.3,5027.9
XS Rating Curve= 0 ,0
Exp/Cntr=0.3,0.1

Type RM Length L Ch R = 1 ,4339    ,165,165,165
BEGIN DESCRIPTION:
Mapping XS 4dfbec19
END DESCRIPTION:
XS GIS Cut Line= 3
      2575479.31     13461197.83      2574132.77     13460334.88
      2573186.22     13459779.25
#Sta/Elev= 30
  3407.9   86.72  3876.2   76.95  3947.5   67.23  3971.2    68.6  4006.9   76.78
  4144.3   81.02  4347.2   84.87  4513.8    83.9  4556.1   80.36  4586.5   82.23
  4701.5   73.67  4810.5   69.94  4831.6    71.9  4852.8   70.15    4868   62.76
  4883.2   60.04  4925.5   61.42  4969.2    57.5  4969.7      57  4984.9    57.5
    5109   71.87  5173.8   74.53  5232.5   72.73  5259.7   77.64  5275.4   75.86
  5435.8   87.74  5568.5   95.13  5642.4   93.12    5825   97.68  6104.8   98.39
#Mann= 5 ,-1 , 0
  3407.9     .07       0  4969.2     .05       0  4984.9     .07       0
  5435.8     .12       0    5825     .07       0
#XS Ineff= 1 ,-1
    3408    4820    85.5
Permanent Ineff=
       F
Bank Sta=4969.2,4984.9
XS Rating Curve= 0 ,0
Exp/Cntr=0.3,0.1

Type RM Length L Ch R = 1 ,4174    ,275,275,275
BEGIN DESCRIPTION:
BOGGY CREEK 8.0
END DESCRIPTION:
XS GIS Cut Line= 3
      2575554.76     13461088.41      2574201.29     13460198.18
      2573211.03     13459585.82
#Sta/Elev= 30
    3380   94.05  3742.9   85.04  3830.3   77.71  4074.3   66.51  4182.7   72.89
  4395.6   74.92  4470.5   74.74  4646.7   75.15  4776.2   64.35    4840   62.92
  4899.8   68.92  4999.5   57.84    5000   57.34  5015.3   57.84  5056.9   58.13
  5101.5   65.13  5166.9    69.4  5209.4   68.68  5261.5   73.63  5325.2   73.14
    5356   76.66  5377.3   74.33  5413.9   78.06  5419.8   74.34  5435.2   73.99
  5471.8    80.3  5514.4   80.22  5566.4   90.41  5697.6   98.88  6164.3      99
#Mann= 5 ,-1 , 0
    3380     .07       0  4395.6     .05       0  4470.5     .07       0
  4999.5     .05       0  5015.3     .07       0
#XS Ineff= 1 ,-1
    3380    4786    85.5
Permanent Ineff=
       F
Bank Sta=4999.5,5015.3
XS Rating Curve= 0 ,0
Exp/Cntr=0.3,0.1