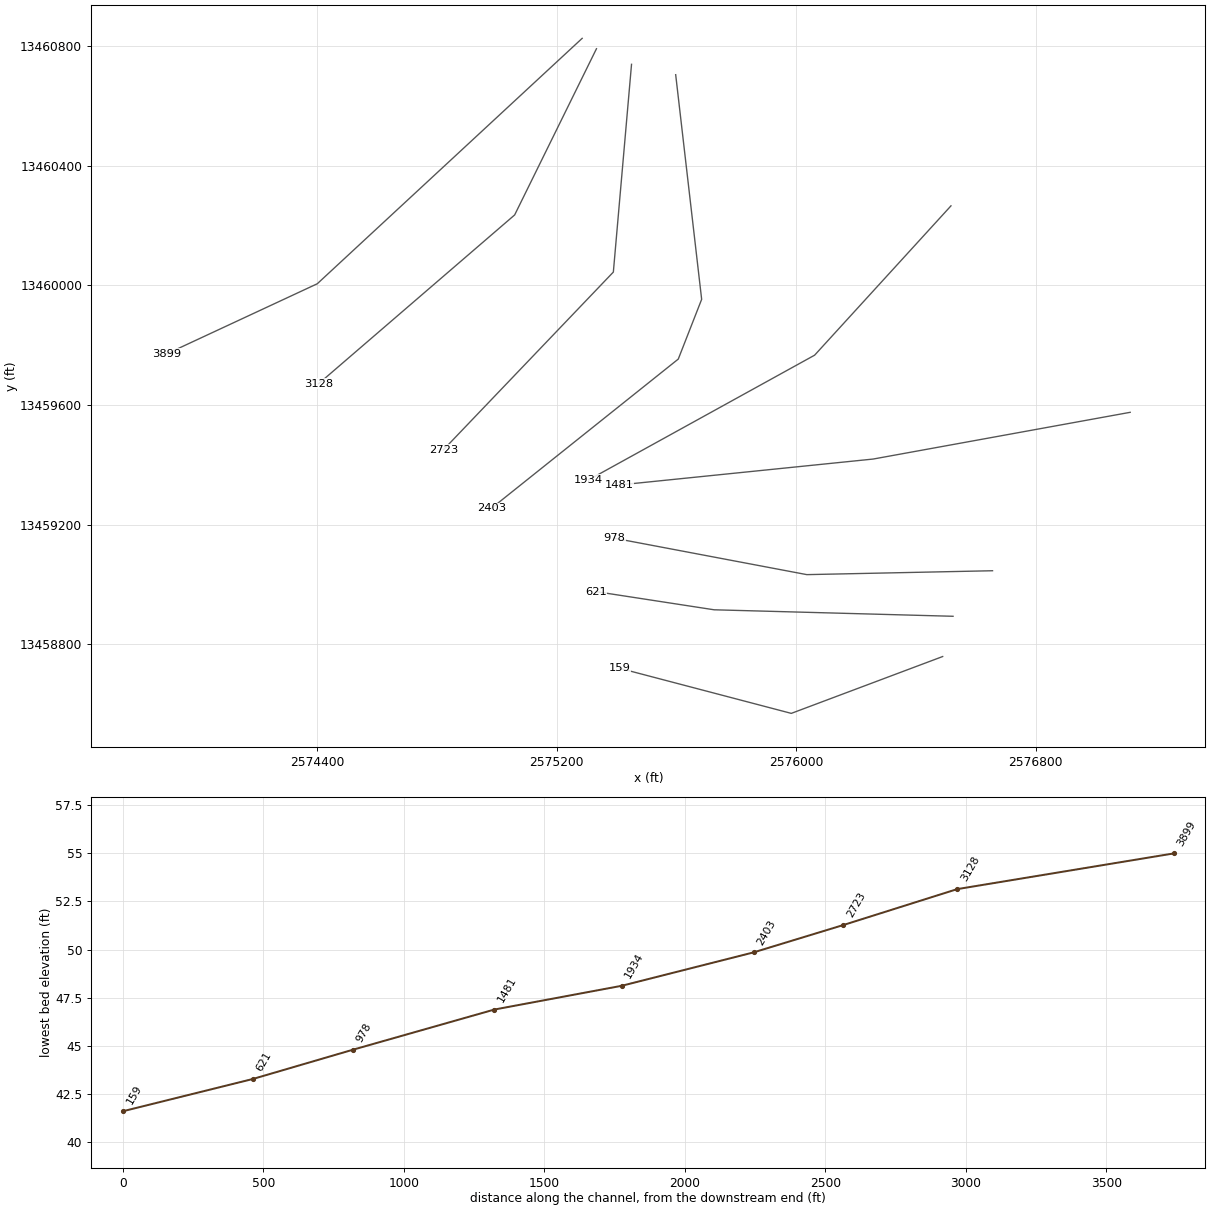
HEC-RAS study BOGGY CREEK.prj: BOGGY CREEK Base Level Engineering

--- BOGGY CREEK.g01 (geometry) --- (continued)

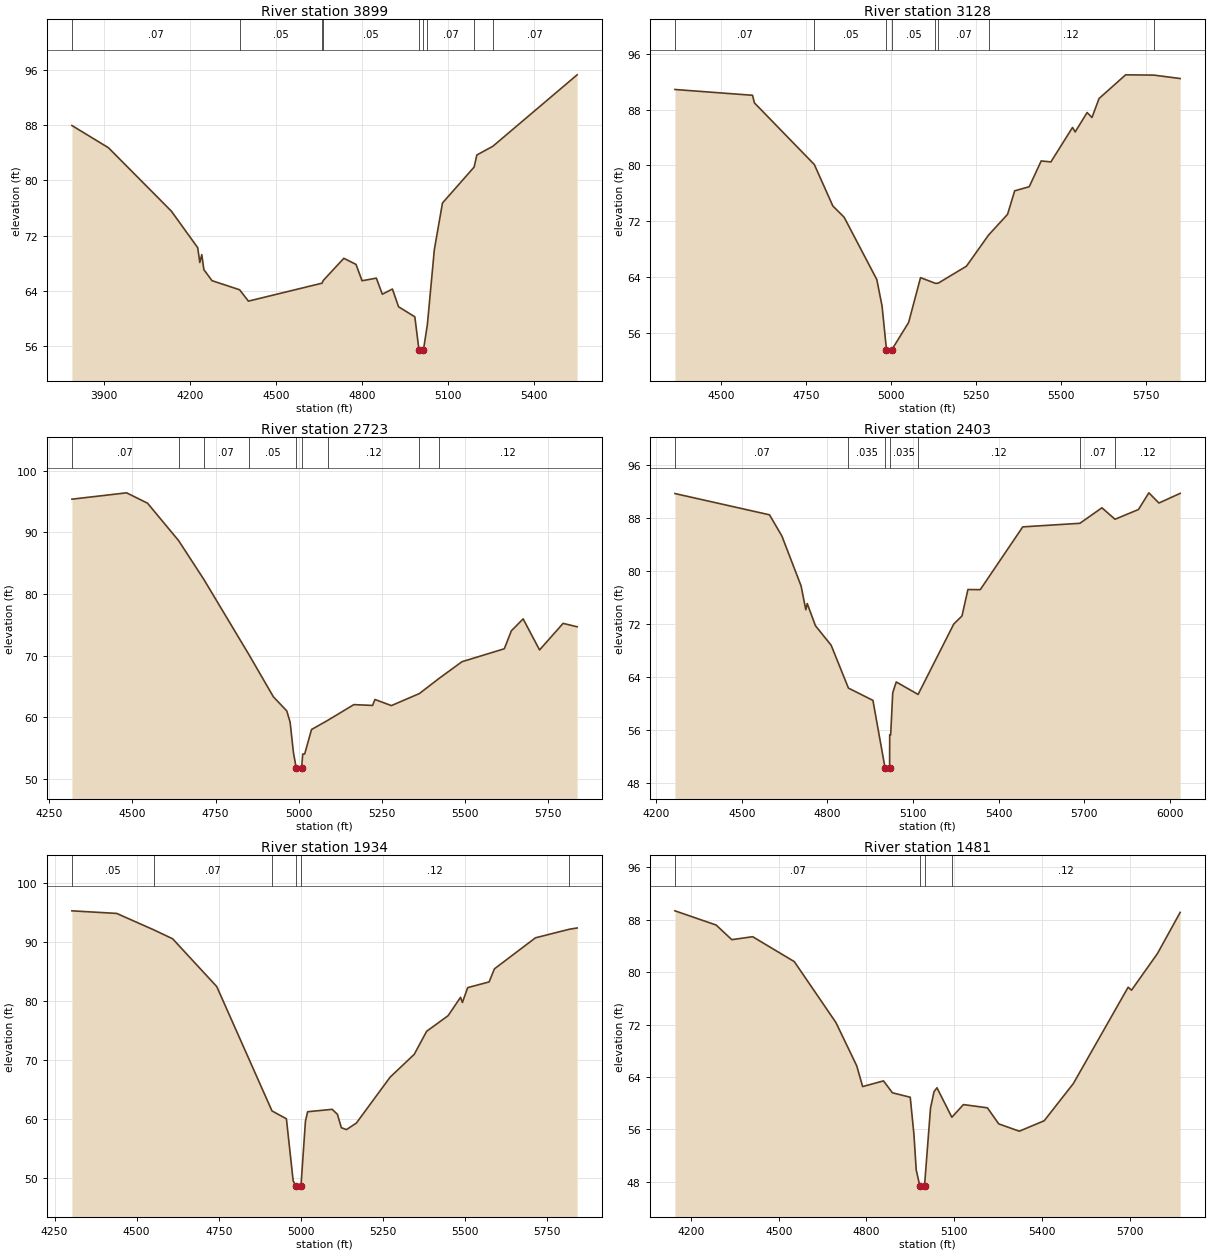
Type RM Length L Ch R = 1 ,3899    ,771,771,771
BEGIN DESCRIPTION:
Mapping XS cc95a5a4
END DESCRIPTION:
XS GIS Cut Line= 3
      2575284.66     13460825.62      2574399.27     13460005.33
      2573895.83     13459770.97
#Sta/Elev= 30
    3789   87.94  3916.5   84.72  4135.9   75.54  4227.8   70.25  4235.1    68.1
    4242   69.24  4249.3   67.07  4277.7   65.47  4373.8   64.16  4404.7   62.51
  4661.6   65.11  4665.7    65.5  4737.5   68.71    4780   67.83    4801   65.46
  4850.9   65.84  4871.8   63.51    4907   64.26  4928.5   61.69  4985.2   60.24
  4999.5   55.48    5000   54.98  5015.3   55.48  5028.9    59.1  5053.2   69.96
  5081.6   76.72    5192   81.92  5201.5   83.67  5257.2   84.93  5551.3   95.28
#Mann= 9 ,-1 , 0
    3789     .07       0  4373.8     .05       0  4661.6     .07       0
  4665.7     .05       0  4999.5     .05       0  5015.3     .05       0
  5028.9     .07       0    5192     .12       0  5257.2     .07       0
Bank Sta=4999.5,5015.3
XS Rating Curve= 0 ,0
Exp/Cntr=0.3,0.1

Type RM Length L Ch R = 1 ,3128    ,405,405,405
BEGIN DESCRIPTION:
Mapping XS b73ae504
END DESCRIPTION:
XS GIS Cut Line= 3
      2575332.41     13460790.89      2575058.99     13460235.37
      2574403.59     13459671.11
#Sta/Elev= 30
  4365.3   90.88  4593.2   90.05  4598.8   88.96  4774.8   80.13    4829   74.21
  4862.3   72.59  4958.3   63.66  4973.7   59.86  4986.6   53.63  4987.1   53.13
  5002.5   53.63  5051.6   57.51  5086.7   63.94  5130.5   63.12  5138.7   63.15
  5221.6   65.58  5286.7   70.05  5342.3      73  5363.2   76.37    5406   76.96
  5441.1   80.65  5469.6   80.51  5533.2   85.45  5540.9    84.8    5576   87.58
  5590.3   86.87  5611.1   89.59  5689.1   92.98    5772   92.94  5849.3   92.45
#Mann= 8 ,-1 , 0
  4365.3     .07       0  4774.8     .05       0  4986.6     .05       0
  5002.5     .05       0  5130.5     .12       0  5138.7     .07       0
  5286.7     .12       0    5772     .07       0
Bank Sta=4986.6,5002.5
XS Rating Curve= 0 ,0
Exp/Cntr=0.3,0.1

Type RM Length L Ch R = 1 ,2723    ,320,320,320
BEGIN DESCRIPTION:
Mapping XS fec4a1a8
END DESCRIPTION:
XS GIS Cut Line= 3
      2575449.62     13460738.81      2575388.85     13460044.39
       2574820.4      13459449.9
#Sta/Elev= 30
    4318   95.39  4482.4   96.42  4545.4   94.74  4638.9   88.67  4714.4   82.41
  4849.2   70.29  4924.1   63.32  4964.3   61.04  4974.3   59.21  4984.3   54.28
  4992.7   51.77  4993.2   51.27  5008.7   51.77  5012.3   54.05  5018.1   54.05
  5038.7   58.02  5086.9   59.49    5166   62.06  5222.3   61.93  5229.6   62.89
  5278.9    61.9  5363.3   63.86  5422.3   66.31  5491.2   69.02  5618.6   71.12
  5639.7   74.03  5675.2   75.97  5724.6   70.93  5795.4   75.24  5837.6   74.69
#Mann= 9 ,-1 , 0
    4318     .07       0  4638.9     .05       0  4714.4     .07       0
  4849.2     .05       0  4992.7     .05       0  5008.7     .05       0
  5086.9     .12       0  5363.3     .07       0  5422.3     .12       0
Bank Sta=4992.7,5008.7
XS Rating Curve= 0 ,0
Exp/Cntr=0.3,0.1

Type RM Length L Ch R = 1 ,2403    ,469,469,469
BEGIN DESCRIPTION:
Mapping XS 2a364708
END DESCRIPTION:
XS GIS Cut Line= 4
      2575597.19     13460704.08      2575683.99     13459953.25
      2575605.87      13459753.6      2574980.85     13459254.45
#Sta/Elev= 30
    4266   91.76  4597.3   88.55  4640.7   85.35    4708   77.81  4724.5   74.21
  4729.5   75.15  4758.3    71.8  4813.3   68.86  4873.8   62.39  4959.7   60.53
    5002   50.35  5002.5   49.85  5018.1   50.35  5018.4   55.32  5021.8   55.32
  5029.1    61.7  5041.4   63.31  5117.9   61.43  5242.9   72.06  5271.7   73.28
  5292.5   77.27  5335.7   77.25  5484.6   86.73  5684.8   87.27    5762   89.61
  5807.9   87.88    5890   89.35  5926.5   91.87  5961.8   90.33  6036.1   91.79
#Mann= 7 ,-1 , 0
    4266     .07       0  4873.8    .035       0    5002    .035       0
  5018.1    .035       0  5117.9     .12       0  5684.8     .07       0
  5807.9     .12       0
Bank Sta=5002,5018.1
XS Rating Curve= 0 ,0
Exp/Cntr=0.3,0.1

Type RM Length L Ch R = 1 ,1934    ,453,453,453
BEGIN DESCRIPTION:
Mapping XS 4c4d335a
END DESCRIPTION:
XS GIS Cut Line= 3
      2576517.31     13460265.73       2576061.6     13459766.62
      2575306.46     13459349.99
#Sta/Elev= 30
  4302.9   95.34  4439.3    94.9  4551.8   92.12  4609.5    90.6  4743.9   82.49
  4912.1   61.39    4956   60.05  4976.5   49.55  4984.2   48.62  4984.7   48.12
  5000.3   48.62    5014   59.68  5020.6   61.25  5095.4   61.66  5111.4   60.81
  5123.3   58.54  5138.9   58.22    5169   59.33  5271.8   67.12  5345.2   70.99
    5383    74.9  5448.4   77.55  5486.2   80.67  5491.9   79.79    5508   82.31
  5573.3   83.28  5589.3   85.49  5714.3   90.76    5817   92.21  5841.2   92.43
#Mann= 6 ,-1 , 0
  4302.9     .05       0  4551.8     .07       0  4912.1     .12       0
  4984.2     .05       0  5000.3     .12       0    5817     .07       0
Bank Sta=4984.2,5000.3
XS Rating Curve= 0 ,0
Exp/Cntr=0.3,0.1

Type RM Length L Ch R = 1 ,1481    ,503,503,503
BEGIN DESCRIPTION:
Mapping XS 765f1b64
END DESCRIPTION:
XS GIS Cut Line= 3
      2577116.27     13459575.64      2576256.91     13459419.39
      2575408.07     13459332.78
#Sta/Elev= 30
  4145.4   89.36  4286.3   87.19  4339.7   84.96    4411   85.41  4553.3   81.61
  4695.5   72.32  4766.7   65.71  4786.9   62.54  4858.2   63.41  4888.7   61.59
  4949.6   60.91  4962.2   55.24    4970   49.83  4982.2   47.39  4982.7   46.89
  4998.4   47.39  5018.9   59.26  5030.8   61.75  5040.9   62.36  5091.8   57.86
  5131.3   59.79  5213.3    59.3    5252   56.85  5322.3   55.73  5407.3   57.32
  5506.9   62.99  5694.3    77.7  5705.9   77.25  5794.8   82.86  5872.1   89.12
#Mann= 4 ,-1 , 0
  4145.4     .07       0  4982.2     .05       0  4998.4     .07       0
  5091.8     .12       0
Bank Sta=4982.2,4998.4
XS Rating Curve= 0 ,0
Exp/Cntr=0.3,0.1

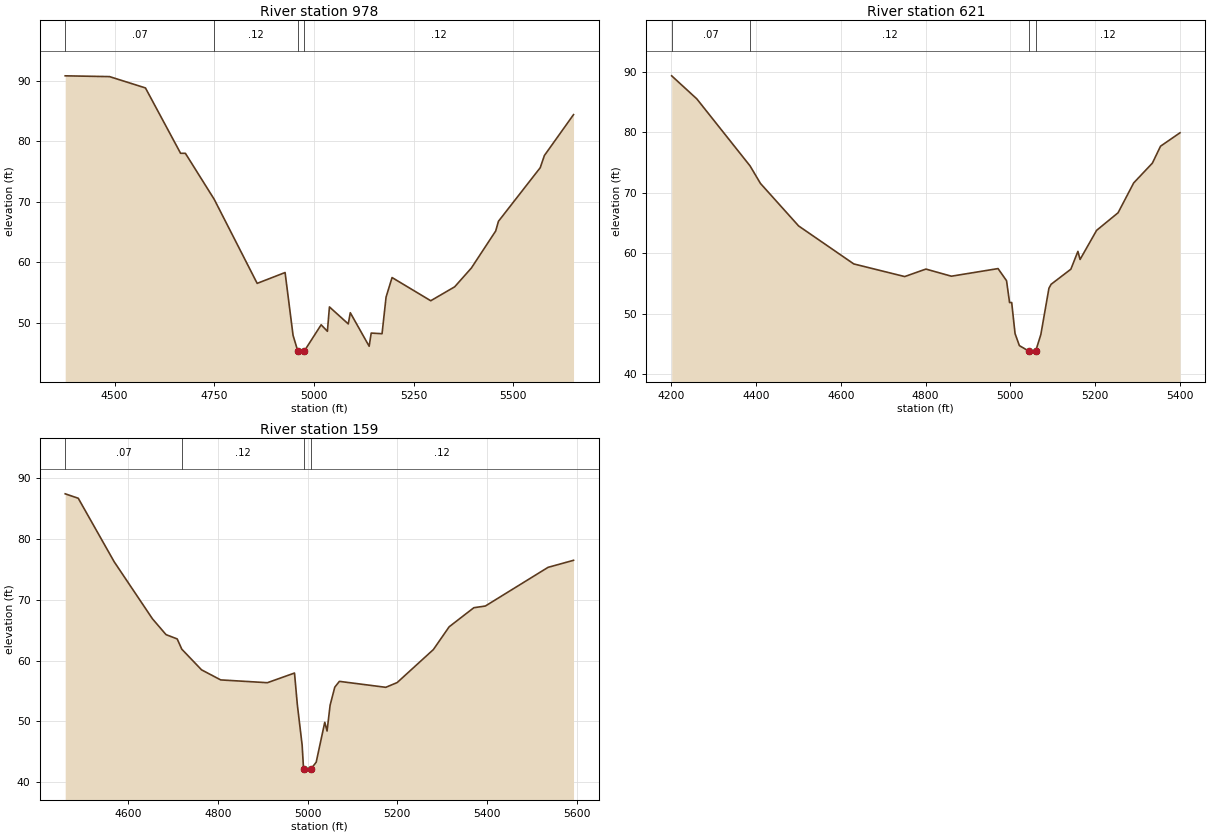
Type RM Length L Ch R = 1 ,978     ,357,357,357
BEGIN DESCRIPTION:
Mapping XS 625db385
END DESCRIPTION:
XS GIS Cut Line= 3
      2576656.19     13459046.13      2576035.56     13459033.11
      2575393.22     13459154.63
#Sta/Elev= 30
  4376.4   90.79  4487.6   90.66  4577.6   88.79  4665.7   77.99  4677.7   77.99
    4750   70.39  4857.7    56.5  4927.7   58.29  4947.7   47.91  4959.6   45.31
  4960.1   44.81  4975.8   45.31  5018.1   49.66  5033.8   48.58  5038.9   52.61
  5086.1    49.8  5091.2   51.65  5138.5   46.11  5143.6   48.29  5170.8   48.18
  5180.9   54.24  5195.9   57.46  5292.9   53.63  5352.9   55.93  5394.7   59.03
  5455.7   65.15  5462.7   66.76  5567.4   75.61  5577.8   77.62  5650.9   84.38
#Mann= 4 ,-1 , 0
  4376.4     .07       0    4750     .12       0  4959.6     .05       0
  4975.8     .12       0
Bank Sta=4959.6,4975.8
XS Rating Curve= 0 ,0
Exp/Cntr=0.3,0.1

Type RM Length L Ch R = 1 ,621     ,462,462,462
BEGIN DESCRIPTION:
Mapping XS dba9d683
END DESCRIPTION:
XS GIS Cut Line= 3
      2576524.23     13458893.91      2575725.65     13458915.61
      2575330.67     13458976.38
#Sta/Elev= 30
  4201.3   89.36  4260.5   85.55  4386.1   74.45  4410.6   71.55  4500.6   64.51
  4630.7   58.22  4750.7   56.13  4800.7   57.37  4860.8   56.19  4970.8   57.45
  4990.8   55.45    4998   51.83    5003   51.83  5010.9   46.69  5021.1    44.7
  5043.3   43.79  5043.8   43.29  5059.5   43.79  5071.7   46.53  5090.8    54.2
  5095.9   54.85  5142.5   57.35  5159.1    60.3  5164.2   58.96  5203.2   63.78
  5253.8   66.69  5290.6   71.63  5334.7   74.91  5353.9   77.71  5399.8   79.93
#Mann= 4 ,-1 , 0
  4201.3     .07       0  4386.1     .12       0  5043.3     .05       0
  5059.5     .12       0
Bank Sta=5043.3,5059.5
XS Rating Curve= 0 ,0
Exp/Cntr=0.3,0.1

Type RM Length L Ch R = 1 ,159     ,0,0,0
BEGIN DESCRIPTION:
BOGGY CREEK 1.0
END DESCRIPTION:
XS GIS Cut Line= 3
      2576489.58     13458759.38      2575983.58     13458569.38
      2575410.02     13458719.98
#Sta/Elev= 30
  4459.5   87.46  4488.6   86.73  4568.7   76.27  4654.1   66.87  4684.3   64.27
  4709.2   63.56  4719.5   61.87  4763.5   58.47  4806.2   56.81  4910.3   56.35
  4970.8   57.94  4977.1   52.75  4987.8    46.1    4991   42.12  4991.5   41.62
  5007.3   42.12  5019.2   43.26  5038.3   49.83  5043.4   48.39  5050.2   52.64
  5060.6   55.61  5070.9   56.57  5174.3   55.59  5199.7   56.37  5280.5   61.81
  5315.7   65.56  5370.7    68.7  5396.4   68.98  5536.2   75.35    5593   76.51
#Mann= 4 ,-1 , 0
  4459.5     .07       0  4719.5     .12       0    4991     .05       0
  5007.3     .12       0
Bank Sta=4991,5007.3
XS Rating Curve= 0 ,0
Exp/Cntr=0.3,0.1

Chan Stop Cuts=-1
Use User Specified Reach Order=0
Composite Channel Slope=5