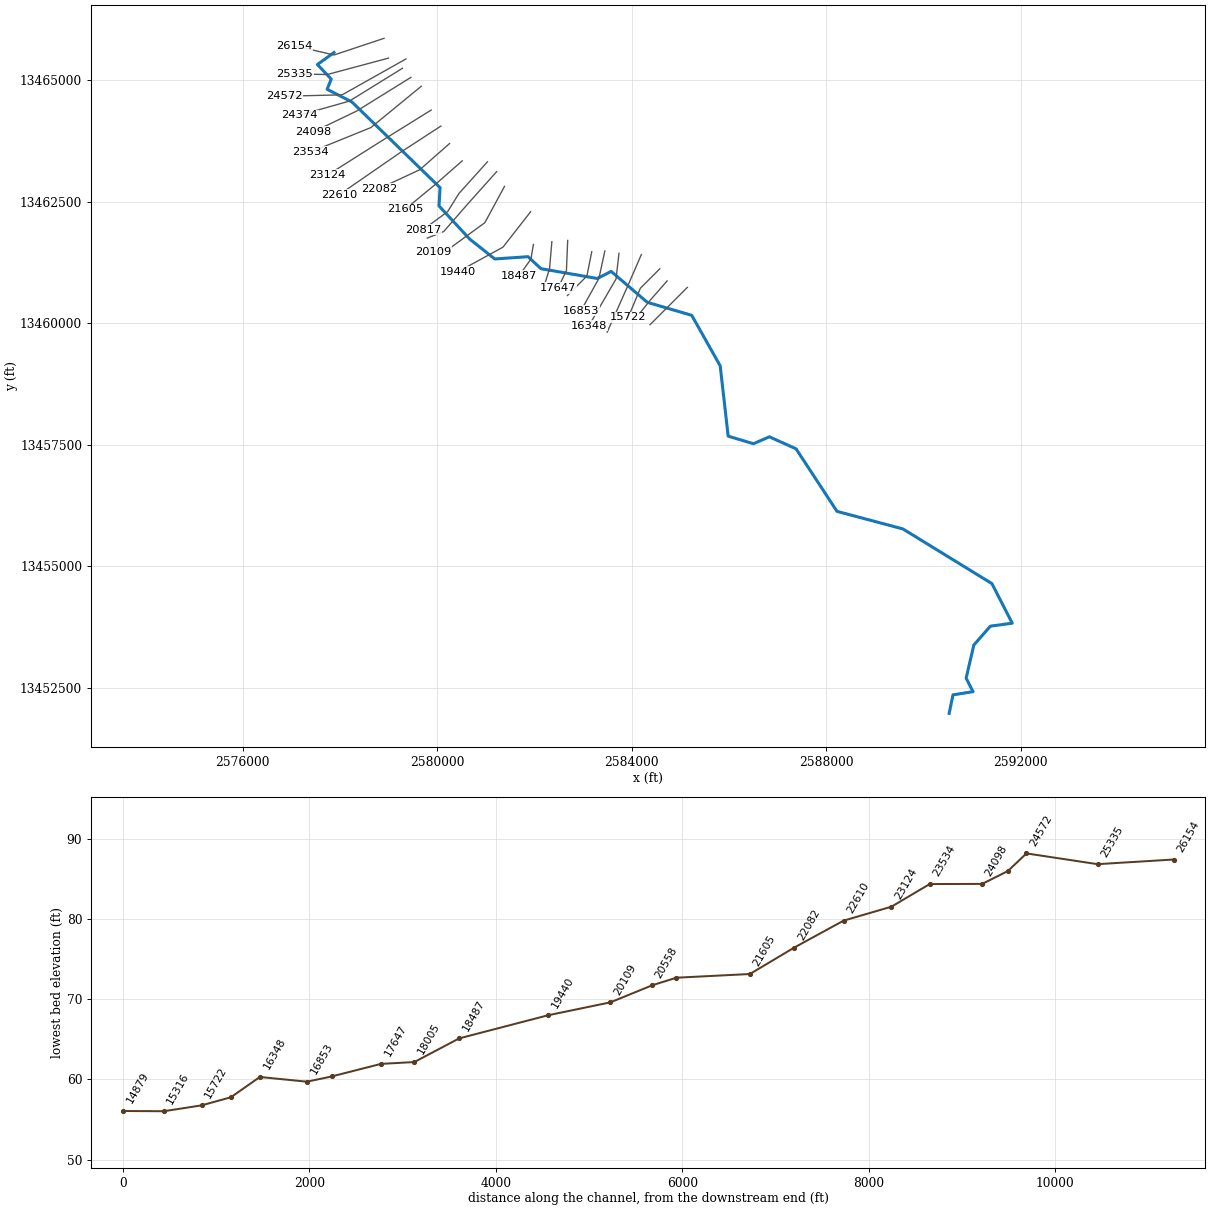
--- COURT BRANCH.prj (project) ---

Proj Title=COURT BRANCH Base Level Engineering
Current Plan=p01
Default Exp/Contr=0.3,0.1
English Units
Geom File=g01
Flow File=f01
Plan File=p01
Y Axis Title=Elevation
X Axis Title(PF)=Main Channel Distance
X Axis Title(XS)=Station
BEGIN DESCRIPTION:
COURT BRANCH
END DESCRIPTION:
DSS Export Rating Curves= 0
DSS Export Rating Curve Sorted= 0
DSS Export Volume Flow Curves= 0
DXF OffsetX= 0
DXF OffsetY= 0
DXF ScaleX= 1
DXF ScaleY= 10

--- COURT BRANCH.p01 (plan) ---

Plan Title=Multiple Run
Program Version=4.10
Short Identifier=Multiple
Geom File=g01
Flow File=f01
Subcritical Flow
K Sum by GR= 0
Std Step Tol= 0.01
Critical Tol= 0.01
Num of Std Step Trials= 20
Max Error Tol= 0.3
Flow Tol Ratio= 0.001
Split Flow NTrial= 30
Split Flow Tol= 0.02
Split Flow Ratio= 0.02
Log Output Level= 0
Friction Slope Method= 1
Unsteady Friction Slope Method= 2
Unsteady Bridges Friction Slope Method= 1
Parabolic Critical Depth
Global Vel Dist= 1 , 1 , 1
Global Log Level= 0
CheckData=True
Encroach Param=-1 ,0,0, 0
BEGIN DESCRIPTION:
Multiple Run
END DESCRIPTION:
Computation Interval=1HOUR
Output Interval=1HOUR
Run HTab= 0
Run UNet= 0
Run PostProcess= 0
Run WQNet= 0
UNET Theta= 1
UNET Theta Warmup= 1
UNET ZTol= 0.02
UNET ZSATol= 0.05
UNET MxIter= 20
UNET MaxInSteps= 0
UNET DtIC= 0
UNET DtMin= 0
UNET MaxCRTS= 20
UNET WFStab= 2
UNET SFStab= 1
UNET WFX= 1
UNET SFX= 1
UNET DSS MLevel= 4
UNET DZMax Abort= 100
UNET Convert EG Bridges= 0
UNET Use Existing IB Tables=-1
UNET Froude Reduction=False
UNET Froude Limit= 1
UNET Froude Power= 10
UNET Time Slicing=0,0, 5
UNET Junction Losses=0
Instantaneous Interval=1HOUR
Write IC File= 0
Write IC File at Sim End=0
Echo Input=False
Echo Parameters=False
Echo Output=False
Write Detailed= 0
WQ AD Non Conservative
WQ ULTIMATE=-1
WQ Max Comp Step=1HOUR
WQ Output Interval=15MIN
WQ Output Selected Increments= 0
WQ Output face flow=0
WQ Output face velocity=0
WQ Output face area=0
WQ Output face dispersion=0
WQ Output cell volume=0
WQ Output cell surface area=0
WQ Output cell continuity=0
WQ Output cumulative cell continuity=0
WQ Output face conc=0
WQ Output face dconc_dx=0
WQ Output face courant=0
WQ Output face peclet=0
WQ Output face adv mass=0
WQ Output face disp mass=0
WQ Output cell mass=0
WQ Output cell source sink temp=0
WQ Output cell source sink nsm=0
WQ Output MaxMinRange=-1
WQ Daily Max Min Mean=-1
WQ Daily Range=0
WQ Daily Time=0
WQ Create Restart=0
WQ Fixed Restart=0
WQ System Summary=0
WQ Use Fixed Temperature=0
Sorting and Armoring Iterations= 10
XS Update Threshold= 0.02
Hydraulics Update Threshold= 0.02
Energy Slope Method= 1
Volume Change Method= 0
XS Weighting Method= 0
Number of US Weighted Cross Sections= 1
Number of DS Weighted Cross Sections= 1
Upstream XS Weight=0.25
Main XS Weight=0.5
Downstream XS Weight=0.25
Number of DS XS's Weighted with US Boundary= 1
Upstream Boundary Weight= 1
Weight of XSs Associated with US Boundary= 0
Number of US XS's Weighted with DS Boundary= 1
Downstream Boundary Weight= 0.5
Weight of XSs Associated with DS Boundary= 0.5
Sediment Output Level= 4
Mass or Volume Output= 0
Output Increment Type= 1
Profile and TS Output Increment= 10
XS Output Flag= 0
XS Output Increment= 10
Disregard all LS=0
Disregard all Conn=0
Disregard all Breaches=0
Disregard all Pumps=0

--- COURT BRANCH.f01 (steady flow) ---

Flow Title=Multiple
Program Version=4.10
Number of Profiles= 7
Profile Names=10-year,25-year,50-year,1pct_min,100-year,1pct_plu,500-year
River Rch & RM=COURT BRANCH,Reach-1         ,26154
     574     891    1165     737    1470    2933    2311
River Rch & RM=COURT BRANCH,Reach-1         ,25335
     915    1456    1937    1244    2482    4952    4028
River Rch & RM=COURT BRANCH,Reach-1         ,24098
    1154    1857    2490    1611    3213    6412    5292
River Rch & RM=COURT BRANCH,Reach-1         ,21605
    1152    1859    2497    1618    3228    6441    5336
River Rch & RM=COURT BRANCH,Reach-1         ,20817
    1281    2079    2803    1823    3636    7256    6054
River Rch & RM=COURT BRANCH,Reach-1         ,19440
    1543    2521    3413    2228    4446    8871    7459
River Rch & RM=COURT BRANCH,Reach-1         ,16348
    1752    2873    3898    2549    5085   10147    8559
River Rch & RM=COURT BRANCH,Reach-1         ,9534
    2316    3840    5250    3456    6895   13757   11761
River Rch & RM=COURT BRANCH,Reach-1         ,374
    2714    4526    6214    4104    8189   16338   14066
Boundary for River Rch & Prof#=COURT BRANCH,Reach-1         , 1
Up Type= 0
Dn Type= 3
Dn Slope=0.00107
Boundary for River Rch & Prof#=COURT BRANCH,Reach-1         , 2
Up Type= 0
Dn Type= 3
Dn Slope=0.00107
Boundary for River Rch & Prof#=COURT BRANCH,Reach-1         , 3
Up Type= 0
Dn Type= 3
Dn Slope=0.00107
Boundary for River Rch & Prof#=COURT BRANCH,Reach-1         , 4
Up Type= 0
Dn Type= 3
Dn Slope=0.00107
Boundary for River Rch & Prof#=COURT BRANCH,Reach-1         , 5
Up Type= 0
Dn Type= 3
Dn Slope=0.00107
Boundary for River Rch & Prof#=COURT BRANCH,Reach-1         , 6
Up Type= 0
Dn Type= 3
Dn Slope=0.00107
Boundary for River Rch & Prof#=COURT BRANCH,Reach-1         , 7
Up Type= 0
Dn Type= 3
Dn Slope=0.00107
DSS Import GetInterval= 0
DSS Import GetPeak= 0
DSS Import FillOption= 0

--- COURT BRANCH.g01 (geometry) ---

Geom Title=Existing Conditions
Program Version=4.10

River Reach=COURT BRANCH    ,Reach-1
Reach XY= 30
        2577875.       13465575.      2577532.46     13465328.61
      2577817.22      13465028.4      2577732.47     13464818.92
      2578242.05     13464558.51      2580055.23     13462795.09
      2580033.85     13462418.05      2580665.22     13461735.52
      2581180.85     13461326.54      2581864.56     13461373.95
      2582130.67     13461126.98      2583290.42     13460925.03
      2583573.72     13461071.63        2584318.     13460434.16
      2585231.21      13460167.2      2585816.76     13459128.23
      2585980.61     13457680.59      2586500.04      13457524.5
      2586828.31     13457666.93      2587377.31     13457419.18
      2588218.93     13456132.45       2589573.5     13455771.39
      2591405.37     13454645.48      2591822.89     13453830.88
      2591372.33      13453769.7      2591033.13     13453381.07
      2590874.59       13452700.      2591017.24     13452421.58
      2590604.61     13452355.95        2590525.       13451975.

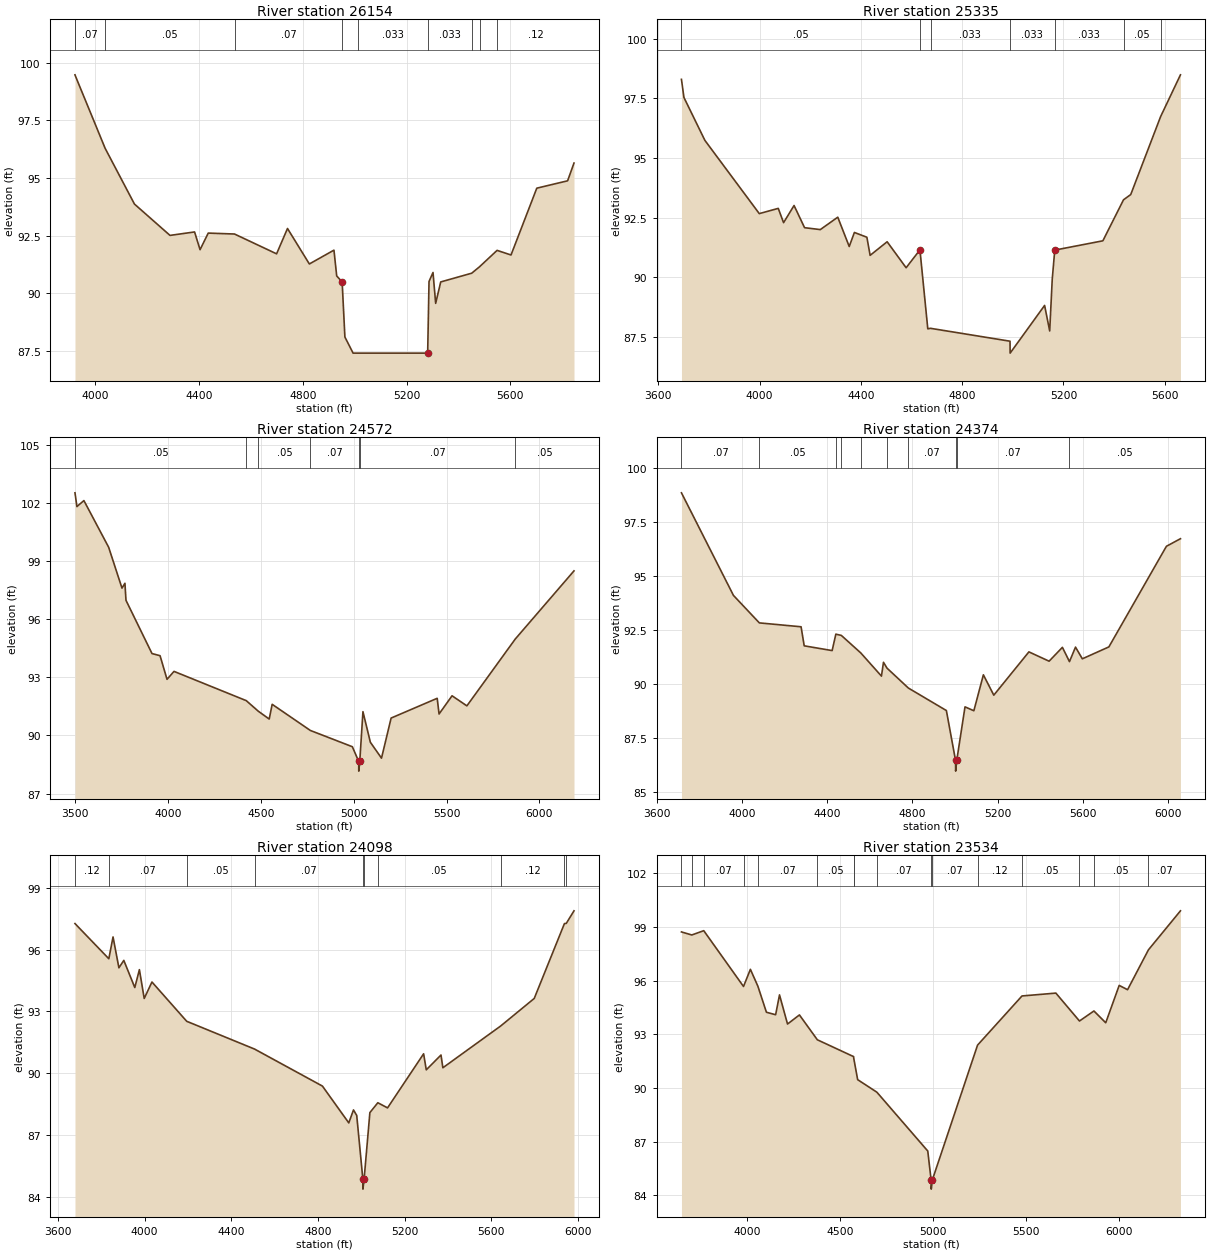
Type RM Length L Ch R = 1 ,26154   ,819,819,819
BEGIN DESCRIPTION:
COURT BRANCH 53.0
END DESCRIPTION:
XS GIS Cut Line= 3
      2578902.66     13465867.55        2577875.       13465525.
      2577055.27      13465715.4
#Sta/Elev= 30
    3921   99.48  3921.5   99.46  4037.3   96.29  4150.4   93.87  4287.5   92.51
  4382.3   92.66  4403.4   91.89    4435   92.61  4536.3   92.57  4698.6   91.71
  4740.7   92.81    4825   91.27  4919.9   91.87  4930.5   90.75  4951.5   90.49
  4962.1    88.1  4993.7    87.4  5012.5    87.4  5281.4    87.4  5286.6   90.51
    5302    90.9  5312.2   89.56  5331.7   90.49  5451.4   90.87  5481.6   91.15
  5549.1   91.86  5602.9   91.66  5702.3   94.56  5821.2   94.88  5845.8   95.65
#Mann= 10 ,-1 , 0
    3921     .05       0  3921.5     .07       0  4037.3     .05       0
  4536.3     .07       0  4951.5     .05       0  5012.5    .033       0
  5281.4    .033       0  5451.4     .12       0  5481.6      .1       0
  5549.1     .12       0
Bank Sta=4951.5,5281.4
XS Rating Curve= 0 ,0
Exp/Cntr=0.3,0.1

Type RM Length L Ch R = 1 ,25335   ,763,763,763
BEGIN DESCRIPTION:
Mapping XS 8b8b8806
END DESCRIPTION:
XS GIS Cut Line= 3
      2578994.49     13465460.18      2577737.57     13465123.38
      2577068.71     13465133.78
#Sta/Elev= 30
  3691.7    98.3  3701.5   97.54  3784.3   95.74    3999   92.67  4073.9   92.89
  4094.9   92.29  4136.3   93.01  4177.8   92.08  4239.9      92  4308.9   92.52
  4354.1   91.29  4374.5   91.88  4423.8   91.68  4436.6   90.92  4503.8   91.49
  4578.7    90.4  4633.3   91.15  4664.3   87.84  4675.1   87.86  4988.9   87.32
  4989.4   86.82  5125.5   88.82  5145.6   87.75  5155.6   89.91  5165.6   91.14
  5355.6   91.53  5437.1   93.25  5465.6   93.47  5583.6   96.74  5661.9   98.49
#Mann= 7 ,-1 , 0
  3691.7     .05       0  4633.3     .05       0  4675.1    .033       0
  4988.9    .033       0  5165.6    .033       0  5437.1     .05       0
  5583.6     .07       0
Bank Sta=4633.3,5165.6
XS Rating Curve= 0 ,0
Exp/Cntr=0.3,0.1

Type RM Length L Ch R = 1 ,24572   ,198,198,198
BEGIN DESCRIPTION:
Mapping XS 629899c3
END DESCRIPTION:
XS GIS Cut Line= 3
      2579353.03     13465442.84      2578042.04     13464704.65
       2576858.1     13464676.47
#Sta/Elev= 30
    3498  102.53  3508.4  101.82    3546  102.13  3679.4   99.72  3751.2   97.61
  3767.1   97.86  3772.8   96.98    3913   94.23  3956.4   94.12  3993.9    92.9
  4031.5   93.31  4420.7    91.8  4486.2   91.25  4544.5   90.85  4560.5   91.61
  4766.2   90.26  4992.5   89.42  5026.7   88.66  5027.1   88.16  5032.5   88.66
  5049.6   91.23  5089.6   89.65  5149.6   88.83  5201.4    90.9  5449.7   91.92
  5459.7   91.11  5529.7   92.05  5609.7   91.53  5870.3   94.98  6186.8    98.5
#Mann= 7 ,-1 , 0
    3498     .05       0  4420.7     .07       0  4486.2     .05       0
  4766.2     .07       0  5026.7     .05       0  5032.5     .07       0
  5870.3     .05       0
Bank Sta=5026.7,5032.5
XS Rating Curve= 0 ,0
Exp/Cntr=0.3,0.1

Type RM Length L Ch R = 1 ,24374   ,276,276,276
BEGIN DESCRIPTION:
Mapping XS c07cfc63
END DESCRIPTION:
XS GIS Cut Line= 3
      2579282.68     13465251.84      2578190.42      13464575.9
       2577171.6     13464286.58
#Sta/Elev= 30
  3715.5   98.83  3959.7   94.09  4081.3   92.82  4277.3   92.64    4292   91.76
  4423.2   91.54  4440.6    92.3  4466.5   92.24  4557.9   91.43  4654.8   90.36
  4664.3      91  4680.8   90.73  4781.1   89.81  4959.7   88.77  5002.7   86.47
  5003.2   85.97  5008.5   86.47  5047.2   88.94  5088.8   88.76  5133.5   90.42
  5182.4   89.48  5347.3   91.48  5442.2   91.05  5504.6   91.69  5537.8   91.03
  5566.2    91.7  5598.2   91.16  5722.9   91.71  5993.2   96.36  6059.1   96.71
#Mann= 10 ,-1 , 0
  3715.5     .07       0  4081.3     .05       0  4440.6     .07       0
  4466.5     .05       0  4557.9     .07       0  4680.8     .05       0
  4781.1     .07       0  5002.7     .05       0  5008.5     .07       0
  5537.8     .05       0
Bank Sta=5002.7,5008.5
XS Rating Curve= 0 ,0
Exp/Cntr=0.3,0.1

Type RM Length L Ch R = 1 ,24098   ,564,564,564
BEGIN DESCRIPTION:
Mapping XS 7f1e65ec
END DESCRIPTION:
XS GIS Cut Line= 3
      2579456.29     13465064.33      2578338.27     13464369.91
      2577449.73       13463943.
#Sta/Elev= 30
  3679.1   97.27  3835.2   95.56  3854.6   96.62  3881.7   95.12  3904.3   95.48
    3955   94.16  3976.2   95.03  3998.5   93.63  4034.1   94.43  4194.4   92.52
  4507.3   91.17  4820.5   89.37  4942.1   87.58  4963.8   88.21  4978.8   87.94
  5006.9   84.86  5007.4   84.36  5012.9   84.86  5039.4   88.08  5076.1   88.56
  5120.9   88.31  5287.3   90.94  5299.6   90.16  5367.5   90.88  5376.1   90.26
  5642.7   92.29  5797.6   93.63  5936.9   97.27  5945.4   97.28    5981   97.89
#Mann= 10 ,-1 , 0
  3679.1     .12       0  3835.2     .07       0  4194.4     .05       0
  4507.3     .07       0  5006.9     .05       0  5012.9     .07       0
  5076.1     .05       0  5642.7     .12       0  5936.9     .05       0
  5945.4     .07       0
Bank Sta=5006.9,5012.9
XS Rating Curve= 0 ,0
Exp/Cntr=0.3,0.1

Type RM Length L Ch R = 1 ,23534   ,410,410,410
BEGIN DESCRIPTION:
Mapping XS 7c9a0fd0
END DESCRIPTION:
XS GIS Cut Line= 3
      2579670.21     13464881.75      2578632.91     13464031.08
      2577391.63     13463527.62
#Sta/Elev= 30
  3647.5   98.72  3703.1   98.55  3767.3   98.79  3980.9   95.67  4017.9   96.63
  4058.3   95.68    4104   94.23  4153.5   94.09  4174.3    95.2  4217.4   93.57
  4281.3   94.08  4377.6   92.69  4572.2   91.75  4573.1   91.66  4594.2   90.46
  4697.4   89.76  4970.9   86.47    4989   84.84  4989.5   84.34    4995   84.84
  5238.3   92.39  5477.1   95.14  5659.1    95.3  5785.9   93.74  5863.6    94.3
    5927   93.64  5999.3   95.73  6044.3   95.49  6156.5   97.72  6328.5    99.9
#Mann= 16 ,-1 , 0
  3647.5     .07       0  3703.1     .12       0  3767.3     .07       0
  3980.9     .12       0  4058.3     .07       0  4377.6     .05       0
  4572.2     .07       0  4573.1     .05       0  4697.4     .07       0
    4989     .05       0    4995     .07       0  5238.3     .12       0
  5477.1     .05       0  5785.9     .07       0  5863.6     .05       0
  6156.5     .07       0
Bank Sta=4989,4995
XS Rating Curve= 0 ,0
Exp/Cntr=0.3,0.1

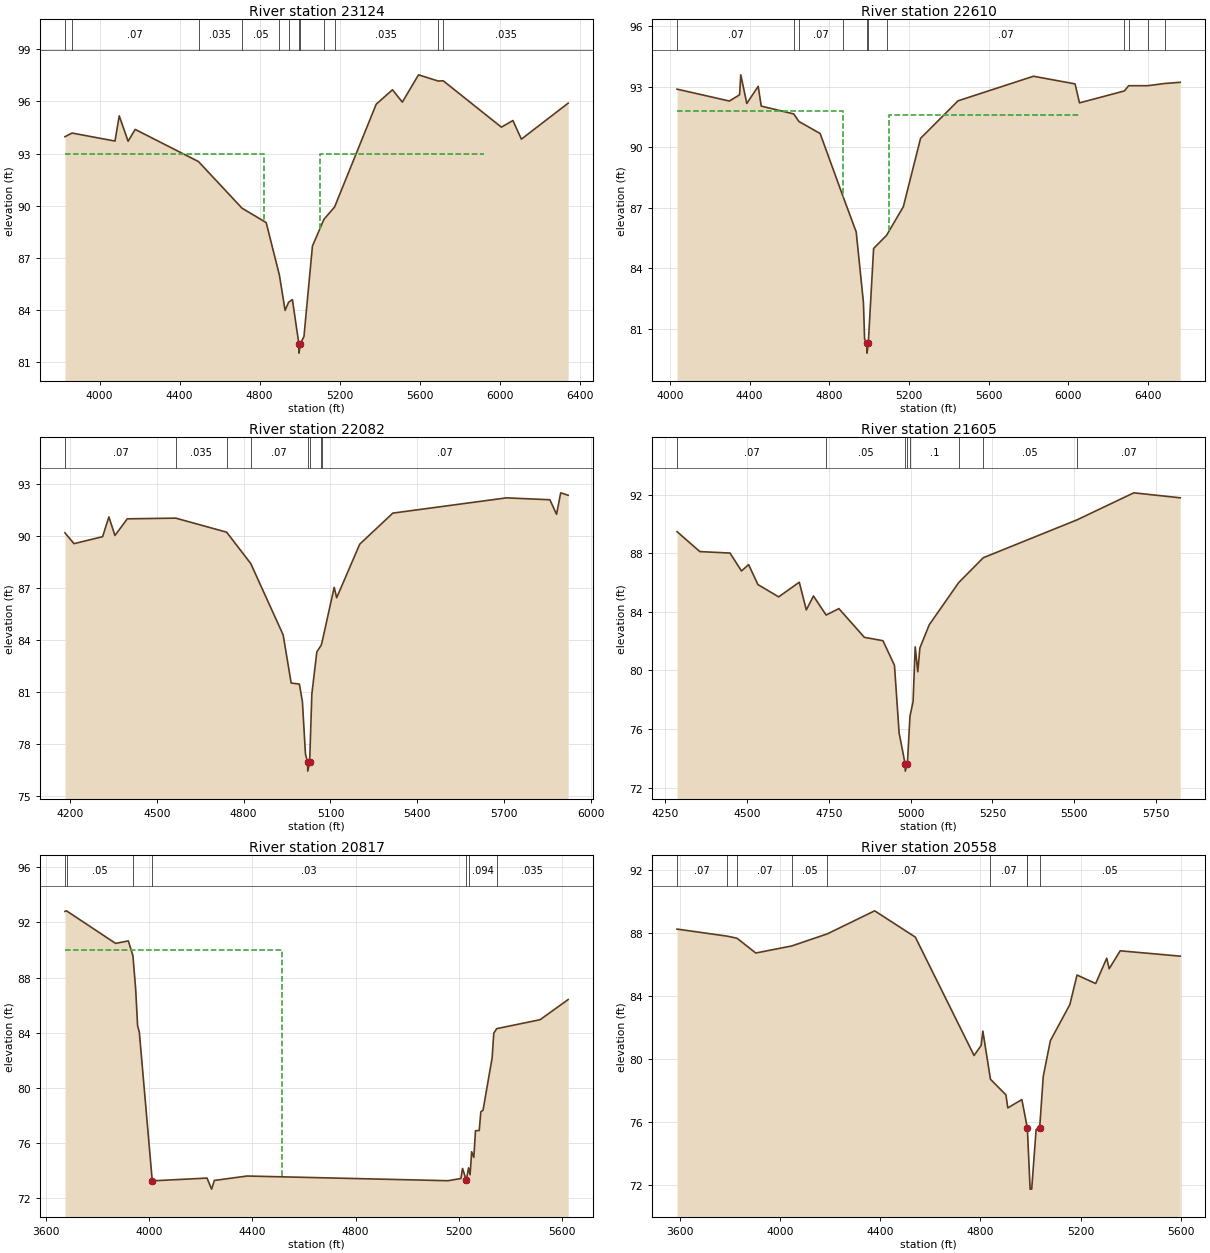
Type RM Length L Ch R = 1 ,23124   ,514,514,514
BEGIN DESCRIPTION:
Mapping XS 61738505
END DESCRIPTION:
XS GIS Cut Line= 3
      2579873.03     13464391.63      2578874.72     13463770.95
      2577743.18     13463054.53
#Sta/Elev= 30
    3827   93.97  3862.5   94.18  4077.1   93.72  4098.3   95.17  4142.6   93.71
  4177.9   94.39  4494.4   92.54  4711.7   89.86  4832.7   89.03  4898.7   86.01
  4927.1   83.98  4944.9   84.45  4963.7    84.6  4996.4   82.02  4996.9   81.52
  5002.5   82.02  5021.5   82.48  5063.8   87.68  5121.4   89.22  5174.2   89.92
  5382.5   95.84  5463.8   96.67    5513   95.96    5594   97.53    5693   97.17
  5717.1   97.19    6008   94.52  6065.7    94.9    6108   93.83  6341.8    95.9
#Mann= 12 ,-1 , 0
    3827    .035       0  3862.5     .07       0  4494.4    .035       0
  4711.7     .05       0  4898.7      .1       0  4944.9    .035       0
  4996.4    .035       0  5002.5    .035       0  5121.4     .07       0
  5174.2    .035       0    5693     .07       0  5717.1    .035       0
#XS Ineff= 2 ,-1
    3827    4823      93    5100    5923      93
Permanent Ineff=
       F       F
Bank Sta=4996.4,5002.5
XS Rating Curve= 0 ,0
Exp/Cntr=0.3,0.1

Type RM Length L Ch R = 1 ,22610   ,528,528,528
BEGIN DESCRIPTION:
Mapping XS f709a8e6
END DESCRIPTION:
XS GIS Cut Line= 3
      2580072.62     13464061.73      2579252.33      13463527.9
      2577978.78     13462647.39
#Sta/Elev= 30
  4035.6   92.87  4298.3   92.28  4349.7   92.59  4355.7   93.58  4385.9   92.16
  4443.2   93.01  4458.4   92.03  4621.8   91.64  4647.3   91.27  4754.2   90.67
  4869.9   87.53  4935.3   85.79  4971.6    82.3  4977.5   80.47  4989.2   80.28
  4989.7   79.78  4996.1   80.28  5022.7   84.97  5087.7   85.62    5172   87.04
  5258.5   90.43  5446.4   92.29  5825.6   93.51  6034.4   93.13  6056.6   92.19
    6282   92.78  6303.5   93.04  6399.3   93.04  6484.2   93.15  6562.6   93.21
#Mann= 11 ,-1 , 0
  4035.6     .07       0  4621.8    .035       0  4647.3     .07       0
  4869.9      .1       0  4989.2     .05       0  4996.1      .1       0
  5087.7     .07       0    6282    .035       0  6303.5     .07       0
  6399.3    .035       0  6484.2     .07       0
#XS Ineff= 2 ,-1
    4035    4871    91.8    5100    6053    91.6
Permanent Ineff=
       F       F
Bank Sta=4989.2,4996.1
XS Rating Curve= 0 ,0
Exp/Cntr=0.3,0.1

Type RM Length L Ch R = 1 ,22082   ,477,477,477
BEGIN DESCRIPTION:
COURT BRANCH 47.0
END DESCRIPTION:
XS GIS Cut Line= 3
      2580251.26      13463702.8      2579637.34     13463162.67
      2578801.61     13462773.97
#Sta/Elev= 30
  4182.3   90.17  4213.7   89.55  4312.4   89.95  4334.2   91.09  4355.1   90.02
  4397.8   90.98  4565.4   91.02  4741.3   90.21  4824.6    88.4  4936.5   84.29
  4964.2   81.51  4992.7   81.45  5003.2   80.42  5013.6   77.42  5021.1   76.93
  5021.6   76.43  5028.1   76.93  5035.7   80.88    5053   83.31    5068   83.69
  5072.1   83.95  5112.9   87.03  5121.6   86.43  5201.3   89.52  5315.7   91.31
  5708.4   92.19  5858.6   92.08  5881.5   91.24  5895.9   92.48  5921.7   92.34
#Mann= 8 ,-1 , 0
  4182.3     .07       0  4565.4    .035       0  4741.3     .05       0
  4824.6     .07       0  5021.1     .05       0  5028.1     .07       0
    5068      .1       0  5072.1     .07       0
Bank Sta=5021.1,5028.1
XS Rating Curve= 0 ,0
Exp/Cntr=0.3,0.1

Type RM Length L Ch R = 1 ,21605   ,788,788,788
BEGIN DESCRIPTION:
COURT BRANCH 46.0
END DESCRIPTION:
XS GIS Cut Line= 3
      2580511.61     13463346.84        2579975.       13462875.
      2579339.55     13462350.36
#Sta/Elev= 30
  4285.7   89.47  4355.5   88.11  4447.6   88.01  4482.7   86.79  4504.5   87.22
    4533   85.86  4596.5   85.02  4659.5   86.02    4681   84.13  4702.8   85.08
  4741.6   83.78  4780.6   84.22  4858.4   82.26  4915.3   82.03  4950.5   80.35
  4964.7   75.74    4983   73.63  4983.5   73.13    4990   73.63  4997.9   76.88
  5007.4   77.87  5013.9   81.61  5021.8   79.91  5028.2   81.53  5056.9   83.12
  5147.1      86    5222   87.69  5508.1   90.27  5682.3   92.12  5824.3   91.78
#Mann= 8 ,-1 , 0
  4285.7     .07       0  4741.6     .05       0    4983     .05       0
    4990     .05       0  4997.9      .1       0  5147.1     .07       0
    5222     .05       0  5508.1     .07       0
Bank Sta=4983,4990
XS Rating Curve= 0 ,0
Exp/Cntr=0.3,0.1

Type RM Length L Ch R = 1 ,20817   ,259,259,259
BEGIN DESCRIPTION:
Mapping XS a4b95a87
END DESCRIPTION:
XS GIS Cut Line= 4
      2581030.45     13463326.65      2580444.52     13462675.62
      2580212.75     13462303.23      2579702.34     13461925.63
#Sta/Elev= 30
  3674.2    92.8  3680.2   92.84  3870.4   90.48  3919.7   90.66  3937.5   89.59
  3948.1   87.18  3955.6   84.52  3962.3   84.05  4012.4   73.27  4224.6   73.47
  4242.4   72.67    4253    73.3  4380.1   73.62  5158.1   73.28  5208.2   73.44
  5214.4   74.17    5229   73.32  5237.8   74.21  5243.6   73.71  5249.8   75.38
  5258.2   74.97  5264.5    76.9  5279.1   76.92  5285.3   78.28  5293.7   78.38
  5329.2    82.2  5335.4   83.97  5346.7    84.3    5515   84.95  5623.6   86.41
#Mann= 7 ,-1 , 0
  3674.2     .07       0  3680.2     .05       0  3937.5     .07       0
  4012.4     .03       0    5229     .03       0  5237.8    .094       0
  5346.7    .035       0
#XS Ineff= 2 , 0
       0  4514.6      90               0
Permanent Ineff=
       F       F
Bank Sta=4012.4,5229
XS Rating Curve= 0 ,0
Exp/Cntr=0.3,0.1

Type RM Length L Ch R = 1 ,20558   ,449,449,449
BEGIN DESCRIPTION:
Mapping XS bb30c1af
END DESCRIPTION:
XS GIS Cut Line= 4
      2581219.74     13463123.99      2580629.44     13462464.24
      2580130.31     13461891.32      2579792.44     13461756.24
#Sta/Elev= 30
  3588.5   88.25  3789.1    87.8  3827.9   87.67  3902.8   86.73  4046.9   87.18
    4189   87.95  4377.5   89.41  4539.8   87.74  4774.3   80.22  4802.8   80.86
  4809.4   81.77  4839.8   78.71  4901.5   77.72  4909.1   76.89  4965.1   77.42
  4984.8    75.8    4987   75.64  4998.1   71.73  5004.4   71.73  5022.1   75.52
  5036.3   75.63  5050.6    78.9    5079   81.16  5156.9   83.46  5185.4   85.33
  5259.8   84.79    5304    86.4  5313.7   85.73  5357.8   86.87  5597.5   86.53
#Mann= 9 ,-1 , 0
  3588.5     .07       0  3789.1     .05       0  3827.9     .07       0
  4046.9     .05       0    4189     .07       0  4839.8     .07       0
  4984.8     .05       0    4987     .05       0  5036.3     .05       0
Bank Sta=4987,5036.3
XS Rating Curve= 0 ,0
Exp/Cntr=0.3,0.1

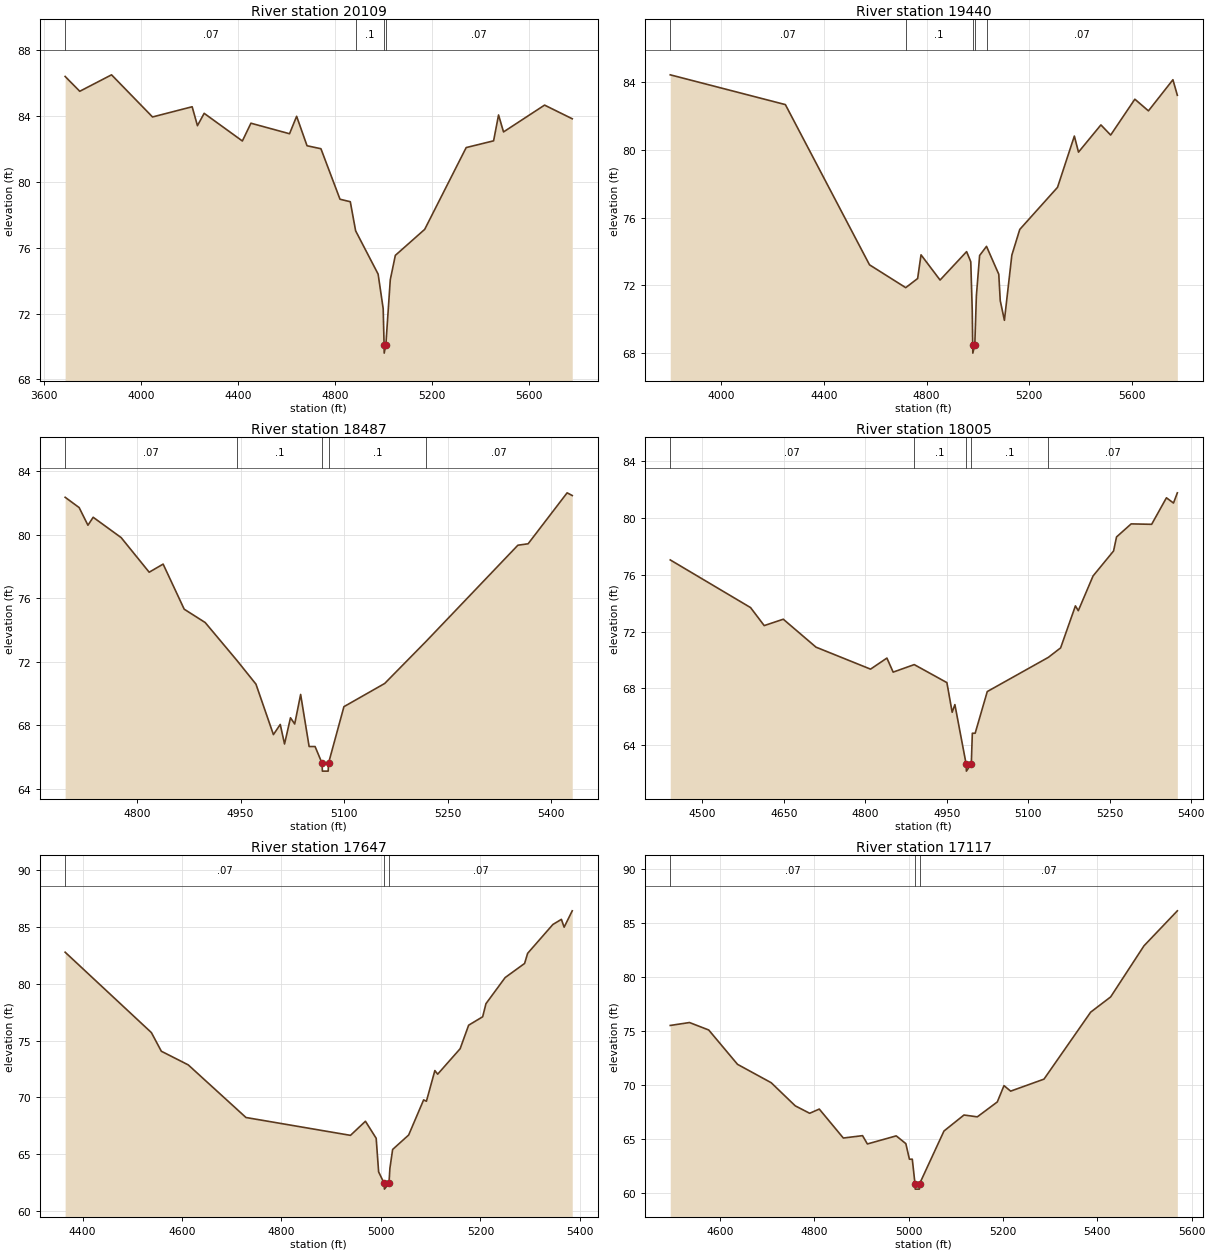
Type RM Length L Ch R = 1 ,20109   ,669,669,669
BEGIN DESCRIPTION:
Mapping XS bafc793a
END DESCRIPTION:
XS GIS Cut Line= 4
      2581380.32     13462820.17      2580976.66     13462073.61
       2580269.2     13461557.12      2579908.25     13461474.62
#Sta/Elev= 30
  3685.8   86.41  3746.2   85.51  3877.5   86.51  4046.8   83.95  4210.5   84.57
  4232.4   83.42  4260.1   84.17    4418   82.49  4453.3   83.57  4612.8   82.93
  4642.1   83.99  4685.1    82.2  4742.5   82.02  4821.3   78.95  4863.8    78.8
  4885.9   77.03  4978.8    74.4  4999.7    72.3  5003.4    70.1  5003.9    69.6
  5010.7    70.1    5029   74.06  5049.9   75.54  5171.2   77.12  5342.6   82.09
  5455.8    82.5  5476.3   84.07  5496.8   83.04  5666.4   84.67  5780.7   83.84
#Mann= 4 ,-1 , 0
  3685.8     .07       0  4885.9      .1       0  5003.4     .05       0
  5010.7     .07       0
Bank Sta=5003.4,5010.7
XS Rating Curve= 0 ,0
Exp/Cntr=0.3,0.1

Type RM Length L Ch R = 1 ,19440   ,953,953,953
BEGIN DESCRIPTION:
Mapping XS f4cf363c
END DESCRIPTION:
XS GIS Cut Line= 3
      2581918.52     13462299.33      2581349.93     13461570.14
      2580429.91     13461066.74
#Sta/Elev= 30
  3802.8   84.44  4250.8   82.68  4578.2   73.21  4719.2   71.86  4765.5    72.4
  4778.7    73.8  4852.8   72.31  4956.1   73.99  4972.3   73.39    4978   70.52
  4979.8   68.49  4980.3   67.99    4988   68.49  4994.1   71.38  5006.7   73.76
  5033.5    74.3  5081.3   72.65    5087   71.09  5103.2   69.93  5132.1   73.78
  5162.9    75.3  5309.9   77.79  5375.4   80.82  5391.5   79.87  5478.7   81.48
  5516.7   80.88  5610.8      83  5663.7   82.31    5759   84.15  5776.2   83.23
#Mann= 5 ,-1 , 0
  3802.8     .07       0  4719.2      .1       0  4979.8     .05       0
    4988      .1       0  5033.5     .07       0
Bank Sta=4979.8,4988
XS Rating Curve= 0 ,0
Exp/Cntr=0.3,0.1

Type RM Length L Ch R = 1 ,18487   ,482,482,482
BEGIN DESCRIPTION:
COURT BRANCH 39.0
END DESCRIPTION:
XS GIS Cut Line= 3
        2581975.     13461625.02        2581925.       13461325.
      2581674.98     13460974.98
#Sta/Elev= 30
  4695.9   82.36  4716.2   81.71  4728.9    80.6  4736.5    81.1    4777   79.82
  4817.6   77.64  4837.8   78.15  4868.3   75.31  4898.7   74.47  4944.7   72.08
  4972.2   70.59  4997.5   67.41  5007.4   68.05  5013.6   66.82  5022.2   68.47
  5028.3   68.08  5036.9   69.94  5049.2   66.66  5057.8   66.66  5067.9   65.61
  5068.4   65.11  5076.8   65.11  5077.3   65.61  5099.6   69.17  5158.6   70.63
  5218.5   73.28  5351.5   79.34  5366.3   79.43  5422.8   82.64  5430.2   82.47
#Mann= 5 ,-1 , 0
  4695.9     .07       0  4944.7      .1       0  5067.9     .05       0
  5077.3      .1       0  5218.5     .07       0
Bank Sta=5067.9,5077.3
XS Rating Curve= 0 ,0
Exp/Cntr=0.3,0.1

Type RM Length L Ch R = 1 ,18005   ,358,358,358
BEGIN DESCRIPTION:
Mapping XS 12e95d25
END DESCRIPTION:
XS GIS Cut Line= 3
      2582354.81     13461682.24      2582307.07     13461126.67
       2582194.8     13460768.26
#Sta/Elev= 30
  4440.9   77.05  4588.7   73.69  4613.8   72.42  4648.9   72.87  4709.1    70.9
  4809.5   69.35  4839.6   70.13  4851.1   69.14  4889.9   69.67    4950    68.4
  4959.7   66.31  4964.7   66.85  4985.4   62.66  4985.9   62.16  4994.9   62.66
  4996.8   64.83    5002   64.83  5024.3   67.77  5136.7   70.18  5159.3   70.85
  5186.5   73.81  5191.8   73.47    5219   75.92  5256.7   77.68  5262.2   78.67
  5289.1   79.59  5326.8   79.56    5354   81.43    5367   81.06  5374.1   81.78
#Mann= 5 ,-1 , 0
  4440.9     .07       0  4889.9      .1       0  4985.4     .05       0
  4994.9      .1       0  5136.7     .07       0
Bank Sta=4985.4,4994.9
XS Rating Curve= 0 ,0
Exp/Cntr=0.3,0.1

Type RM Length L Ch R = 1 ,17647   ,530,530,530
BEGIN DESCRIPTION:
Mapping XS 272b2a7e
END DESCRIPTION:
XS GIS Cut Line= 3
      2582680.33     13461708.24      2582654.29     13461087.61
      2582481.32      13460728.7
#Sta/Elev= 30
  4365.1   82.77  4538.5    75.7  4558.5   74.06  4612.6   72.86  4728.7   68.23
  4938.8   66.66  4968.9    67.9  4990.5    66.4  4995.4   63.45  5006.6   62.43
  5007.1   61.93  5016.2   62.43  5018.1   63.77  5023.6   65.42  5055.8   66.69
  5085.9   69.78  5091.5   69.66  5108.5   72.36  5114.1   72.04  5159.3   74.28
  5176.4   76.35  5204.6   77.09  5211.2   78.24  5249.8   80.54  5288.9   81.78
    5295   82.67  5345.8   85.21  5362.9   85.66  5368.4   84.97  5384.7   86.41
#Mann= 3 ,-1 , 0
  4365.1     .07       0  5006.6     .05       0  5016.2     .07       0
Bank Sta=5006.6,5016.2
XS Rating Curve= 0 ,0
Exp/Cntr=0.3,0.1

Type RM Length L Ch R = 1 ,17117   ,264,264,264
BEGIN DESCRIPTION:
COURT BRANCH 36.0
END DESCRIPTION:
XS GIS Cut Line= 3
      2583174.99     13461474.97        2583075.       13460975.
      2582674.97     13460574.97
#Sta/Elev= 30
  4494.1   75.51  4534.9   75.78  4575.7   75.09  4636.8   71.91  4708.2   70.21
  4759.2   68.07  4789.8   67.38  4810.2   67.77  4861.2   65.09    4902   65.31
  4912.2   64.54  4973.4   65.29  4993.8   64.57  5001.4   63.13  5007.5   63.13
  5013.2   60.86  5013.7   60.36  5022.5   60.36    5023   60.86  5074.7   65.74
  5117.1   67.22  5145.4   67.05  5187.8   68.43    5202   69.94  5216.1   69.43
  5286.8   70.54  5385.8   76.74  5428.2   78.15  5498.9   82.88  5569.7   86.12
#Mann= 3 ,-1 , 0
  4494.1     .07       0  5013.2     .05       0    5023     .07       0
Bank Sta=5013.2,5023
XS Rating Curve= 0 ,0
Exp/Cntr=0.3,0.1

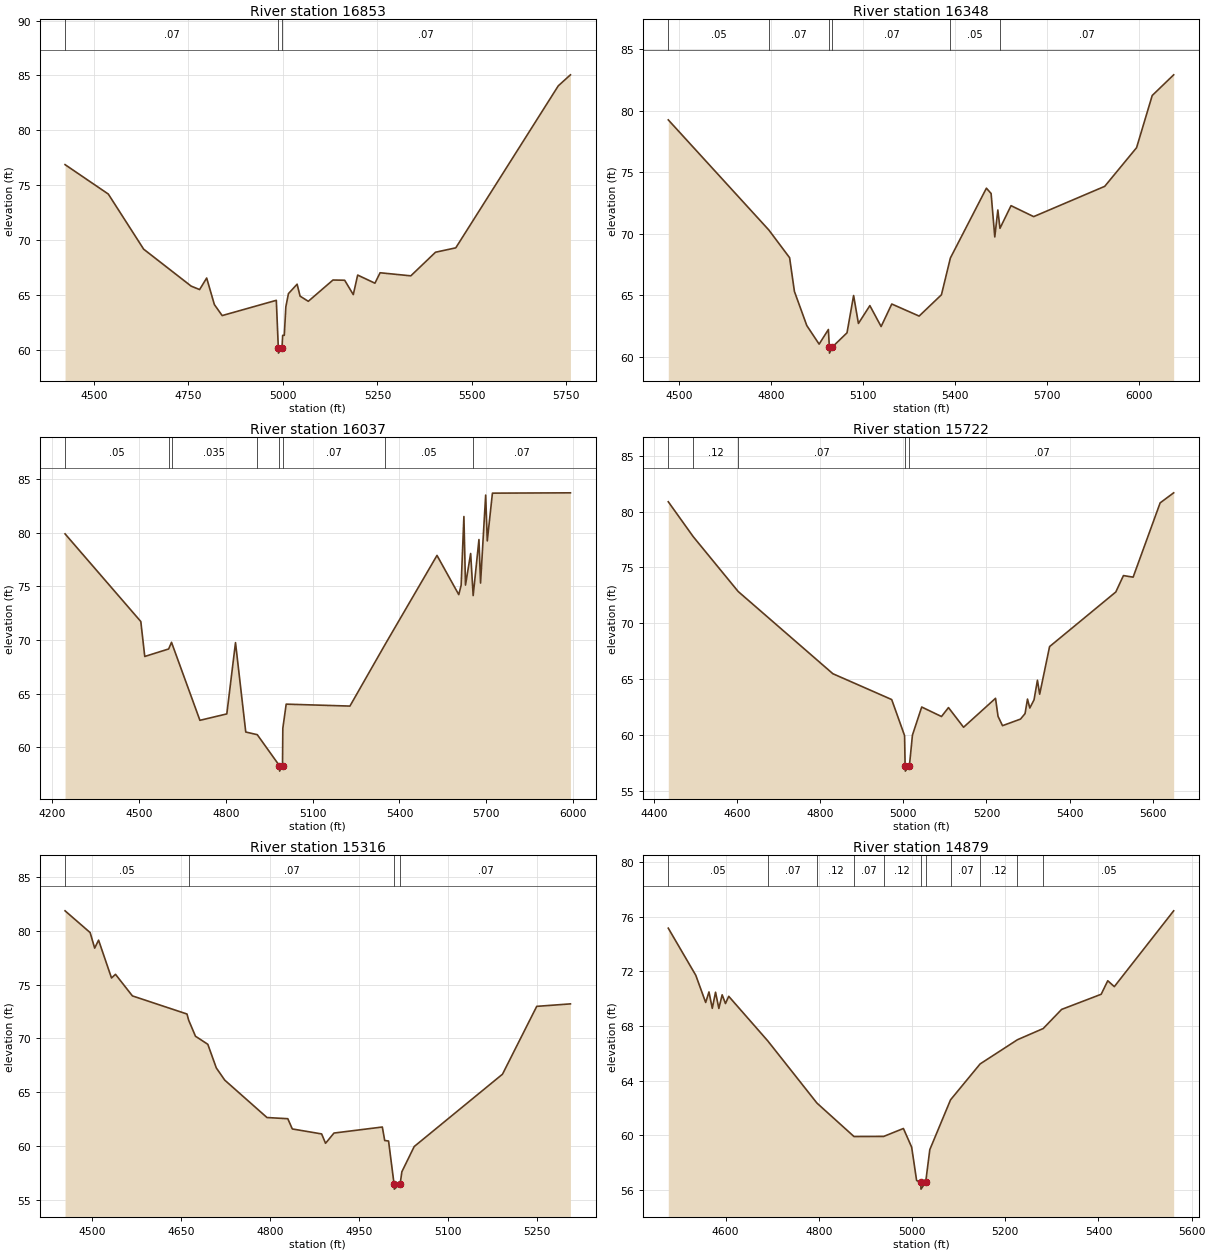
Type RM Length L Ch R = 1 ,16853   ,505,505,505
BEGIN DESCRIPTION:
Mapping XS 61a20ec2
END DESCRIPTION:
XS GIS Cut Line= 3
      2583444.22     13461491.25      2583322.69     13460927.02
      2582953.79     13460262.98
#Sta/Elev= 30
  4423.8   76.88  4538.2    74.2  4631.7   69.18  4757.5   65.81  4779.7    65.5
  4798.4   66.55  4818.8   64.13  4839.4   63.13  4982.6   64.52  4987.9   60.21
  4988.4   59.71  4997.7   60.21  4999.4   61.33  5003.7   61.33  5007.8   63.93
  5014.7   65.13  5037.6   65.99  5045.5    64.9  5067.2   64.43  5132.5   66.37
  5163.4   66.35  5186.2   65.04  5197.8   66.82  5243.5   66.08  5257.1   67.03
  5338.4   66.75  5403.7    68.9  5457.3    69.3  5728.5   84.06  5760.6   85.06
#Mann= 3 ,-1 , 0
  4423.8     .07       0  4987.9     .05       0  4997.7     .07       0
Bank Sta=4987.9,4997.7
XS Rating Curve= 0 ,0
Exp/Cntr=0.3,0.1

Type RM Length L Ch R = 1 ,16348   ,311,311,311
BEGIN DESCRIPTION:
Mapping XS 3074ae82
END DESCRIPTION:
XS GIS Cut Line= 3
      2583735.02     13461443.54      2583674.26       13460914.
      2583114.37     13459950.47
#Sta/Elev= 30
  4465.5   79.25  4793.4    70.3    4861   68.05  4876.7   65.31    4917   62.54
  4957.2   61.03  4987.4   62.22  4990.5    60.8    4991    60.3  5000.4    60.8
  5048.1   61.95  5069.6   64.98  5085.3   62.71  5122.6   64.16  5159.3   62.46
    5194   64.29  5283.2   63.31  5355.9   65.04  5385.1   68.03  5502.5    73.7
  5517.8   73.27  5529.8   69.74  5539.8   71.93  5546.7   70.44  5582.8   72.28
  5656.6   71.39  5888.2   73.85    5992   76.99    6043   81.23  6112.9   82.91
#Mann= 6 ,-1 , 0
  4465.5     .05       0  4793.4     .07       0  4990.5     .05       0
  5000.4     .07       0  5385.1     .05       0  5546.7     .07       0
Bank Sta=4990.5,5000.4
XS Rating Curve= 0 ,0
Exp/Cntr=0.3,0.1

Type RM Length L Ch R = 1 ,16037   ,315,315,315
BEGIN DESCRIPTION:
COURT BRANCH 34.0
END DESCRIPTION:
XS GIS Cut Line= 3
      2584195.11     13461417.51      2583894.99     13460724.94
      2583491.97     13459820.25
#Sta/Elev= 30
  4245.2   79.91  4506.8   71.73  4520.4   68.47    4603   69.17  4612.8   69.79
  4710.9   62.51  4803.8   63.11  4833.8   69.76  4869.2   61.42    4909   61.17
  4985.7   58.27  4986.2   57.77  4996.1   58.27  4997.2   61.76  5008.8   64.02
  5228.9   63.84  5350.6    69.6  5529.6    77.9  5604.8   74.24    5613   75.12
  5622.5   81.53    5628   75.13  5645.8   78.08  5654.5   74.15  5674.5   79.38
    5680   75.32  5697.7   83.53  5703.2   79.25    5721   83.71  5990.4   83.74
#Mann= 8 ,-1 , 0
  4245.2     .05       0    4603     .07       0  4612.8    .035       0
    4909     .07       0  4985.7     .05       0  4996.1     .07       0
  5350.6     .05       0  5654.5     .07       0
Bank Sta=4985.7,4996.1
XS Rating Curve= 0 ,0
Exp/Cntr=0.3,0.1

Type RM Length L Ch R = 1 ,15722   ,406,406,406
BEGIN DESCRIPTION:
COURT BRANCH 33.0
END DESCRIPTION:
XS GIS Cut Line= 3
        2584575.       13461125.        2584175.       13460725.
      2583924.99     13460124.98
#Sta/Elev= 30
  4434.6   80.88  4494.5   77.76  4602.6   72.85  4830.6   65.48    4972   63.17
    5003   59.94  5004.3   57.26  5004.8   56.76  5014.7   57.26  5021.9   59.98
  5044.2    62.5  5091.8   61.65  5108.6   62.45  5144.9   60.69  5221.8   63.28
  5227.8   61.67  5238.6   60.83  5281.9   61.42  5292.8   61.91  5298.7   63.21
  5304.2   62.41  5314.4   63.14  5322.6    64.9    5328   63.65  5351.8   67.91
  5511.1    72.8  5529.5   74.27  5552.8   74.13  5617.8   80.78  5650.3   81.68
#Mann= 5 ,-1 , 0
  4434.6     .07       0  4494.5     .12       0  4602.6     .07       0
  5004.3     .05       0  5014.7     .07       0
Bank Sta=5004.3,5014.7
XS Rating Curve= 0 ,0
Exp/Cntr=0.3,0.1

Type RM Length L Ch R = 1 ,15316   ,437,437,437
BEGIN DESCRIPTION:
COURT BRANCH 32.0
END DESCRIPTION:
XS GIS Cut Line= 3
      2584725.02     13460875.03        2584375.       13460475.
        2584175.       13460225.
#Sta/Elev= 30
  4454.2   81.84  4496.5   79.82  4504.1   78.38  4510.7   79.12  4532.5   75.61
  4539.2   75.95  4567.7   73.95  4659.7   72.27  4662.5    71.7    4674   70.21
  4694.8   69.46  4709.1   67.27  4723.3   66.14  4794.5   62.67  4829.6   62.56
  4837.2   61.61  4886.6   61.15  4893.2   60.28  4907.4   61.23  4988.9   61.79
  4992.9   60.54  4999.4   60.49  5008.6   56.53  5009.1   56.03    5019   56.53
  5021.8   57.64  5042.6   59.98  5191.4   66.69  5249.1   72.98  5305.9   73.21
#Mann= 4 ,-1 , 0
  4454.2     .05       0  4662.5     .07       0  5008.6     .05       0
    5019     .07       0
Bank Sta=5008.6,5019
XS Rating Curve= 0 ,0
Exp/Cntr=0.3,0.1

Type RM Length L Ch R = 1 ,14879   ,482,482,482
BEGIN DESCRIPTION:
COURT BRANCH 31.0
END DESCRIPTION:
XS GIS Cut Line= 3
       2585141.3     13460742.15        2584775.       13460375.
      2584375.01     13459975.01
#Sta/Elev= 30
  4477.1   75.17  4536.1   71.72  4557.3   69.73  4564.4    70.5  4571.5    69.3
  4578.5   70.48  4585.6   69.29  4592.7   70.29  4599.8   69.65  4606.8   70.18
  4690.7   66.91  4796.1   62.36  4875.6   59.91  4939.3   59.92  4981.6    60.5
  4999.3   59.13  5009.9   56.69  5018.8   56.56  5019.3   56.06  5029.3   56.56
  5038.2   58.95  5082.7    62.6  5146.2   65.23  5226.2      67  5281.5   67.82
    5321   69.22  5405.9   70.33    5420   71.32  5434.1   70.89  5561.4   76.44
#Mann= 11 ,-1 , 0
  4477.1     .05       0  4690.7     .07       0  4796.1     .12       0
  4875.6     .07       0  4939.3     .12       0  5018.8     .05       0
  5029.3     .12       0  5082.7     .07       0  5146.2     .12       0
  5226.2     .07       0  5281.5     .05       0
Bank Sta=5018.8,5029.3
XS Rating Curve= 0 ,0
Exp/Cntr=0.3,0.1