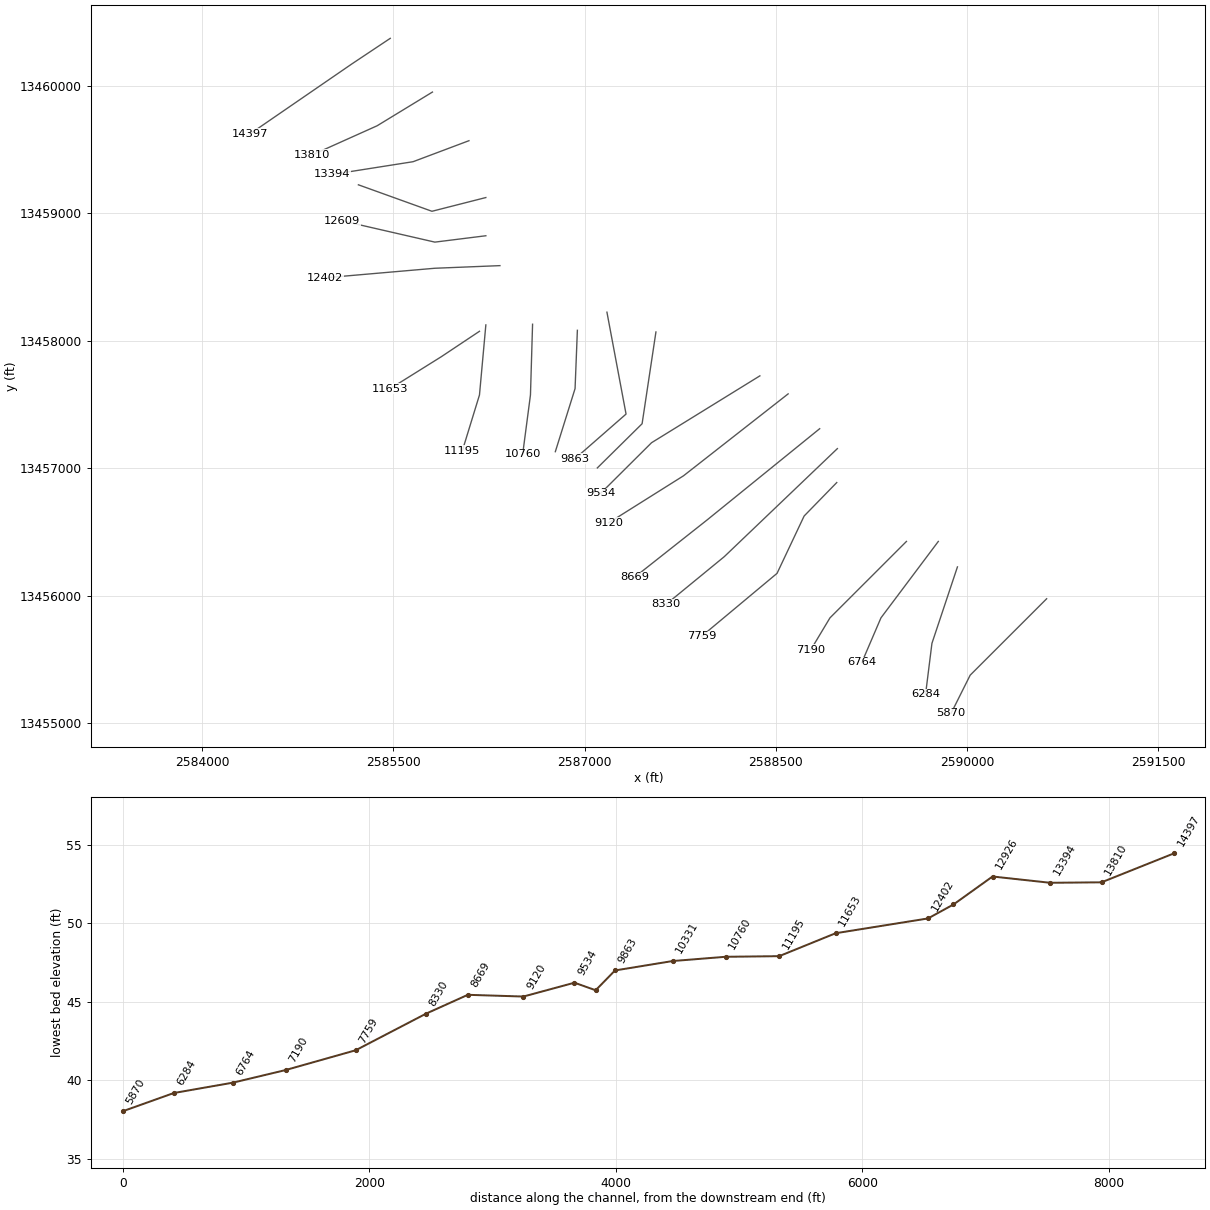
HEC-RAS study COURT BRANCH.prj: COURT BRANCH Base Level Engineering

--- COURT BRANCH.g01 (geometry) --- (continued)

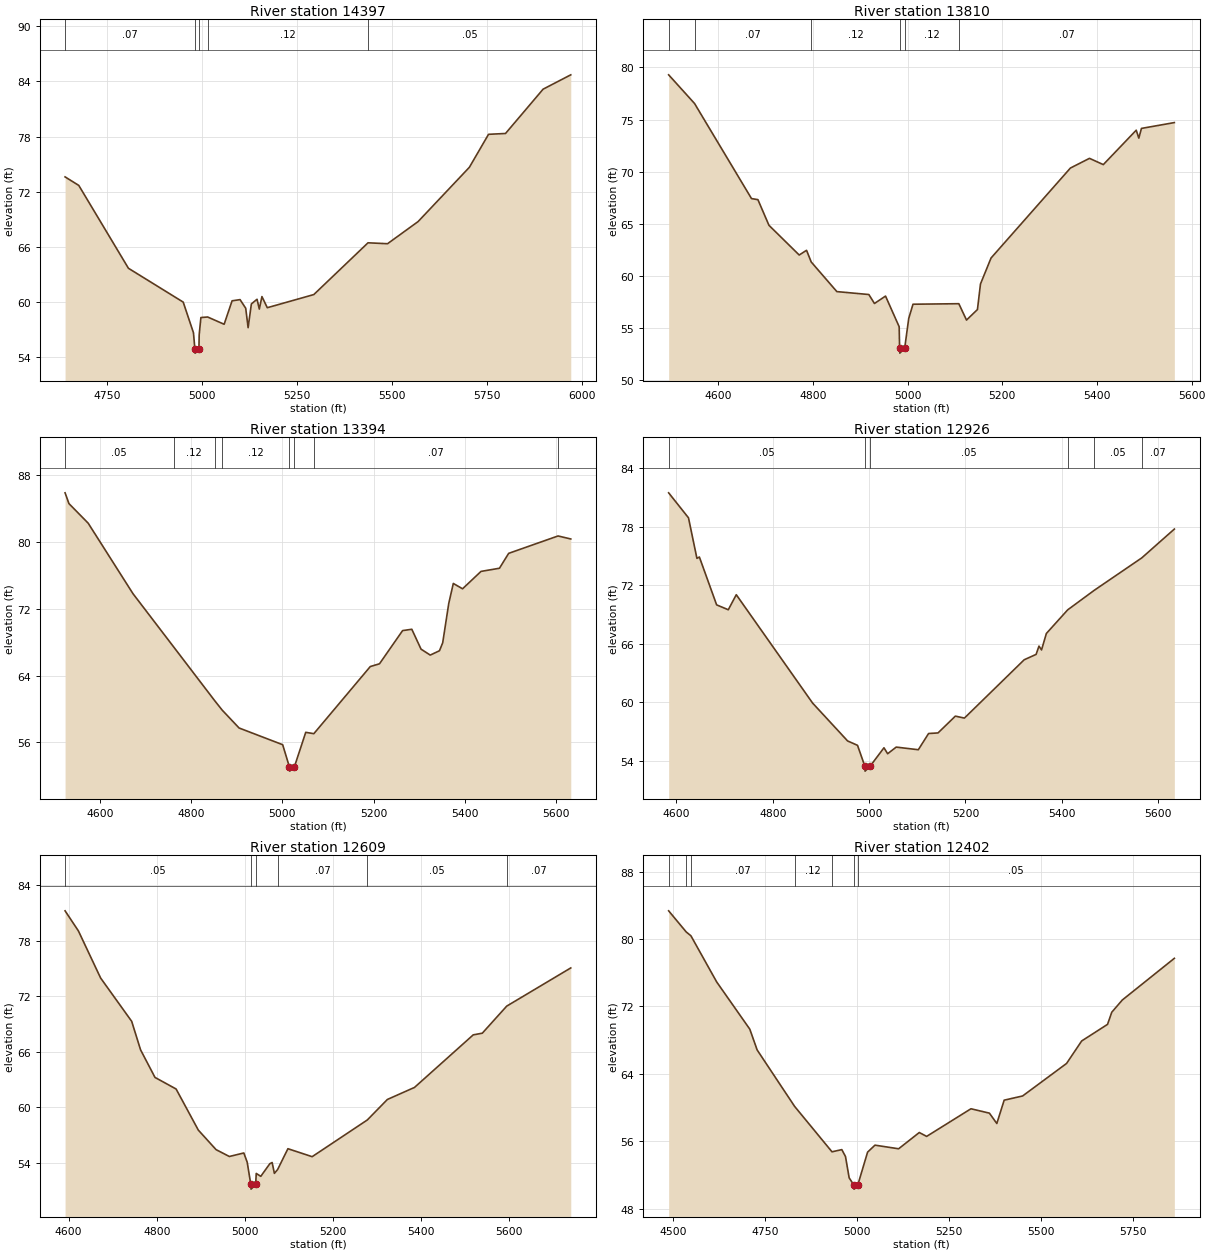
Type RM Length L Ch R = 1 ,14397   ,587,587,587
BEGIN DESCRIPTION:
COURT BRANCH 30.0
END DESCRIPTION:
XS GIS Cut Line= 3
      2585475.01     13460375.01        2585175.       13460175.
        2584375.       13459625.
#Sta/Elev= 30
  4640.2   73.61  4676.3   72.68    4807   63.67  4951.2   59.99  4978.2   56.66
  4981.9   54.94  4982.4   54.44  4992.6   54.94  4993.3   56.44  4997.8   58.31
  5015.5   58.37    5059   57.58  5079.9   60.13  5100.9   60.26  5115.8   59.32
  5122.1   57.21  5130.7   59.79  5145.6    60.3  5151.6   59.23  5158.5   60.59
  5172.6   59.38  5295.1   60.81  5437.8   66.44  5489.2   66.34  5569.7   68.75
  5704.6   74.65  5755.1   78.24  5799.8   78.33  5898.8   83.15  5971.6   84.71
#Mann= 5 ,-1 , 0
  4640.2     .07       0  4981.9     .05       0  4992.6     .07       0
  5015.5     .12       0  5437.8     .05       0
Bank Sta=4981.9,4992.6
XS Rating Curve= 0 ,0
Exp/Cntr=0.3,0.1

Type RM Length L Ch R = 1 ,13810   ,416,416,416
BEGIN DESCRIPTION:
Mapping XS fca90255
END DESCRIPTION:
XS GIS Cut Line= 3
      2585805.96     13459953.26      2585371.96     13459688.52
      2584861.55     13459459.27
#Sta/Elev= 30
  4495.6   79.29  4550.3   76.54  4670.6   67.42  4684.1   67.32  4707.4   64.86
  4771.3   62.01  4786.8   62.46  4796.7   61.34  4850.8    58.5  4918.4   58.22
  4930.2   57.36  4953.6   58.07  4982.4   55.13  4983.3    53.1  4983.8    52.6
  4994.1    53.1  5002.6   55.93  5011.6   57.29  5108.4   57.34  5124.6   55.77
  5147.7   56.78  5154.1   59.23  5176.4   61.72    5344   70.35  5384.3   71.28
  5413.5   70.68    5483   73.98  5488.5   73.22    5494   74.15  5563.5   74.71
#Mann= 6 ,-1 , 0
  4495.6     .05       0  4550.3     .07       0  4796.7     .12       0
  4983.3     .05       0  4994.1     .12       0  5108.4     .07       0
Bank Sta=4983.3,4994.1
XS Rating Curve= 0 ,0
Exp/Cntr=0.3,0.1

Type RM Length L Ch R = 1 ,13394   ,468,468,468
BEGIN DESCRIPTION:
Mapping XS fb85f687
END DESCRIPTION:
XS GIS Cut Line= 3
      2586092.44     13459571.33      2585654.07      13459406.4
      2585020.36     13459306.57
#Sta/Elev= 30
    4523   85.86  4531.5   84.57  4573.7   82.23    4672    73.8    4761   67.45
  4851.5   60.99  4867.8   59.87  4904.9   57.73  5000.6   55.73  5015.4   53.07
  5015.9   52.57  5026.2   53.07  5051.2   57.21    5069   57.05  5192.9   65.08
  5213.1   65.41  5263.8   69.38    5284   69.54  5304.3   67.16  5324.5   66.45
  5344.7   66.97  5351.8   67.92    5365    72.6  5375.1   75.02  5395.4   74.38
  5435.9   76.46  5476.4   76.84  5496.6   78.62    5605    80.7  5632.9   80.34
#Mann= 8 ,-1 , 0
    4523     .05       0    4761     .12       0  4851.5     .05       0
  4867.8     .12       0  5015.4     .05       0  5026.2     .12       0
    5069     .07       0    5605     .05       0
Bank Sta=5015.4,5026.2
XS Rating Curve= 0 ,0
Exp/Cntr=0.3,0.1

Type RM Length L Ch R = 1 ,12926   ,317,317,317
BEGIN DESCRIPTION:
COURT BRANCH 27.0
END DESCRIPTION:
XS GIS Cut Line= 3
      2586224.96     13459124.99      2585802.15     13459017.15
      2585224.98     13459225.01
#Sta/Elev= 30
    4584   81.46  4625.2    78.9  4642.7   74.75  4647.8   74.89  4683.6   69.99
  4707.8   69.49  4724.4   71.03  4882.8   59.94  4955.5   56.06  4976.1   55.61
  4991.3   53.47  4991.8   52.97  5002.2   53.47    5031   55.36  5038.6   54.75
  5056.4   55.43  5102.3   55.16  5123.6   56.82  5143.2   56.88  5179.2    58.6
    5198    58.4  5322.1   64.37  5346.8   64.92  5352.8   65.77  5358.1   65.38
  5368.1   67.06  5412.4   69.48  5467.5   71.48  5566.2    74.8  5633.8   77.75
#Mann= 6 ,-1 , 0
    4584     .05       0  4991.3     .05       0  5002.2     .05       0
  5412.4     .07       0  5467.5     .05       0  5566.2     .07       0
Bank Sta=4991.3,5002.2
XS Rating Curve= 0 ,0
Exp/Cntr=0.3,0.1

Type RM Length L Ch R = 1 ,12609   ,207,207,207
BEGIN DESCRIPTION:
COURT BRANCH 26.0
END DESCRIPTION:
XS GIS Cut Line= 3
      2586225.03       13458825.        2585825.       13458775.
      2585099.27     13458941.82
#Sta/Elev= 30
  4591.9   81.21  4622.2   79.04  4672.6   73.96  4743.1   69.29  4763.3   66.21
    4796   63.24  4843.9   61.99  4894.3   57.56  4934.6   55.45  4964.8   54.71
  4997.6   55.09  5005.3   54.09  5013.5   51.69    5014   51.19  5024.5   51.69
  5025.8   52.88  5036.1   52.57  5056.6   53.93  5061.9   54.06    5067   52.89
  5074.4   53.31  5097.7   55.55  5152.7   54.69  5277.9   58.65  5323.4   60.86
    5385   62.16  5518.3   67.83  5538.9   68.01  5594.3   70.93  5739.7   75.05
#Mann= 6 ,-1 , 0
  4591.9     .05       0  5013.5     .05       0  5024.5     .05       0
  5074.4     .07       0  5277.9     .05       0  5594.3     .07       0
Bank Sta=5013.5,5024.5
XS Rating Curve= 0 ,0
Exp/Cntr=0.3,0.1

Type RM Length L Ch R = 1 ,12402   ,749,749,749
BEGIN DESCRIPTION:
COURT BRANCH 25.0
END DESCRIPTION:
XS GIS Cut Line= 3
      2586335.51     13458590.43      2585824.52      13458569.8
      2584963.97     13458494.95
#Sta/Elev= 30
  4488.6   83.34  4536.4   80.83  4549.1   80.38  4619.2    74.9  4709.3   69.29
  4729.3   66.82  4831.2   60.12  4932.8   54.73  4959.5   54.99  4969.5   54.17
  4979.5   51.64    4992    50.8  4992.5    50.3    5003    50.8  5029.6   54.69
  5049.7   55.52    5114   55.09  5170.2   57.02  5190.2   56.56  5310.7   59.84
  5360.9   59.32    5381   58.09    5401   60.86  5451.2   61.36  5570.7   65.22
  5611.8   67.89  5682.1   69.86  5693.6    71.3  5722.2   72.75  5863.8    77.7
#Mann= 7 ,-1 , 0
  4488.6    .035       0  4536.4     .05       0  4549.1     .07       0
  4831.2     .12       0  4932.8     .05       0    4992     .05       0
    5003     .05       0
Bank Sta=4992,5003
XS Rating Curve= 0 ,0
Exp/Cntr=0.3,0.1

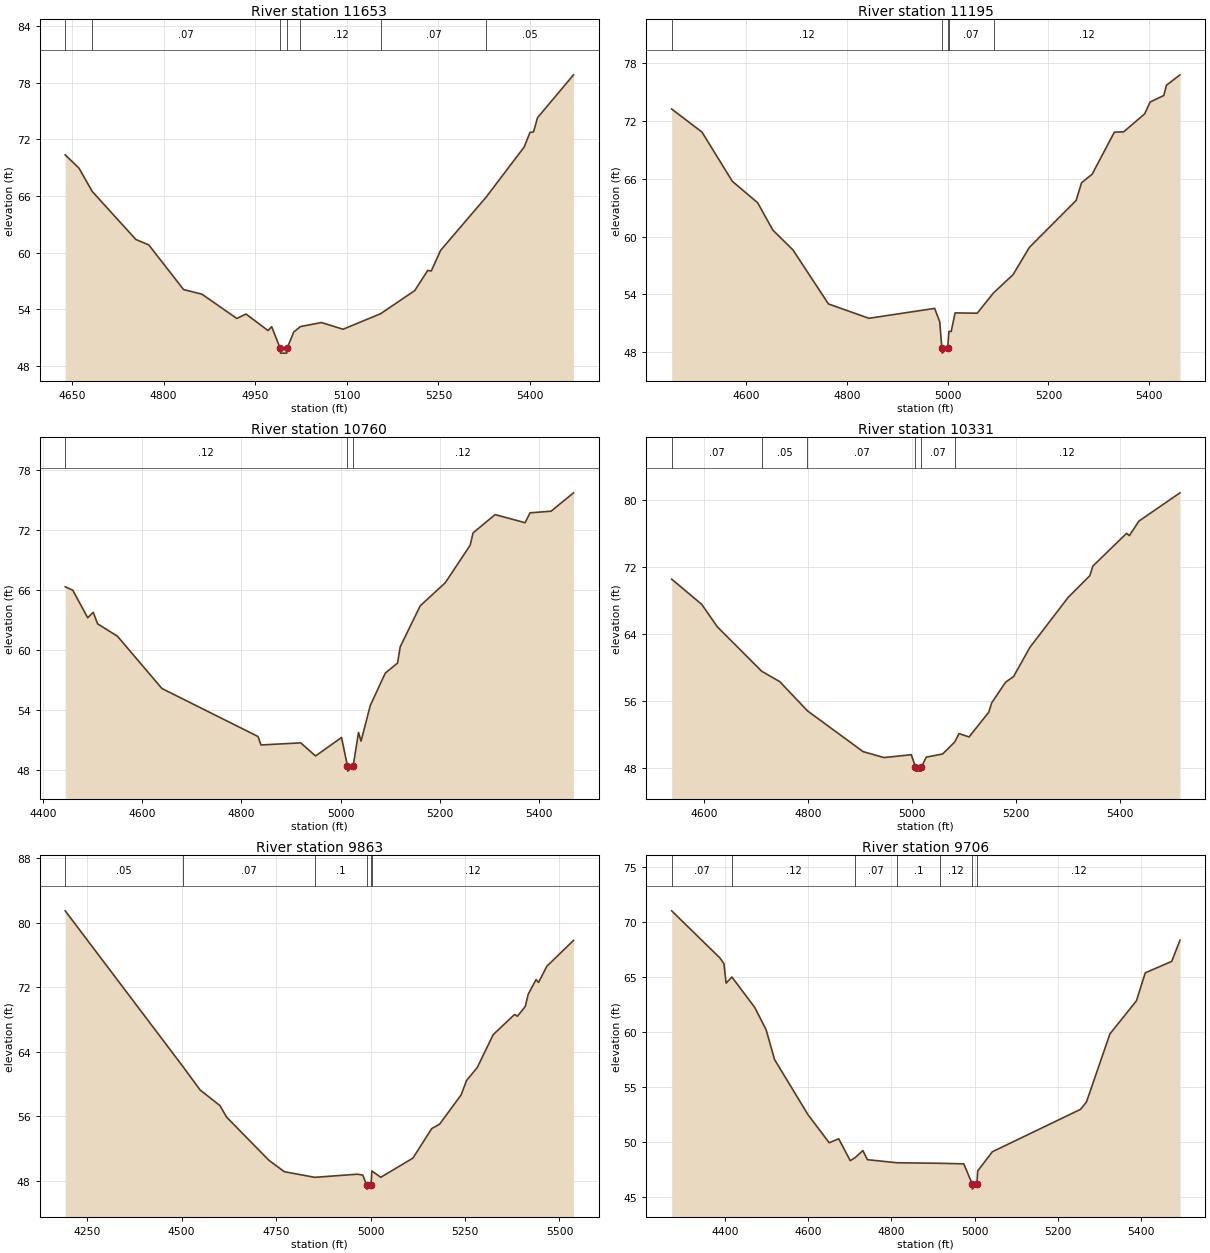
Type RM Length L Ch R = 1 ,11653   ,458,458,458
BEGIN DESCRIPTION:
COURT BRANCH 24.0
END DESCRIPTION:
XS GIS Cut Line= 3
      2586175.04     13458075.02        2585875.       13457875.
        2585475.       13457625.
#Sta/Elev= 30
  4638.8   70.35  4661.4   68.94  4683.1   66.47  4754.5   61.39  4775.6   60.82
  4832.6   56.09  4862.7    55.6  4919.8   53.03  4934.8    53.5  4970.9   51.75
  4976.9   52.16  4990.8   49.86  4991.3   49.36  5001.5   49.36    5002   49.86
    5013    51.6  5023.9   52.17  5058.4    52.6  5093.7   51.89  5155.2   53.53
  5211.1   55.98  5232.3   58.11  5238.2   58.06  5253.5   60.24  5328.2   65.89
  5390.3   71.18  5399.8   72.72  5405.6   72.78  5412.1   74.28  5471.1   78.82
#Mann= 7 ,-1 , 0
  4638.8     .12       0  4683.1     .07       0  4990.8     .05       0
    5002     .07       0  5023.9     .12       0  5155.2     .07       0
  5328.2     .05       0
Bank Sta=4990.8,5002
XS Rating Curve= 0 ,0
Exp/Cntr=0.3,0.1

Type RM Length L Ch R = 1 ,11195   ,435,435,435
BEGIN DESCRIPTION:
COURT BRANCH 23.0
END DESCRIPTION:
XS GIS Cut Line= 3
        2586225.     13458124.98        2586175.       13457575.
      2586040.89     13457138.17
#Sta/Elev= 30
  4452.1   73.27  4512.3   70.87  4572.6   65.75  4622.8   63.53  4652.9   60.69
  4693.1   58.61  4763.4   53.01  4843.7   51.52  4974.2   52.55  4984.3   51.15
  4988.6    48.4  4989.1    47.9    5000    48.4  5002.5   50.15    5007   50.15
  5014.8   52.08  5058.7   52.05  5091.1   54.16  5129.9   56.06  5162.1   58.88
    5255   63.76  5265.9   65.61  5286.8   66.49    5331   70.86  5349.6    70.9
  5391.2   72.77  5401.9   73.99  5429.1   74.67  5434.4   75.74  5461.3   76.82
#Mann= 5 ,-1 , 0
  4452.1     .12       0  4988.6     .05       0    5000     .12       0
  5002.5     .07       0  5091.1     .12       0
Bank Sta=4988.6,5000
XS Rating Curve= 0 ,0
Exp/Cntr=0.3,0.1

Type RM Length L Ch R = 1 ,10760   ,429,429,429
BEGIN DESCRIPTION:
COURT BRANCH 22.0
END DESCRIPTION:
XS GIS Cut Line= 3
      2586591.57     13458130.34        2586575.       13457575.
       2586513.7     13457107.99
#Sta/Elev= 30
    4444   66.32  4459.3   65.97  4489.4   63.22  4500.6   63.76  4509.4   62.61
  4549.4   61.37  4639.4   56.13  4833.3   51.33  4839.5   50.48  4919.6   50.69
  4949.6   49.38  5002.1   51.23  5014.1   48.36  5014.6   47.86  5025.5   48.36
  5036.4   51.73  5041.5   50.86  5060.1   54.43  5090.4   57.67  5115.2   58.68
  5120.6   60.31    5161   64.41  5211.4   66.71  5261.8   70.47  5267.7   71.71
  5312.2   73.54  5372.8   72.73  5382.8   73.72  5425.2   73.88  5470.6   75.72
#Mann= 3 ,-1 , 0
    4444     .12       0  5014.1     .05       0  5025.5     .12       0
Bank Sta=5014.1,5025.5
XS Rating Curve= 0 ,0
Exp/Cntr=0.3,0.1

Type RM Length L Ch R = 1 ,10331   ,468,468,468
BEGIN DESCRIPTION:
COURT BRANCH 21.0
END DESCRIPTION:
XS GIS Cut Line= 3
      2586943.14     13458082.64        2586925.       13457625.
      2586770.12     13457129.65
#Sta/Elev= 30
  4537.7   70.51  4595.4    67.5  4625.4   64.82  4710.8   59.51  4745.5   58.27
  4798.6   54.79  4905.6   49.92  4945.7   49.21  4998.3   49.55  5006.2   48.09
  5006.7   47.59  5017.2   47.59  5017.7   48.09  5027.1   49.26  5058.6   49.64
  5081.6   51.06    5090   52.07  5109.3   51.67  5147.1   54.62  5152.9   55.75
  5179.5   58.21  5194.8   58.88  5226.2   62.36  5299.5   68.31  5341.5   70.93
  5347.1   72.06  5412.1   75.98  5417.3    75.7  5435.8   77.44  5514.7   80.81
#Mann= 6 ,-1 , 0
  4537.7     .07       0  4710.8     .05       0  4798.6     .07       0
  5006.2     .05       0  5017.7     .07       0  5081.6     .12       0
Bank Sta=5006.2,5017.7
XS Rating Curve= 0 ,0
Exp/Cntr=0.3,0.1

Type RM Length L Ch R = 1 ,9863    ,157,157,157
BEGIN DESCRIPTION:
COURT BRANCH 20.0
END DESCRIPTION:
XS GIS Cut Line= 3
      2587174.99     13458225.04        2587325.       13457425.
        2586925.       13457075.
#Sta/Elev= 30
  4191.7   81.47  4504.2   62.12  4548.7   59.28  4601.3   57.34  4619.1    55.9
    4731   50.56  4771.7   49.15  4852.3   48.45    4965   48.84  4979.4   48.73
  4989.7   47.49  4990.2   46.99  5001.3   47.49  5003.3   49.24    5027   48.46
    5112   50.83  5161.8   54.49  5182.7   55.04  5239.6   58.66  5253.9   60.44
  5282.4   62.06  5324.6   66.13  5381.1   68.63  5388.7   68.41  5409.5   69.62
  5417.1   71.12    5438   72.95  5444.7    72.6  5466.5    74.6  5537.2   77.81
#Mann= 6 ,-1 , 0
  4191.7     .05       0  4504.2     .07       0  4852.3      .1       0
  4989.7     .05       0  5001.3      .1       0  5003.3     .12       0
Bank Sta=4989.7,5001.3
XS Rating Curve= 0 ,0
Exp/Cntr=0.3,0.1

Type RM Length L Ch R = 1 ,9706    ,172,172,172
BEGIN DESCRIPTION:
Mapping XS fd27a0b7
END DESCRIPTION:
XS GIS Cut Line= 3
      2587559.46      13458069.6      2587450.95     13457349.11
       2587099.7      13457002.2
#Sta/Elev= 30
  4271.8   71.05  4387.7   66.77  4397.6   66.23  4402.7   64.47  4416.6   65.03
  4471.6   62.26  4498.9   60.23  4519.2   57.52  4599.5   52.51  4650.6   49.95
  4673.5   50.31  4701.2   48.32  4713.7   48.62  4731.5   49.24  4742.4   48.41
  4813.6   48.13  4917.4   48.08  4974.2   48.03  4994.2   46.23  4994.7   45.73
  5005.8   46.23  5007.6   47.38  5042.9   49.13    5255   52.99  5269.2   53.66
  5325.7   59.86  5389.3   62.86  5410.6   65.41  5474.2   66.45  5494.1   68.38
#Mann= 7 ,-1 , 0
  4271.8     .07       0  4416.6     .12       0  4713.7     .07       0
  4813.6      .1       0  4917.4     .12       0  4994.2     .05       0
  5005.8     .12       0
Bank Sta=4994.2,5005.8
XS Rating Curve= 0 ,0
Exp/Cntr=0.3,0.1

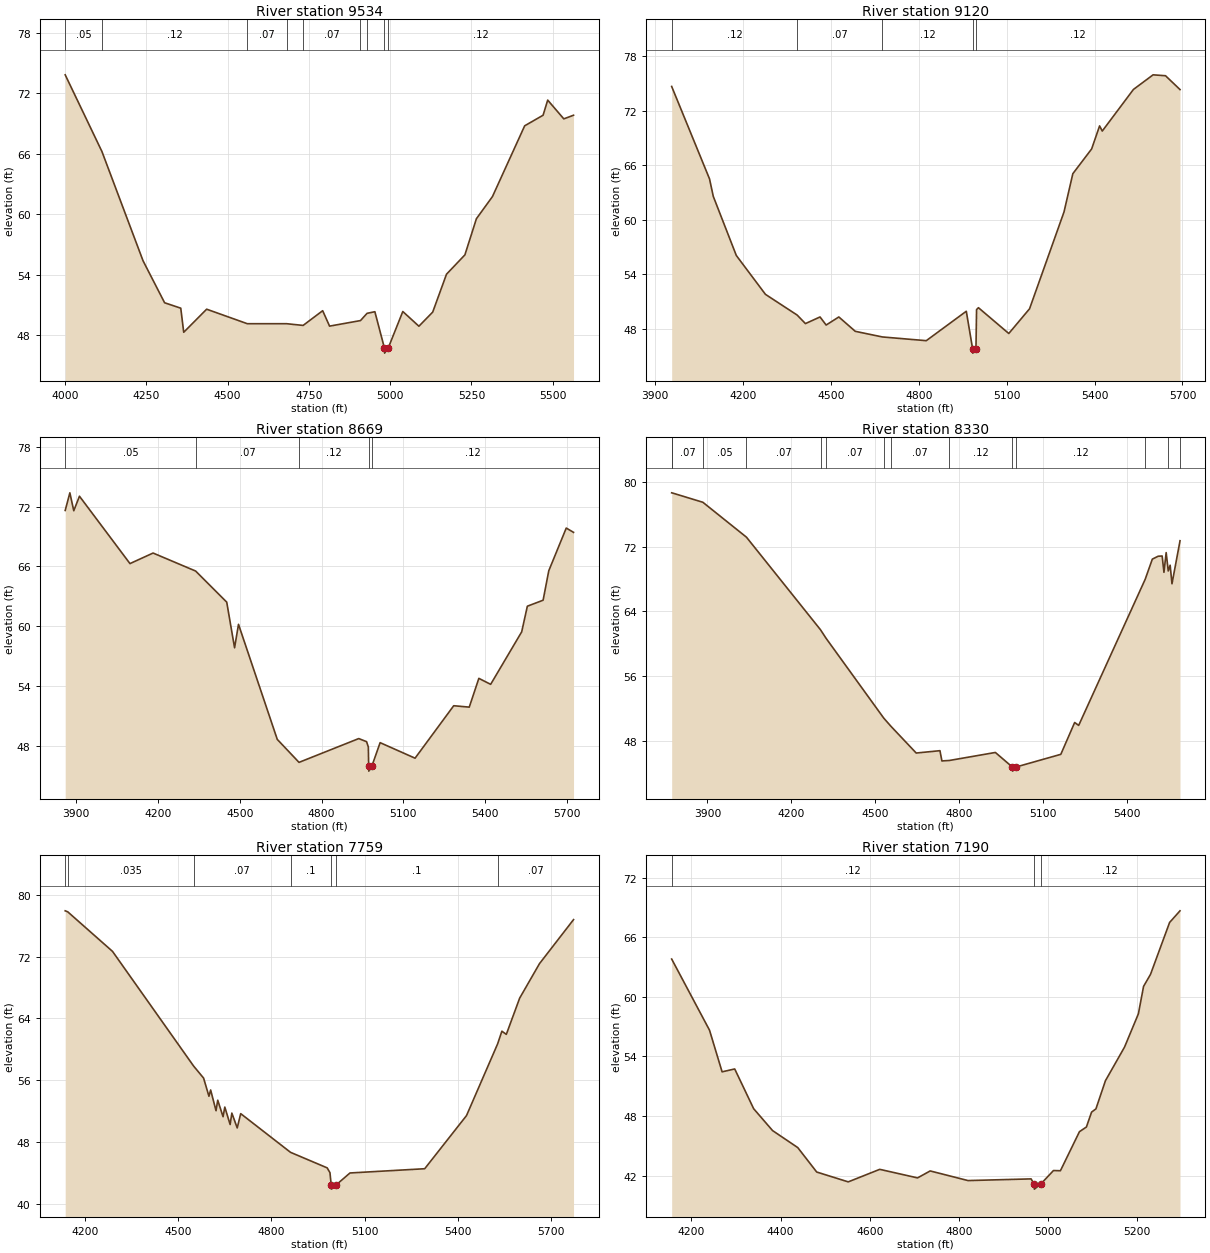
Type RM Length L Ch R = 1 ,9534    ,414,414,414
BEGIN DESCRIPTION:
COURT BRANCH 19.0
END DESCRIPTION:
XS GIS Cut Line= 3
      2588375.03     13457725.02        2587525.     13457199.99
      2587125.42     13456802.23
#Sta/Elev= 30
  4000.9   73.83  4113.8   66.22  4240.3   55.37  4306.5   51.21  4356.2   50.67
  4365.3   48.28  4435.8   50.57  4560.8   49.13  4681.6   49.13  4732.4   48.96
  4792.5   50.42  4813.7   48.89  4908.8   49.44    4929   50.16    4953   50.32
  4982.4   46.71  4982.9   46.21    4994   46.71  5038.9   50.34  5088.4   48.88
  5130.8   50.28  5173.2   54.04  5229.8   55.96  5265.2   59.55  5314.6   61.75
  5413.6   68.77  5470.2   69.82  5484.4   71.32  5533.9   69.46  5563.8   69.82
#Mann= 9 ,-1 , 0
  4000.9     .05       0  4113.8     .12       0  4560.8     .07       0
  4681.6     .12       0  4732.4     .07       0  4908.8      .1       0
    4929     .12       0  4982.4     .05       0    4994     .12       0
Bank Sta=4982.4,4994
XS Rating Curve= 0 ,0
Exp/Cntr=0.3,0.1

Type RM Length L Ch R = 1 ,9120    ,451,451,451
BEGIN DESCRIPTION:
COURT BRANCH 18.0
END DESCRIPTION:
XS GIS Cut Line= 3
      2588596.76     13457583.47      2587775.87     13456940.36
      2587190.53      13456572.2
#Sta/Elev= 30
  3957.2   74.68  4086.3   64.51  4099.2   62.58  4177.7   56.08  4277.1    51.8
  4385.3   49.52  4413.6   48.58  4463.4   49.31  4484.2   48.42  4527.5   49.31
  4583.6   47.73    4676   47.11  4825.9    46.7  4962.4   49.94  4983.8   45.83
  4984.3   45.33  4995.4   45.83  4997.4   50.12  5003.8   50.33  5107.4   47.49
  5178.2   50.21  5295.8   60.87  5325.9   65.08    5390    67.8  5417.2   70.34
  5426.3   69.77  5532.6   74.35  5599.7   75.96  5642.1   75.86  5691.5   74.34
#Mann= 5 ,-1 , 0
  3957.2     .12       0  4385.3     .07       0    4676     .12       0
  4983.8     .05       0  4995.4     .12       0
Bank Sta=4983.8,4995.4
XS Rating Curve= 0 ,0
Exp/Cntr=0.3,0.1

Type RM Length L Ch R = 1 ,8669    ,339,339,339
BEGIN DESCRIPTION:
COURT BRANCH 17.0
END DESCRIPTION:
XS GIS Cut Line= 3
      2588844.15     13457310.03       2587958.5     13456591.76
      2587390.21     13456142.53
#Sta/Elev= 30
  3859.7   71.63  3876.8    73.4  3891.1    71.6    3912   73.06  4097.3   66.29
  4182.1   67.35  4338.3   65.54  4452.2   62.42    4481   57.83  4495.4   60.19
  4637.6   48.63  4717.4   46.32  4936.5   48.71  4965.2    48.4  4971.7   47.86
  4972.9   45.94  4973.4   45.44  4984.6   45.94  5014.9    48.3  5143.1   46.74
  5284.9   52.01  5341.9   51.87  5377.1   54.76  5420.4   54.16  5534.2   59.43
    5555   62.01  5612.8   62.61  5633.6   65.57  5697.7   69.86  5724.4   69.43
#Mann= 5 ,-1 , 0
  3859.7     .05       0  4338.3     .07       0  4717.4     .12       0
  4972.9     .05       0  4984.6     .12       0
Bank Sta=4972.9,4984.6
XS Rating Curve= 0 ,0
Exp/Cntr=0.3,0.1

Type RM Length L Ch R = 1 ,8330    ,571,571,571
BEGIN DESCRIPTION:
COURT BRANCH 16.0
END DESCRIPTION:
XS GIS Cut Line= 3
      2588983.08     13457153.81      2588095.38     13456305.16
      2587638.88     13455930.91
#Sta/Elev= 30
  3771.9   78.69  3774.5   78.67  3883.5   77.52  4039.4    73.2  4304.3   61.74
  4324.5   60.67  4530.8   50.79  4556.3   49.79  4646.7   46.48  4731.6   46.77
  4738.6    45.5  4765.5   45.56  4929.8   46.55    4991   44.74  4991.5   44.24
  5002.7   44.74    5164   46.32  5213.5   50.26  5227.9    49.9  5465.7   67.98
  5491.3   70.48  5512.1   70.84  5526.4   70.87  5532.9   68.85  5540.8   71.29
  5548.3   69.02  5555.1   69.73  5561.6   67.43    5590   72.67  5590.3   72.76
#Mann= 14 ,-1 , 0
  3771.9     .05       0  3774.5     .07       0  3883.5     .05       0
  4039.4     .07       0  4304.3    .035       0  4324.5     .07       0
  4530.8    .035       0  4556.3     .07       0  4765.5     .12       0
    4991     .05       0  5002.7     .12       0  5465.7     .07       0
  5548.3     .12       0    5590     .07       0
Bank Sta=4991,5002.7
XS Rating Curve= 0 ,0
Exp/Cntr=0.3,0.1

Type RM Length L Ch R = 1 ,7759    ,569,569,569
BEGIN DESCRIPTION:
COURT BRANCH 15.0
END DESCRIPTION:
XS GIS Cut Line= 4
      2588978.14     13456887.27      2588722.34     13456624.73
      2588509.81     13456174.53      2587916.49     13455679.05
#Sta/Elev= 30
  4135.6   77.93  4143.8    77.8    4288   72.68  4549.4   57.83  4581.4   56.28
  4598.6   53.93  4604.1   54.74  4621.4   52.06  4626.9   53.42  4644.1   51.28
  4649.7   52.53  4666.9   50.27  4672.4   51.75  4689.7   49.83  4700.9   51.68
  4861.5   46.67  4979.5   44.66  4988.4   44.04  4992.5   42.41    4993   41.91
    5007   42.41  5052.9      44  5293.6   44.55  5428.3   51.43  5528.4    60.7
  5542.2   62.35  5556.5   61.94  5599.5   66.63  5663.3   71.09    5773   76.79
#Mann= 7 ,-1 , 0
  4135.6     .05       0  4143.8    .035       0  4549.4     .07       0
  4861.5      .1       0  4992.5     .05       0    5007      .1       0
  5528.4     .07       0
Bank Sta=4992.5,5007
XS Rating Curve= 0 ,0
Exp/Cntr=0.3,0.1

Type RM Length L Ch R = 1 ,7190    ,426,426,426
BEGIN DESCRIPTION:
COURT BRANCH 14.0
END DESCRIPTION:
XS GIS Cut Line= 3
        2589525.       13456425.        2588925.       13455825.
      2588774.99     13455574.98
#Sta/Elev= 30
  4155.6    63.8  4240.5   56.64  4268.7   52.45    4297   52.74  4339.5   48.74
  4381.9   46.54  4438.4   44.83  4480.9   42.37  4551.6   41.38  4622.3   42.64
  4707.1   41.78  4735.4   42.48  4820.3   41.51  4961.7   41.68  4968.6   41.15
  4969.1   40.65  4983.2   41.15  5011.9   42.52  5027.5    42.5  5070.2   46.43
  5085.8    46.9  5097.4    48.4  5107.1   48.72  5128.5   51.56  5171.3   54.94
  5202.4   58.29    5214   61.05  5229.6   62.26  5272.4   67.48  5295.7   68.65
#Mann= 3 ,-1 , 0
  4155.6     .12       0  4968.6     .05       0  4983.2     .12       0
Bank Sta=4968.6,4983.2
XS Rating Curve= 0 ,0
Exp/Cntr=0.3,0.1

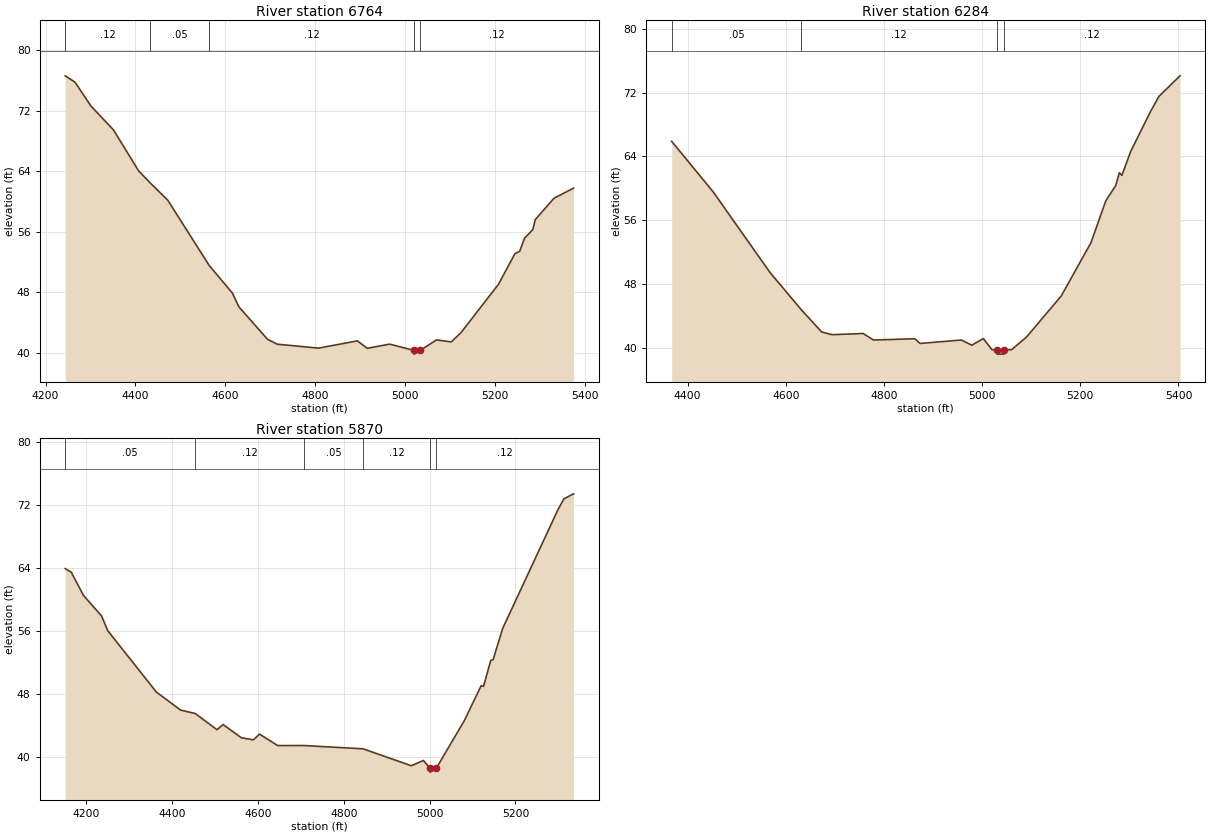
Type RM Length L Ch R = 1 ,6764    ,480,480,480
BEGIN DESCRIPTION:
COURT BRANCH 13.0
END DESCRIPTION:
XS GIS Cut Line= 3
      2589774.99     13456424.99        2589325.       13455825.
      2589174.99     13455474.98
#Sta/Elev= 30
  4243.7   76.58  4265.6   75.74    4301   72.59    4351   69.45  4407.2   64.02
  4433.3   62.42  4471.8   60.17  4564.3   51.53  4615.6   47.91  4630.1   46.09
  4693.7   41.81  4715.6   41.16  4807.2   40.64  4893.7    41.6  4915.6   40.62
  4965.6   41.17    5019   40.35  5019.5   39.85  5033.6   40.35  5069.8   41.73
  5102.5   41.46  5124.2   42.69  5207.7   49.08  5243.9   53.09  5254.8   53.44
  5265.7   55.17  5283.8   56.27  5289.3    57.6    5331   60.42  5374.5   61.76
#Mann= 5 ,-1 , 0
  4243.7     .12       0  4433.3     .05       0  4564.3     .12       0
    5019     .05       0  5033.6     .12       0
Bank Sta=5019,5033.6
XS Rating Curve= 0 ,0
Exp/Cntr=0.3,0.1

Type RM Length L Ch R = 1 ,6284    ,414,414,414
BEGIN DESCRIPTION:
COURT BRANCH 12.0
END DESCRIPTION:
XS GIS Cut Line= 3
      2589925.01     13456225.02        2589725.       13455625.
        2589675.     13455224.98
#Sta/Elev= 30
  4367.5   65.89  4451.8   59.57  4567.8   49.44  4631.7   44.75  4673.2   41.97
  4694.3   41.63  4757.5   41.78  4778.6   40.96  4862.9   41.12  4873.5   40.53
  4957.8   40.96  4978.9   40.31  5002.5   41.14  5020.1   39.74  5030.4   39.69
  5030.9   39.19  5044.6   39.19  5045.1   39.69  5060.4   39.76  5090.7   41.36
  5161.2   46.49  5221.7   53.17  5251.9   58.42  5272.1   60.34  5279.6   61.95
  5284.7   61.62  5302.3   64.57  5342.6   69.58  5360.3   71.54  5403.1   74.11
#Mann= 4 ,-1 , 0
  4367.5     .05       0  4631.7     .12       0  5030.4     .05       0
  5045.1     .12       0
Bank Sta=5030.4,5045.1
XS Rating Curve= 0 ,0
Exp/Cntr=0.3,0.1

Type RM Length L Ch R = 1 ,5870    ,460,460,460
BEGIN DESCRIPTION:
COURT BRANCH 11.0
END DESCRIPTION:
XS GIS Cut Line= 3
      2590624.99     13455974.99        2590025.       13455375.
      2589875.01     13455075.02
#Sta/Elev= 30
  4151.4   63.87  4165.5   63.42  4193.8   60.48  4236.2   57.85  4250.4      56
  4363.5   48.21  4420.1   45.91  4454.3   45.47  4504.9   43.42  4519.1   44.07
  4561.5    42.4  4589.8   42.13  4603.9   42.86  4646.4    41.4  4706.7   41.41
  4845.1   40.99  4957.5   38.84  4985.8   39.51  5000.8   38.53  5001.3   38.03
  5015.8   38.53    5081   44.57  5120.1      49  5125.7   48.93  5142.5    52.2
    5148   52.32  5170.4   56.29    5299   71.35    5313   72.74  5335.3   73.37
#Mann= 6 ,-1 , 0
  4151.4     .05       0  4454.3     .12       0  4706.7     .05       0
  4845.1     .12       0  5000.8     .05       0  5015.8     .12       0
Bank Sta=5000.8,5015.8
XS Rating Curve= 0 ,0
Exp/Cntr=0.3,0.1