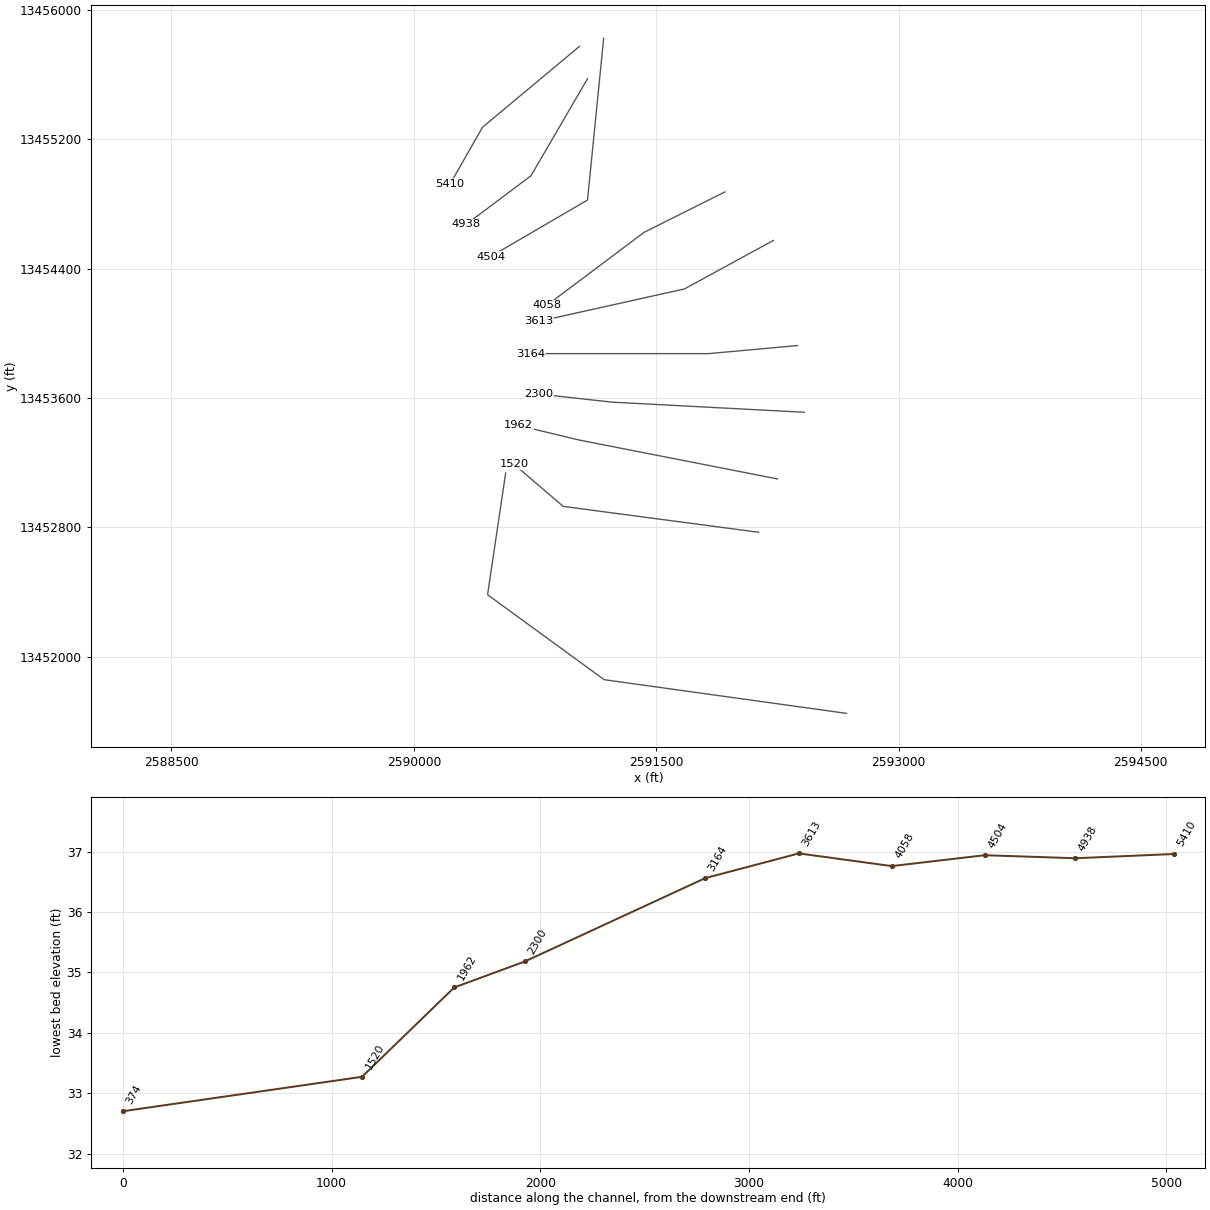
HEC-RAS study COURT BRANCH.prj: COURT BRANCH Base Level Engineering

--- COURT BRANCH.g01 (geometry) --- (continued)

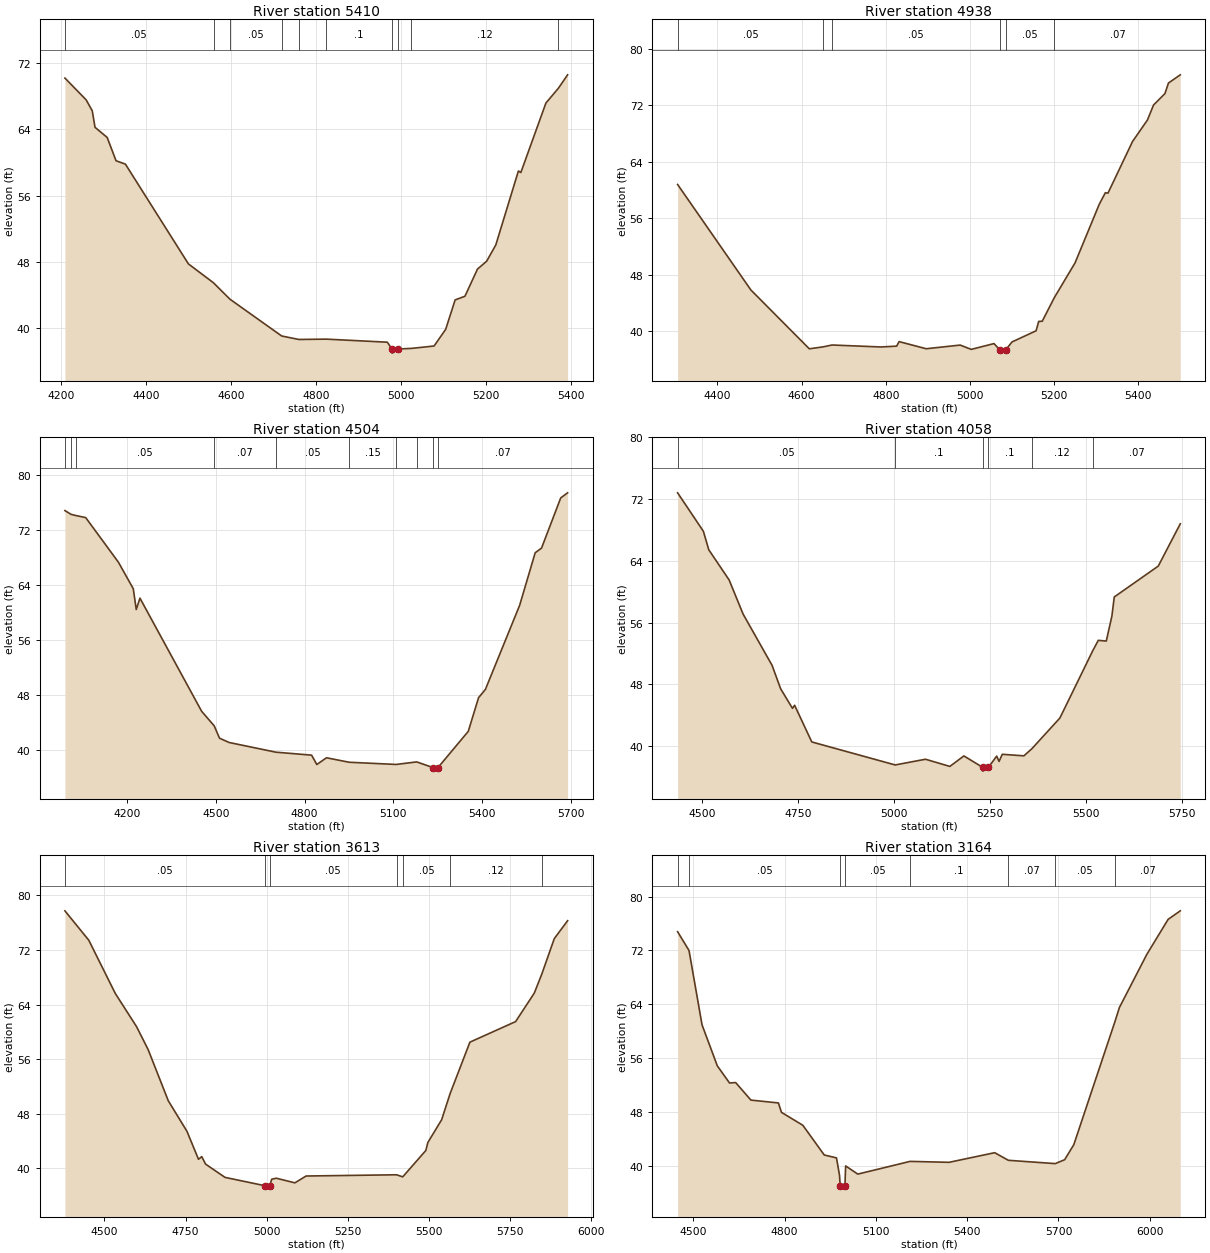
Type RM Length L Ch R = 1 ,5410    ,472,472,472
BEGIN DESCRIPTION:
COURT BRANCH 10.0
END DESCRIPTION:
XS GIS Cut Line= 3
      2591024.99     13455774.99        2590425.       13455275.
      2590225.01     13454925.02
#Sta/Elev= 30
  4208.7   70.19  4258.8   67.55  4273.1   66.23  4279.6   64.24  4308.3   63.01
  4329.1    60.2  4351.2   59.79  4499.6   47.74  4558.8   45.45  4597.3   43.48
  4719.3   39.03  4759.7   38.61  4824.3   38.65  4968.2   38.28  4978.9   37.46
  4979.4   36.96    4994   37.46  5024.7   37.53  5078.3   37.82  5105.6   39.83
  5127.9   43.39    5151   43.83  5180.5   47.11  5202.1   48.06  5223.7   50.03
  5276.9   58.96  5282.7   58.78  5341.7   67.17    5371   68.95  5392.8   70.58
#Mann= 10 ,-1 , 0
  4208.7     .05       0  4558.8     .07       0  4597.3     .05       0
  4719.3     .07       0  4759.7     .05       0  4824.3      .1       0
  4978.9     .05       0    4994      .1       0  5024.7     .12       0
    5371     .07       0
Bank Sta=4978.9,4994
XS Rating Curve= 0 ,0
Exp/Cntr=0.3,0.1

Type RM Length L Ch R = 1 ,4938    ,434,434,434
BEGIN DESCRIPTION:
COURT BRANCH 9.0
END DESCRIPTION:
XS GIS Cut Line= 3
        2591075.       13455575.        2590725.       13454975.
      2590325.02     13454675.02
#Sta/Elev= 30
  4305.4   60.76  4479.5   45.83  4618.4    37.5  4651.6   37.78  4672.4   38.04
  4788.7   37.76    4826   37.88  4831.7   38.52  4896.2   37.51  4976.9   38.03
  5003.2   37.42  5057.3   38.24  5070.6   37.39  5071.1   36.89  5085.7   37.39
    5100   38.47  5157.3   40.05  5163.6   41.38  5171.9    41.4    5201   44.78
    5250   49.67  5307.3   57.94  5321.9   59.59  5328.2   59.54  5386.5   66.84
  5421.9   69.88  5436.5   72.01  5463.6   73.63  5471.9   75.12    5500   76.28
#Mann= 6 ,-1 , 0
  4305.4     .05       0  4651.6     .07       0  4672.4     .05       0
  5070.6     .05       0  5085.7     .05       0    5201     .07       0
Bank Sta=5070.6,5085.7
XS Rating Curve= 0 ,0
Exp/Cntr=0.3,0.1

Type RM Length L Ch R = 1 ,4504    ,446,446,446
BEGIN DESCRIPTION:
COURT BRANCH 8.0
END DESCRIPTION:
XS GIS Cut Line= 3
        2591175.     13455824.97        2591075.       13454825.
      2590474.98     13454474.99
#Sta/Elev= 30
  3989.5   74.79  4010.5   74.24  4025.5   74.08  4059.8   73.77  4170.4   67.29
  4220.6   63.44  4230.7   60.42  4243.2   62.07  4451.8   45.63  4494.4   43.51
  4512.1   41.73  4544.7    41.1  4703.1   39.69  4823.6   39.26  4841.2    37.9
  4873.9   38.88  4950.5   38.23  5109.1   37.91  5178.9   38.28  5235.3   37.44
  5235.8   36.94  5250.6   37.44  5353.3   42.72  5388.1   47.61  5411.2   48.81
    5527   61.03  5579.5   68.66    5601   69.34  5665.9   76.63  5689.1   77.37
#Mann= 10 ,-1 , 0
  3989.5     .05       0  4010.5     .07       0  4025.5     .05       0
  4494.4     .07       0  4703.1     .05       0  4950.5     .15       0
  5109.1     .05       0  5178.9     .07       0  5235.3     .05       0
  5250.6     .07       0
Bank Sta=5235.3,5250.6
XS Rating Curve= 0 ,0
Exp/Cntr=0.3,0.1

Type RM Length L Ch R = 1 ,4058    ,445,445,445
BEGIN DESCRIPTION:
COURT BRANCH 7.0
END DESCRIPTION:
XS GIS Cut Line= 3
        2591925.       13454875.        2591425.       13454625.
      2590825.02     13454175.01
#Sta/Elev= 30
  4436.6   72.81  4503.7   67.83  4517.7   65.44  4570.8   61.52  4607.1   57.11
  4682.6   50.46  4704.9   47.43  4735.7   44.89  4741.3   45.29    4786   40.54
  5003.2   37.56  5082.1    38.3  5145.6   37.37  5182.1   38.73  5230.7   37.26
  5231.2   36.76    5246   37.26  5267.5    38.7  5273.7   38.02  5282.1   38.94
  5338.3   38.74  5359.1   39.66  5432.1   43.64  5517.7   52.36  5532.1    53.7
  5552.9   53.61  5567.5   56.84  5573.7   59.32  5688.3   63.32  5745.6    68.8
#Mann= 6 ,-1 , 0
  4436.6     .05       0  5003.2      .1       0  5230.7     .05       0
    5246      .1       0  5359.1     .12       0  5517.7     .07       0
Bank Sta=5230.7,5246
XS Rating Curve= 0 ,0
Exp/Cntr=0.3,0.1

Type RM Length L Ch R = 1 ,3613    ,449,449,449
BEGIN DESCRIPTION:
COURT BRANCH 6.0
END DESCRIPTION:
XS GIS Cut Line= 3
      2592225.02     13454575.01        2591675.       13454275.
      2590774.98       13454075.
#Sta/Elev= 30
  4378.1   77.72  4451.7   73.41  4533.3   65.62  4598.8   60.76  4634.4   57.41
  4696.6    49.9    4754   45.44  4789.6   41.34  4799.6   41.73  4811.5   40.63
  4871.3   38.69  4994.1   37.47  4994.6   36.97  5009.5   37.47  5014.9   38.41
    5029   38.57  5086.6   37.89  5121.1   38.89  5399.6   39.07  5418.8   38.77
  5489.9   42.63  5496.3   43.81  5538.6   47.13  5564.7   50.96  5625.7   58.49
  5766.5    61.5  5824.1   65.68  5847.3   68.48  5885.6   73.65  5926.6   76.27
#Mann= 7 ,-1 , 0
  4378.1     .05       0  4994.1     .05       0  5009.5     .05       0
  5399.6     .07       0  5418.8     .05       0  5564.7     .12       0
  5847.3     .07       0
Bank Sta=4994.1,5009.5
XS Rating Curve= 0 ,0
Exp/Cntr=0.3,0.1

Type RM Length L Ch R = 1 ,3164    ,864,864,864
BEGIN DESCRIPTION:
COURT BRANCH 5.0
END DESCRIPTION:
XS GIS Cut Line= 3
      2592375.01       13453925.        2591825.       13453875.
      2590724.98       13453875.
#Sta/Elev= 30
  4448.2   74.79  4485.7      72  4528.5   60.96  4578.7   54.87  4618.9   52.32
    4639   52.39  4689.2   49.78  4779.6   49.36  4789.6   47.96  4859.9   46.04
  4930.2   41.63  4970.4    41.2  4980.4   38.62  4982.6   37.06  4983.1   36.56
  4998.2   37.06  5000.5      40  5040.5   38.79  5212.4   40.68  5340.5   40.54
  5490.5   41.97  5535.5   40.84  5689.5   40.35  5720.5   40.93  5750.5   43.16
  5886.1   61.49  5900.5   63.54  5990.5   71.42  6060.5   76.62  6100.5   77.89
#Mann= 8 ,-1 , 0
  4448.2     .07       0  4485.7     .05       0  4982.6     .05       0
  4998.2     .05       0  5212.4      .1       0  5535.5     .07       0
  5689.5     .05       0  5886.1     .07       0
Bank Sta=4982.6,4998.2
XS Rating Curve= 0 ,0
Exp/Cntr=0.3,0.1

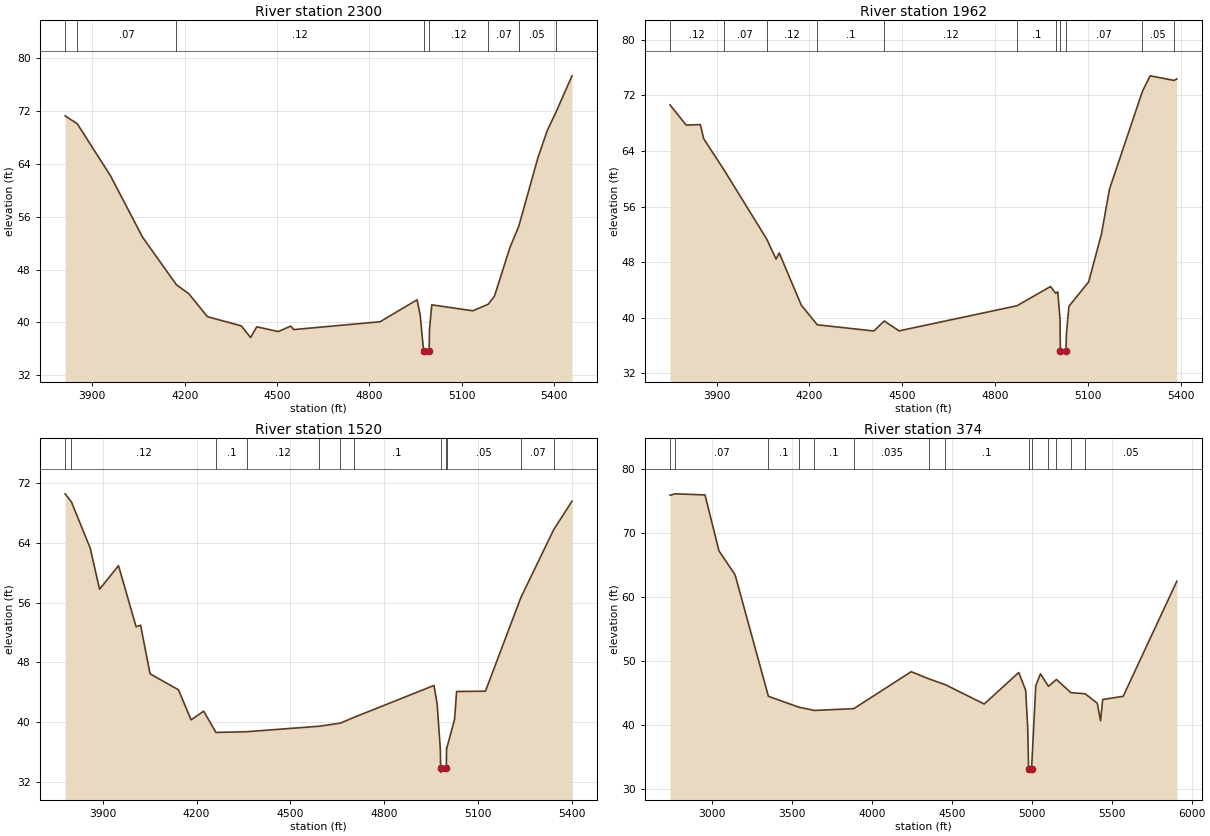
Type RM Length L Ch R = 1 ,2300    ,338,338,338
BEGIN DESCRIPTION:
COURT BRANCH 4.0
END DESCRIPTION:
XS GIS Cut Line= 3
      2592416.24     13453512.31        2591225.       13453575.
      2590774.96       13453625.
#Sta/Elev= 30
  3811.8   71.29  3851.1    70.1  3958.2   62.28  4063.4   52.89    4173    45.7
  4213.6   44.32  4273.7   40.86  4383.8   39.46  4413.9    37.7  4433.9   39.32
    4504    38.6  4544.1   39.43  4554.1    38.9  4834.5   40.09  4954.6   43.42
  4964.6    41.1  4975.6   35.68  4976.1   35.18  4993.8   35.68  4994.7   38.91
  5002.2   42.65  5135.5   41.75  5185.4   42.74  5205.9   43.98  5256.2   51.37
  5284.6   54.55  5346.8   64.93    5377   69.05  5404.1    71.7  5457.5   77.36
#Mann= 8 ,-1 , 0
  3811.8     .05       0  3851.1     .07       0    4173     .12       0
  4975.6     .05       0  4993.8     .12       0  5185.4     .07       0
  5284.6     .05       0  5404.1     .07       0
Bank Sta=4975.6,4993.8
XS Rating Curve= 0 ,0
Exp/Cntr=0.3,0.1

Type RM Length L Ch R = 1 ,1962    ,442,442,442
BEGIN DESCRIPTION:
COURT BRANCH 3.0
END DESCRIPTION:
XS GIS Cut Line= 3
      2592251.26     13453099.99      2591023.99     13453340.42
      2590647.95     13453430.63
#Sta/Elev= 30
  3749.4   70.63  3801.6   67.72  3847.5   67.79  3858.1   65.77  3923.2   61.32
  4061.7   51.32    4092   48.43  4102.2   49.32  4173.6   41.79  4225.3   38.97
  4407.9   38.08  4441.4   39.52  4489.5    38.1  4870.1   41.71  4978.6   44.48
  4995.3   43.51    5002   43.71  5009.2    39.9  5010.4   35.25  5010.9   34.75
  5028.6   35.25  5029.8   37.62    5038   41.64  5101.8   45.15  5142.9   51.99
  5169.1   58.51  5275.7    72.6  5300.3   74.81  5377.5   74.15  5386.7   74.37
#Mann= 11 ,-1 , 0
  3749.4     .12       0  3923.2     .07       0  4061.7     .12       0
  4225.3      .1       0  4441.4     .12       0  4870.1      .1       0
  4995.3     .07       0  5010.4     .05       0  5028.6     .07       0
  5275.7     .05       0  5377.5     .07       0
Bank Sta=5010.4,5028.6
XS Rating Curve= 0 ,0
Exp/Cntr=0.3,0.1

Type RM Length L Ch R = 1 ,1520    ,1146,1146,1146
BEGIN DESCRIPTION:
COURT BRANCH 2.0
END DESCRIPTION:
XS GIS Cut Line= 3
      2592134.12     13452770.12      2590924.57     13452930.18
      2590620.31     13453190.31
#Sta/Elev= 30
  3779.9   70.58  3800.1   69.49    3860   63.31    3890   57.79  3950.5   60.95
  4006.8   52.76  4021.1   52.97  4051.4   46.45  4142.2   44.31  4182.5   40.28
  4222.9   41.44    4262   38.59  4361.3   38.69  4591.5   39.42    4660   39.84
    4702   40.59  4959.2   44.89  4969.3   42.38  4979.4   36.32  4980.4   33.77
  4980.9   33.27  4998.6   33.77  4999.3   36.54  5000.4   36.54  5024.8   40.32
  5031.4   44.08  5123.6   44.12  5236.9   56.68  5342.1    65.8  5400.3   69.59
#Mann= 12 ,-1 , 0
  3779.9     .07       0  3800.1     .12       0    4262      .1       0
  4361.3     .12       0  4591.5      .1       0    4660     .12       0
    4702      .1       0  4980.4     .05       0  4998.6      .1       0
  5000.4     .05       0  5236.9     .07       0  5342.1     .05       0
Bank Sta=4980.4,4998.6
XS Rating Curve= 0 ,0
Exp/Cntr=0.3,0.1

Type RM Length L Ch R = 1 ,374     ,0,0,0
BEGIN DESCRIPTION:
COURT BRANCH 1.0
END DESCRIPTION:
XS GIS Cut Line= 4
      2592678.16     13451650.06      2591178.13      13451858.4
      2590456.45     13452383.94      2590568.42     13453136.97
#Sta/Elev= 30
  2739.1   75.88  2771.7    76.1    2958   75.93  3045.2   67.21  3146.1   63.46
  3354.1   44.53  3542.4   42.84    3642   42.32    3888    42.6  4246.6   48.36
  4360.3   47.22    4460   46.34  4703.4   43.32    4919   48.23  4962.5   45.47
  4975.4   39.55  4980.9    33.2  4981.4    32.7  4999.3    33.2  5025.6   46.17
    5055   48.03  5104.8   46.08  5154.9   47.15  5244.8    45.1  5334.6   44.92
  5410.2   43.44  5430.4   40.71    5444   44.03    5572   44.52  5907.6   62.47
#Mann= 14 ,-1 , 0
  2739.1     .12       0  2771.7     .07       0  3354.1      .1       0
  3542.4     .12       0    3642      .1       0    3888    .035       0
  4360.3     .15       0    4460      .1       0  4980.9     .05       0
  4999.3      .1       0  5104.8     .12       0  5154.9     .05       0
  5244.8     .12       0  5334.6     .05       0
Bank Sta=4980.9,4999.3
XS Rating Curve= 0 ,0
Exp/Cntr=0.3,0.1

Chan Stop Cuts=-1
Use User Specified Reach Order=0
Composite Channel Slope=5