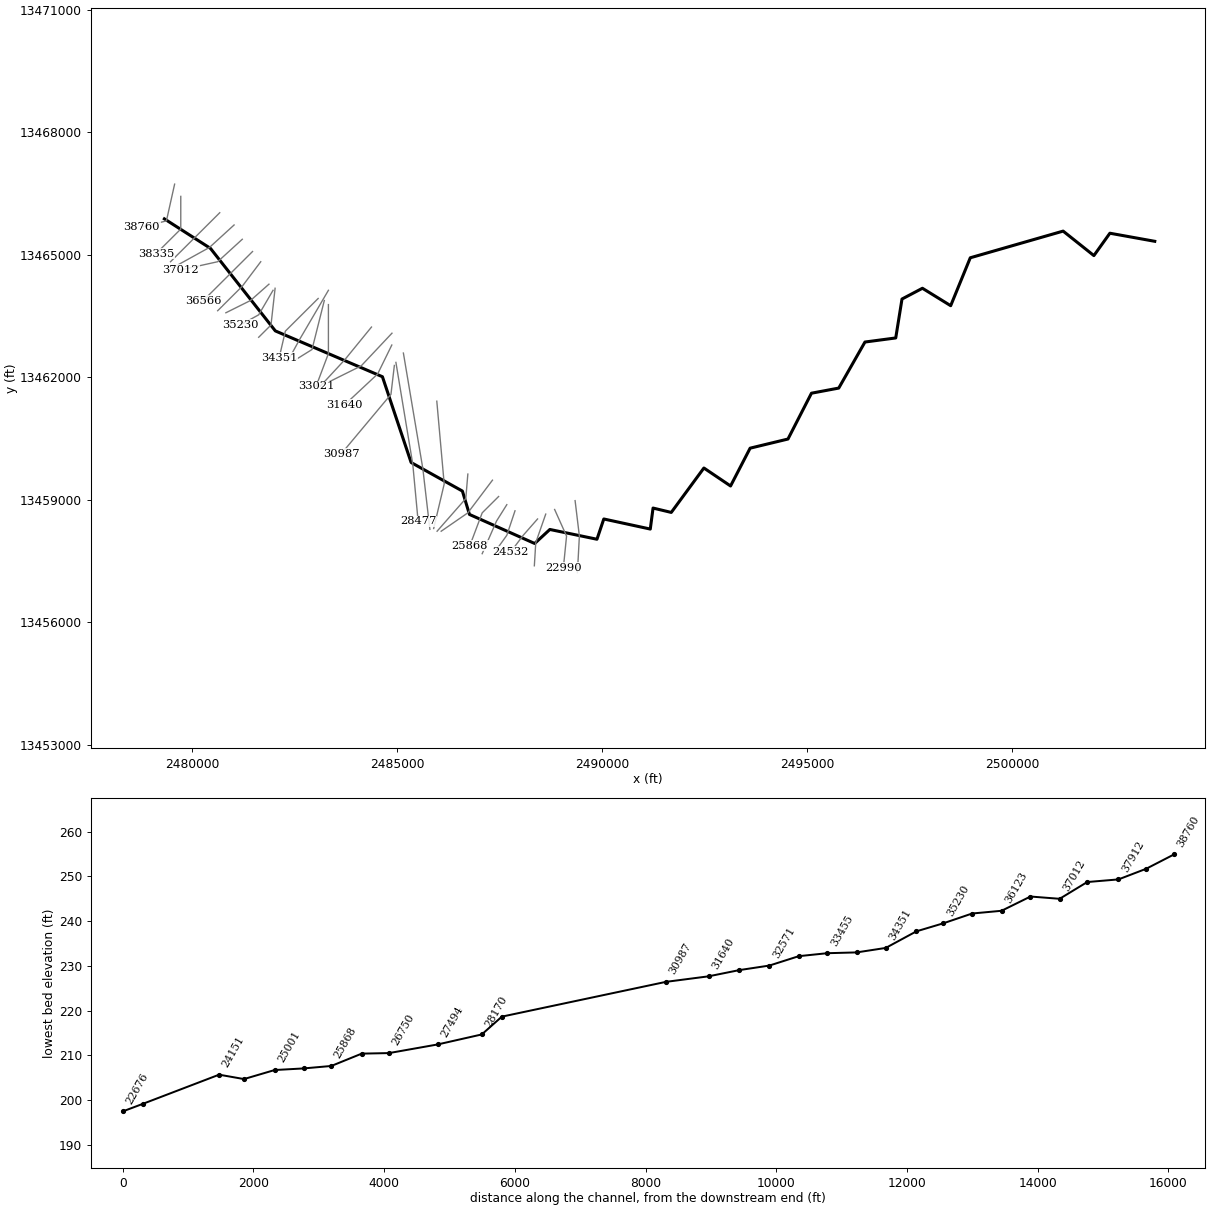
--- FARMER CREEK.prj (project) ---

Proj Title=FARMER CREEK Base Level Engineering
Current Plan=p01
Default Exp/Contr=0.3,0.1
English Units
Geom File=g01
Flow File=f01
Plan File=p01
Y Axis Title=Elevation
X Axis Title(PF)=Main Channel Distance
X Axis Title(XS)=Station
BEGIN DESCRIPTION:
FARMER CREEK
END DESCRIPTION:
DSS Export Rating Curves= 0
DSS Export Rating Curve Sorted= 0
DSS Export Volume Flow Curves= 0
DXF OffsetX= 0
DXF OffsetY= 0
DXF ScaleX= 1
DXF ScaleY= 10

--- FARMER CREEK.p01 (plan) ---

Plan Title=Multiple Run
Short Identifier=Multiple
Geom File=g01
Flow File=f01
Subcritical Flow
K Sum by GR= 0
Std Step Tol= 0.01
Critical Tol= 0.01
Num of Std Step Trials= 20
Max Error Tol= 0.3
Flow Tol Ratio= 0.001
Split Flow NTrial= 30
Split Flow Tol= 0.02
Split Flow Ratio= 0.02
Log Output Level= 0
Friction Slope Method= 1
Unsteady Friction Slope Method= 2
Unsteady Bridges Friction Slope Method= 1
Parabolic Critical Depth
Global Vel Dist=  1 , 1 , 1
Global Log Level= 0
CheckData=True
Encroach Param= -1, 0, 0, 0
BEGIN DESCRIPTION:
Multiple Run
END DESCRIPTION:

--- FARMER CREEK.f01 (steady flow) ---

Flow Title=Multiple
Number of Profiles=7
Profile Names=10-year,25-year,50-year,1pct_min,100-year,1pct_plu,500-year
River Rch & RM= FARMER CREEK,Reach-1,38760
     726    1176    1584    1032    2059    4109    3444
River Rch & RM= FARMER CREEK,Reach-1,34820
     966    1585    2152    1413    2819    5624    4785
River Rch & RM= FARMER CREEK,Reach-1,30987
    1207    1998    2729    1799    3590    7163    6153
River Rch & RM= FARMER CREEK,Reach-1,25001
    1333    2215    3033    2004    3998    7977    6881
River Rch & RM= FARMER CREEK,Reach-1,21750
    1557    2606    3584    2377    4743    9464    8230
River Rch & RM= FARMER CREEK,Reach-1,19521
    1769    2971    4096    2723    5432   10839    9464
River Rch & RM= FARMER CREEK,Reach-1,12836
    2218    3761    5219    3489    6961   13889   12267
River Rch & RM= FARMER CREEK,Reach-1,9031
    2518    4290    5972    4003    7986   15935   14149
River Rch & RM= FARMER CREEK,Reach-1,5638
    2578    4387    6103    4087    8155   16271   14422
Boundary for River Rch & Prof#=FARMER CREEK,Reach-1,1
Up Type=0
Dn Type=3
Dn Slope=0.005
Boundary for River Rch & Prof#=FARMER CREEK,Reach-1,2
Up Type=0
Dn Type=3
Dn Slope=0.005
Boundary for River Rch & Prof#=FARMER CREEK,Reach-1,3
Up Type=0
Dn Type=3
Dn Slope=0.005
Boundary for River Rch & Prof#=FARMER CREEK,Reach-1,4
Up Type=0
Dn Type=3
Dn Slope=0.005
Boundary for River Rch & Prof#=FARMER CREEK,Reach-1,5
Up Type=0
Dn Type=3
Dn Slope=0.005
Boundary for River Rch & Prof#=FARMER CREEK,Reach-1,6
Up Type=0
Dn Type=3
Dn Slope=0.005
Boundary for River Rch & Prof#=FARMER CREEK,Reach-1,7
Up Type=0
Dn Type=3
Dn Slope=0.005

--- FARMER CREEK.g01 (geometry) ---

Geom Title=Existing Conditions
Program Version=4.10

River Reach=FARMER CREEK    ,Reach-1
Reach XY= 30
        2479325.       13465875.      2480448.82       13465152.
      2482030.61     13463130.59      2484642.14     13462008.54
      2485341.63     13459908.29      2486592.13     13459208.56
      2486764.62      13458635.8      2488354.82     13457924.56
      2488724.75     13458268.03      2489873.55     13458028.53
      2490040.21     13458524.76      2491173.64     13458278.04
      2491241.24     13458792.23      2491685.16     13458685.28
      2492480.85     13459772.96      2493131.21      13459332.8
      2493607.86     13460258.72      2494531.21      13460482.8
      2495103.99      13461605.1      2495769.39     13461730.59
      2496408.32     13462858.36       2497158.8     13462958.29
      2497311.44     13463911.51      2497809.61     13464174.92
      2498498.47     13463748.01      2498976.48     13464921.55
       2501240.4      13465574.9       2501990.4     13464975.09
      2502380.65     13465523.04        2503475.       13465325.

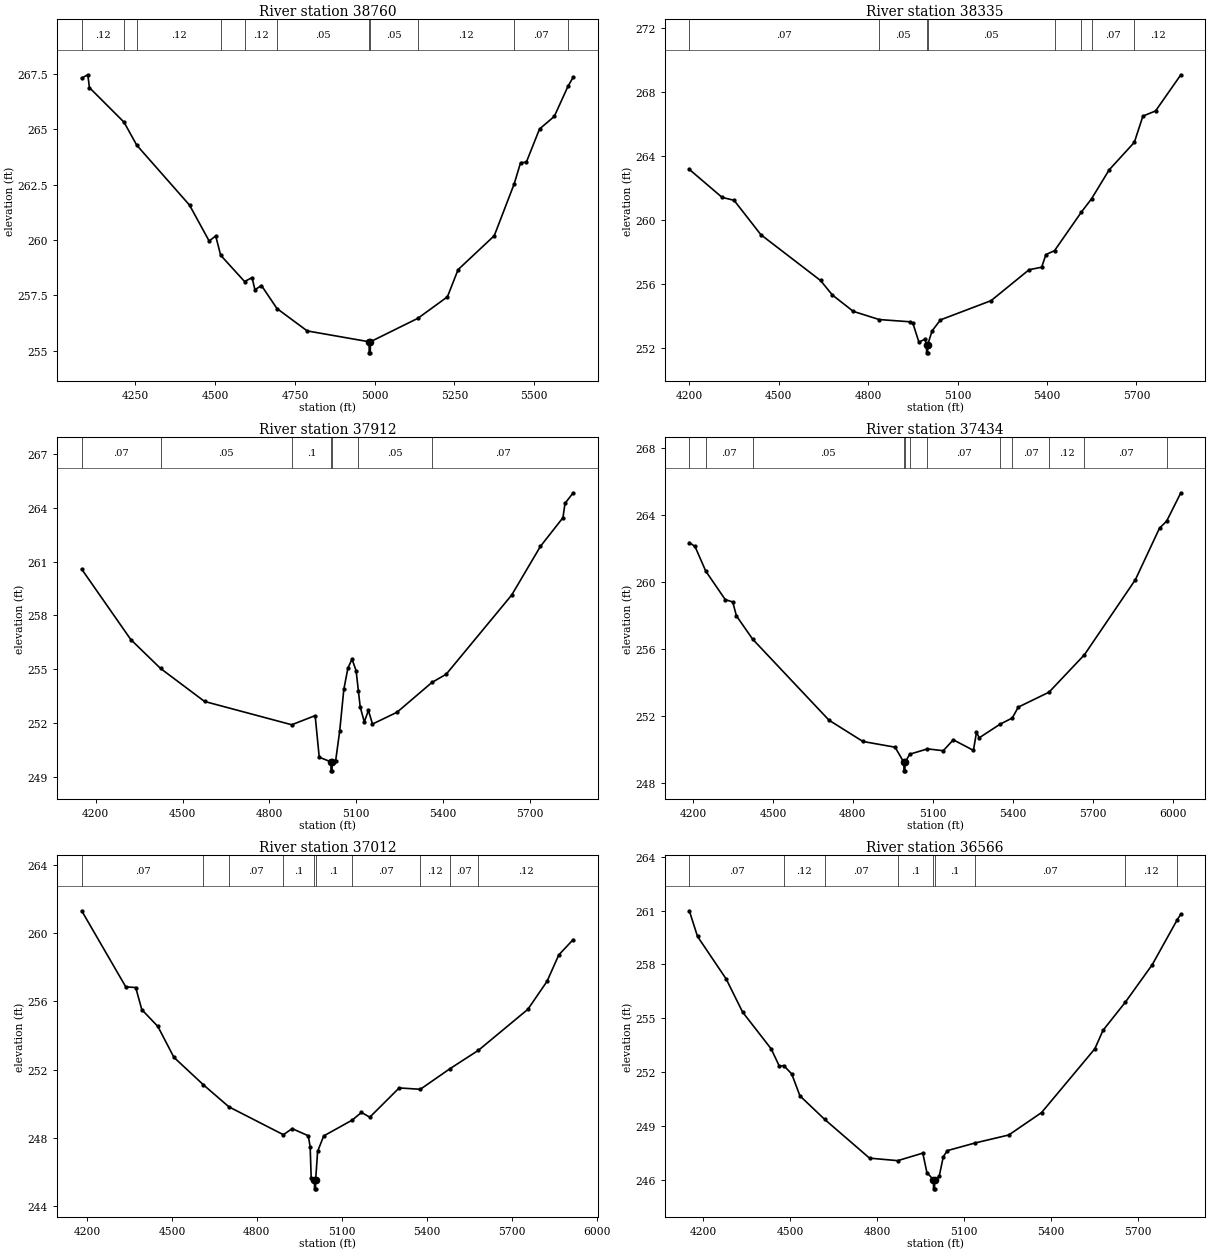
Type RM Length L Ch R = 1 ,38760   ,425,425,425
BEGIN DESCRIPTION:
FARMER CREEK 75.0
END DESCRIPTION:
XS GIS Cut Line= 3
        2479575.       13466725.        2479375.       13465825.
      2478775.02     13465675.01
#Sta/Elev= 30
  4081.8  267.31    4101  267.46  4106.1  266.88  4214.4  265.32  4254.4  264.28
  4419.9  261.57  4481.3  259.95  4501.8  260.18  4517.3  259.31  4592.3  258.12
  4615.8   258.3  4624.7  257.75  4645.2  257.94  4693.9   256.9  4788.6  255.89
  4982.5   255.4  4982.8   254.9  4986.3   254.9  4986.5   255.4  5135.4  256.46
    5228  257.43  5261.5  258.66  5374.8  260.19  5437.2  262.53  5457.3  263.49
  5475.3  263.51  5516.6  265.01    5563  265.58  5605.8  266.94  5622.2  267.35
#Mann= 11 ,-1 , 0
  4081.8     .12       0  4214.4     .07       0  4254.4     .12       0
  4517.3     .07       0  4592.3     .12       0  4693.9     .05       0
  4982.5     .05       0  4986.5     .05       0  5135.4     .12       0
  5437.2     .07       0  5605.8     .12       0
Bank Sta=4982.5,4986.5
XS Rating Curve= 0 ,0
Exp/Cntr=0.3,0.1

Type RM Length L Ch R = 1 ,38335   ,423,423,423
BEGIN DESCRIPTION:
FARMER CREEK 74.0
END DESCRIPTION:
XS GIS Cut Line= 3
        2479725.       13466425.        2479725.       13465625.
      2479125.02     13465025.02
#Sta/Elev= 30
  4200.3  263.16  4310.3  261.41  4350.3  261.23  4440.3  259.08  4640.3  256.22
  4680.3  255.31  4750.3  254.29  4837.1  253.78  4940.3  253.64  4950.3  253.54
  4970.3  252.37  4990.3  252.55  4995.8   252.2  4996.1   251.7  4999.6   251.7
  4999.8   252.2  5014.4  253.07  5042.7  253.76  5212.4  254.96  5339.7  256.89
  5382.1  257.05  5396.3  257.84  5425.1  258.08  5515.5   260.5  5549.2  261.32
  5608.4  263.13  5692.8  264.85  5721.6  266.49    5764  266.81  5848.8  269.07
#Mann= 8 ,-1 , 0
  4200.3     .07       0  4837.1     .05       0  4995.8     .05       0
  4999.8     .05       0  5425.1     .07       0  5515.5     .12       0
  5549.2     .07       0  5692.8     .12       0
Bank Sta=4995.8,4999.8
XS Rating Curve= 0 ,0
Exp/Cntr=0.3,0.1

Type RM Length L Ch R = 1 ,37912   ,478,478,478
BEGIN DESCRIPTION:
FARMER CREEK 73.0
END DESCRIPTION:
XS GIS Cut Line= 3
        2480675.       13466025.        2480075.       13465425.
      2479474.97     13464824.97
#Sta/Elev= 30
  4151.7  260.58  4321.4  256.65  4424.1  255.04    4576   253.2    4877   251.9
  4957.8  252.41  4971.9  250.09  5012.4  249.83  5012.6  249.33  5016.1  249.33
  5016.4  249.83  5028.5  249.88  5042.7  251.57  5056.8  253.87  5070.9  255.06
  5085.1  255.56  5099.2  254.92    5107   253.8  5113.4  252.89  5127.5  252.06
  5141.7   252.7  5155.8  251.94  5240.7   252.6    5361  254.26  5410.4  254.72
  5636.6  259.14  5735.6  261.85  5813.4  263.45  5820.5  264.25  5848.8  264.84
#Mann= 7 ,-1 , 0
  4151.7     .07       0  4424.1     .05       0    4877      .1       0
  5012.4     .05       0  5016.4      .1       0    5107     .05       0
    5361     .07       0
Bank Sta=5012.4,5016.4
XS Rating Curve= 0 ,0
Exp/Cntr=0.3,0.1

Type RM Length L Ch R = 1 ,37434   ,422,422,422
BEGIN DESCRIPTION:
FARMER CREEK 72.0
END DESCRIPTION:
XS GIS Cut Line= 3
      2481025.02     13465725.02        2480425.       13465175.
      2479525.03     13464675.02
#Sta/Elev= 30
  4186.6  262.35  4207.9  262.12  4248.2  260.65  4321.4  258.95  4349.4  258.81
  4363.3  257.98  4424.2  256.59  4710.5  251.76  4837.8  250.49  4958.3  250.15
  4991.5  249.24  4991.7  248.74  4995.2  248.74  4995.5  249.24  5013.1  249.73
  5079.9  250.05    5139  249.94  5176.7  250.59  5252.2  249.96  5263.7  251.04
    5274  250.71    5352  251.52  5397.9  251.89  5420.4  252.54  5535.7  253.43
  5668.4  255.66  5859.7  260.14  5950.1  263.21  5976.9  263.63  6030.1  265.32
#Mann= 12 ,-1 , 0
  4186.6     .12       0  4248.2     .07       0  4424.2     .05       0
  4991.5     .05       0  4995.5     .05       0  5013.1      .1       0
  5079.9     .07       0    5352     .12       0  5397.9     .07       0
  5535.7     .12       0  5668.4     .07       0  5976.9     .12       0
Bank Sta=4991.5,4995.5
XS Rating Curve= 0 ,0
Exp/Cntr=0.3,0.1

Type RM Length L Ch R = 1 ,37012   ,446,446,446
BEGIN DESCRIPTION:
FARMER CREEK 71.0
END DESCRIPTION:
XS GIS Cut Line= 3
        2481225.       13465375.        2480625.       13464825.
        2479725.       13464625.
#Sta/Elev= 30
  4181.4  261.33  4337.1  256.86  4372.2  256.82  4393.8  255.52  4450.6  254.53
    4507  252.72  4611.5   251.1  4701.3  249.81  4893.8  248.17  4924.7  248.53
  4981.5  248.11  4988.3  247.47    4992  245.61  5003.6  245.49  5003.8  244.99
  5007.3  244.99  5007.6  245.49  5014.6  247.19  5036.3   248.1  5136.9  249.03
  5169.5  249.48  5198.9   249.2  5302.7  250.92  5377.4  250.84  5482.1  252.05
  5582.5  253.13  5757.2  255.54  5825.1  257.19  5866.1  258.73  5917.3  259.64
#Mann= 10 ,-1 , 0
  4181.4     .07       0  4611.5     .05       0  4701.3     .07       0
  4893.8      .1       0  5003.6     .05       0  5007.6      .1       0
  5136.9     .07       0  5377.4     .12       0  5482.1     .07       0
  5582.5     .12       0
Bank Sta=5003.6,5007.6
XS Rating Curve= 0 ,0
Exp/Cntr=0.3,0.1

Type RM Length L Ch R = 1 ,36566   ,443,443,443
BEGIN DESCRIPTION:
FARMER CREEK 70.0
END DESCRIPTION:
XS GIS Cut Line= 3
      2481475.03     13465075.03        2480875.       13464475.
        2480275.       13463875.
#Sta/Elev= 30
  4151.2  260.99  4179.5  259.56  4278.5  257.19  4335.1  255.35  4434.1  253.29
  4462.4  252.32  4477.2  252.37  4504.8   251.9  4533.1  250.68  4618.5  249.37
  4773.5  247.21  4870.9  247.07  4957.3  247.49  4971.5  246.41  4994.2     246
  4994.5   245.5    4998   245.5  4998.2     246  5013.9  246.19  5028.1  247.29
  5042.2  247.63  5139.2  248.06  5254.3   248.5  5367.5  249.75  5551.3   253.3
  5579.6  254.33  5656.8   255.9  5749.3  257.98  5836.2   260.5  5848.3   260.8
#Mann= 9 ,-1 , 0
  4151.2     .07       0  4477.2     .12       0  4618.5     .07       0
  4870.9      .1       0  4994.2     .05       0  4998.2      .1       0
  5139.2     .07       0  5656.8     .12       0  5836.2     .07       0
Bank Sta=4994.2,4998.2
XS Rating Curve= 0 ,0
Exp/Cntr=0.3,0.1

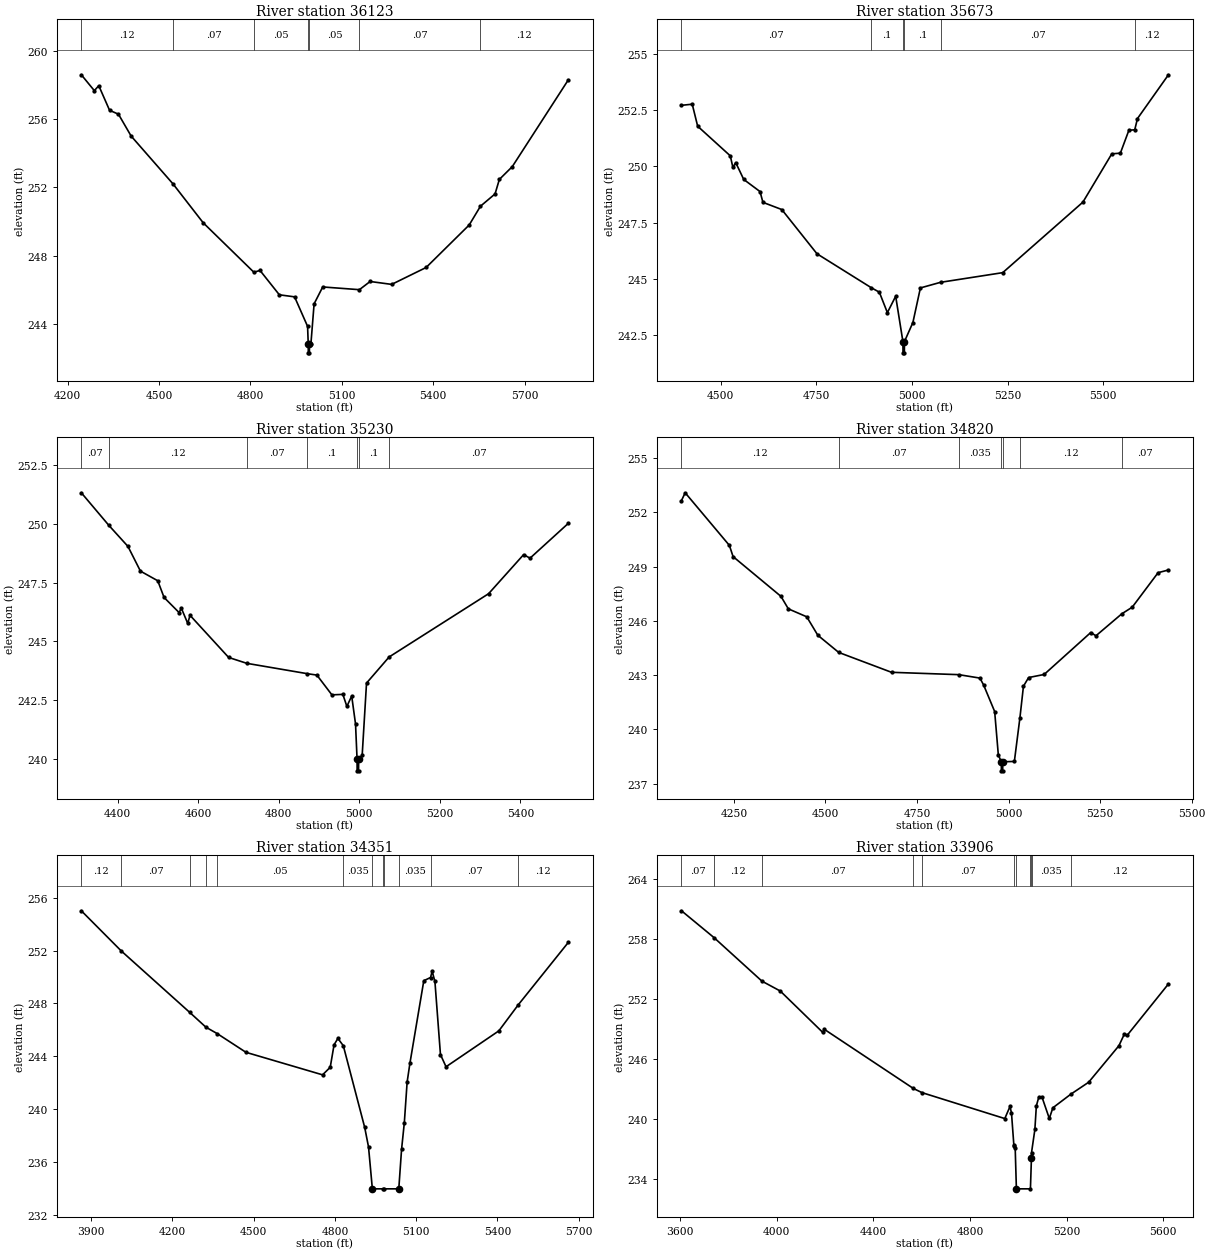
Type RM Length L Ch R = 1 ,36123   ,450,450,450
BEGIN DESCRIPTION:
FARMER CREEK 69.0
END DESCRIPTION:
XS GIS Cut Line= 3
      2481674.99     13464824.98        2481225.       13464225.
      2480625.01     13463625.01
#Sta/Elev= 30
  4245.2   258.6  4287.9  257.67  4302.5  257.96  4337.9  256.52  4367.1  256.29
  4408.7  255.01  4546.5   252.2  4645.2  249.93  4811.7  247.03  4831.6  247.14
  4895.2  245.71  4945.2  245.59  4987.9  243.86  4990.1  242.81  4990.3  242.31
  4993.8  242.31  4994.1  242.81  4998.7  242.81  5009.3  245.18  5037.6  246.17
    5158  246.01  5193.2  246.49  5263.9  246.32    5377  247.31  5518.4   249.8
  5555.4   250.9  5603.3  251.62  5617.4  252.47  5659.9  253.22  5843.7   258.3
#Mann= 7 ,-1 , 0
  4245.2     .12       0  4546.5     .07       0  4811.7     .05       0
  4990.1     .05       0  4994.1     .05       0    5158     .07       0
  5555.4     .12       0
Bank Sta=4990.1,4994.1
XS Rating Curve= 0 ,0
Exp/Cntr=0.3,0.1

Type RM Length L Ch R = 1 ,35673   ,443,443,443
BEGIN DESCRIPTION:
FARMER CREEK 68.0
END DESCRIPTION:
XS GIS Cut Line= 3
      2481875.03     13464275.03        2481425.       13463875.
      2480825.04     13463575.02
#Sta/Elev= 30
  4397.4  252.72  4425.5  252.77  4439.7  251.79    4525  250.47  4531.7  249.96
  4539.2  250.17  4560.1  249.42  4602.7  248.88  4610.3   248.4  4659.6  248.08
  4751.6  246.11  4893.5   244.6  4914.6   244.4  4935.6  243.49  4957.3  244.22
  4976.2   242.2  4976.5   241.7    4980   241.7  4980.2   242.2  5002.3  243.05
  5021.9  244.59  5074.6  244.84  5237.1  245.27  5446.7  248.41  5522.2  250.56
  5544.6  250.59  5566.9  251.61  5582.2  251.63  5589.3  252.13  5670.3  254.08
#Mann= 6 ,-1 , 0
  4397.4     .07       0  4893.5      .1       0  4976.2     .05       0
  4980.2      .1       0  5074.6     .07       0  5582.2     .12       0
Bank Sta=4976.2,4980.2
XS Rating Curve= 0 ,0
Exp/Cntr=0.3,0.1

Type RM Length L Ch R = 1 ,35230   ,410,410,410
BEGIN DESCRIPTION:
FARMER CREEK 67.0
END DESCRIPTION:
XS GIS Cut Line= 3
        2481975.       13464125.        2481625.       13463525.
        2481175.       13463275.
#Sta/Elev= 30
  4309.6  251.32  4378.2  249.93  4425.4  249.04  4456.4  247.99  4499.4  247.58
  4515.1  246.87  4552.3  246.23  4558.1  246.41  4573.8  245.77  4579.6  246.11
  4675.5  244.32  4720.6  244.07  4870.8  243.63  4894.6  243.57  4931.9  242.73
  4959.1  242.75  4969.1  242.24  4981.1  242.68  4990.6  241.49  4994.4     240
  4994.6   239.5  4998.1   239.5  4998.4     240  5007.1  240.16  5017.9  243.23
    5074  244.34  5321.1  247.03    5408  248.69    5424  248.54    5519  250.02
#Mann= 7 ,-1 , 0
  4309.6     .07       0  4378.2     .12       0  4720.6     .07       0
  4870.8      .1       0  4994.4     .05       0  4998.4      .1       0
    5074     .07       0
Bank Sta=4994.4,4998.4
XS Rating Curve= 0 ,0
Exp/Cntr=0.3,0.1

Type RM Length L Ch R = 1 ,34820   ,469,469,469
BEGIN DESCRIPTION:
FARMER CREEK 66.0
END DESCRIPTION:
XS GIS Cut Line= 3
      2482025.01     13464175.05        2481925.       13463275.
      2481624.97     13462974.97
#Sta/Elev= 30
  4106.7  252.66  4116.8  253.09  4237.5  250.18  4247.6  249.56  4378.4  247.36
  4398.5  246.67  4448.8  246.23    4479  245.21  4536.1  244.26  4680.3  243.16
    4864  243.03  4921.7  242.84  4931.8  242.46    4962  240.99    4972  238.59
  4980.1  238.21  4980.4  237.71  4983.9  237.71  4984.1  238.21  5015.8  238.23
    5031  240.65  5040.6  242.39  5054.7  242.87  5097.1  243.04  5224.4  245.36
  5238.6  245.18  5309.5   246.4  5337.6  246.76  5408.3  248.67  5436.6  248.82
#Mann= 7 ,-1 , 0
  4106.7     .12       0  4536.1     .07       0    4864    .035       0
  4980.1    .035       0  4984.1    .035       0    5031     .12       0
  5309.5     .07       0
Bank Sta=4980.1,4984.1
XS Rating Curve= 0 ,0
Exp/Cntr=0.3,0.1

Type RM Length L Ch R = 1 ,34351   ,445,445,445
BEGIN DESCRIPTION:
FARMER CREEK 65.0
END DESCRIPTION:
XS GIS Cut Line= 3
      2483074.98     13463924.98        2482275.       13463125.
      2482125.01     13462475.03
#Sta/Elev= 30
  3863.4     255  4010.7  251.97    4264  247.32  4323.4  246.21  4365.5  245.72
  4471.5  244.31  4754.3  242.61  4782.6  243.18  4796.8  244.88  4810.9  245.36
  4830.9  244.81  4909.9  238.64    4924  237.17  4938.2     234  4978.4     234
  4982.8     234  5035.8     234  5046.1  236.99  5056.3     239  5066.6  242.06
  5076.8  243.47  5128.2  249.72    5153  249.96    5159  250.43  5169.2  249.67
  5189.7  244.14  5210.3  243.22  5405.3  245.93  5477.5  247.91  5661.8  252.61
#Mann= 12 ,-1 , 0
  3863.4     .12       0  4010.7     .07       0    4264     .05       0
  4323.4     .07       0  4365.5     .05       0  4830.9    .035       0
  4938.2    .035       0  4978.4    .035       0  4982.8    .035       0
  5035.8    .035       0    5153     .07       0  5477.5     .12       0
Bank Sta=4938.2,5035.8
XS Rating Curve= 0 ,0
Exp/Cntr=0.3,0.1

Type RM Length L Ch R = 1 ,33906   ,451,451,451
BEGIN DESCRIPTION:
FARMER CREEK 64.0
END DESCRIPTION:
XS GIS Cut Line= 3
      2483324.98     13464124.96        2482625.       13462925.
        2482325.       13462375.
#Sta/Elev= 30
    3606  260.86  3740.7  258.17    3939  253.81  4014.9  252.82    4191  248.67
  4196.8  248.99  4565.6  243.06  4601.5  242.64  4944.3  240.04  4965.8  241.25
    4972   240.6  4981.6  237.44  4983.7  237.32  4987.3  237.12  4992.3     233
  5050.4     233  5054.6  236.12  5054.9  236.62  5068.8  238.95  5074.9  241.31
  5084.9  242.18  5097.7  242.23  5128.6  240.05  5143.3  241.12    5218  242.49
  5291.4  243.68  5416.7  247.34    5439   248.5  5450.8  248.38  5621.7  253.53
#Mann= 11 ,-1 , 0
    3606     .07       0  3740.7     .12       0    3939     .07       0
  4565.6     .05       0  4601.5     .07       0  4983.7    .035       0
  4992.3    .035       0  5050.4    .035       0  5054.6    .035       0
  5054.9    .035       0    5218     .12       0
Bank Sta=4992.3,5054.6
XS Rating Curve= 0 ,0
Exp/Cntr=0.3,0.1

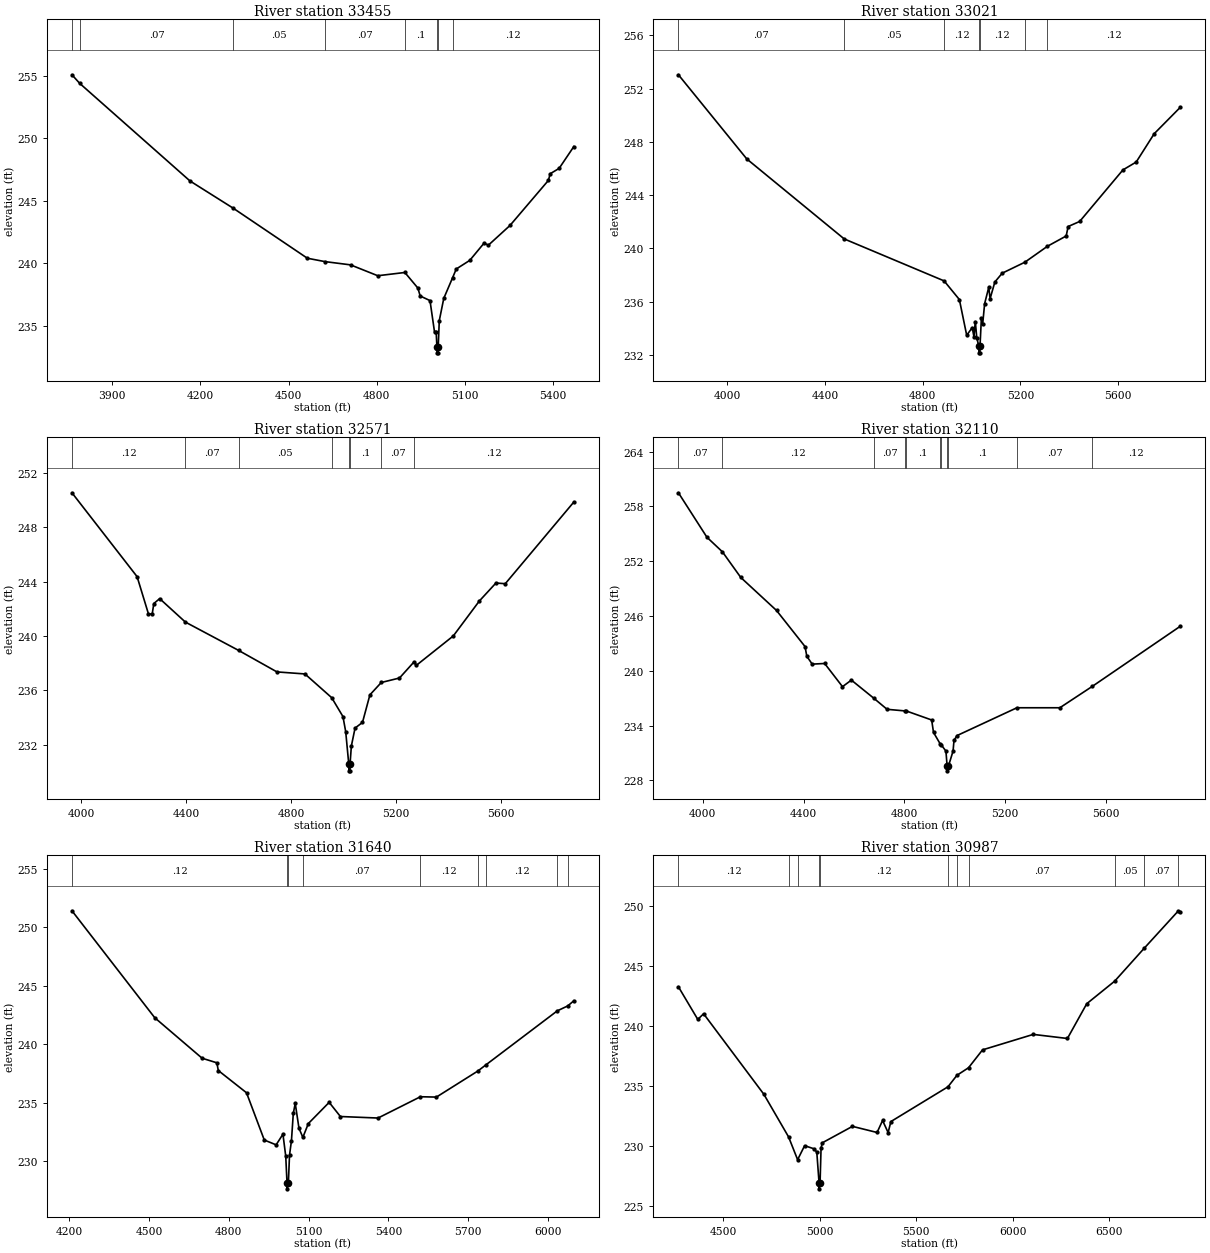
Type RM Length L Ch R = 1 ,33455   ,434,434,434
BEGIN DESCRIPTION:
FARMER CREEK 63.0
END DESCRIPTION:
XS GIS Cut Line= 3
        2483225.       13463875.        2482925.       13462675.
      2482525.03     13462425.02
#Sta/Elev= 30
  3762.6  255.07  3789.1  254.38  4164.6  246.57  4311.8  244.39    4564  240.39
  4623.9  240.12  4710.9  239.86  4803.7  238.99  4895.9  239.25  4940.3     238
    4948  237.37  4981.5     237    4997  234.47  5002.5  234.47    5005  233.32
  5005.3  232.82  5009.2  232.82  5009.5  233.32  5013.1   235.4  5028.4  237.18
  5058.4  238.83  5070.9  239.53  5116.9  240.22  5165.2  241.59  5180.5  241.44
  5253.7  243.01  5384.6  246.62  5390.5  247.15  5421.1  247.58  5471.2  249.33
#Mann= 8 ,-1 , 0
  3762.6     .12       0  3789.1     .07       0  4311.8     .05       0
  4623.9     .07       0  4895.9      .1       0    5005     .05       0
  5009.5      .1       0  5058.4     .12       0
Bank Sta=5005,5009.5
XS Rating Curve= 0 ,0
Exp/Cntr=0.3,0.1

Type RM Length L Ch R = 1 ,33021   ,450,450,450
BEGIN DESCRIPTION:
FARMER CREEK 62.0
END DESCRIPTION:
XS GIS Cut Line= 3
        2483325.     13463775.04        2483325.       13462575.
      2483025.01     13461775.04
#Sta/Elev= 30
    3800  253.03    4080  246.71  4478.6  240.71  4887.5  237.56    4950  236.16
    4980  233.48  5002.7  234.05  5009.8  233.36  5015.2  234.51  5021.4  233.27
  5029.7  232.66    5030  232.16  5034.1  232.16  5034.5  232.66  5040.1  234.75
  5045.4  234.32  5053.4  235.85  5070.3  237.08  5075.7  236.22  5095.3  237.48
  5125.5  238.14  5217.9  238.96  5310.6  240.16  5387.2  240.93  5395.2  241.64
  5442.4  242.02  5619.5  245.89  5673.8  246.48  5747.6  248.61  5854.4  250.59
#Mann= 7 ,-1 , 0
    3800     .07       0  4478.6     .05       0  4887.5     .12       0
  5029.7     .05       0  5034.5     .12       0  5217.9     .07       0
  5310.6     .12       0
Bank Sta=5029.7,5034.5
XS Rating Curve= 0 ,0
Exp/Cntr=0.3,0.1

Type RM Length L Ch R = 1 ,32571   ,461,461,461
BEGIN DESCRIPTION:
FARMER CREEK 61.0
END DESCRIPTION:
XS GIS Cut Line= 3
      2484375.03     13463225.03        2483725.       13462425.
      2483125.01     13461775.01
#Sta/Elev= 30
  3964.5  250.55  4213.1  244.37  4256.2  241.64  4270.6   241.6    4277  242.39
  4299.3  242.75  4397.5  241.02  4600.9  238.93  4746.8  237.35  4853.6   237.2
  4955.8  235.45  4998.7  234.06  5009.2  232.95  5020.9  230.56  5021.3  230.06
  5025.5  230.06  5025.8  230.56  5030.8  231.89  5044.9  233.21  5073.3  233.63
  5101.6  235.66    5145  236.57  5214.5   236.9  5270.1  238.09  5278.6  237.83
  5419.8     240    5519  242.57  5582.5   243.9  5618.2  243.85  5879.9  249.87
#Mann= 8 ,-1 , 0
  3964.5     .12       0  4397.5     .07       0  4600.9     .05       0
  4955.8      .1       0  5020.9     .05       0  5025.8      .1       0
    5145     .07       0  5270.1     .12       0
Bank Sta=5020.9,5025.8
XS Rating Curve= 0 ,0
Exp/Cntr=0.3,0.1

Type RM Length L Ch R = 1 ,32110   ,470,470,470
BEGIN DESCRIPTION:
FARMER CREEK 60.0
END DESCRIPTION:
XS GIS Cut Line= 3
      2484875.03     13463075.03        2484125.       13462275.
      2483325.04     13461875.02
#Sta/Elev= 30
  3903.5   259.5  4016.6  254.63  4078.1  253.03    4151  250.22  4292.6  246.61
  4405.9  242.65  4412.8  241.59  4434.2  240.73  4483.6   240.8  4554.4  238.26
  4589.6  238.98  4678.3     237  4731.2  235.78  4803.7   235.6  4806.3  235.61
  4908.1  234.61  4915.4  233.25  4942.6  231.96  4945.8   231.9  4964.7   231.2
  4969.5  229.54  4969.9  229.04  4974.5  229.54    4993  231.21  4996.7  232.37
  5008.5   232.9  5246.3  235.95  5416.6  235.95  5545.2  238.29  5894.5  244.88
#Mann= 11 ,-1 , 0
  3903.5     .07       0  4078.1     .12       0  4678.3     .07       0
  4803.7     .12       0  4806.3      .1       0  4942.6     .12       0
  4945.8      .1       0  4969.5     .05       0  4974.5      .1       0
  5246.3     .07       0  5545.2     .12       0
Bank Sta=4969.5,4974.5
XS Rating Curve= 0 ,0
Exp/Cntr=0.3,0.1

Type RM Length L Ch R = 1 ,31640   ,653,653,653
BEGIN DESCRIPTION:
FARMER CREEK 59.0
END DESCRIPTION:
XS GIS Cut Line= 3
      2484870.76     13462784.76        2484525.       13462075.
      2483724.99     13461324.99
#Sta/Elev= 30
  4210.5  251.41  4521.7  242.27  4699.7  238.81    4755  238.42  4760.5  237.76
  4866.5  235.86  4933.3  231.82  4977.8  231.41  5003.4  232.32  5013.9  230.44
  5018.7  228.15  5019.1  227.65  5023.8  228.15  5028.1  230.53  5035.4  231.77
  5042.3   234.1  5049.6  234.95  5063.7  232.82  5078.3  232.05  5098.9  233.23
  5177.1  235.04  5219.3  233.83  5360.7   233.7  5520.1  235.52  5580.1  235.49
    5736  237.72  5765.9  238.24  6034.4  242.86  6073.6  243.28  6096.6  243.72
#Mann= 9 ,-1 , 0
  4210.5     .12       0  5018.7     .05       0  5023.8     .12       0
  5078.3     .07       0  5520.1     .12       0    5736     .07       0
  5765.9     .12       0  6034.4     .07       0  6073.6     .12       0
Bank Sta=5018.7,5023.8
XS Rating Curve= 0 ,0
Exp/Cntr=0.3,0.1

Type RM Length L Ch R = 1 ,30987   ,2510,2510,2510
BEGIN DESCRIPTION:
Mapping XS 13665f98
END DESCRIPTION:
XS GIS Cut Line= 3
      2484933.25     13462284.75      2484849.92     13461576.41
      2483641.57       13460125.
#Sta/Elev= 30
  4267.4  243.26  4367.8  240.54    4398  241.01  4710.2   234.3  4838.5  230.74
  4885.3  228.84  4921.6  230.01    4972  229.74  4984.8  229.46  4996.5  226.91
  4996.9  226.41  5001.7  226.91  5006.9  229.82  5013.4  230.25  5169.6  231.62
  5297.2  231.11  5325.8  232.11  5354.5   231.1  5368.8  232.02  5664.7  234.92
  5711.3  235.88  5771.4  236.51  5843.9     238  6106.9  239.29  6283.9  238.95
  6384.2  241.85  6528.9  243.73  6683.4   246.5  6859.4   249.6  6869.2   249.5
#Mann= 11 ,-1 , 0
  4267.4     .12       0  4838.5     .07       0  4885.3     .12       0
  4996.5     .05       0  5001.7     .12       0  5664.7     .07       0
  5711.3     .12       0  5771.4     .07       0  6528.9     .05       0
  6683.4     .07       0  6859.4     .12       0
Bank Sta=4996.5,5001.7
XS Rating Curve= 0 ,0
Exp/Cntr=0.3,0.1

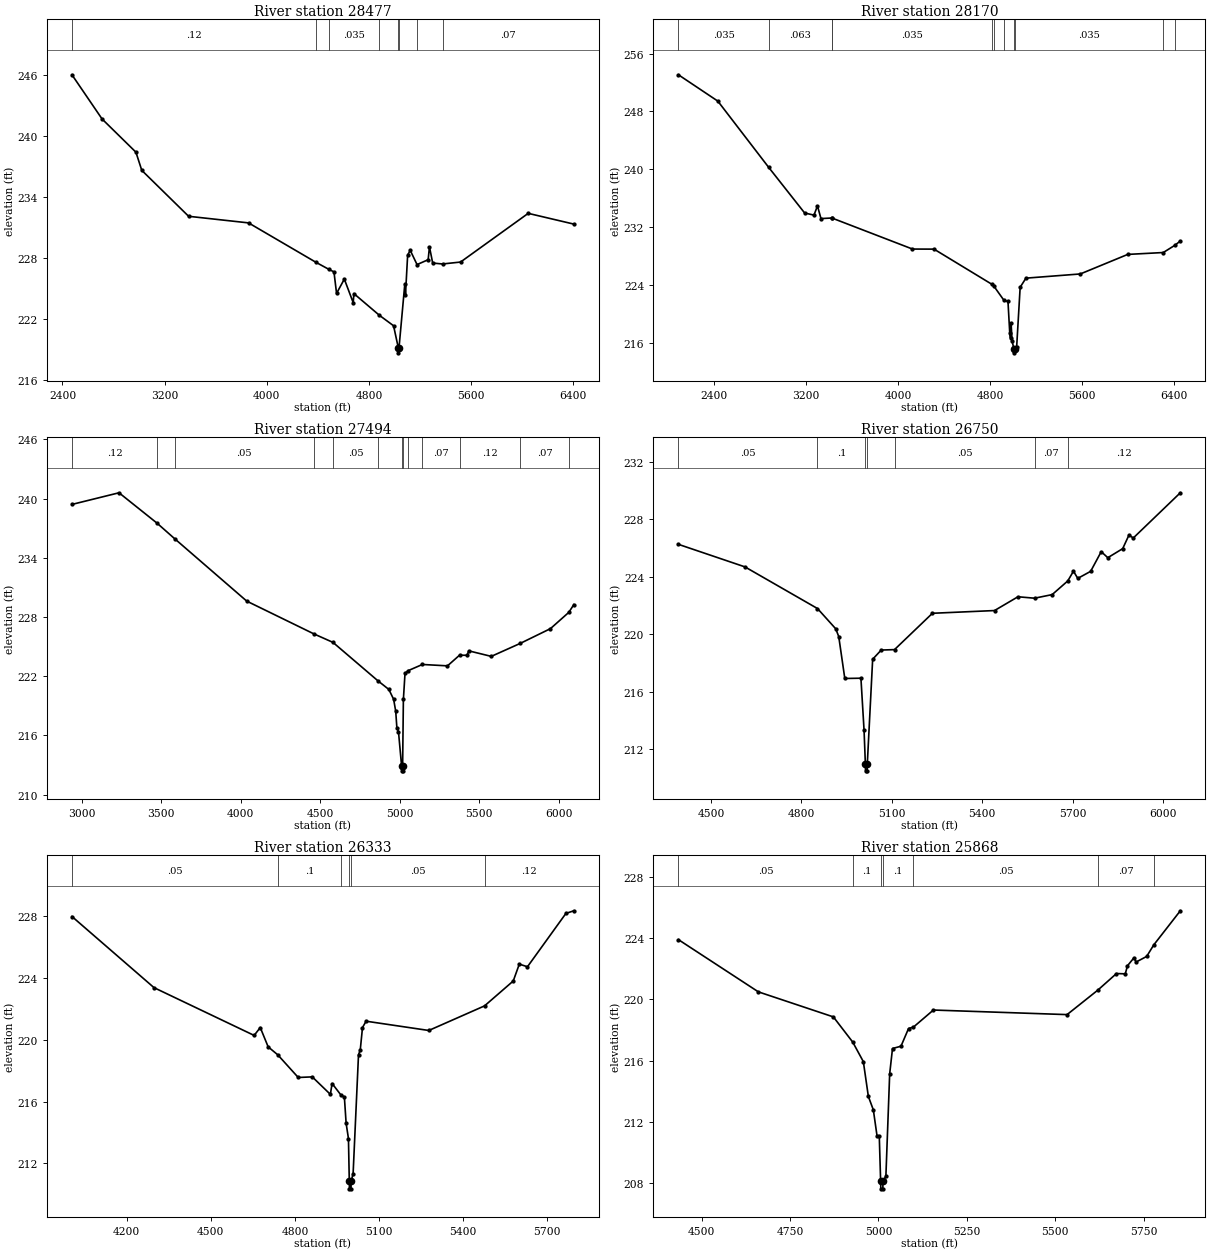
Type RM Length L Ch R = 1 ,28477   ,307,307,307
BEGIN DESCRIPTION:
Mapping XS 18b1c6cc
END DESCRIPTION:
XS GIS Cut Line= 3
      2484971.01      13462359.2      2485382.47     13459864.39
      2485512.61     13458469.26
#Sta/Elev= 30
  2474.4  246.04  2710.4  241.68  2975.3  238.41  3021.1  236.62  3387.9  232.09
    3857  231.44  4384.2  227.56    4486  226.86  4525.9  226.61  4546.2  224.49
    4607   225.9  4676.7  223.57  4681.8  224.47  4881.6  222.33  4992.5   221.3
  5029.6  219.13  5030.1  218.63  5035.2  219.13  5080.8  225.45  5085.8  224.36
  5102.7  228.25  5122.8  228.74  5176.3  227.33  5263.4  227.81  5273.5  229.08
  5298.9  227.48  5375.9  227.39  5517.1  227.58  6046.8  232.38  6404.1  231.32
#Mann= 8 ,-1 , 0
  2474.4     .12       0  4384.2      .1       0    4486    .035       0
  4881.6     .12       0  5029.6     .05       0  5035.2     .12       0
  5176.3     .05       0  5375.9     .07       0
Bank Sta=5029.6,5035.2
XS Rating Curve= 0 ,0
Exp/Cntr=0.3,0.1

Type RM Length L Ch R = 1 ,28170   ,676,676,676
BEGIN DESCRIPTION:
Mapping XS 45250c71
END DESCRIPTION:
XS GIS Cut Line= 3
      2485153.31      13462588.3      2485627.26     13459760.22
      2485799.14     13458270.62
#Sta/Elev= 30
  2089.8  253.07  2432.8  249.43  2875.6  240.27  3188.2  233.97  3269.3  233.68
  3299.7  234.95  3330.2   233.2  3424.5  233.28    3430  233.25  4126.5  228.99
  4313.7  228.98  4818.4  224.11  4836.1  223.83  4922.9  221.89  4957.3  221.75
  4972.6  217.42  4979.4  216.67  4984.5  218.73  4992.8  216.29  5009.8  215.15
  5010.3  214.65  5016.1  215.15    5033  215.51  5063.2  223.71  5113.6  224.97
  5586.7  225.55  5999.4  228.25  6308.5  228.51  6407.4  229.49  6456.8   230.1
#Mann= 11 ,-1 , 0
  2089.8    .035       0  2875.6    .063       0  3424.5     .07       0
    3430    .035       0  4818.4    .063       0  4836.1     .05       0
  4922.9    .035       0  5009.8    .035       0  5016.1    .035       0
  6308.5    .063       0  6407.4    .035       0
Bank Sta=5009.8,5016.1
XS Rating Curve= 0 ,0
Exp/Cntr=0.3,0.1

Type RM Length L Ch R = 1 ,27494   ,744,744,744
BEGIN DESCRIPTION:
Mapping XS 9a38d15e
END DESCRIPTION:
XS GIS Cut Line= 3
      2485967.98     13461409.74      2486148.53     13459381.97
      2485891.59     13458291.73
#Sta/Elev= 30
  2938.6  239.41  3234.5  240.59    3473  237.52  3584.1  235.94  4037.7  229.61
  4461.1  226.28  4579.7  225.43  4862.1  221.54  4931.2  220.66  4961.3  219.66
  4974.4  218.45  4981.6  216.79  4991.8  216.38  5011.3  212.91  5011.8  212.41
  5017.3  212.41  5017.8  212.91  5022.6  219.64  5032.9   222.3  5053.6  222.57
  5142.1  223.19    5300  223.05  5375.7  224.13  5423.3  224.12  5433.6  224.57
  5575.3  224.01  5756.7  225.32  5947.3  226.82  6062.7  228.47  6094.5  229.26
#Mann= 13 ,-1 , 0
  2938.6     .12       0    3473     .07       0  3584.1     .05       0
  4461.1     .07       0  4579.7     .05       0  4862.1      .1       0
  5011.3     .05       0  5017.8      .1       0  5053.6     .05       0
  5142.1     .07       0  5375.7     .12       0  5756.7     .07       0
  6062.7     .12       0
Bank Sta=5011.3,5017.8
XS Rating Curve= 0 ,0
Exp/Cntr=0.3,0.1

Type RM Length L Ch R = 1 ,26750   ,417,417,417
BEGIN DESCRIPTION:
FARMER CREEK 49.0
END DESCRIPTION:
XS GIS Cut Line= 3
        2486725.     13459625.05        2486675.       13459025.
      2485975.03     13458225.03
#Sta/Elev= 30
  4392.3  226.25  4613.1  224.68  4853.7  221.78  4914.2  220.37  4924.2  219.83
  4944.3  216.91  4997.8  216.93  5008.2   213.3  5012.5  210.98    5013  210.48
  5018.5  210.48    5019  210.98  5036.7  218.25  5065.1  218.89  5109.2  218.92
    5235  221.45    5441  221.64  5518.8   222.6  5573.8   222.5  5632.2  222.75
  5683.9   223.7  5702.9  224.38  5717.2  223.88  5759.9  224.37    5795  225.74
  5816.8  225.32  5866.2  225.95  5887.1   226.9  5901.3  226.69  6057.4  229.84
#Mann= 7 ,-1 , 0
  4392.3     .05       0  4853.7      .1       0  5012.5     .05       0
    5019      .1       0  5109.2     .05       0  5573.8     .07       0
  5683.9     .12       0
Bank Sta=5012.5,5019
XS Rating Curve= 0 ,0
Exp/Cntr=0.3,0.1

Type RM Length L Ch R = 1 ,26333   ,465,465,465
BEGIN DESCRIPTION:
FARMER CREEK 48.0
END DESCRIPTION:
XS GIS Cut Line= 3
      2487324.98     13459474.98        2486725.       13458675.
      2486075.04     13458225.03
#Sta/Elev= 30
  4004.4  227.97  4297.1  223.37  4654.4  220.28  4676.2  220.79  4704.4  219.54
  4738.4  219.03  4811.7  217.56  4861.7   217.6  4926.2  216.47  4932.5  217.17
  4965.2   216.4  4976.2  216.31  4982.5   214.6  4990.8  213.61  4993.8  210.86
  4994.3  210.36  4999.9  210.36  5000.4  210.86  5007.4  211.33  5026.7  219.04
  5032.8  219.32  5040.9  220.79  5053.7   221.2  5277.4   220.6  5476.3  222.19
  5578.7   223.8  5600.3  224.89  5629.4  224.72  5766.6  228.17  5794.9  228.34
#Mann= 6 ,-1 , 0
  4004.4     .05       0  4738.4      .1       0  4965.2     .05       0
  4993.8     .05       0  5000.4     .05       0  5476.3     .12       0
Bank Sta=4993.8,5000.4
XS Rating Curve= 0 ,0
Exp/Cntr=0.3,0.1

Type RM Length L Ch R = 1 ,25868   ,423,423,423
BEGIN DESCRIPTION:
FARMER CREEK 47.0
END DESCRIPTION:
XS GIS Cut Line= 3
      2487474.97     13459074.97        2487075.       13458675.
      2486775.02     13457875.05
#Sta/Elev= 30
  4434.1  223.92  4660.3   220.5  4872.5  218.86  4927.3  217.21  4957.3  215.93
  4971.5  213.65  4985.6  212.77  4996.2  211.04  5002.4  211.04  5006.2   208.1
  5006.7   207.6  5012.4   207.6  5012.9   208.1  5021.1  208.43  5031.8  215.13
  5039.8  216.79  5063.8  216.94  5085.2   218.1  5098.9  218.19  5155.5  219.31
  5533.7  219.01  5620.5  220.61  5673.5   221.7  5698.4  221.68  5704.6  222.21
  5723.3  222.74  5728.7  222.45  5758.9  222.82  5779.1  223.58  5854.1  225.81
#Mann= 7 ,-1 , 0
  4434.1     .05       0  4927.3      .1       0  5006.2     .05       0
  5012.9      .1       0  5098.9     .05       0  5620.5     .07       0
  5779.1     .12       0
Bank Sta=5006.2,5012.9
XS Rating Curve= 0 ,0
Exp/Cntr=0.3,0.1

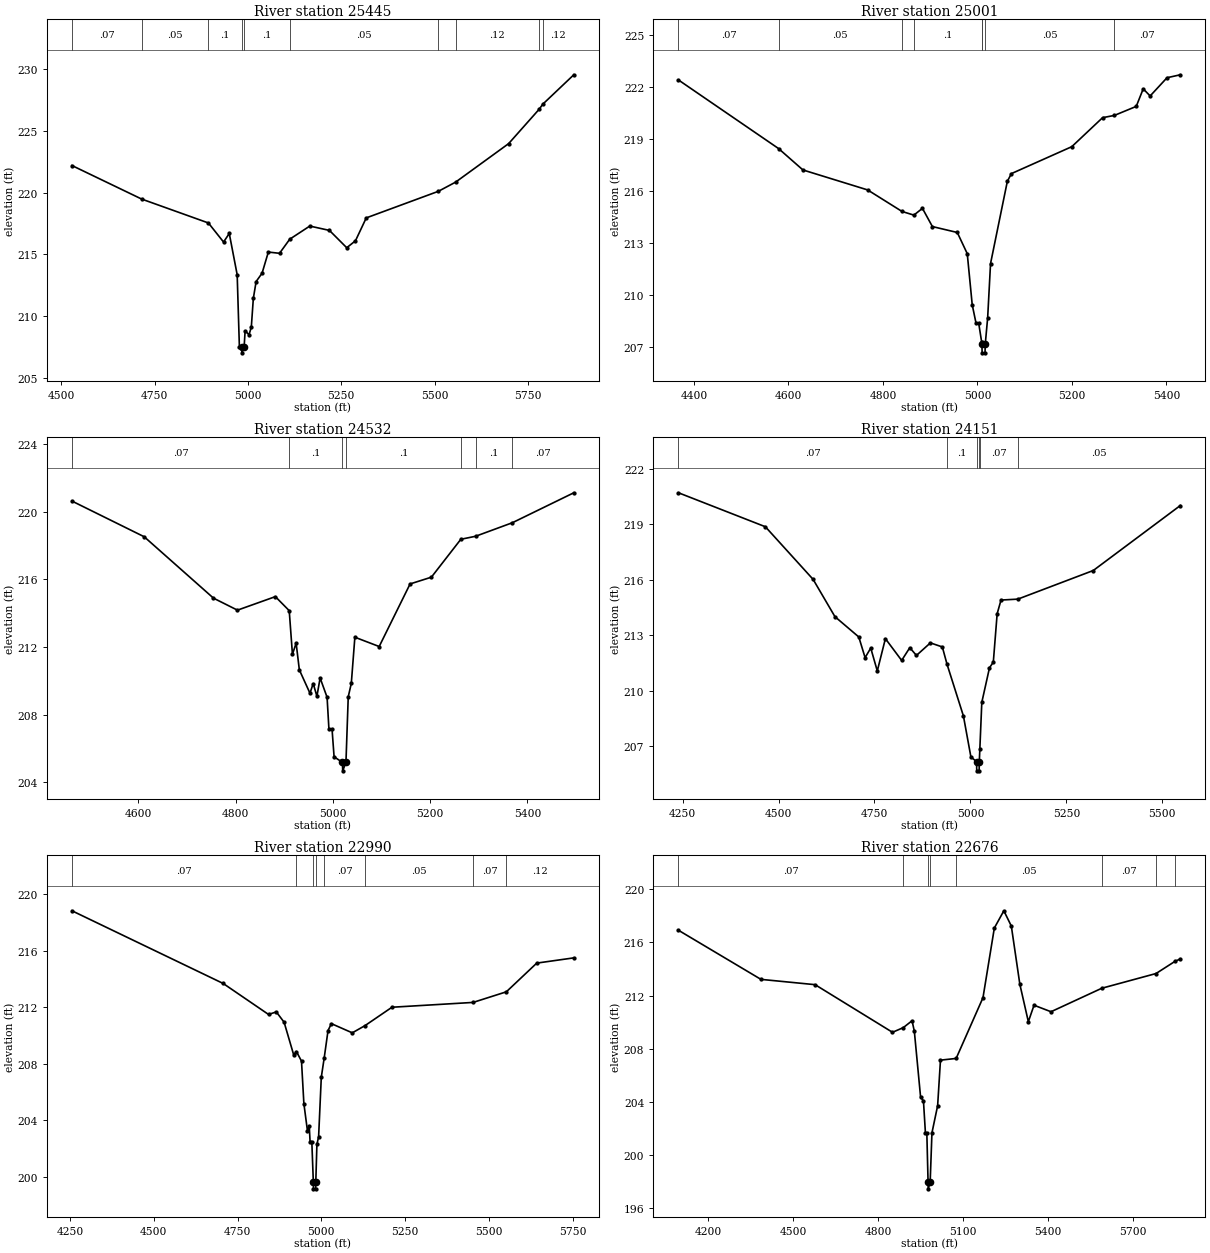
Type RM Length L Ch R = 1 ,25445   ,444,444,444
BEGIN DESCRIPTION:
FARMER CREEK 46.0
END DESCRIPTION:
XS GIS Cut Line= 3
      2487675.01     13458875.02        2487425.       13458475.
      2487075.01     13457675.03
#Sta/Elev= 30
  4528.3  222.18  4715.2  219.47    4894  217.54  4934.6     216  4949.9  216.69
  4971.1  213.36    4977  207.56  4983.1  207.55  4983.6  207.05  4989.8  207.55
  4992.4  208.83  5002.8  208.51    5009  209.13  5014.4  211.45  5021.9  212.81
  5037.8  213.48  5054.6  215.19  5084.6  215.09    5112  216.23  5165.7  217.29
  5218.3  216.94  5264.7  215.54  5288.1   216.1    5317  217.95  5510.5   220.1
  5556.5  220.84  5698.6  223.95  5780.5  226.73  5790.3  227.14  5873.2  229.51
#Mann= 10 ,-1 , 0
  4528.3     .07       0  4715.2     .05       0    4894      .1       0
  4983.1     .05       0  4989.8      .1       0    5112     .05       0
  5510.5     .07       0  5556.5     .12       0  5780.5     .07       0
  5790.3     .12       0
Bank Sta=4983.1,4989.8
XS Rating Curve= 0 ,0
Exp/Cntr=0.3,0.1

Type RM Length L Ch R = 1 ,25001   ,469,469,469
BEGIN DESCRIPTION:
FARMER CREEK 45.0
END DESCRIPTION:
XS GIS Cut Line= 3
      2487874.99     13458724.98        2487675.       13458125.
      2487425.03     13457775.04
#Sta/Elev= 30
  4367.1   222.4  4579.1  218.45  4630.6  217.22  4767.6  216.07  4840.4  214.83
  4865.5  214.62  4883.6  215.01  4904.7  213.96  4957.4  213.62  4978.5   212.4
    4989  209.46  4996.9  208.42  5002.6  208.42  5009.1  207.29  5009.5  207.19
    5010  206.69  5016.1  206.69  5016.6  207.19  5021.7  208.71  5027.8  211.83
  5063.4  216.57    5072  217.01  5199.8  218.56    5265  220.23    5290  220.36
  5336.3  220.88    5351  221.89  5365.7  221.48  5401.4  222.53  5429.6   222.7
#Mann= 8 ,-1 , 0
  4367.1     .07       0  4579.1     .05       0  4840.4     .07       0
  4865.5      .1       0  5009.1     .05       0  5009.5     .05       0
  5016.6     .05       0    5290     .07       0
Bank Sta=5009.5,5016.6
XS Rating Curve= 0 ,0
Exp/Cntr=0.3,0.1

Type RM Length L Ch R = 1 ,24532   ,381,381,381
BEGIN DESCRIPTION:
FARMER CREEK 44.0
END DESCRIPTION:
XS GIS Cut Line= 3
      2488424.98     13458524.98        2488075.       13458125.
      2487774.99     13457724.98
#Sta/Elev= 30
  4463.8  220.62  4612.3  218.51  4754.7  214.88    4804  214.17  4881.9  214.97
  4910.4  214.14    4917  211.56  4924.6  212.22  4931.2  210.64    4953  209.26
  4959.7  209.83  4967.3  209.08  4973.9  210.16  4988.2  209.02    4992  207.14
  4998.4  207.14  5002.6   205.5  5019.8  205.17  5020.3  204.67    5027  205.17
  5031.7  209.05    5038  209.84  5045.3  212.57  5095.3  212.02  5158.8  215.72
  5202.6  216.12  5263.1  218.36  5293.6  218.54  5369.1  219.34  5495.3  221.11
#Mann= 7 ,-1 , 0
  4463.8     .07       0  4910.4      .1       0  5019.8     .05       0
    5027      .1       0  5263.1     .07       0  5293.6      .1       0
  5369.1     .07       0
Bank Sta=5019.8,5027
XS Rating Curve= 0 ,0
Exp/Cntr=0.3,0.1

Type RM Length L Ch R = 1 ,24151   ,1161,1161,1161
BEGIN DESCRIPTION:
Mapping XS 91fe243c
END DESCRIPTION:
XS GIS Cut Line= 3
      2488624.22      13458644.4      2488381.15     13457945.58
      2488346.52     13457378.53
#Sta/Elev= 30
  4239.1  220.71  4465.6  218.87    4590  216.02  4646.9     214  4709.1   212.9
  4725.5  211.78  4740.2   212.3  4757.3  211.06  4778.4  212.81  4820.8  211.63
    4842  212.32  4859.3   211.9  4895.7  212.58  4926.8  212.36  4939.1  211.42
  4981.8  208.62  5001.3   206.4    5016  206.15  5016.5  205.65  5022.7  205.65
  5023.2  206.15  5024.6  206.84  5029.7  209.36  5049.7  211.23  5059.7  211.54
  5069.7  214.16  5079.8   214.9  5123.6  214.95  5320.2   216.5  5547.1  220.02
#Mann= 6 ,-1 , 0
  4239.1     .07       0  4939.1      .1       0    5016     .05       0
  5023.2      .1       0  5024.6     .07       0  5123.6     .05       0
Bank Sta=5016,5023.2
XS Rating Curve= 0 ,0
Exp/Cntr=0.3,0.1

Type RM Length L Ch R = 1 ,22990   ,314,314,314
BEGIN DESCRIPTION:
Mapping XS dea388cf
END DESCRIPTION:
XS GIS Cut Line= 3
      2488841.22     13458757.22      2489132.02     13458106.17
       2489053.9     13457324.91
#Sta/Elev= 30
  4255.6  218.82  4707.1  213.68  4842.5  211.49  4865.7  211.67    4889  210.94
  4917.6  208.63  4925.7  208.87  4940.9  208.19    4948  205.19  4958.6  203.27
  4964.1  203.59  4966.5   202.5  4971.7   202.5  4976.2  199.66  4976.7  199.16
  4983.1  199.16  4983.6  199.66  4986.9   202.3    4992  202.85    5000  207.05
  5008.7  208.42  5020.1  210.35  5030.1  210.84  5092.5  210.19  5130.5   210.7
    5211     212    5453  212.34  5552.4  213.09  5643.2  215.12  5753.8  215.49
#Mann= 8 ,-1 , 0
  4255.6     .07       0  4925.7      .1       0  4976.2     .05       0
  4983.6      .1       0  5008.7     .07       0  5130.5     .05       0
    5453     .07       0  5552.4     .12       0
Bank Sta=4976.2,4983.6
XS Rating Curve= 0 ,0
Exp/Cntr=0.3,0.1

Type RM Length L Ch R = 1 ,22676   ,361,361,361
BEGIN DESCRIPTION:
Mapping XS afdd4fb2
END DESCRIPTION:
XS GIS Cut Line= 3
      2489340.36     13458974.19      2489444.52     13458106.17
      2489396.84     13457208.88
#Sta/Elev= 30
  4094.7  216.92    4386  213.22  4577.3  212.82  4850.7  209.23  4888.7  209.58
  4919.8   210.1  4927.9  209.31    4950  204.34  4960.1  204.06    4967  201.66
    4972  201.66  4976.4  197.93  4976.9  197.43  4983.8  197.93  4990.1  201.65
  5010.2   203.7  5020.2  207.13  5075.6  207.26  5170.4  211.84  5210.5  217.09
  5244.1  218.39  5270.5  217.24  5300.6  212.85  5330.6  210.03  5350.7  211.27
  5410.7  210.78    5590  212.55  5781.7  213.66  5848.8  214.58  5867.5  214.76
#Mann= 8 ,-1 , 0
  4094.7     .07       0  4888.7      .1       0  4976.4     .05       0
  4983.8      .1       0  5075.6     .05       0    5590     .07       0
  5781.7     .12       0  5848.8     .07       0
Bank Sta=4976.4,4983.8
XS Rating Curve= 0 ,0
Exp/Cntr=0.3,0.1