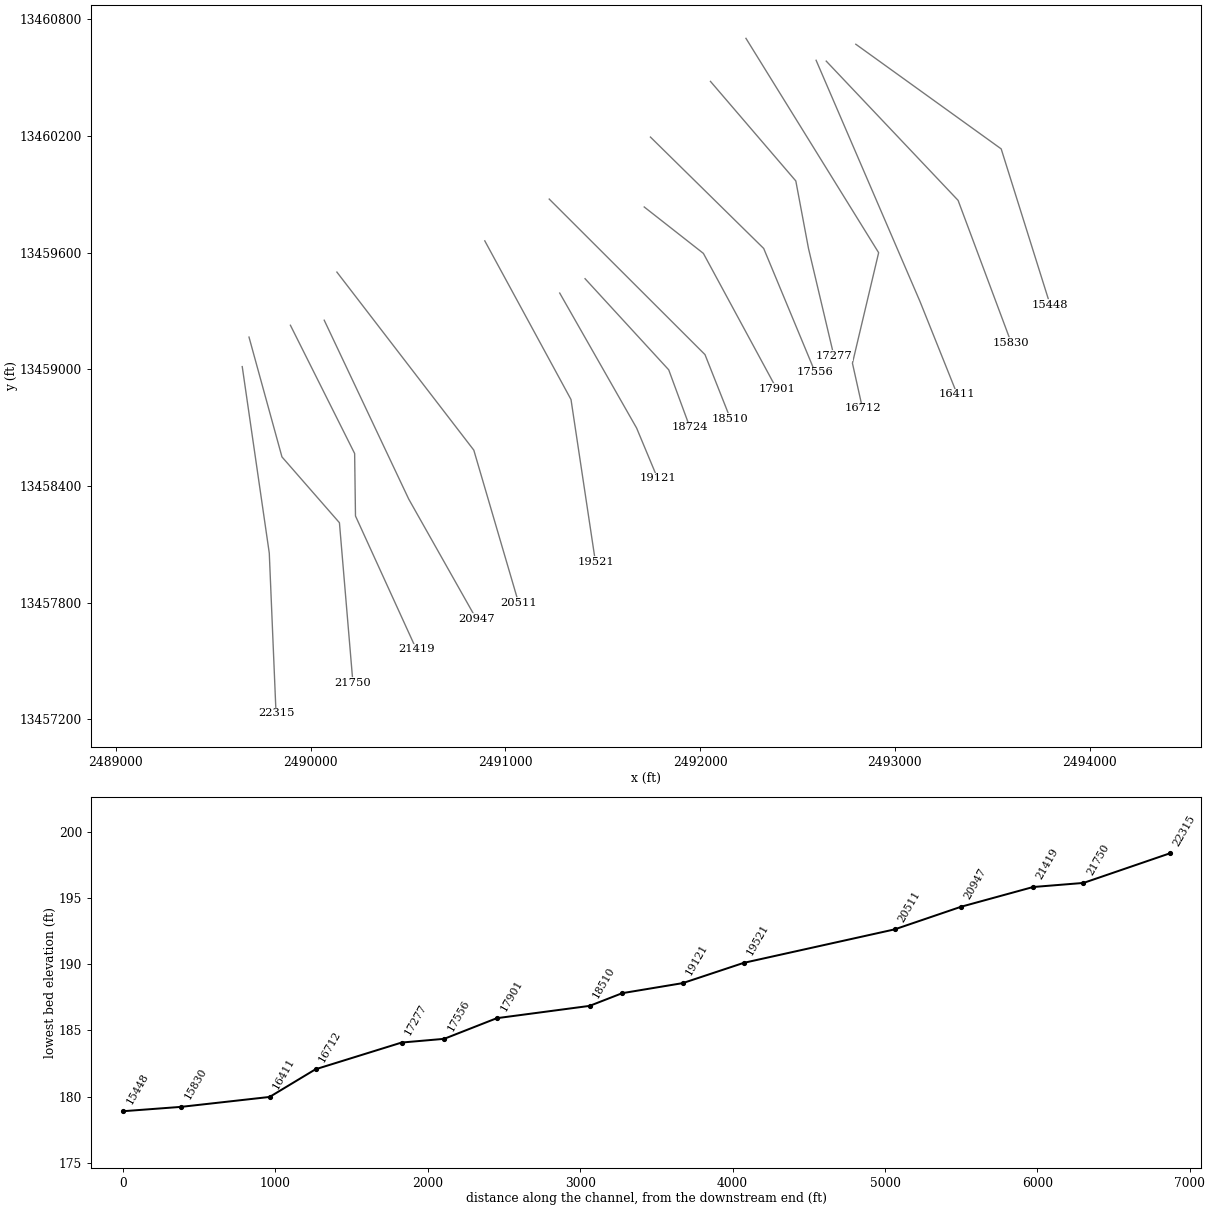
HEC-RAS study FARMER CREEK.prj: FARMER CREEK Base Level Engineering

--- FARMER CREEK.g01 (geometry) --- (continued)

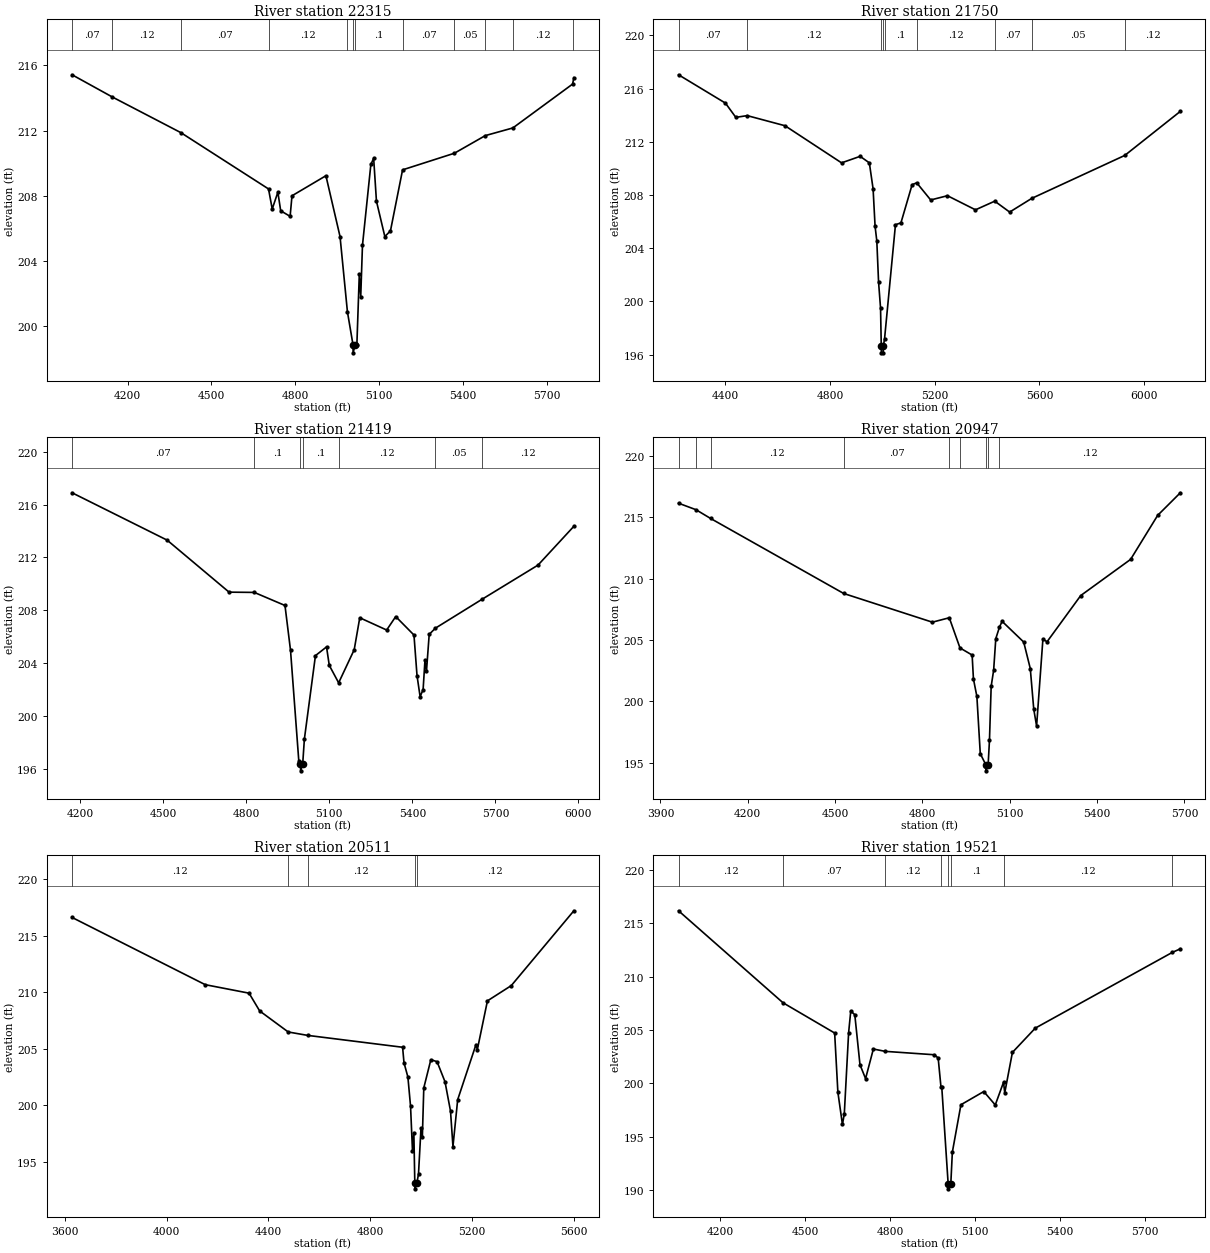
Type RM Length L Ch R = 1 ,22315   ,565,565,565
BEGIN DESCRIPTION:
Mapping XS 006fe48e
END DESCRIPTION:
XS GIS Cut Line= 3
      2489648.51     13459013.31       2489787.4     13458054.09
      2489822.11     13457229.74
#Sta/Elev= 30
  4001.5  215.42  4145.2  214.06  4390.7  211.87    4704  208.42  4717.2  207.19
  4737.4  208.22  4747.5  207.08  4781.2  206.74  4787.9     208  4909.2  209.23
  4959.7   205.5  4986.1  200.89    5006  198.87  5006.5  198.37  5013.7  198.87
  5019.9  198.87  5028.6  203.19  5033.7  201.82  5039.9  204.96  5069.9  209.92
  5079.9   210.3  5089.9  207.67  5119.9   205.5    5140  205.85  5183.3  209.59
  5368.7  210.61  5479.1  211.69  5577.7  212.16  5791.3  214.85  5795.8  215.24
#Mann= 12 ,-1 , 0
  4001.5     .07       0  4145.2     .12       0  4390.7     .07       0
    4704     .12       0  4986.1      .1       0    5006     .05       0
  5013.7      .1       0  5183.3     .07       0  5368.7     .05       0
  5479.1     .07       0  5577.7     .12       0  5791.3     .07       0
Bank Sta=5006,5013.7
XS Rating Curve= 0 ,0
Exp/Cntr=0.3,0.1

Type RM Length L Ch R = 1 ,21750   ,331,331,331
BEGIN DESCRIPTION:
Mapping XS aa6dc363
END DESCRIPTION:
XS GIS Cut Line= 4
      2489683.24     13459165.17      2489852.51     13458548.88
      2490147.65     13458210.34      2490217.09      13457385.7
#Sta/Elev= 30
  4222.1  217.04  4401.2  214.91  4440.8  213.84  4484.3  213.97  4628.6  213.21
  4844.5  210.42  4915.5  210.91  4950.6  210.42  4964.9  208.47  4972.5  205.65
  4979.1  204.55  4985.8  201.46  4993.4   199.5  4996.1  196.64  4996.6  196.14
  5003.5  196.14    5004  196.64  5008.6  197.18  5050.3  205.77  5071.2  205.91
  5113.9  208.78  5131.5  208.92  5184.8  207.63  5248.8  207.95  5355.8  206.89
  5429.4  207.54  5486.3  206.72  5570.7  207.75  5925.9  210.98  6137.9  214.29
#Mann= 9 ,-1 , 0
  4222.1     .07       0  4484.3     .12       0  4996.1     .05       0
    5004     .12       0  5008.6      .1       0  5131.5     .12       0
  5429.4     .07       0  5570.7     .05       0  5925.9     .12       0
Bank Sta=4996.1,5004
XS Rating Curve= 0 ,0
Exp/Cntr=0.3,0.1

Type RM Length L Ch R = 1 ,21419   ,472,472,472
BEGIN DESCRIPTION:
Mapping XS 33a08332
END DESCRIPTION:
XS GIS Cut Line= 4
      2489895.89       13459226.      2490225.77     13458566.24
      2490230.11     13458245.06      2490542.47     13457559.61
#Sta/Elev= 30
  4171.2   216.9  4514.6  213.31  4738.2  209.37  4829.3  209.35  4940.1  208.36
  4960.1  204.96  4990.1  196.55  4996.1  196.33  4996.6  195.83    5004  196.33
  5010.1  198.23  5050.1  204.56  5090.1  205.22  5100.1  203.82  5133.9   202.5
  5190.1  205.01  5210.1  207.43  5307.3   206.5    5340  207.52  5405.9  206.12
  5416.9  203.05  5428.1  201.45  5438.9  201.99  5445.6   204.2  5451.1  203.39
  5460.9  206.17  5483.3  206.64  5652.5  208.84  5853.9  211.42  5983.3  214.36
#Mann= 7 ,-1 , 0
  4171.2     .07       0  4829.3      .1       0  4996.1     .05       0
    5004      .1       0  5133.9     .12       0  5483.3     .05       0
  5652.5     .12       0
Bank Sta=4996.1,5004
XS Rating Curve= 0 ,0
Exp/Cntr=0.3,0.1

Type RM Length L Ch R = 1 ,20947   ,436,436,436
BEGIN DESCRIPTION:
Mapping XS f21425ff
END DESCRIPTION:
XS GIS Cut Line= 3
      2490069.52       13459252.      2490503.55     13458331.86
       2490850.4     13457716.21
#Sta/Elev= 30
    3962  216.16  4021.9  215.63  4071.9  214.92  4529.4   208.8    4834  206.46
  4892.2  206.82    4929  204.36  4970.7  203.78  4975.2  201.83    4987  200.41
  4998.7  195.74  5017.6  194.84  5018.1  194.34  5025.7  194.84  5030.3  196.84
  5036.1  201.23  5044.6  202.54    5052  205.12  5064.7  206.06  5073.7  206.53
  5147.9  204.84  5170.5  202.68  5182.4  199.37  5192.2  197.99  5213.8  205.06
  5228.3  204.87  5343.8  208.63  5515.2  211.58  5608.2  215.17    5686  217.01
#Mann= 9 ,-1 , 0
    3962     .12       0  4021.9     .07       0  4071.9     .12       0
  4529.4     .07       0  4892.2     .12       0    4929     .07       0
  5017.6     .05       0  5025.7     .07       0  5064.7     .12       0
Bank Sta=5017.6,5025.7
XS Rating Curve= 0 ,0
Exp/Cntr=0.3,0.1

Type RM Length L Ch R = 1 ,20511   ,990,990,990
BEGIN DESCRIPTION:
Mapping XS f77c2268
END DESCRIPTION:
XS GIS Cut Line= 3
       2490134.6     13459499.44      2490837.75      13458583.6
       2491067.5     13457798.98
#Sta/Elev= 30
    3628  216.61  4151.4  210.67  4323.6  209.92  4365.3  208.35  4477.6  206.49
  4553.6  206.19  4927.1  205.14  4932.6  203.77  4947.9  202.51  4958.3  199.94
    4966  195.96  4971.3   197.6  4975.1  193.13  4975.6  192.63  4983.2  193.13
  4989.6  193.95  4999.5  198.03  5004.7  197.19  5010.4  201.55  5038.1  204.04
  5062.5  203.87  5093.8  202.09  5115.4   199.5    5125  196.37  5143.6  200.51
  5215.6  205.38  5220.8  204.93  5260.5  209.24  5354.3  210.59  5600.2   217.2
#Mann= 5 ,-1 , 0
    3628     .12       0  4477.6     .07       0  4553.6     .12       0
  4975.1     .05       0  4983.2     .12       0
Bank Sta=4975.1,4983.2
XS Rating Curve= 0 ,0
Exp/Cntr=0.3,0.1

Type RM Length L Ch R = 1 ,19521   ,400,400,400
BEGIN DESCRIPTION:
Mapping XS f66aa5ea
END DESCRIPTION:
XS GIS Cut Line= 3
      2490894.17     13459659.99      2491336.88     13458844.02
      2491462.48     13458008.14
#Sta/Elev= 30
  4052.9  216.19  4422.1  207.56  4604.7  204.72  4616.1  199.17  4632.2  196.14
  4638.8  197.13  4654.1  204.76  4661.6  206.78  4675.9  206.44  4694.2  201.75
    4714  200.44  4741.5  203.22  4783.2     203  4957.4  202.68  4970.6  202.37
  4980.5  199.65  4983.3  199.65  5005.8   190.6  5006.3   190.1  5015.3   190.6
  5020.7  193.54    5051  197.99  5131.8  199.23  5172.4  197.97  5201.6   200.1
  5205.9  199.11    5233   202.9  5313.9  205.18  5797.8  212.28  5826.5  212.62
#Mann= 8 ,-1 , 0
  4052.9     .12       0  4422.1     .07       0  4783.2     .12       0
  4980.5      .1       0  5005.8     .05       0  5015.3      .1       0
  5201.6     .12       0  5797.8     .07       0
Bank Sta=5005.8,5015.3
XS Rating Curve= 0 ,0
Exp/Cntr=0.3,0.1

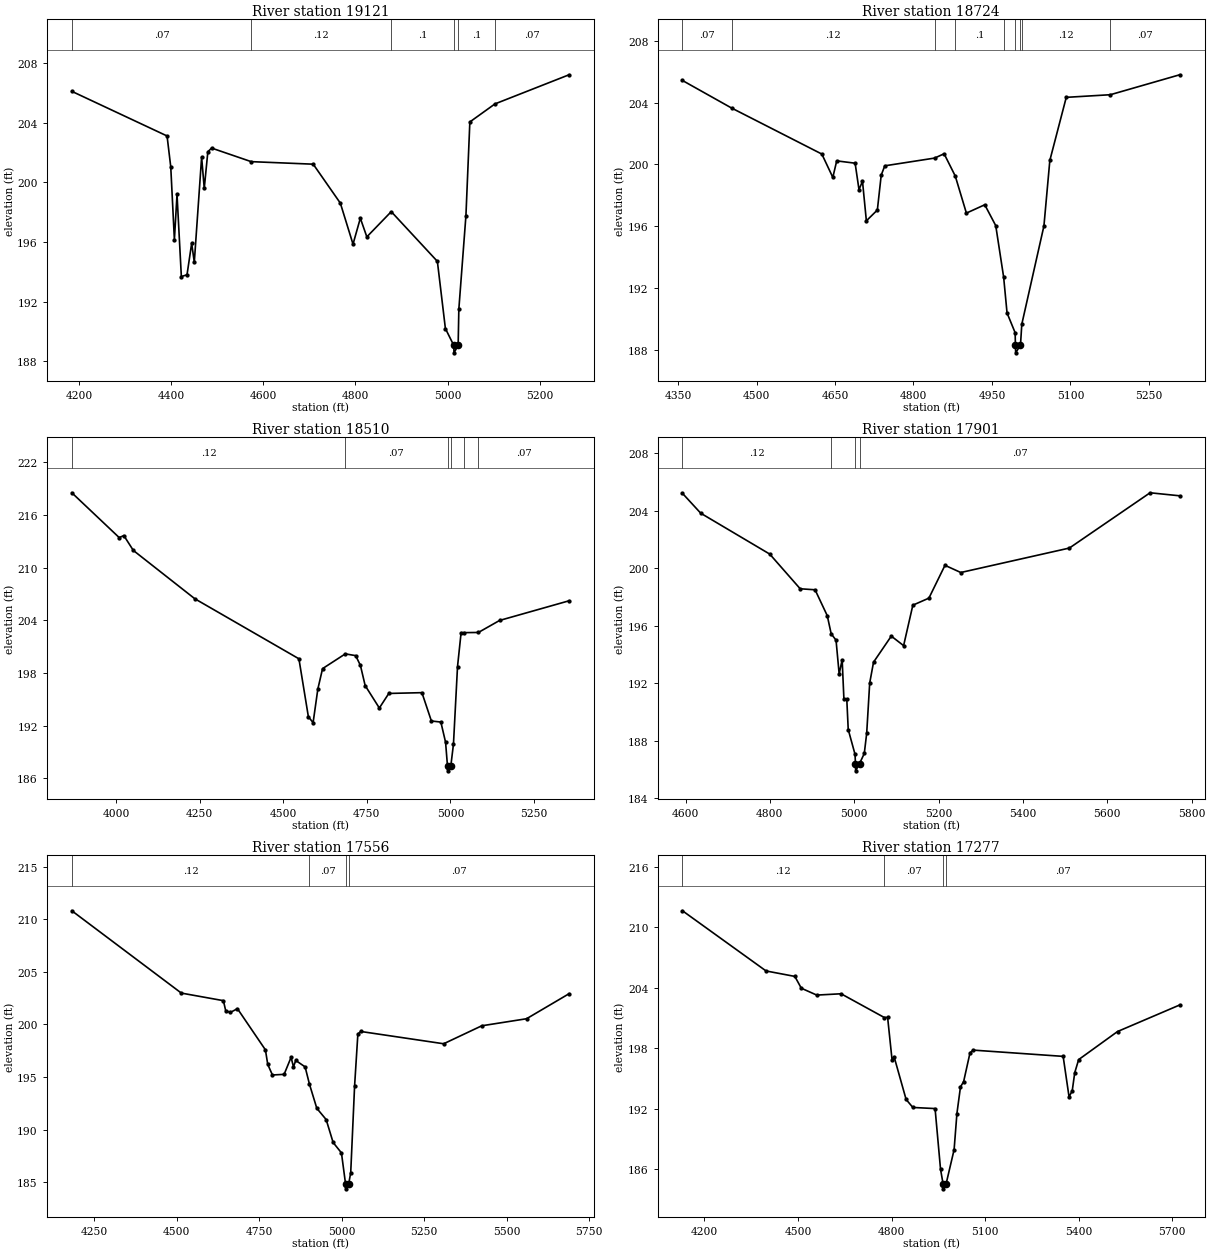
Type RM Length L Ch R = 1 ,19121   ,397,397,397
BEGIN DESCRIPTION:
Mapping XS 7c97361b
END DESCRIPTION:
XS GIS Cut Line= 3
      2491278.88     13459391.59      2491673.83     13458697.18
      2491781.64     13458438.41
#Sta/Elev= 30
  4184.5  206.09  4391.2   203.1  4399.2  201.03  4407.1  196.15  4412.8  199.18
  4422.2  193.68  4434.5   193.8  4444.6  195.91  4450.3  194.64  4466.2  201.68
  4471.9  199.59  4479.7  202.04  4487.8  202.29  4573.8  201.38  4708.4  201.21
  4767.3   198.6  4794.8  195.85  4810.7  197.59  4824.8  196.34  4877.8  198.03
  4977.9   194.7  4995.3   190.2  5013.5  189.07    5014  188.57    5023  189.07
  5024.5   191.5  5039.9  197.77  5048.4  204.04    5103  205.25  5263.7   207.2
#Mann= 6 ,-1 , 0
  4184.5     .07       0  4573.8     .12       0  4877.8      .1       0
  5013.5     .05       0    5023      .1       0    5103     .07       0
Bank Sta=5013.5,5023
XS Rating Curve= 0 ,0
Exp/Cntr=0.3,0.1

Type RM Length L Ch R = 1 ,18724   ,214,214,214
BEGIN DESCRIPTION:
Mapping XS c78d0ae1
END DESCRIPTION:
XS GIS Cut Line= 3
      2491409.06     13459465.42      2491838.76     13458996.65
      2491947.28     13458701.48
#Sta/Elev= 30
  4358.5  205.43  4452.3  203.65  4624.9  200.67  4645.9  199.16  4653.3  200.23
  4688.5  200.08  4695.9  198.37  4702.6  198.91    4710  196.35    4731  197.05
  4738.4  199.31  4745.2  199.91  4840.4  200.41  4858.6  200.69  4879.9  199.25
  4901.2  196.85  4936.3  197.39  4957.3  196.04  4972.4  192.71  4978.9  190.39
  4994.4  189.11  4994.9  188.31  4995.4  187.81  5004.6  188.31  5007.1  189.66
  5049.4  196.02  5060.7  200.26  5092.1  204.34  5176.4  204.51  5308.9   205.8
#Mann= 9 ,-1 , 0
  4358.5     .07       0  4452.3     .12       0  4840.4     .07       0
  4879.9      .1       0  4972.4     .07       0  4994.9     .05       0
  5004.6     .07       0  5007.1     .12       0  5176.4     .07       0
Bank Sta=4994.9,5004.6
XS Rating Curve= 0 ,0
Exp/Cntr=0.3,0.1

Type RM Length L Ch R = 1 ,18510   ,609,609,609
BEGIN DESCRIPTION:
FARMER CREEK 33.0
END DESCRIPTION:
XS GIS Cut Line= 3
      2491225.01     13459874.99        2492025.       13459075.
      2492155.59     13458744.95
#Sta/Elev= 30
  3868.1  218.54  4009.5  213.44  4023.6  213.66  4051.9  211.97  4235.8  206.46
  4546.9  199.62  4575.2  193.01  4589.3  192.34  4603.5  196.18  4617.6   198.5
  4685.6  200.18  4716.6  199.98  4730.8  198.86  4744.9  196.57  4787.3  194.01
  4815.6  195.67  4914.6  195.76  4942.9  192.53  4971.2  192.41  4985.3  190.11
  4991.1  187.35  4991.6  186.85  5000.8  187.35  5008.9   189.9    5021  198.73
  5031.7  202.59  5039.8   202.6  5083.4  202.62  5146.8  203.99  5354.4  206.23
#Mann= 6 ,-1 , 0
  3868.1     .12       0  4685.6     .07       0  4991.1     .05       0
  5000.8     .07       0  5039.8     .12       0  5083.4     .07       0
Bank Sta=4991.1,5000.8
XS Rating Curve= 0 ,0
Exp/Cntr=0.3,0.1

Type RM Length L Ch R = 1 ,17901   ,345,345,345
BEGIN DESCRIPTION:
Mapping XS 19ad9d34
END DESCRIPTION:
XS GIS Cut Line= 3
      2491712.88     13459834.33      2492016.71     13459595.61
      2492393.47     13458898.39
#Sta/Elev= 30
  4592.8   205.2  4636.1  203.82  4799.7  200.98  4871.9  198.57  4907.2   198.5
  4936.1   196.7  4945.4  195.44  4956.9     195  4964.3  192.65  4971.4  193.64
  4975.6  190.89  4982.4  190.89  4985.8  188.79    5002  187.06  5002.9  186.42
  5003.4  185.92  5012.6  186.42  5023.9  187.13  5029.6  188.54  5036.7  192.02
  5045.8  193.47  5087.9  195.28  5117.1  194.62    5139  197.43  5177.1  197.92
  5215.2   200.2  5252.7   199.7  5510.2   201.4  5701.5  205.24  5771.7  205.03
#Mann= 4 ,-1 , 0
  4592.8     .12       0  4945.4     .07       0  5002.9     .05       0
  5012.6     .07       0
Bank Sta=5002.9,5012.6
XS Rating Curve= 0 ,0
Exp/Cntr=0.3,0.1

Type RM Length L Ch R = 1 ,17556   ,279,279,279
BEGIN DESCRIPTION:
Mapping XS bf4e8485
END DESCRIPTION:
XS GIS Cut Line= 3
      2491744.87     13460193.84      2492326.47     13459620.93
      2492590.63     13458984.34
#Sta/Elev= 30
  4182.9  210.81  4514.5  202.98  4641.8  202.26  4648.8  201.31    4663  201.14
  4684.3   201.5  4769.1  197.58  4776.1   196.2  4790.3  195.19  4825.7  195.25
  4846.8  196.87    4854  195.97    4861  196.57  4889.3  195.96  4902.4  194.32
  4924.7  192.02    4953  190.95  4974.1  188.77  4999.3  187.78  5011.6  184.86
  5012.1  184.36  5021.4  184.86  5027.4  185.91  5039.1  194.14    5049  199.07
  5057.6  199.33  5308.8  198.16  5424.2  199.87  5559.8  200.54  5688.5  202.92
#Mann= 4 ,-1 , 0
  4182.9     .12       0  4902.4     .07       0  5011.6     .05       0
  5021.4     .07       0
Bank Sta=5011.6,5021.4
XS Rating Curve= 0 ,0
Exp/Cntr=0.3,0.1

Type RM Length L Ch R = 1 ,17277   ,565,565,565
BEGIN DESCRIPTION:
Mapping XS 0b1931e6
END DESCRIPTION:
XS GIS Cut Line= 4
      2492053.06     13460480.27       2492491.4     13459968.15
       2492556.5     13459620.93      2492686.67     13459069.87
#Sta/Elev= 30
  4129.9  211.62  4397.8  205.66    4490  205.12  4510.8  203.95  4560.2  203.27
  4638.2   203.4  4776.7  201.05  4787.4  201.06  4801.7  196.83  4808.1  197.17
  4846.7  192.93  4868.3  192.14  4939.5  192.03    4957  186.02  4965.1  184.58
  4965.6  184.08  4974.9  184.58  5000.5  187.96  5009.5  191.54  5020.9  194.17
    5031   194.7  5051.4  197.54  5061.6  197.82    5350   197.2  5368.9  193.19
  5379.1  193.79  5387.1  195.58  5399.7  196.88  5524.3  199.66  5723.5  202.29
#Mann= 4 ,-1 , 0
  4129.9     .12       0  4776.7     .07       0  4965.1     .05       0
  4974.9     .07       0
Bank Sta=4965.1,4974.9
XS Rating Curve= 0 ,0
Exp/Cntr=0.3,0.1

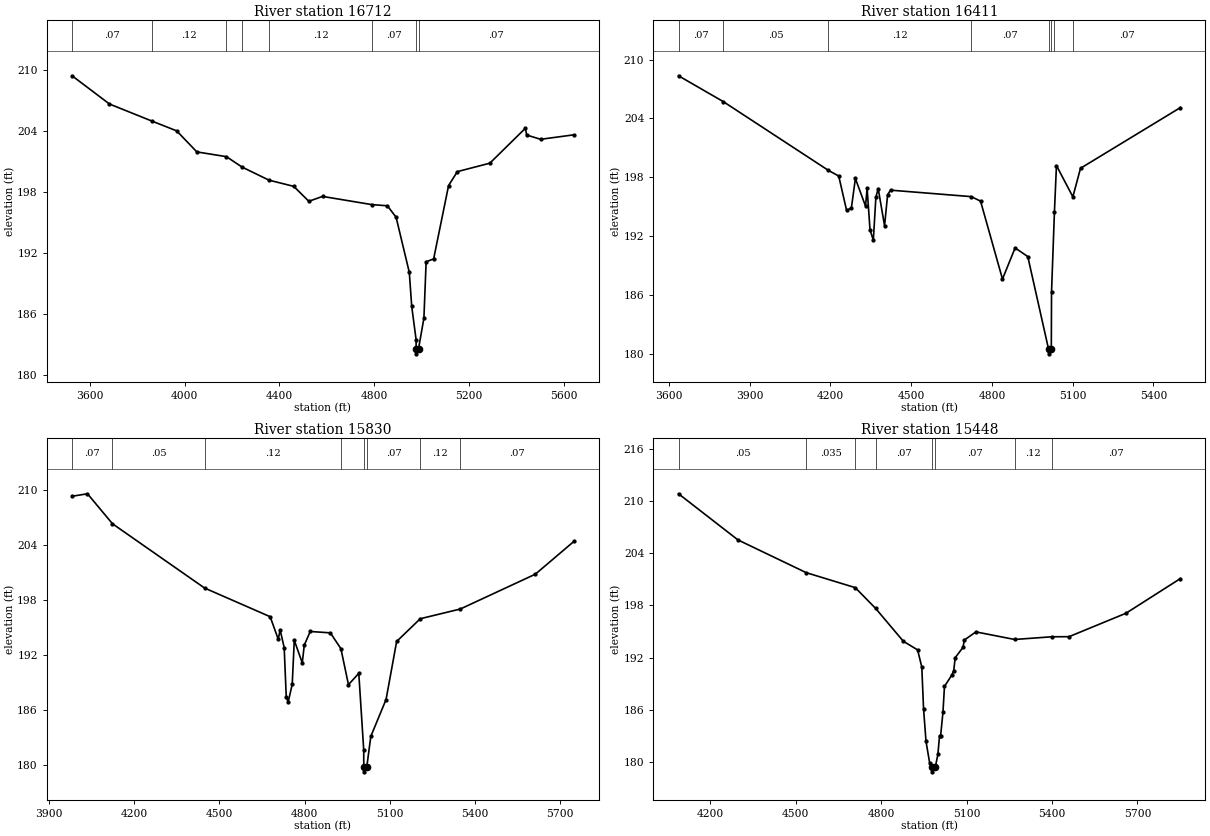
Type RM Length L Ch R = 1 ,16712   ,301,301,301
BEGIN DESCRIPTION:
Mapping XS d348834c
END DESCRIPTION:
XS GIS Cut Line= 4
      2492235.29      13460701.7      2492916.74     13459599.23
       2492782.2     13459030.65      2492833.86     13458798.18
#Sta/Elev= 30
  3524.7  209.42  3682.7  206.64  3862.1  204.96  3966.4     204  4051.4  201.93
  4176.6  201.46  4242.1  200.44    4356  199.15  4460.5  198.54  4524.3  197.07
  4582.2  197.55  4791.2  196.74  4855.9  196.63  4892.7   195.5  4948.4  190.08
  4958.7  186.72  4977.2  183.45  4977.3  182.56  4977.8  182.06  4987.4  182.56
  5010.1  185.57  5019.5  191.12  5051.2   191.4  5114.3  198.62  5151.4  199.99
  5288.5  200.82  5438.7  204.26  5443.9  203.59    5503  203.17  5643.2  203.61
#Mann= 8 ,-1 , 0
  3524.7     .07       0  3862.1     .12       0  4176.6     .05       0
  4242.1     .07       0    4356     .12       0  4791.2     .07       0
  4977.3     .05       0  4987.4     .07       0
Bank Sta=4977.3,4987.4
XS Rating Curve= 0 ,0
Exp/Cntr=0.3,0.1

Type RM Length L Ch R = 1 ,16411   ,581,581,581
BEGIN DESCRIPTION:
Mapping XS a41684a7
END DESCRIPTION:
XS GIS Cut Line= 3
      2492595.55     13460588.84      2493129.42     13459347.49
      2493320.21     13458870.51
#Sta/Elev= 30
  3635.4  208.34  3802.5  205.69  4191.7   198.7  4230.8  198.11  4260.1   194.6
  4277.9  194.86  4292.7  197.86  4330.4  195.04  4336.3  196.84  4347.1  192.62
  4359.4  191.56  4368.9  195.96  4377.5  196.83  4401.1  193.04  4412.5  196.21
  4423.3  196.67  4723.4  196.01  4757.9  195.55  4839.4   187.6  4886.4  190.78
  4933.5  189.89  5010.5  180.47    5011  179.97  5020.9  180.47  5021.7  186.27
  5032.5  194.46    5040  199.18    5101  195.99  5129.4   198.9  5500.4  205.09
#Mann= 8 ,-1 , 0
  3635.4     .07       0  3802.5     .05       0  4191.7     .12       0
  4723.4     .07       0  5010.5     .05       0  5020.9     .07       0
  5032.5     .12       0    5101     .07       0
Bank Sta=5010.5,5020.9
XS Rating Curve= 0 ,0
Exp/Cntr=0.3,0.1

Type RM Length L Ch R = 1 ,15830   ,382,382,382
BEGIN DESCRIPTION:
Mapping XS 83eee32b
END DESCRIPTION:
XS GIS Cut Line= 3
      2492647.67     13460584.45      2493324.73     13459868.32
      2493598.16     13459134.85
#Sta/Elev= 30
  3980.6  209.28  4034.9  209.55    4123  206.28  4447.5  199.27  4678.7  196.14
  4707.1  193.69  4713.9  194.69  4728.1  192.77  4735.4  187.36  4742.3  186.84
  4756.4  188.77  4763.7  193.57  4791.8   191.1  4798.9  193.04  4819.9  194.53
  4890.7  194.38  4927.9  192.66  4954.6  188.73    4991  189.96  5008.4  181.59
  5008.6  179.72  5009.1  179.22    5019  179.72  5033.4  183.09  5087.1  187.11
  5124.4  193.44  5207.6  195.92  5348.7  196.98  5613.2  200.78  5748.9  204.35
#Mann= 8 ,-1 , 0
  3980.6     .07       0    4123     .05       0  4447.5     .12       0
  4927.9     .07       0  5008.6     .05       0    5019     .07       0
  5207.6     .12       0  5348.7     .07       0
Bank Sta=5008.6,5019
XS Rating Curve= 0 ,0
Exp/Cntr=0.3,0.1

Type RM Length L Ch R = 1 ,15448   ,318,318,318
BEGIN DESCRIPTION:
Mapping XS 33a455f1
END DESCRIPTION:
XS GIS Cut Line= 3
      2492799.57     13460671.26      2493546.08     13460133.08
      2493797.83      13459330.1
#Sta/Elev= 30
  4088.8  210.82  4297.5  205.52  4537.3  201.76  4709.4  200.04  4780.9  197.65
  4877.9  193.89  4928.2  192.89  4942.9  190.92  4949.1  186.11  4957.7  182.39
  4970.8  179.85  4979.5  179.39    4980  178.89    4990  179.39  4999.4  180.89
  5005.3  183.06  5009.1  183.06  5017.2  185.73  5022.5   188.7    5049  190.04
  5054.9  190.49  5060.2     192  5087.3  193.17  5092.6  194.03  5132.8  194.96
  5268.9  194.09  5399.6   194.4  5459.8  194.41  5659.7   197.1  5850.6  201.08
#Mann= 8 ,-1 , 0
  4088.8     .05       0  4537.3    .035       0  4709.4     .12       0
  4780.9     .07       0  4979.5     .05       0    4990     .07       0
  5268.9     .12       0  5399.6     .07       0
Bank Sta=4979.5,4990
XS Rating Curve= 0 ,0
Exp/Cntr=0.3,0.1