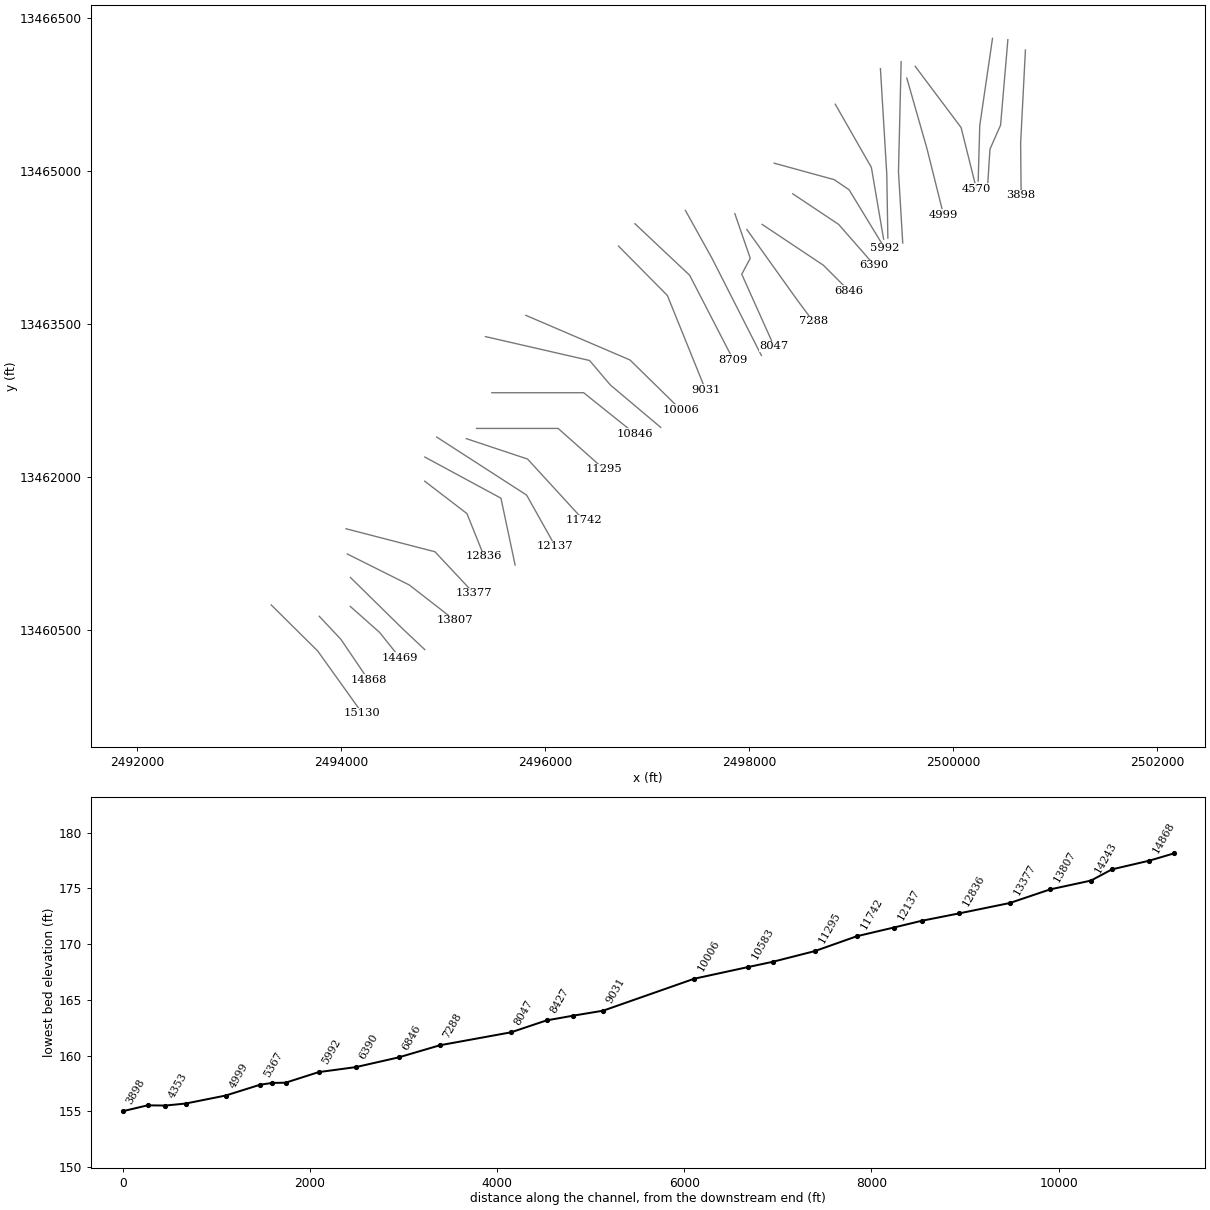
HEC-RAS study FARMER CREEK.prj: FARMER CREEK Base Level Engineering

--- FARMER CREEK.g01 (geometry) --- (continued)

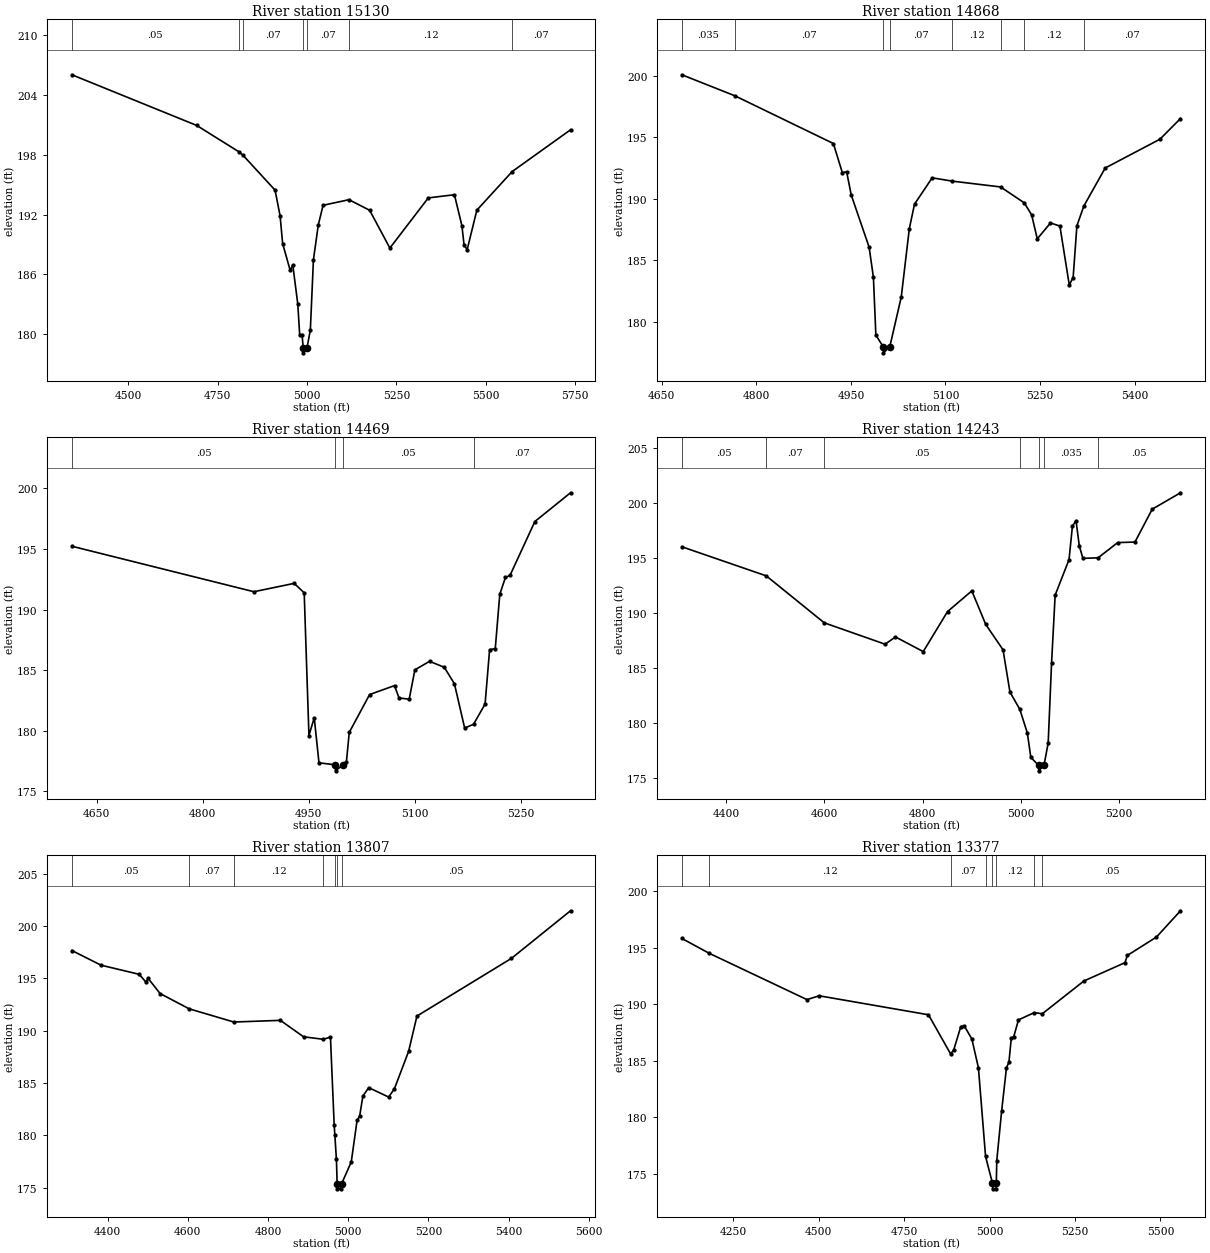
Type RM Length L Ch R = 1 ,15130   ,262,262,262
BEGIN DESCRIPTION:
Mapping XS 1a10be57
END DESCRIPTION:
XS GIS Cut Line= 3
      2493311.68     13460745.09      2493767.44     13460293.67
      2494205.83     13459681.66
#Sta/Elev= 30
  4342.3  206.02  4691.2  200.94  4809.1   198.3    4821  197.94  4910.4  194.45
  4924.5  191.87  4931.6  189.09  4952.8  186.39  4959.9  186.95    4974  183.02
  4979.3  179.91    4986  179.91  4989.2  178.63  4989.7  178.13  4999.7  178.63
  5009.1  180.43  5017.7  187.46  5031.3  190.96  5044.7  192.93  5117.1  193.49
  5174.9  192.43  5231.5  188.64  5338.9  193.67    5412  193.99  5432.9  190.88
    5439  188.94  5447.6  188.48  5474.7  192.44  5573.4  196.31  5736.6   200.5
#Mann= 7 ,-1 , 0
  4342.3     .05       0  4809.1    .035       0    4821     .07       0
  4989.2     .05       0  4999.7     .07       0  5117.1     .12       0
  5573.4     .07       0
Bank Sta=4989.2,4999.7
XS Rating Curve= 0 ,0
Exp/Cntr=0.3,0.1

Type RM Length L Ch R = 1 ,14868   ,399,399,399
BEGIN DESCRIPTION:
Mapping XS 195a1ffb
END DESCRIPTION:
XS GIS Cut Line= 3
      2493783.55     13460633.11      2493995.36     13460407.42
      2494265.57     13460009.02
#Sta/Elev= 30
  4681.9  200.09    4766  198.38  4922.2   194.5  4936.4  192.13  4943.2  192.21
  4950.5  190.32  4978.9  186.07  4985.7  183.62  4989.6  178.92  5001.2  177.98
  5001.7  177.48  5011.7  177.98  5029.9  182.03  5042.7  187.59  5050.9  189.57
  5078.9  191.71  5111.1  191.44  5187.4  190.97  5224.9  189.68  5236.7   188.7
  5245.6  186.75  5266.6  188.04  5281.5  187.79  5296.4     183  5302.5   183.6
  5308.5  187.81  5319.4  189.41  5353.4  192.51  5440.2  194.85  5472.8  196.53
#Mann= 8 ,-1 , 0
  4681.9    .035       0    4766     .07       0  5001.2     .05       0
  5011.7     .07       0  5111.1     .12       0  5187.4     .07       0
  5224.9     .12       0  5319.4     .07       0
Bank Sta=5001.2,5011.7
XS Rating Curve= 0 ,0
Exp/Cntr=0.3,0.1

Type RM Length L Ch R = 1 ,14469   ,226,226,226
BEGIN DESCRIPTION:
FARMER CREEK 24.0
END DESCRIPTION:
XS GIS Cut Line= 3
      2494086.96     13460730.39        2494375.       13460475.
      2494574.99     13460225.01
#Sta/Elev= 30
    4615  195.22  4872.4  191.47  4929.3  192.16  4943.5  191.38  4950.2  179.61
  4957.7  181.08  4964.4  177.36  4987.3   177.2  4987.8   176.7  4998.4   177.2
  5003.2  177.43  5007.2  179.87    5036  182.99  5071.2  183.73  5077.6  182.71
    5092  182.61    5100  185.03  5120.8  185.73  5141.6  185.24    5156  183.87
  5170.4  180.23    5183  180.54  5199.3  182.21  5205.7  186.69  5213.7  186.78
  5220.1  191.26  5228.1  192.65  5234.5  192.81  5269.7  197.26  5320.1  199.63
#Mann= 4 ,-1 , 0
    4615     .05       0  4987.3     .05       0  4998.4     .05       0
    5183     .07       0
Bank Sta=4987.3,4998.4
XS Rating Curve= 0 ,0
Exp/Cntr=0.3,0.1

Type RM Length L Ch R = 1 ,14243   ,436,436,436
BEGIN DESCRIPTION:
Mapping XS 3dff1af9
END DESCRIPTION:
XS GIS Cut Line= 3
      2494088.65     13461014.13      2494600.77     13460510.68
       2494817.8     13460306.68
#Sta/Elev= 30
  4309.7  196.02  4481.7  193.38  4599.8  189.12  4723.8  187.18  4744.9  187.84
  4801.5  186.51    4851  190.14  4900.5  192.02  4928.8  188.98  4964.1  186.67
  4978.2  182.84  4998.3  181.27  5013.6  179.13  5020.7  176.92  5036.4  176.19
  5036.9  175.69  5047.6  176.19  5056.1  178.22    5063  185.47  5070.3  191.63
  5098.6  194.86  5105.5  197.89  5112.8  198.39  5119.6  196.08  5126.9  194.97
  5157.8  195.02  5197.8   196.4  5232.9  196.45  5268.1  199.43  5325.7  200.92
#Mann= 7 ,-1 , 0
  4309.7     .05       0  4481.7     .07       0  4599.8     .05       0
  4998.3    .035       0  5036.4    .035       0  5047.6    .035       0
  5157.8     .05       0
Bank Sta=5036.4,5047.6
XS Rating Curve= 0 ,0
Exp/Cntr=0.3,0.1

Type RM Length L Ch R = 1 ,13807   ,430,430,430
BEGIN DESCRIPTION:
Mapping XS 80cd45f5
END DESCRIPTION:
XS GIS Cut Line= 3
      2494058.26     13461244.18      2494665.88     13460940.37
      2495111.43     13460594.31
#Sta/Elev= 30
  4311.1  197.67  4383.8  196.27  4478.9   195.4  4495.6  194.66  4501.2  195.01
  4531.1  193.56  4603.6   192.1  4715.1  190.84    4831     191  4888.8  189.43
    4938  189.19  4955.9   189.4  4965.2  181.02  4966.9  180.02  4970.8  177.71
  4972.6   175.4  4973.1   174.9  4983.4   174.9  4983.9   175.4  5007.8  177.47
  5022.3  181.44  5028.6  181.83  5036.8  183.76  5051.3  184.57  5101.1  183.67
  5115.5  184.47  5150.8  188.03  5171.6  191.41  5407.2  196.92  5554.6  201.47
#Mann= 7 ,-1 , 0
  4311.1     .05       0  4603.6     .07       0  4715.1     .12       0
    4938     .07       0  4966.9     .05       0  4972.6     .05       0
  4983.9     .05       0
Bank Sta=4972.6,4983.9
XS Rating Curve= 0 ,0
Exp/Cntr=0.3,0.1

Type RM Length L Ch R = 1 ,13377   ,541,541,541
BEGIN DESCRIPTION:
Mapping XS bd24a28a
END DESCRIPTION:
XS GIS Cut Line= 3
      2494045.24     13461491.58      2494917.61     13461265.89
      2495298.56     13460858.97
#Sta/Elev= 30
  4100.1  195.83  4179.9  194.52  4466.1  190.42  4501.6  190.76  4821.4  189.08
  4886.1  185.62  4895.2  185.96  4915.9  188.03  4926.2  188.09  4948.4  186.93
  4967.5  184.39  4988.4  176.55  5008.6  174.18  5009.1  173.68  5019.4  173.68
  5019.9  174.18  5021.1  176.15  5035.3  180.53  5049.5  184.38  5056.8  184.89
  5063.6     187  5070.9  187.15  5084.7  188.63  5130.9  189.27  5154.4  189.17
  5276.1  192.07  5396.3  193.69  5403.1  194.33  5488.1  195.95  5558.6  198.28
#Mann= 8 ,-1 , 0
  4100.1     .05       0  4179.9     .12       0  4886.1     .07       0
  4988.4     .12       0  5008.6     .05       0  5019.9     .12       0
  5130.9     .07       0  5154.4     .05       0
Bank Sta=5008.6,5019.9
XS Rating Curve= 0 ,0
Exp/Cntr=0.3,0.1

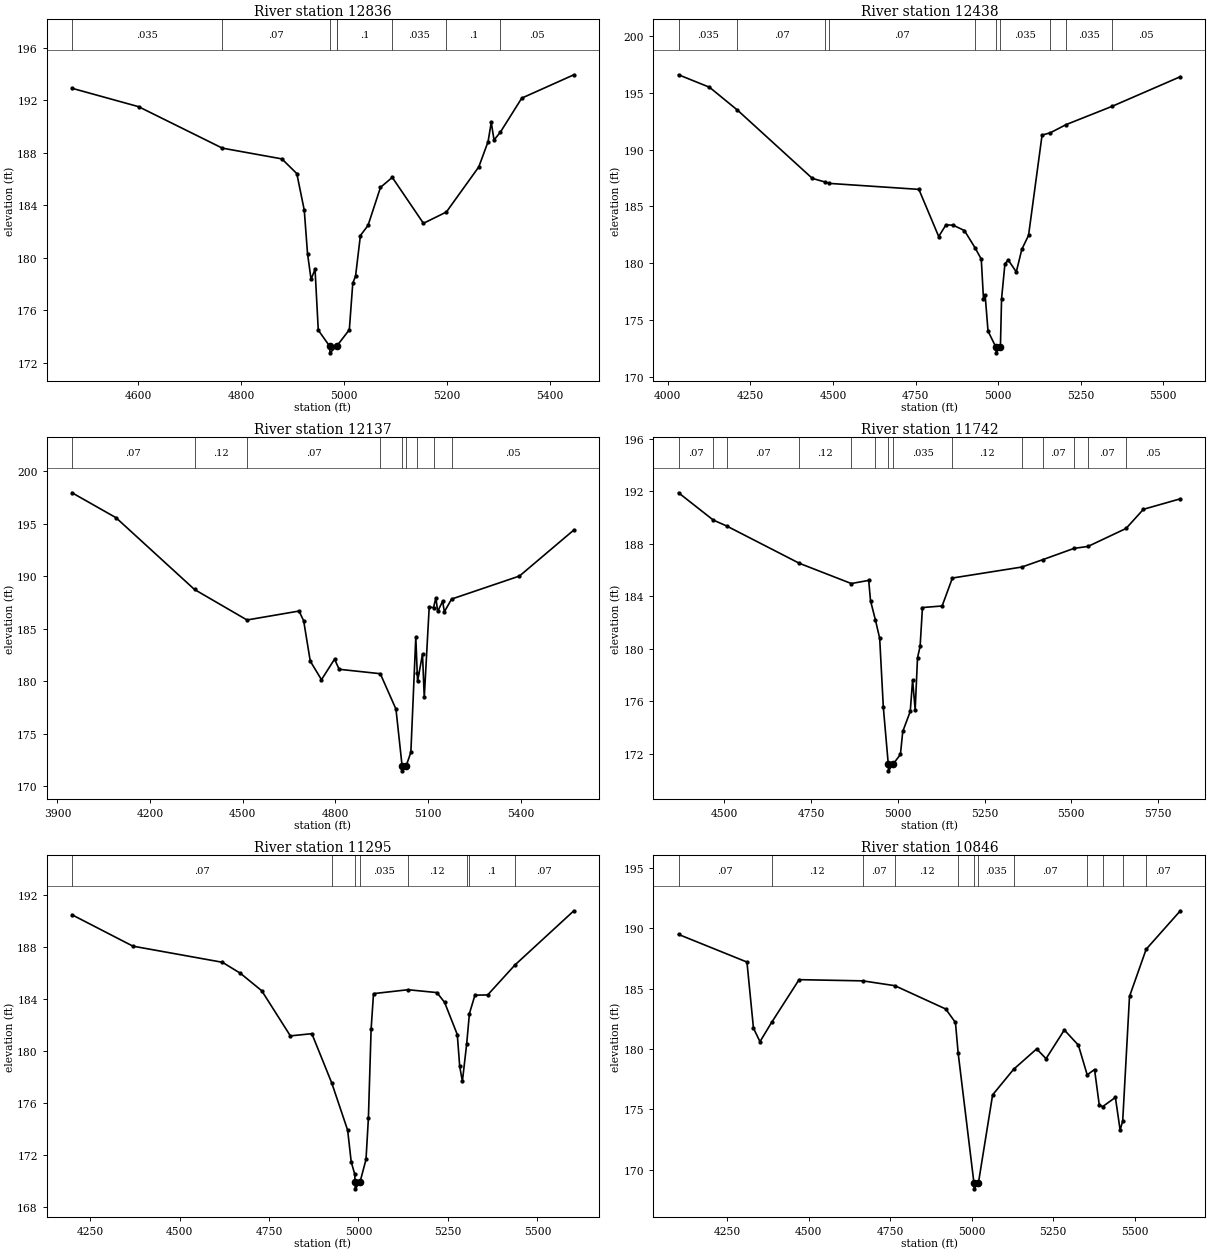
Type RM Length L Ch R = 1 ,12836   ,398,398,398
BEGIN DESCRIPTION:
Mapping XS c91c0115
END DESCRIPTION:
XS GIS Cut Line= 3
      2494816.78     13461957.99      2495230.83     13461640.29
      2495399.46     13461220.37
#Sta/Elev= 30
  4472.1  192.91  4601.2  191.51  4763.9  188.35  4879.5  187.53  4908.5  186.41
    4923  183.62  4929.3  180.32  4936.2  178.35  4943.9  179.12  4950.2  174.48
  4972.4  173.25  4972.9  172.75  4985.9  173.25  4986.2  173.27  5010.5  174.51
  5017.2  178.06  5022.6   178.6    5032  181.69  5046.8  182.46    5071  185.36
  5093.9  186.12  5154.4  182.62  5198.9  183.48  5261.9  186.92  5279.9  188.84
  5286.1  190.31  5291.5  188.97    5304  189.58  5345.3  192.16  5446.5  193.94
#Mann= 8 ,-1 , 0
  4472.1    .035       0  4763.9     .07       0  4972.4     .05       0
  4985.9     .07       0  4986.2      .1       0  5093.9    .035       0
  5198.9      .1       0    5304     .05       0
Bank Sta=4972.4,4985.9
XS Rating Curve= 0 ,0
Exp/Cntr=0.3,0.1

Type RM Length L Ch R = 1 ,12438   ,301,301,301
BEGIN DESCRIPTION:
Mapping XS 2a7706bc
END DESCRIPTION:
XS GIS Cut Line= 3
      2494817.78     13462194.71      2495564.31     13461791.07
       2495703.2     13461135.69
#Sta/Elev= 30
  4032.8  196.62  4126.5  195.52  4211.2   193.5  4437.7  187.48  4477.5  187.15
    4488  187.04  4760.2  186.51  4820.2  182.35  4842.1  183.38  4863.9  183.35
  4897.9  182.88  4929.7  181.38    4949  180.36  4955.6  176.88  4960.7  177.19
  4969.4  174.01  4993.3  172.59  4993.8  172.09  5006.9  172.59  5010.4  176.86
  5020.6  179.95  5030.8  180.27    5055  179.23  5071.7  181.22  5092.1  182.46
    5133   191.3  5157.8   191.5  5205.4  192.22  5344.4  193.83  5551.4  196.45
#Mann= 10 ,-1 , 0
  4032.8    .035       0  4211.2     .07       0  4477.5     .12       0
    4488     .07       0  4929.7    .035       0  4993.3    .035       0
  5006.9    .035       0  5157.8     .05       0  5205.4    .035       0
  5344.4     .05       0
Bank Sta=4993.3,5006.9
XS Rating Curve= 0 ,0
Exp/Cntr=0.3,0.1

Type RM Length L Ch R = 1 ,12137   ,395,395,395
BEGIN DESCRIPTION:
Mapping XS 9c5c7d17
END DESCRIPTION:
XS GIS Cut Line= 3
      2494934.99     13462390.01      2495816.05     13461821.45
      2496097.58     13461319.03
#Sta/Elev= 30
  3947.5  197.93  4089.7  195.56  4343.9  188.73  4513.8  185.83  4682.3  186.68
  4697.3  185.75  4718.6  181.92  4754.9  180.15  4797.2   182.1  4812.3  181.14
  4945.3  180.72  4996.1  177.35  5015.8  171.98  5016.3  171.48  5029.4  171.98
  5044.3  173.24  5060.3   184.2  5064.9  180.79    5066  179.98    5082  182.59
  5087.7  178.46  5103.7  187.07  5117.6     187  5125.4  187.94  5131.1  186.64
  5147.1  187.61  5152.8  186.61  5176.2  187.82  5395.9  190.01    5572  194.39
#Mann= 9 ,-1 , 0
  3947.5     .07       0  4343.9     .12       0  4513.8     .07       0
  4945.3    .035       0  5015.8    .035       0  5029.4    .035       0
  5064.9     .07       0  5117.6     .12       0  5176.2     .05       0
Bank Sta=5015.8,5029.4
XS Rating Curve= 0 ,0
Exp/Cntr=0.3,0.1

Type RM Length L Ch R = 1 ,11742   ,447,447,447
BEGIN DESCRIPTION:
FARMER CREEK 18.0
END DESCRIPTION:
XS GIS Cut Line= 3
        2495225.       13462375.        2495825.       13462175.
        2496375.       13461575.
#Sta/Elev= 30
    4368   191.9  4468.1  189.82  4506.6  189.37  4716.5  186.52    4866  184.98
  4916.1  185.22  4921.4  183.67  4935.7  182.18  4947.8   180.8  4958.3  175.55
  4972.6   171.2  4973.1   170.7  4986.2   171.2  5007.6  171.95  5014.3   173.7
  5035.9  175.23  5042.7  177.62  5050.1  175.36  5056.9  179.33  5064.3  180.18
  5071.1  183.15  5127.8  183.27  5157.4   185.4  5357.8  186.24  5417.9   186.8
  5507.9  187.66  5548.3  187.81    5658  189.18    5708  190.64  5814.4  191.44
#Mann= 14 ,-1 , 0
    4368     .07       0  4468.1     .12       0  4506.6     .07       0
  4716.5     .12       0    4866     .07       0  4935.7    .035       0
  4972.6    .035       0  4986.2    .035       0  5157.4     .12       0
  5357.8      .1       0  5417.9     .07       0  5507.9      .1       0
  5548.3     .07       0    5658     .05       0
Bank Sta=4972.6,4986.2
XS Rating Curve= 0 ,0
Exp/Cntr=0.3,0.1

Type RM Length L Ch R = 1 ,11295   ,449,449,449
BEGIN DESCRIPTION:
FARMER CREEK 17.0
END DESCRIPTION:
XS GIS Cut Line= 3
      2495324.98       13462475.        2496125.       13462475.
        2496575.       13462075.
#Sta/Elev= 30
  4199.7  190.44  4369.7  188.03  4619.7  186.79  4669.7  185.95  4729.7   184.6
  4809.7  181.13  4869.7   181.3  4925.3  177.51  4969.7  173.88  4979.7  171.44
  4989.7  170.48  4990.4  169.87  4990.9  169.37  5004.1  169.87    5021  171.63
  5027.7   174.8  5035.3  181.65    5042  184.38  5138.6  184.68  5219.2  184.46
  5240.6  183.71  5276.1  181.23  5282.8  178.79  5290.3  177.63  5302.2  180.48
    5310  182.85  5325.4  184.26    5361  184.28  5437.1  186.58  5601.8  190.75
#Mann= 8 ,-1 , 0
  4199.7     .07       0  4925.3    .035       0  4990.4    .035       0
  5004.1    .035       0  5138.6     .12       0  5302.2     .07       0
    5310      .1       0  5437.1     .07       0
Bank Sta=4990.4,5004.1
XS Rating Curve= 0 ,0
Exp/Cntr=0.3,0.1

Type RM Length L Ch R = 1 ,10846   ,263,263,263
BEGIN DESCRIPTION:
FARMER CREEK 16.0
END DESCRIPTION:
XS GIS Cut Line= 3
      2495474.97       13462825.        2496375.       13462825.
      2496874.96     13462425.03
#Sta/Elev= 30
  4100.3   189.5  4310.3  187.21  4330.3  181.73  4350.3  180.61  4385.9   182.2
  4470.3  185.75    4666  185.65  4764.3  185.25  4920.3  183.32  4950.3   182.2
  4958.6  179.67    5007  168.91  5007.5  168.41  5020.9  168.91  5064.4   176.2
  5128.9  178.32  5199.6  180.01  5228.4   179.2  5284.5  181.58  5327.7  180.32
  5354.7  177.86  5377.3   178.3  5391.7  175.37  5401.9  175.22  5441.3  175.99
  5455.8  173.28  5463.7  174.03  5484.6  184.36  5535.7  188.27  5640.6  191.46
#Mann= 12 ,-1 , 0
  4100.3     .07       0  4385.9     .12       0    4666     .07       0
  4764.3     .12       0  4958.6    .035       0    5007    .035       0
  5020.9    .035       0  5128.9     .07       0  5354.7    .035       0
  5401.9     .07       0  5463.7     .12       0  5535.7     .07       0
Bank Sta=5007,5020.9
XS Rating Curve= 0 ,0
Exp/Cntr=0.3,0.1

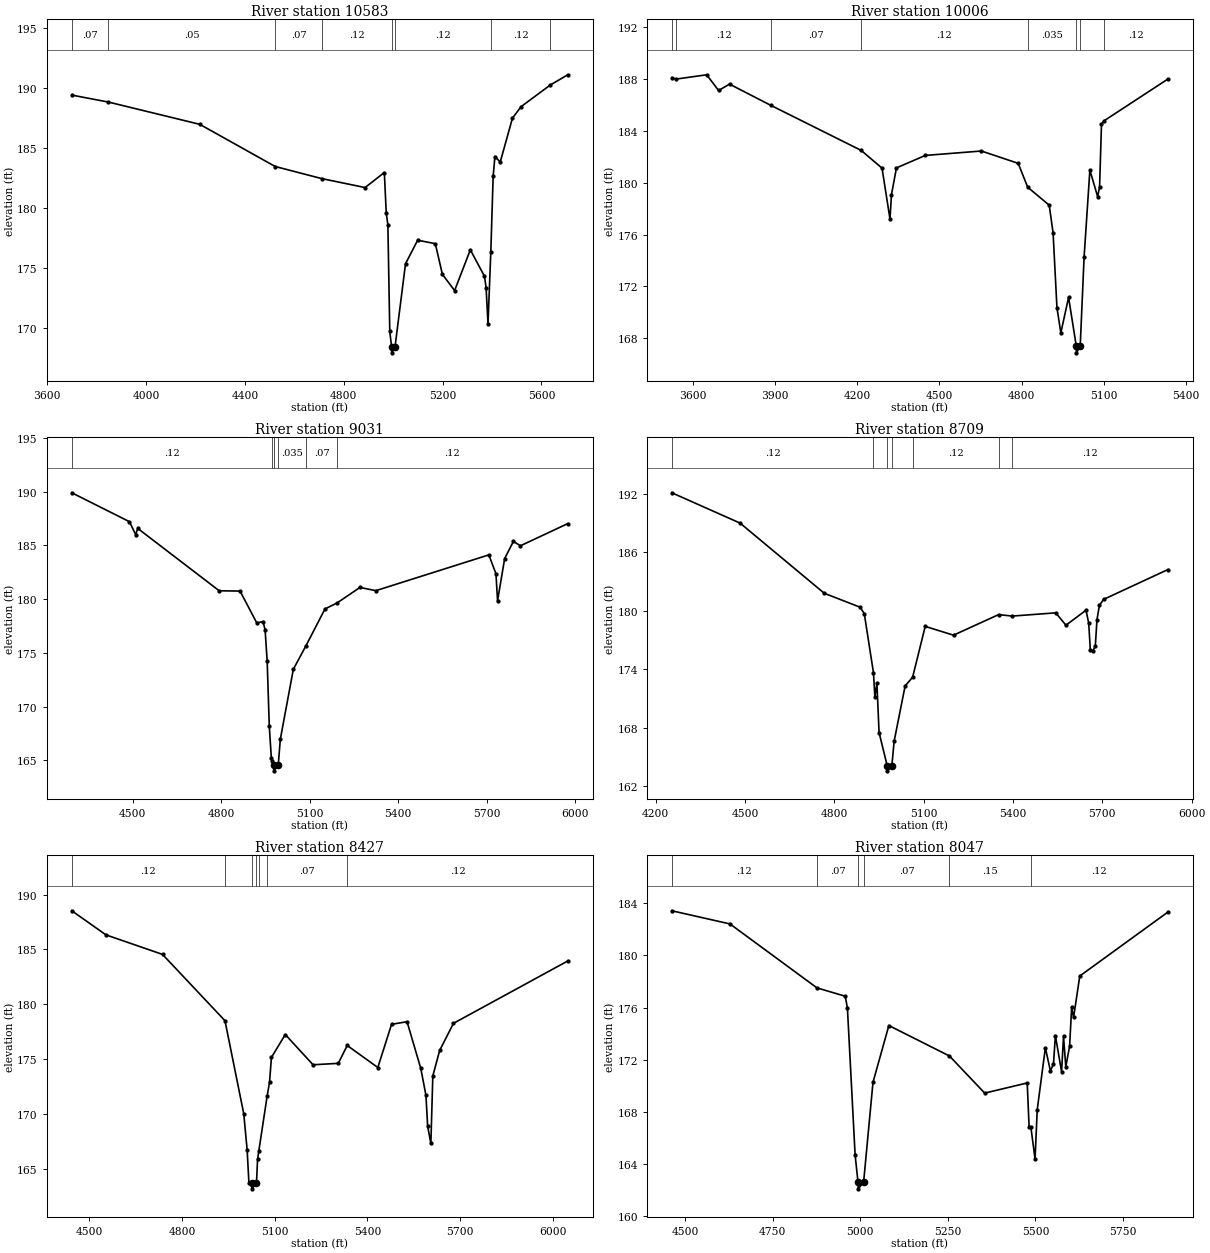
Type RM Length L Ch R = 1 ,10583   ,577,577,577
BEGIN DESCRIPTION:
Mapping XS f25f82dd
END DESCRIPTION:
XS GIS Cut Line= 4
      2495412.44     13463375.26      2496433.24     13463140.89
      2496636.36     13462901.31       2497130.6     13462485.11
#Sta/Elev= 30
  3699.1  189.38  3847.4   188.8    4217  186.95  4522.5  183.44  4711.6  182.43
  4886.2  181.69  4964.2  182.94    4972  179.54  4978.5  178.61  4986.2  169.72
  4993.6  168.44  4994.1  167.94  5007.5  168.44  5049.9  175.35  5099.1  177.31
  5170.6  177.02  5199.2  174.47  5248.6  173.12  5312.3  176.51  5369.5  174.31
  5376.1  173.37  5383.8  170.34  5395.1   176.3  5404.7  182.64  5411.8  184.27
  5433.3  183.81  5482.7  187.46  5517.8  188.42    5636  190.22  5706.7  191.07
#Mann= 8 ,-1 , 0
  3699.1     .07       0  3847.4     .05       0  4522.5     .07       0
  4711.6     .12       0  4993.6     .05       0  5007.5     .12       0
  5395.1     .12       0    5636     .07       0
Bank Sta=4993.6,5007.5
XS Rating Curve= 0 ,0
Exp/Cntr=0.3,0.1

Type RM Length L Ch R = 1 ,10006   ,975,975,975
BEGIN DESCRIPTION:
Mapping XS 75c2bcbc
END DESCRIPTION:
XS GIS Cut Line= 3
      2495808.22     13463583.61      2496829.07      13463146.1
      2497329.05     13462656.54
#Sta/Elev= 30
  3523.8  188.07  3539.7  187.97  3650.8   188.3  3694.4  187.09  3734.2  187.58
  3884.6  185.95  4214.5  182.48  4290.9  181.11  4319.9  177.19  4325.4  179.08
  4343.5  181.13  4448.7  182.09  4653.6  182.43  4787.9  181.48  4822.6  179.64
  4901.1  178.26  4915.2  176.13  4929.3  170.37  4943.5  168.43  4971.8  171.16
    5000  167.39  5000.5  166.89  5014.2  167.39  5028.4  174.26  5049.5  180.96
  5077.8  178.92  5084.9  179.66  5091.9   184.5  5102.2  184.77  5334.2  187.97
#Mann= 8 ,-1 , 0
  3523.8     .05       0  3539.7     .12       0  3884.6     .07       0
  4214.5     .12       0  4822.6    .035       0    5000    .035       0
  5014.2    .035       0  5102.2     .12       0
Bank Sta=5000,5014.2
XS Rating Curve= 0 ,0
Exp/Cntr=0.3,0.1

Type RM Length L Ch R = 1 ,9031    ,322,322,322
BEGIN DESCRIPTION:
Mapping XS f5a654b8
END DESCRIPTION:
XS GIS Cut Line= 3
      2496716.56     13464262.78      2497195.74     13463778.39
      2497570.36     13462852.25
#Sta/Elev= 30
  4293.9   189.9  4489.2  187.21  4510.4  186.01  4517.5  186.58  4793.3  180.78
    4864  180.75  4920.6  177.79  4941.8  177.91  4948.9  177.14  4955.9  174.22
    4963  168.18    4970  165.23  4973.7  164.89  4977.8  164.52  4978.3  164.02
  4993.2  164.52  5000.5  166.97  5044.5  173.47  5087.2  175.66  5151.8  179.09
  5192.4  179.64  5270.2  181.09  5324.1  180.79  5706.9  184.12    5731  182.36
  5736.4  179.85  5760.5  183.78    5790  185.37  5814.1  184.97  5974.3  187.03
#Mann= 6 ,-1 , 0
  4293.9     .12       0  4973.7    .035       0  4977.8    .035       0
  4993.2    .035       0  5087.2     .07       0  5192.4     .12       0
Bank Sta=4977.8,4993.2
XS Rating Curve= 0 ,0
Exp/Cntr=0.3,0.1

Type RM Length L Ch R = 1 ,8709    ,282,282,282
BEGIN DESCRIPTION:
Mapping XS f3a2eddc
END DESCRIPTION:
XS GIS Cut Line= 3
      2496878.03     13464481.52      2497414.49     13463976.31
       2497840.3     13463150.64
#Sta/Elev= 30
  4254.2   192.1  4483.2  188.99    4766  181.79  4886.2  180.36  4900.4  179.71
  4931.2  173.65    4936  171.13  4942.8  172.58  4950.1   167.5  4977.6  164.07
  4978.1  163.57    4993  164.07  5000.7  166.61  5037.6  172.28  5062.8  173.18
  5105.1  178.39  5200.1  177.49  5351.6   179.6  5397.2  179.45  5543.4  179.78
  5577.7  178.51  5645.2  180.05  5654.2  178.72  5659.8  175.92  5667.7  175.84
  5676.4  176.37    5682  179.09  5690.2  180.55  5704.2  181.16  5920.1  184.22
#Mann= 7 ,-1 , 0
  4254.2     .12       0  4931.2    .035       0  4977.6    .035       0
    4993    .035       0  5062.8     .12       0  5351.6     .07       0
  5397.2     .12       0
Bank Sta=4977.6,4993
XS Rating Curve= 0 ,0
Exp/Cntr=0.3,0.1

Type RM Length L Ch R = 1 ,8427    ,380,380,380
BEGIN DESCRIPTION:
Mapping XS fd6631fb
END DESCRIPTION:
XS GIS Cut Line= 3
      2497372.81     13464611.75      2497633.24     13464142.98
      2498117.56     13463189.94
#Sta/Elev= 30
  4443.2  188.52  4553.9  186.32  4736.9  184.54    4939  178.49  4999.8     170
  5010.8   166.7  5016.5  163.69  5025.3  163.65  5025.8  163.15    5041  163.65
  5044.5  165.84  5048.7  166.63  5075.4   171.6  5083.2  172.87  5089.4  175.14
  5134.2  177.23    5224  174.47  5305.8   174.6  5334.7  176.23  5433.7  174.22
  5478.2  178.16  5528.3   178.4  5572.8  174.13  5589.4  171.69    5595  168.85
  5605.4   167.3  5611.7  173.45  5633.9  175.78  5678.5  178.25  6048.5  183.94
#Mann= 7 ,-1 , 0
  4443.2     .12       0    4939     .07       0  5025.3     .05       0
    5041     .07       0  5048.7    .035       0  5075.4     .07       0
  5334.7     .12       0
Bank Sta=5025.3,5041
XS Rating Curve= 0 ,0
Exp/Cntr=0.3,0.1

Type RM Length L Ch R = 1 ,8047    ,759,759,759
BEGIN DESCRIPTION:
Mapping XS dc988c5a
END DESCRIPTION:
XS GIS Cut Line= 4
      2497857.19     13464580.49      2498008.24     13464142.98
       2497924.9     13463986.73      2498242.26     13463279.18
#Sta/Elev= 30
  4462.6  183.43  4628.4  182.42  4876.6  177.51  4957.2  176.87  4963.5  175.98
  4985.5  164.68  4993.8  162.58  4994.3  162.08  5009.7  162.58  5036.5  170.26
  5081.8  174.62  5254.8  172.28  5355.2  169.43  5476.6  170.21    5482  166.83
  5486.9  166.85    5499  164.37  5505.2  168.16  5528.4  172.91  5542.8  171.13
  5551.6  171.68    5557  173.85  5574.7  171.07  5580.2  173.79  5586.7  171.46
  5597.6  173.04  5603.4  176.01  5608.9  175.24  5626.6  178.42    5878  183.33
#Mann= 6 ,-1 , 0
  4462.6     .12       0  4876.6     .07       0  4993.8     .05       0
  5009.7     .07       0  5254.8     .15       0  5486.9     .12       0
Bank Sta=4993.8,5009.7
XS Rating Curve= 0 ,0
Exp/Cntr=0.3,0.1

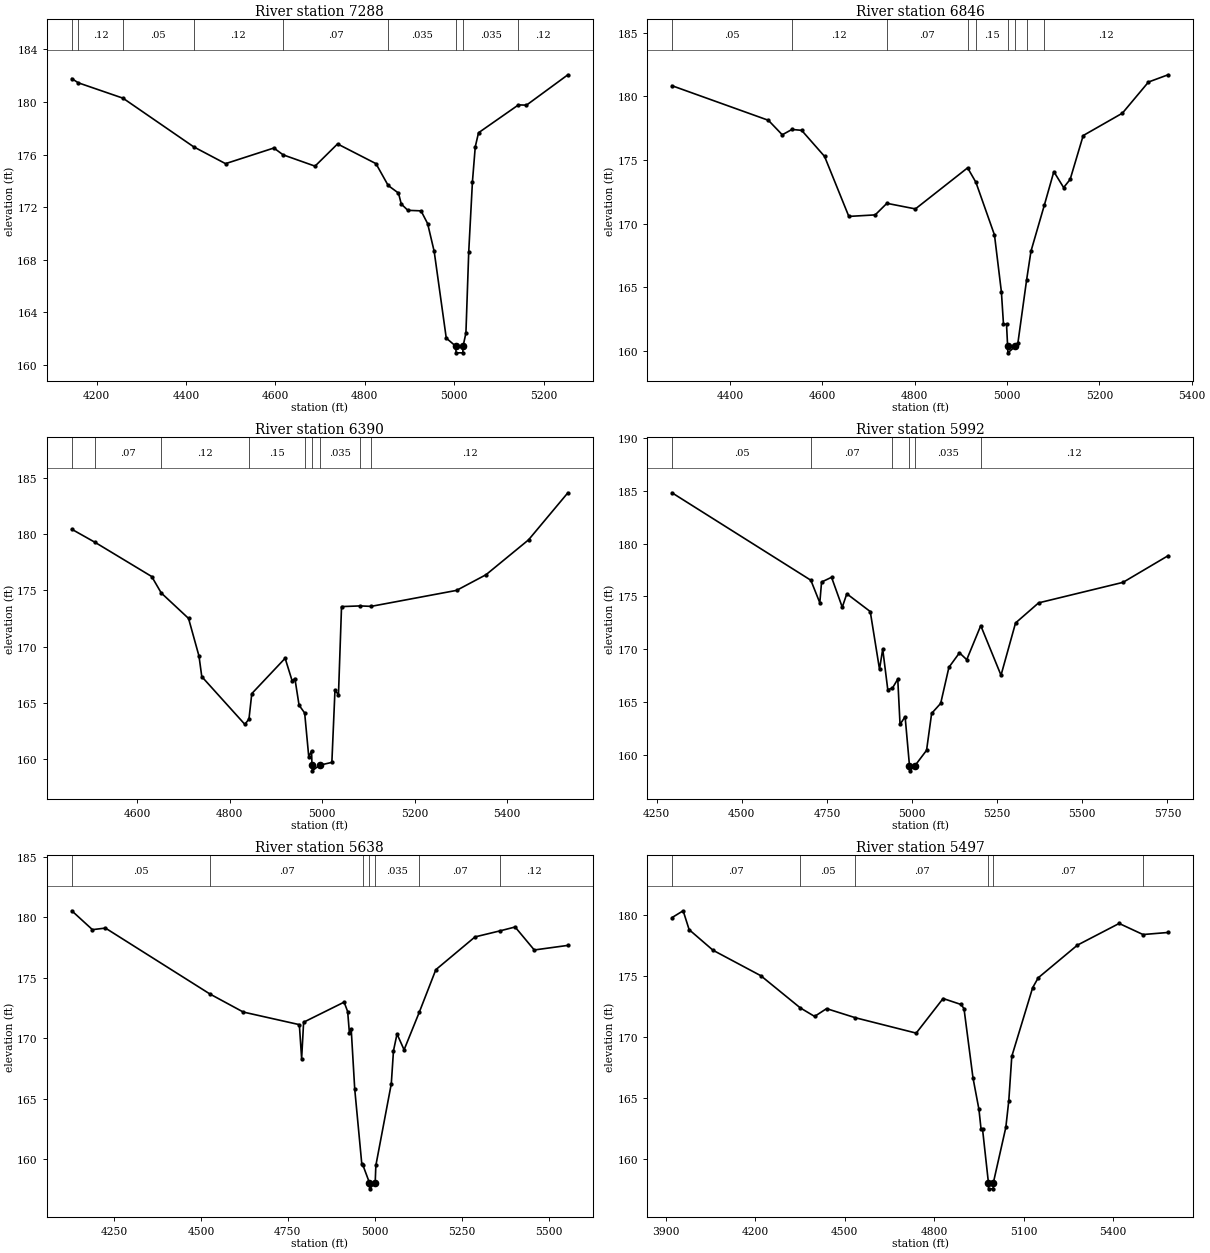
Type RM Length L Ch R = 1 ,7288    ,442,442,442
BEGIN DESCRIPTION:
FARMER CREEK 11.0
END DESCRIPTION:
XS GIS Cut Line= 3
      2497974.98     13464425.02        2498475.       13463725.
      2498625.02     13463524.97
#Sta/Elev= 30
  4144.2  181.78  4158.7  181.46  4258.8  180.29    4417  176.59  4488.3  175.31
  4596.5   176.5  4617.2  175.98  4688.6  175.12    4739  176.81    4825  175.31
  4852.3  173.65  4875.4  173.07  4881.6  172.24  4896.3  171.76  4925.8  171.72
  4940.6  170.75  4955.3  168.63  4982.3  162.04  5003.7  161.42  5004.2  160.92
  5019.4  160.92  5019.9  161.42  5026.3  162.43  5032.6  168.61  5040.9  173.95
  5047.2  176.59  5054.5  177.66  5143.9  179.78  5161.8  179.76  5254.5  182.07
#Mann= 9 ,-1 , 0
  4144.2     .05       0  4158.7     .12       0  4258.8     .05       0
    4417     .12       0  4617.2     .07       0  4852.3    .035       0
  5003.7    .035       0  5019.9    .035       0  5143.9     .12       0
Bank Sta=5003.7,5019.9
XS Rating Curve= 0 ,0
Exp/Cntr=0.3,0.1

Type RM Length L Ch R = 1 ,6846    ,456,456,456
BEGIN DESCRIPTION:
FARMER CREEK 10.0
END DESCRIPTION:
XS GIS Cut Line= 3
        2498125.       13464475.        2498725.       13464075.
      2498975.02     13463824.98
#Sta/Elev= 30
  4274.1  180.84  4482.9  178.12    4513  176.98  4533.9   177.4    4555  177.33
  4604.6  175.28  4657.2  170.56  4714.3  170.68  4739.6  171.59  4801.4  171.15
  4914.5  174.38  4932.5  173.24  4972.7   169.1  4987.7  164.62  4992.2  162.08
  4998.8  162.08  5001.2  160.33  5001.7  159.83  5017.5  160.33  5023.5  160.62
  5042.4  165.59  5051.8  167.83  5080.9  171.47  5101.3  174.08  5122.5  172.83
  5136.6  173.47  5164.9  176.92  5249.8  178.68  5306.3  181.13  5348.8   181.7
#Mann= 9 ,-1 , 0
  4274.1     .05       0  4533.9     .12       0  4739.6     .07       0
  4914.5    .035       0  4932.5     .15       0  5001.2     .05       0
  5017.5     .15       0  5042.4    .035       0  5080.9     .12       0
Bank Sta=5001.2,5017.5
XS Rating Curve= 0 ,0
Exp/Cntr=0.3,0.1

Type RM Length L Ch R = 1 ,6390    ,398,398,398
BEGIN DESCRIPTION:
FARMER CREEK 9.0
END DESCRIPTION:
XS GIS Cut Line= 3
      2498424.97     13464775.02        2498875.       13464475.
      2499225.02     13464074.98
#Sta/Elev= 30
    4459  180.42  4509.6  179.25  4631.8  176.22  4652.4  174.76  4711.4   172.5
    4734  169.15    4740  167.33  4833.1  163.09    4842  163.56  4848.1  165.82
  4920.2  168.96  4935.3  166.96  4941.3  167.16  4950.3  164.79  4962.4   164.1
  4971.3  160.19  4977.3  160.74  4978.2  159.46  4978.7  158.96  4994.5  159.46
  5021.2  159.71  5027.9   166.1  5035.5  165.73  5042.1  173.55  5082.3  173.61
  5106.1  173.57  5290.8  174.99  5354.4  176.38  5446.4  179.48  5531.4  183.66
#Mann= 9 ,-1 , 0
    4459     .05       0  4509.6     .07       0  4652.4     .12       0
    4842     .15       0  4962.4    .035       0  4978.2    .035       0
  4994.5    .035       0  5082.3     .15       0  5106.1     .12       0
Bank Sta=4978.2,4994.5
XS Rating Curve= 0 ,0
Exp/Cntr=0.3,0.1

Type RM Length L Ch R = 1 ,5992    ,354,354,354
BEGIN DESCRIPTION:
Mapping XS aa33fcbb
END DESCRIPTION:
XS GIS Cut Line= 4
      2498242.65     13465075.26      2498831.15     13464913.81
      2498976.99     13464814.85      2499325.94     13464241.94
#Sta/Elev= 30
  4294.8   184.8  4702.7  176.53    4729   174.4  4734.2  176.36  4763.5  176.81
    4795  173.98  4808.3  175.25  4877.2  173.57  4904.4  168.11  4913.8  170.02
  4928.7  166.18  4942.5  166.34    4958  167.18  4964.7   162.9  4979.6  163.63
  4992.4  159.01  4992.9  158.51  5008.8  159.01  5042.6  160.45  5057.5  163.94
  5084.1  164.89  5108.3   168.3  5139.3  169.67  5160.6  169.02  5201.8  172.24
  5261.3  167.55    5304  172.49  5371.7  174.39  5619.6  176.33  5752.1  178.85
#Mann= 6 ,-1 , 0
  4294.8     .05       0  4702.7     .07       0  4942.5    .035       0
  4992.4    .035       0  5008.8    .035       0  5201.8     .12       0
Bank Sta=4992.4,5008.8
XS Rating Curve= 0 ,0
Exp/Cntr=0.3,0.1

Type RM Length L Ch R = 1 ,5638    ,141,141,141
BEGIN DESCRIPTION:
Mapping XS db2675c0
END DESCRIPTION:
XS GIS Cut Line= 3
      2498841.57     13465653.39      2499195.74      13465033.6
      2499315.53     13464330.47
#Sta/Elev= 30
  4128.6  180.54    4188  178.98  4225.4  179.11  4526.1  173.66    4622  172.17
  4783.2  171.13  4789.8  168.33  4795.5  171.33    4912  172.99  4922.2  172.21
  4927.3  170.41  4932.4  170.75  4942.5  165.81  4962.8  159.63  4966.3   159.5
  4984.9  158.06  4985.4  157.56  5001.4  158.06  5003.3  159.49  5047.7  166.24
    5054  168.97  5064.2  170.36  5084.5  169.05  5128.7  172.19  5175.8  175.67
  5288.5  178.38  5361.8  178.89  5403.9   179.2    5459   177.3  5555.7  177.68
#Mann= 7 ,-1 , 0
  4128.6     .05       0  4526.1     .07       0  4966.3    .035       0
  4984.9    .035       0  5001.4    .035       0  5128.7     .07       0
  5361.8     .12       0
Bank Sta=4984.9,5001.4
XS Rating Curve= 0 ,0
Exp/Cntr=0.3,0.1

Type RM Length L Ch R = 1 ,5497    ,130,130,130
BEGIN DESCRIPTION:
Mapping XS f21db49d
END DESCRIPTION:
XS GIS Cut Line= 3
      2499284.28     13466002.36      2499346.78     13464965.89
      2499357.19     13464340.93
#Sta/Elev= 30
  3920.7   179.8  3958.1  180.36  3978.2  178.81  4058.3  177.12  4218.6  175.03
  4350.9  172.39  4398.9  171.69    4439  172.33  4535.9  171.58  4739.5  170.32
  4829.7  173.16  4889.8  172.67  4899.8  172.33  4929.9  166.65  4949.9  164.06
    4957  162.43    4962  162.43  4981.7  158.04  4982.2  157.54  4997.7  157.54
  4998.2  158.04    5040  162.58    5050  164.78    5060  168.41    5130  174.05
  5148.7  174.86    5280  177.54    5420  179.32    5500  178.41  5584.1  178.58
#Mann= 6 ,-1 , 0
  3920.7     .07       0  4350.9     .05       0  4535.9     .07       0
  4981.7     .05       0  4998.2     .07       0    5500     .12       0
Bank Sta=4981.7,4998.2
XS Rating Curve= 0 ,0
Exp/Cntr=0.3,0.1

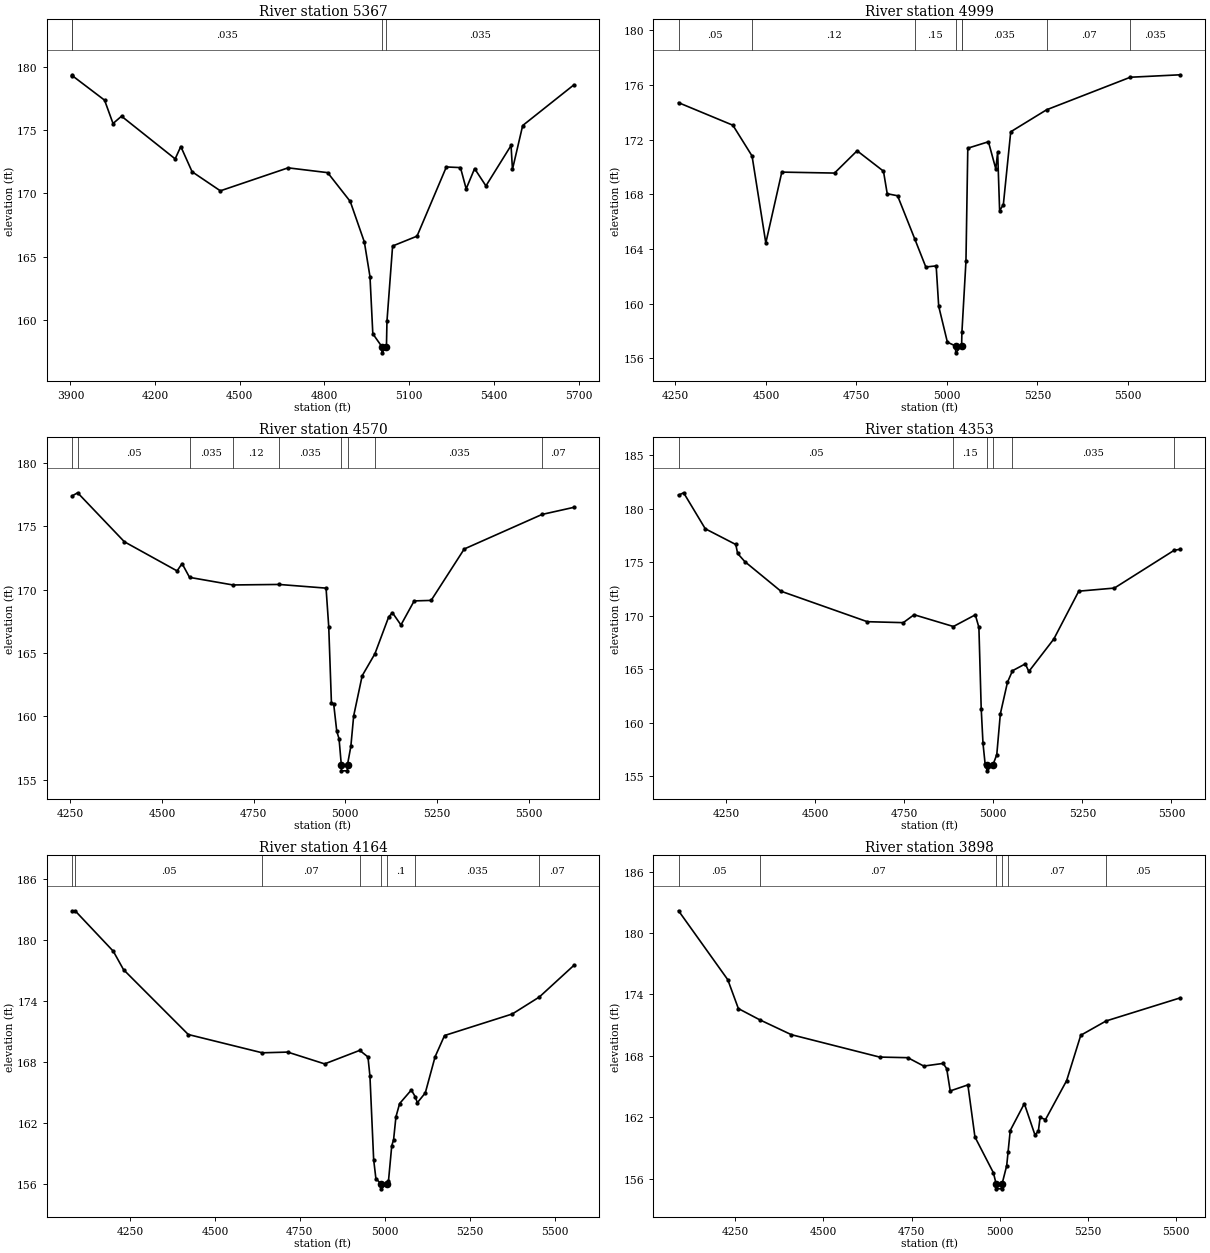
Type RM Length L Ch R = 1 ,5367    ,368,368,368
BEGIN DESCRIPTION:
Mapping XS acbd8cea
END DESCRIPTION:
XS GIS Cut Line= 3
       2499487.4      13466070.1      2499461.36     13464991.93
      2499503.03     13464294.06
#Sta/Elev= 30
  3905.9   179.4  3907.2  179.32    4021  177.39    4051  175.54  4081.1  176.12
  4271.1  172.74  4291.1  173.72  4331.1  171.72  4431.2  170.21  4671.2  172.03
  4811.3  171.65  4891.3  169.37  4941.3  166.16  4961.3  163.41  4971.3  158.89
  5003.1  157.88  5003.6  157.38  5019.6  157.88  5021.4  159.88  5041.4  165.84
  5127.9  166.62  5231.8   172.1  5281.8  172.05    5302  170.37  5331.9  171.97
    5372   170.6    5461   173.8    5466  171.91  5502.2  175.38  5683.5   178.6
#Mann= 4 ,-1 , 0
  3905.9     .07       0  3907.2    .035       0  5003.1    .035       0
  5019.6    .035       0
Bank Sta=5003.1,5019.6
XS Rating Curve= 0 ,0
Exp/Cntr=0.3,0.1

Type RM Length L Ch R = 1 ,4999    ,429,429,429
BEGIN DESCRIPTION:
Mapping XS f88b5df9
END DESCRIPTION:
XS GIS Cut Line= 3
      2499543.06      13465909.3      2499740.98     13465216.55
      2499902.45     13464570.69
#Sta/Elev= 30
  4258.4  174.71  4408.5  173.06  4461.5  170.81  4499.5  164.45  4543.7  169.63
  4689.3  169.56  4751.7  171.19  4824.5   169.7  4834.9  168.05  4863.5   167.9
  4911.3  164.72  4941.5  162.69  4970.1  162.77  4977.1  159.82  5001.1  157.19
  5023.6  156.91  5024.1  156.41  5040.4  156.91  5041.2   157.9  5052.4  163.11
  5057.5  171.38  5114.5  171.85  5134.8  169.87    5140  171.08  5145.4  166.81
  5155.7  167.25  5176.1  172.58  5275.2  174.19  5506.4  176.57  5644.6  176.75
#Mann= 8 ,-1 , 0
  4258.4     .05       0  4461.5     .12       0  4911.3     .15       0
  5023.6     .05       0  5040.4     .15       0  5041.2    .035       0
  5275.2     .07       0  5506.4    .035       0
Bank Sta=5023.6,5040.4
XS Rating Curve= 0 ,0
Exp/Cntr=0.3,0.1

Type RM Length L Ch R = 1 ,4570    ,217,217,217
BEGIN DESCRIPTION:
FARMER CREEK 5.0
END DESCRIPTION:
XS GIS Cut Line= 3
      2499625.01     13466024.99        2500075.       13465425.
      2500225.01     13464824.96
#Sta/Elev= 30
  4254.8   177.4    4270  177.65  4397.5  173.78  4541.2  171.48  4554.8  172.06
  4575.2  170.97  4693.4  170.37  4819.2  170.41  4947.5  170.12  4954.8  167.07
  4962.1  161.08  4968.3  160.97  4976.7  158.81  4982.9  158.23    4989  156.19
  4989.5  155.69  5005.5  155.69    5006  156.19  5015.1  157.62  5022.8  160.03
    5046   163.2  5080.8  164.94  5118.2  167.84  5128.5  168.18  5151.7  167.21
  5187.8  169.11  5234.1  169.15  5324.3  173.21  5536.6  175.94  5623.3   176.5
#Mann= 9 ,-1 , 0
  4254.8     .07       0    4270     .05       0  4575.2    .035       0
  4693.4     .12       0  4819.2    .035       0    4989     .05       0
    5006    .035       0  5080.8    .035       0  5536.6     .07       0
Bank Sta=4989,5006
XS Rating Curve= 0 ,0
Exp/Cntr=0.3,0.1

Type RM Length L Ch R = 1 ,4353    ,189,189,189
BEGIN DESCRIPTION:
Mapping XS 0146fa5a
END DESCRIPTION:
XS GIS Cut Line= 3
      2500383.23     13466299.19      2500258.24     13465445.06
      2500242.66     13464900.01
#Sta/Elev= 30
  4116.6  181.26  4130.9  181.48  4191.6  178.12  4277.3  176.65  4282.5  175.81
  4302.7  175.05  4403.8  172.29  4646.4  169.44  4747.4  169.35  4777.8  170.09
  4888.1  168.99  4949.6  170.08  4959.7  168.91  4966.2  161.31  4971.2  158.08
  4977.3  156.11  4981.4  156.01  4981.9  155.51  4998.4  156.01  5009.9  157.02
  5019.9  160.83  5039.9  163.78    5054  164.86  5089.9   165.5  5099.9  164.79
    5170  167.82    5240  172.29    5340  172.58  5508.4  176.12  5525.1   176.2
#Mann= 6 ,-1 , 0
  4116.6     .05       0  4888.1     .15       0  4981.4     .05       0
  4998.4     .15       0    5054    .035       0  5508.4     .07       0
Bank Sta=4981.4,4998.4
XS Rating Curve= 0 ,0
Exp/Cntr=0.3,0.1

Type RM Length L Ch R = 1 ,4164    ,266,266,266
BEGIN DESCRIPTION:
Mapping XS adb8fdbe
END DESCRIPTION:
XS GIS Cut Line= 4
      2500533.79     13466285.95      2500462.17     13465448.29
      2500358.01     13465211.75      2500334.14     13464834.18
#Sta/Elev= 30
  4079.3  182.83  4088.3  182.88  4200.7   178.9  4230.8  177.09  4421.5  170.71
  4639.3  168.91  4714.2  168.98    4823  167.82  4926.3  169.15  4950.6   168.5
  4956.4   166.6  4967.3  158.41  4973.9  156.54  4988.7  156.03  4989.2  155.53
  5005.7  156.03    5011  156.31  5020.6  159.77    5026  160.36  5032.9  162.61
  5043.8  163.92  5078.2  165.25  5089.4  164.61    5096     164  5119.4  164.97
  5148.2  168.52    5176  170.61  5375.6  172.73  5455.2   174.4  5556.8  177.51
#Mann= 8 ,-1 , 0
  4079.3     .07       0  4088.3     .05       0  4639.3     .07       0
  4926.3      .1       0  4988.7     .05       0  5005.7      .1       0
  5089.4    .035       0  5455.2     .07       0
Bank Sta=4988.7,5005.7
XS Rating Curve= 0 ,0
Exp/Cntr=0.3,0.1

Type RM Length L Ch R = 1 ,3898    ,406,406,406
BEGIN DESCRIPTION:
Mapping XS 13ae72aa
END DESCRIPTION:
XS GIS Cut Line= 3
      2500705.73     13466184.49      2500658.85     13465273.03
      2500664.06     13464762.62
#Sta/Elev= 30
  4089.1  182.18  4228.8  175.44  4258.8  172.62    4319  171.53    4409  170.07
  4659.3  167.88  4739.4  167.82  4784.6     167  4839.6  167.26  4849.6  166.75
  4859.6  164.57  4909.7  165.16  4929.7  160.07  4982.1  156.57  4989.7   155.5
  4990.2     155  5006.3     155  5006.8   155.5  5019.8  157.27  5023.8  158.64
  5029.8   160.7  5069.8  163.33  5099.8  160.28  5109.5  160.62  5114.5  161.98
  5129.8  161.77  5189.8  165.58  5229.8  170.01  5301.7  171.41  5512.2  173.67
#Mann= 6 ,-1 , 0
  4089.1     .05       0    4319     .07       0  4989.7     .05       0
  5006.8     .07       0  5023.8     .07       0  5301.7     .05       0
Bank Sta=4989.7,5006.8
XS Rating Curve= 0 ,0
Exp/Cntr=0.3,0.1