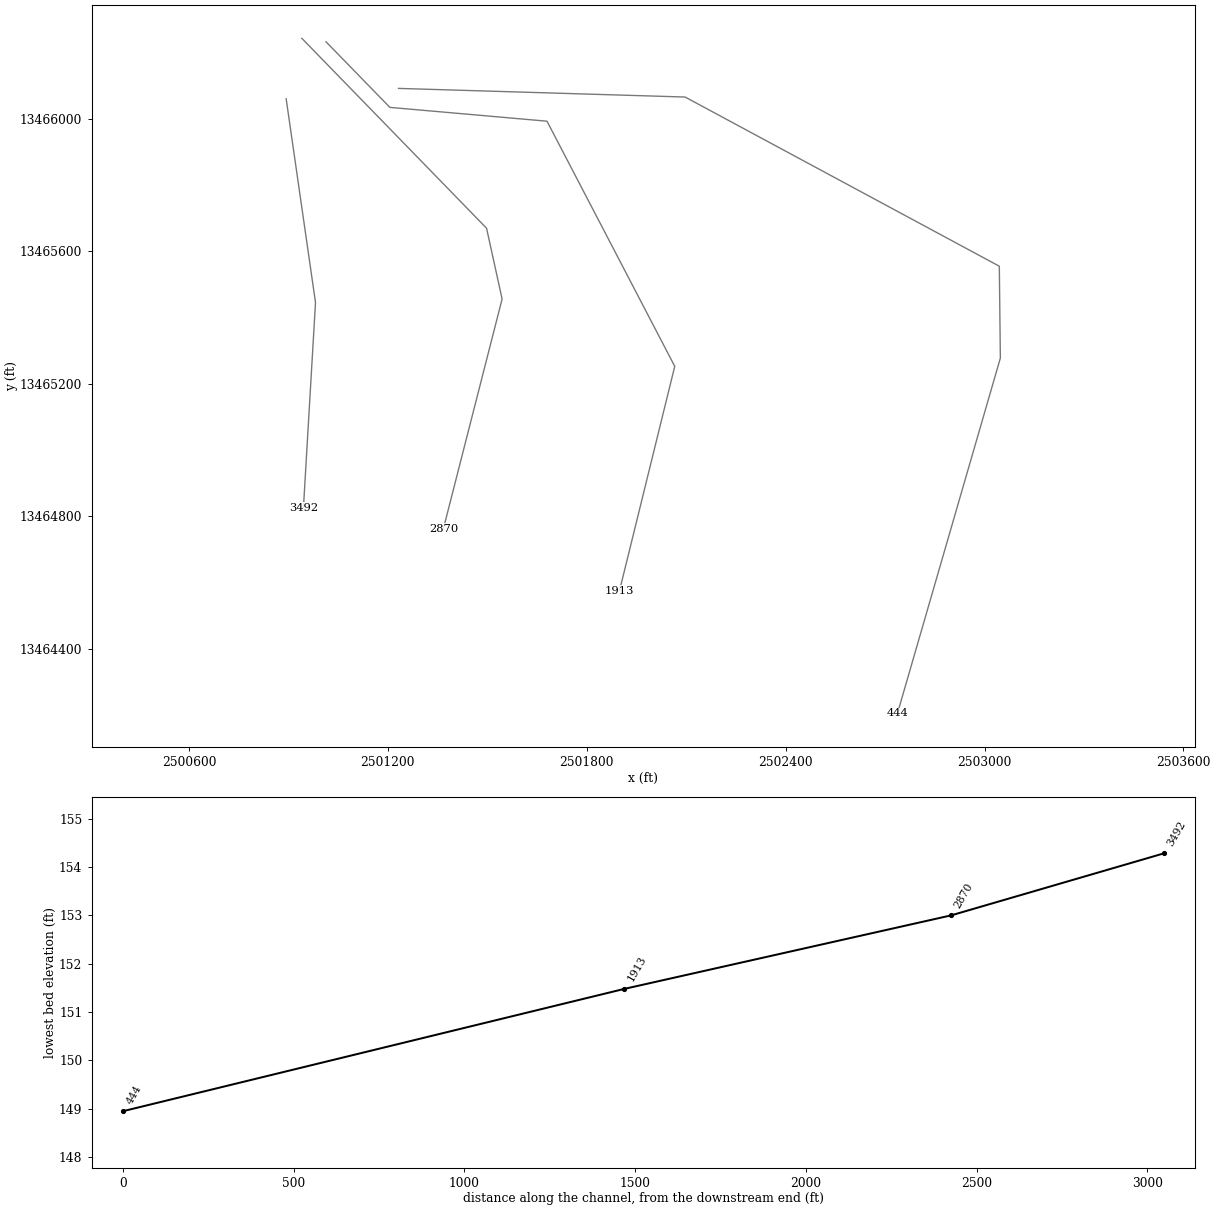
HEC-RAS study FARMER CREEK.prj: FARMER CREEK Base Level Engineering

--- FARMER CREEK.g01 (geometry) --- (continued)

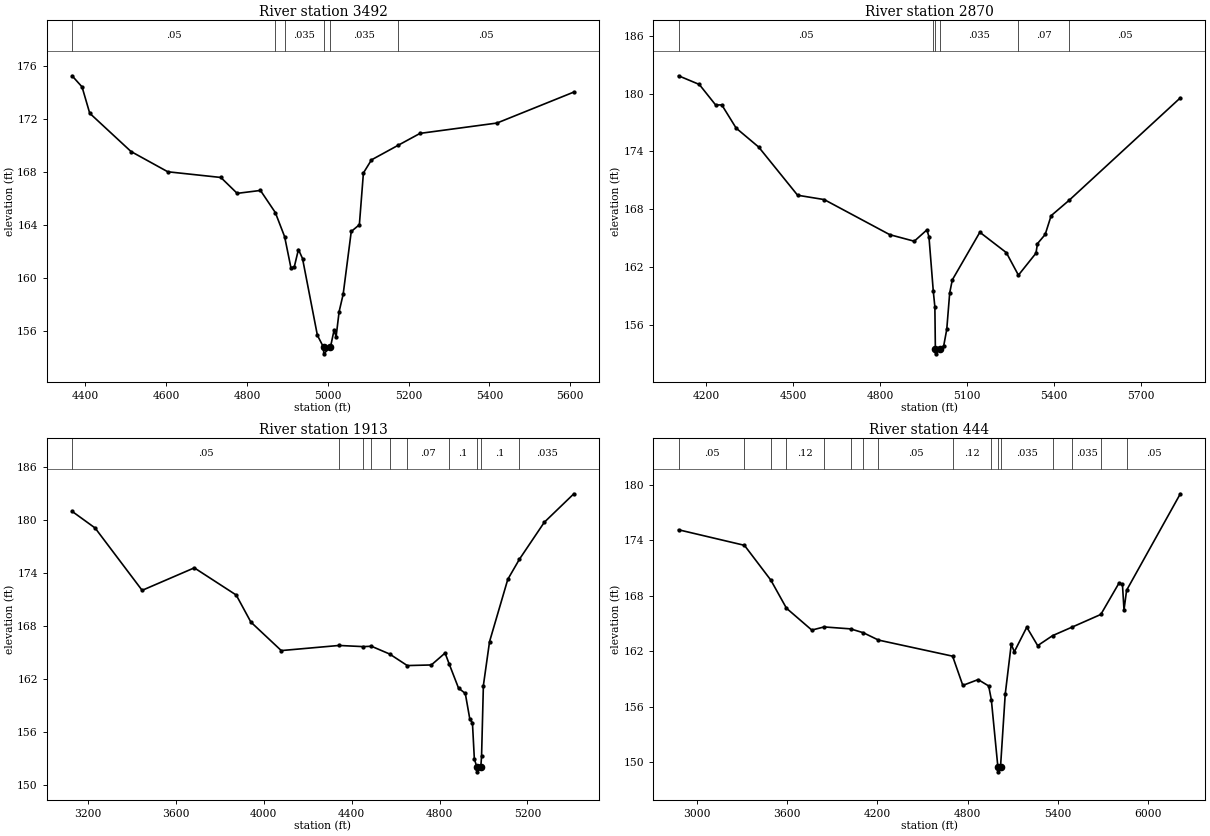
Type RM Length L Ch R = 1 ,3492    ,622,622,622
BEGIN DESCRIPTION:
Mapping XS 83cc415c
END DESCRIPTION:
XS GIS Cut Line= 3
      2500893.23     13466059.45      2500981.77      13465444.9
      2500945.31     13464825.07
#Sta/Elev= 30
    4367  175.28  4391.7  174.44  4410.7  172.45  4512.9  169.56  4603.9  168.03
  4735.2   167.6  4775.6   166.4  4833.2  166.62    4870  164.95    4893  163.13
  4908.7  160.77  4917.1  160.87  4927.2  162.16  4937.3  161.48  4974.1  155.68
  4989.3  154.78  4989.8  154.28  5006.4  154.78  5015.4  156.07  5020.4  155.57
  5027.9  157.47  5037.9  158.78  5057.9  163.52    5078  164.03    5088  167.94
    5108  168.93  5173.3  170.02  5228.2  170.93  5418.5  171.71  5608.8  174.05
#Mann= 6 ,-1 , 0
    4367     .05       0    4870     .07       0    4893    .035       0
  4989.3    .035       0  5006.4    .035       0  5173.3     .05       0
Bank Sta=4989.3,5006.4
XS Rating Curve= 0 ,0
Exp/Cntr=0.3,0.1

Type RM Length L Ch R = 1 ,2870    ,957,957,957
BEGIN DESCRIPTION:
Mapping XS f2a9fa7f
END DESCRIPTION:
XS GIS Cut Line= 4
      2500940.55     13466241.91      2501497.82     13465669.02
       2501544.7     13465455.48      2501367.62     13464762.79
#Sta/Elev= 30
  4104.7  181.84  4176.4  180.94  4232.9  178.81  4254.1  178.82  4303.7  176.41
  4381.4  174.45  4515.9  169.45  4607.7     169  4834.1  165.36  4918.7  164.68
  4962.5  165.86  4969.5  165.13  4984.5  159.47  4989.9  157.87  4991.6   153.5
  4992.1     153  5008.8   153.5  5020.6  153.86  5030.9  155.53  5041.1  159.32
  5050.1  160.67  5145.2  165.61  5236.6   163.5  5278.4  161.16    5339  163.44
  5344.2  164.43  5370.8  165.38  5391.4  167.33  5453.7  168.93  5837.5  179.55
#Mann= 6 ,-1 , 0
  4104.7     .05       0  4984.5    .035       0  4991.6    .035       0
  5008.8    .035       0  5278.4     .07       0  5453.7     .05       0
Bank Sta=4991.6,5008.8
XS Rating Curve= 0 ,0
Exp/Cntr=0.3,0.1

Type RM Length L Ch R = 1 ,1913    ,1469,1469,1469
BEGIN DESCRIPTION:
Mapping XS c9e4cff7
END DESCRIPTION:
XS GIS Cut Line= 5
      2501013.44     13466231.52      2501206.15      13466033.6
      2501680.11     13465991.93      2502065.53     13465252.35
      2501898.87     13464575.28
#Sta/Elev= 30
    3128  181.02  3232.8  179.13  3446.8  172.06  3684.2  174.61  3874.9  171.53
  3941.7  168.46  4079.9  165.23  4342.5  165.81  4452.1  165.68  4490.2  165.72
    4573  164.84  4653.3  163.53  4762.8   163.6  4825.3  164.95  4844.8  163.66
  4886.4  160.98  4917.3  160.37  4937.9  157.46  4949.8  157.04  4958.5  152.94
  4970.5  151.98    4971  151.48  4987.7  151.98  4991.3  153.22  4999.6  161.27
  5027.7  166.25  5110.7  173.31  5163.4  175.58  5276.8  179.78  5411.3  183.01
#Mann= 10 ,-1 , 0
    3128     .05       0  4342.5      .1       0  4452.1    .035       0
  4490.2     .07       0    4573    .035       0  4653.3     .07       0
  4844.8      .1       0  4970.5     .05       0  4987.7      .1       0
  5163.4    .035       0
Bank Sta=4970.5,4987.7
XS Rating Curve= 0 ,0
Exp/Cntr=0.3,0.1

Type RM Length L Ch R = 1 ,444     ,0,0,0
BEGIN DESCRIPTION:
FARMER CREEK 2.0
END DESCRIPTION:
XS GIS Cut Line= 5
      2501232.24     13466090.89      2502096.78     13466064.85
       2503044.7     13465554.43      2503047.83     13465277.26
      2502737.39     13464205.44
#Sta/Elev= 30
  2879.2  175.11    3317  173.43  3492.5  169.67  3596.5  166.63  3764.8  164.27
  3846.6  164.61  4022.2   164.4  4107.6  163.98  4207.8  163.19  4700.5  161.45
  4768.4  158.29  4870.2  158.92  4940.2  158.23  4957.9  156.74  5001.5  149.45
    5002  148.95  5018.8  149.45  5050.2  157.34  5090.2  162.74  5110.7  161.93
  5193.4  164.58  5265.8  162.59    5365  163.67  5495.8   164.6  5685.5  165.96
    5806  169.34  5829.1  169.22  5839.5  166.45  5856.7  168.57  6213.8     179
#Mann= 16 ,-1 , 0
  2879.2     .05       0    3317     .12       0  3492.5     .05       0
  3596.5     .12       0  3846.6     .05       0  4022.2     .07       0
  4107.6     .12       0  4207.8     .05       0  4700.5     .12       0
  4957.9    .035       0  5001.5    .035       0  5018.8    .035       0
    5365     .05       0  5495.8    .035       0  5685.5     .12       0
  5856.7     .05       0
Bank Sta=5001.5,5018.8
XS Rating Curve= 0 ,0
Exp/Cntr=0.3,0.1

Chan Stop Cuts=-1
Use User Specified Reach Order=0
Composite Channel Slope=5