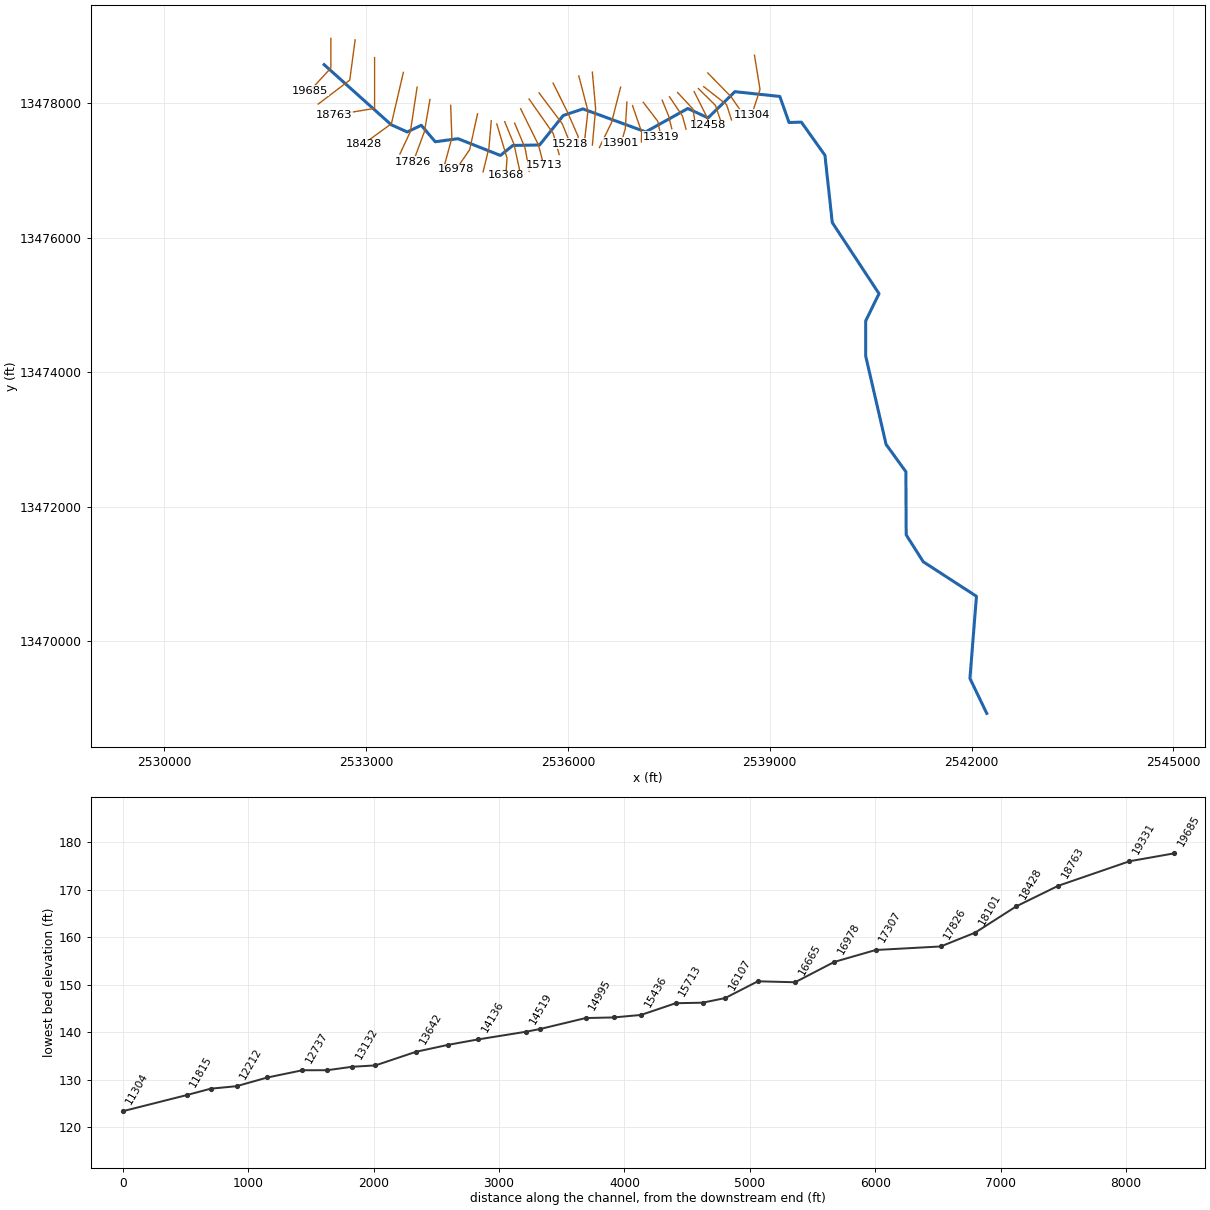
--- GOBBLER CREEK.prj (project) ---

Proj Title=GOBBLER CREEK Base Level Engineering
Current Plan=p01
Default Exp/Contr=0.3,0.1
English Units
Geom File=g01
Flow File=f01
Plan File=p01
Y Axis Title=Elevation
X Axis Title(PF)=Main Channel Distance
X Axis Title(XS)=Station
BEGIN DESCRIPTION:
GOBBLER CREEK
END DESCRIPTION:
DSS Export Rating Curves= 0
DSS Export Rating Curve Sorted= 0
DSS Export Volume Flow Curves= 0
DXF OffsetX= 0
DXF OffsetY= 0
DXF ScaleX= 1
DXF ScaleY= 10

--- GOBBLER CREEK.p01 (plan) ---

Plan Title=Multiple Run
Short Identifier=Multiple
Geom File=g01
Flow File=f01
Subcritical Flow
K Sum by GR= 0
Std Step Tol= 0.01
Critical Tol= 0.01
Num of Std Step Trials= 20
Max Error Tol= 0.3
Flow Tol Ratio= 0.001
Split Flow NTrial= 30
Split Flow Tol= 0.02
Split Flow Ratio= 0.02
Log Output Level= 0
Friction Slope Method= 1
Unsteady Friction Slope Method= 2
Unsteady Bridges Friction Slope Method= 1
Parabolic Critical Depth
Global Vel Dist=  1 , 1 , 1
Global Log Level= 0
CheckData=True
Encroach Param= -1, 0, 0, 0
BEGIN DESCRIPTION:
Multiple Run
END DESCRIPTION:

--- GOBBLER CREEK.f01 (steady flow) ---

Flow Title=Multiple
Number of Profiles=7
Profile Names=10-year,25-year,50-year,1pct_min,100-year,1pct_plu,500-year
River Rch & RM= GOBBLER CREEK,Reach-1,19685
     751    1206    1615    1047    2088    4167    3450
River Rch & RM= GOBBLER CREEK,Reach-1,11304
    1415    2337    3188    2098    4186    8353    7143
River Rch & RM= GOBBLER CREEK,Reach-1,7018
    1542    2554    3491    2302    4592    9163    7863
River Rch & RM= GOBBLER CREEK,Reach-1,3932
    1956    3274    4505    2988    5962   11896   10335
Boundary for River Rch & Prof#=GOBBLER CREEK,Reach-1,1
Up Type=0
Dn Type=3
Dn Slope=0.005
Boundary for River Rch & Prof#=GOBBLER CREEK,Reach-1,2
Up Type=0
Dn Type=3
Dn Slope=0.005
Boundary for River Rch & Prof#=GOBBLER CREEK,Reach-1,3
Up Type=0
Dn Type=3
Dn Slope=0.005
Boundary for River Rch & Prof#=GOBBLER CREEK,Reach-1,4
Up Type=0
Dn Type=3
Dn Slope=0.005
Boundary for River Rch & Prof#=GOBBLER CREEK,Reach-1,5
Up Type=0
Dn Type=3
Dn Slope=0.005
Boundary for River Rch & Prof#=GOBBLER CREEK,Reach-1,6
Up Type=0
Dn Type=3
Dn Slope=0.005
Boundary for River Rch & Prof#=GOBBLER CREEK,Reach-1,7
Up Type=0
Dn Type=3
Dn Slope=0.005

--- GOBBLER CREEK.g01 (geometry) ---

Geom Title=Existing Conditions
Program Version=4.10

River Reach=GOBBLER CREEK   ,Reach-1
Reach XY= 30
        2532375.       13478575.       2533372.7     13477680.83
      2533609.94     13477574.27      2533818.96     13477673.43
      2534026.48     13477428.45      2534364.57     13477473.95
      2534994.99     13477224.94      2535180.64     13477373.38
      2535577.44     13477380.48      2535930.18     13477819.59
      2536221.58     13477917.18      2537155.12     13477574.91
      2537780.86     13477922.94      2538081.99     13477783.82
      2538481.03     13478173.34       2539148.9     13478102.28
      2539285.63     13477714.88      2539469.39     13477720.22
      2539819.52     13477227.44      2539928.55     13476226.47
      2540623.42     13475168.95      2540426.06     13474764.56
      2540425.52     13474240.22      2540728.54     13472926.46
      2541022.93     13472519.14      2541027.24     13471580.93
      2541280.62     13471180.62      2542071.93      13470666.7
      2541974.96     13469444.98        2542225.       13468925.

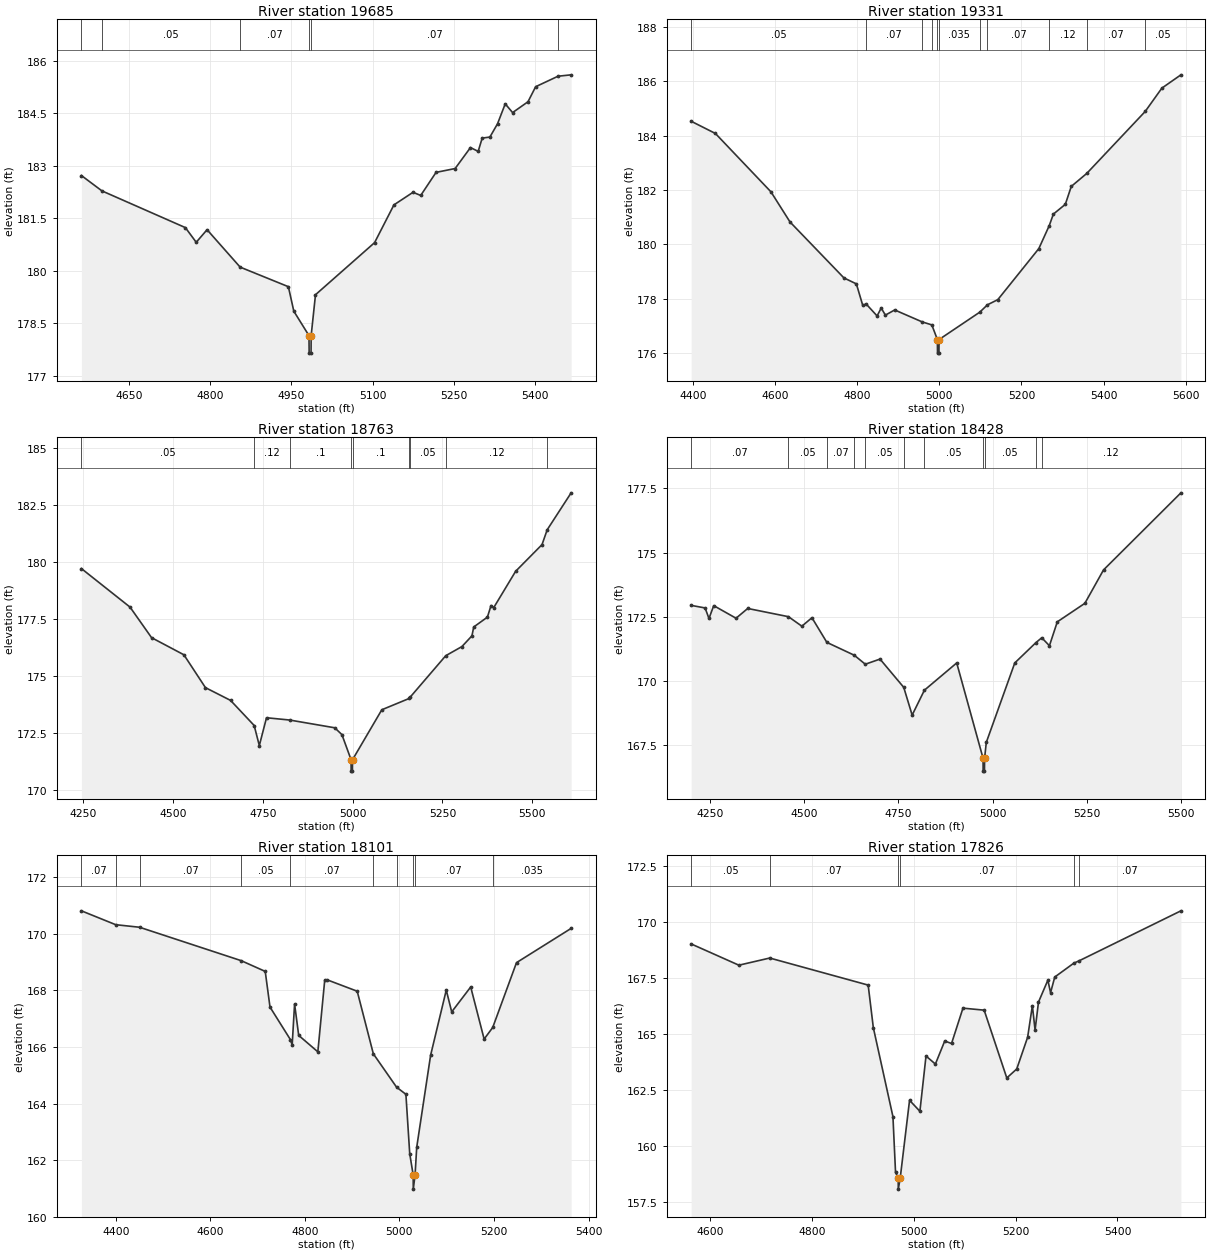
Type RM Length L Ch R = 1 ,19685   ,354,354,354
BEGIN DESCRIPTION:
GOBBLER CREEK 43.0
END DESCRIPTION:
XS GIS Cut Line= 3
        2532475.     13478966.84        2532475.       13478525.
      2532162.21     13478185.58
#Sta/Elev= 30
  4562.6  182.72  4600.5  182.28  4754.4  181.23  4774.4  180.81  4794.4  181.17
  4855.4   180.1  4944.4  179.54  4954.4  178.84  4982.4  178.14  4982.7  177.64
  4986.2  177.64  4986.4  178.14  4994.4  179.31  5103.4   180.8  5139.1  181.88
  5174.3  182.24  5188.5  182.15  5216.8  182.81    5252  182.92  5280.3  183.52
  5294.5  183.41  5301.9  183.79  5316.1  183.82  5330.2   184.2  5344.4  184.77
    5358  184.52  5386.4  184.83  5400.5  185.26  5441.8  185.56    5466   185.6
#Mann= 6 ,-1 , 0
  4562.6    .035       0  4600.5     .05       0  4855.4     .07       0
  4982.4     .05       0  4986.4     .07       0  5441.8     .05       0
Bank Sta=4982.4,4986.4
XS Rating Curve= 0 ,0
Exp/Cntr=0.3,0.1

Type RM Length L Ch R = 1 ,19331   ,568,568,568
BEGIN DESCRIPTION:
GOBBLER CREEK 42.0
END DESCRIPTION:
XS GIS Cut Line= 3
      2532835.77     13478943.49      2532755.21     13478345.09
      2532287.03     13477988.85
#Sta/Elev= 30
  4396.2  184.53  4455.2  184.08  4590.4  181.93  4636.8  180.82    4768  178.76
  4798.3  178.54  4813.8  177.75  4822.1   177.8  4848.7  177.36  4858.8  177.65
  4868.9  177.39  4891.6  177.58  4958.5  177.14  4981.9  177.03  4995.5  176.49
  4995.8  175.99  4999.3  175.99  4999.5  176.49  5098.8   177.5  5117.4  177.77
  5142.6  177.96  5242.4  179.84  5267.9  180.69  5277.8  181.11  5306.9  181.47
  5321.4  182.13  5359.2  182.61  5501.3  184.89  5541.9  185.75  5588.3  186.24
#Mann= 11 ,-1 , 0
  4396.2     .05       0  4822.1     .07       0  4958.5     .05       0
  4981.9    .035       0  4995.5    .035       0  4999.5    .035       0
  5098.8     .05       0  5117.4     .07       0  5267.9     .12       0
  5359.2     .07       0  5501.3     .05       0
Bank Sta=4995.5,4999.5
XS Rating Curve= 0 ,0
Exp/Cntr=0.3,0.1

Type RM Length L Ch R = 1 ,18763   ,335,335,335
BEGIN DESCRIPTION:
GOBBLER CREEK 41.0
END DESCRIPTION:
XS GIS Cut Line= 3
        2533125.     13478680.39        2533125.       13477925.
      2532524.97     13477824.99
#Sta/Elev= 30
  4244.6  179.71    4380  178.02    4440  176.68    4530  175.93    4590  174.49
    4660  173.93  4725.7  172.83    4740  171.95    4760  173.17  4824.4  173.07
    4950  172.73    4970  172.43  4995.5  171.33  4995.7  170.83  4999.2  170.83
  4999.5  171.33  5081.1  173.52    5158  174.02  5159.9  174.07  5259.1  175.89
  5304.1  176.29    5332  176.76  5337.1  177.15  5375.1  177.58  5385.2  178.09
  5392.8     178  5453.7  179.59  5527.2  180.76  5541.6  181.41  5608.3  183.03
#Mann= 9 ,-1 , 0
  4244.6     .05       0  4725.7     .12       0  4824.4      .1       0
  4995.5     .05       0  4999.5      .1       0    5158    .035       0
  5159.9     .05       0  5259.1     .12       0  5541.6     .05       0
Bank Sta=4995.5,4999.5
XS Rating Curve= 0 ,0
Exp/Cntr=0.3,0.1

Type RM Length L Ch R = 1 ,18428   ,327,327,327
BEGIN DESCRIPTION:
Mapping XS 97d1b9da
END DESCRIPTION:
XS GIS Cut Line= 3
      2533552.93     13478460.92      2533374.98     13477697.03
      2532959.13     13477393.81
#Sta/Elev= 30
  4200.3  172.95  4237.2  172.85  4247.5  172.44  4260.1  172.94  4319.3  172.45
  4350.3  172.83  4458.3  172.51  4493.9  172.14  4520.6  172.47  4560.2  171.51
  4632.9  171.01  4662.1  170.66  4701.2  170.86  4764.1  169.76  4786.4  168.68
  4818.9  169.65  4904.6  170.71  4974.5     167  4974.7   166.5  4978.2   166.5
  4978.5     167  4983.1  167.62  5058.6  170.71  5114.6   171.5  5130.2  171.69
  5150.5  171.38  5171.4  172.31  5244.5  173.03    5294  174.33  5499.3  177.33
#Mann= 11 ,-1 , 0
  4200.3     .07       0  4458.3     .05       0  4560.2     .07       0
  4632.9     .12       0  4662.1     .05       0  4764.1     .07       0
  4818.9     .05       0  4974.5     .05       0  4978.5     .05       0
  5114.6    .035       0  5130.2     .12       0
Bank Sta=4974.5,4978.5
XS Rating Curve= 0 ,0
Exp/Cntr=0.3,0.1

Type RM Length L Ch R = 1 ,18101   ,275,275,275
BEGIN DESCRIPTION:
Mapping XS 7bc199d8
END DESCRIPTION:
XS GIS Cut Line= 3
      2533756.92     13478239.55      2533657.09     13477579.84
      2533500.86     13477245.67
#Sta/Elev= 30
  4327.2  170.81  4399.8  170.32  4450.2  170.23  4665.2  169.05  4716.1  168.67
  4726.2  167.41  4769.4  166.26  4773.1  166.07  4778.2  167.52  4786.9  166.41
  4827.4  165.83  4841.9  168.35  4847.6  168.37  4910.7  167.97  4944.8  165.76
    4994  164.58  5013.7  164.33  5021.8  162.23  5029.1  161.48  5029.3  160.98
  5033.1  161.48  5036.6  162.46    5066  165.71  5099.1  168.01  5110.6  167.24
  5150.8  168.12  5179.2  166.28  5197.4  166.69  5247.7  168.98  5363.3  170.19
#Mann= 10 ,-1 , 0
  4327.2     .07       0  4399.8     .12       0  4450.2     .07       0
  4665.2     .05       0  4769.4     .07       0  4944.8     .05       0
    4994     .07       0  5029.1     .05       0  5033.1     .07       0
  5197.4    .035       0
Bank Sta=5029.1,5033.1
XS Rating Curve= 0 ,0
Exp/Cntr=0.3,0.1

Type RM Length L Ch R = 1 ,17826   ,519,519,519
BEGIN DESCRIPTION:
Mapping XS 94aef243
END DESCRIPTION:
XS GIS Cut Line= 3
      2533947.88     13478057.22      2533865.43     13477579.84
      2533700.48     13477132.75
#Sta/Elev= 30
  4563.5  169.03  4657.1  168.08  4717.7   168.4  4910.8  167.19  4920.9  165.29
  4959.4  161.31  4964.5  158.82  4969.7  158.57  4969.9  158.07  4973.7  158.57
    4992  162.04  5012.3  161.55  5024.3  164.02  5042.7  163.66    5061  164.69
  5074.4  164.58  5096.8  166.16  5138.4  166.07  5182.8  163.04  5202.3  163.44
  5223.7  164.86    5233  166.27  5238.3  165.18    5245  166.43  5263.4  167.41
  5268.7  166.85  5276.9  167.55  5314.3  168.17  5324.2  168.27  5524.5  170.51
#Mann= 6 ,-1 , 0
  4563.5     .05       0  4717.7     .07       0  4969.7     .05       0
  4973.7     .07       0  5314.3     .12       0  5324.2     .07       0
Bank Sta=4969.7,4973.7
XS Rating Curve= 0 ,0
Exp/Cntr=0.3,0.1

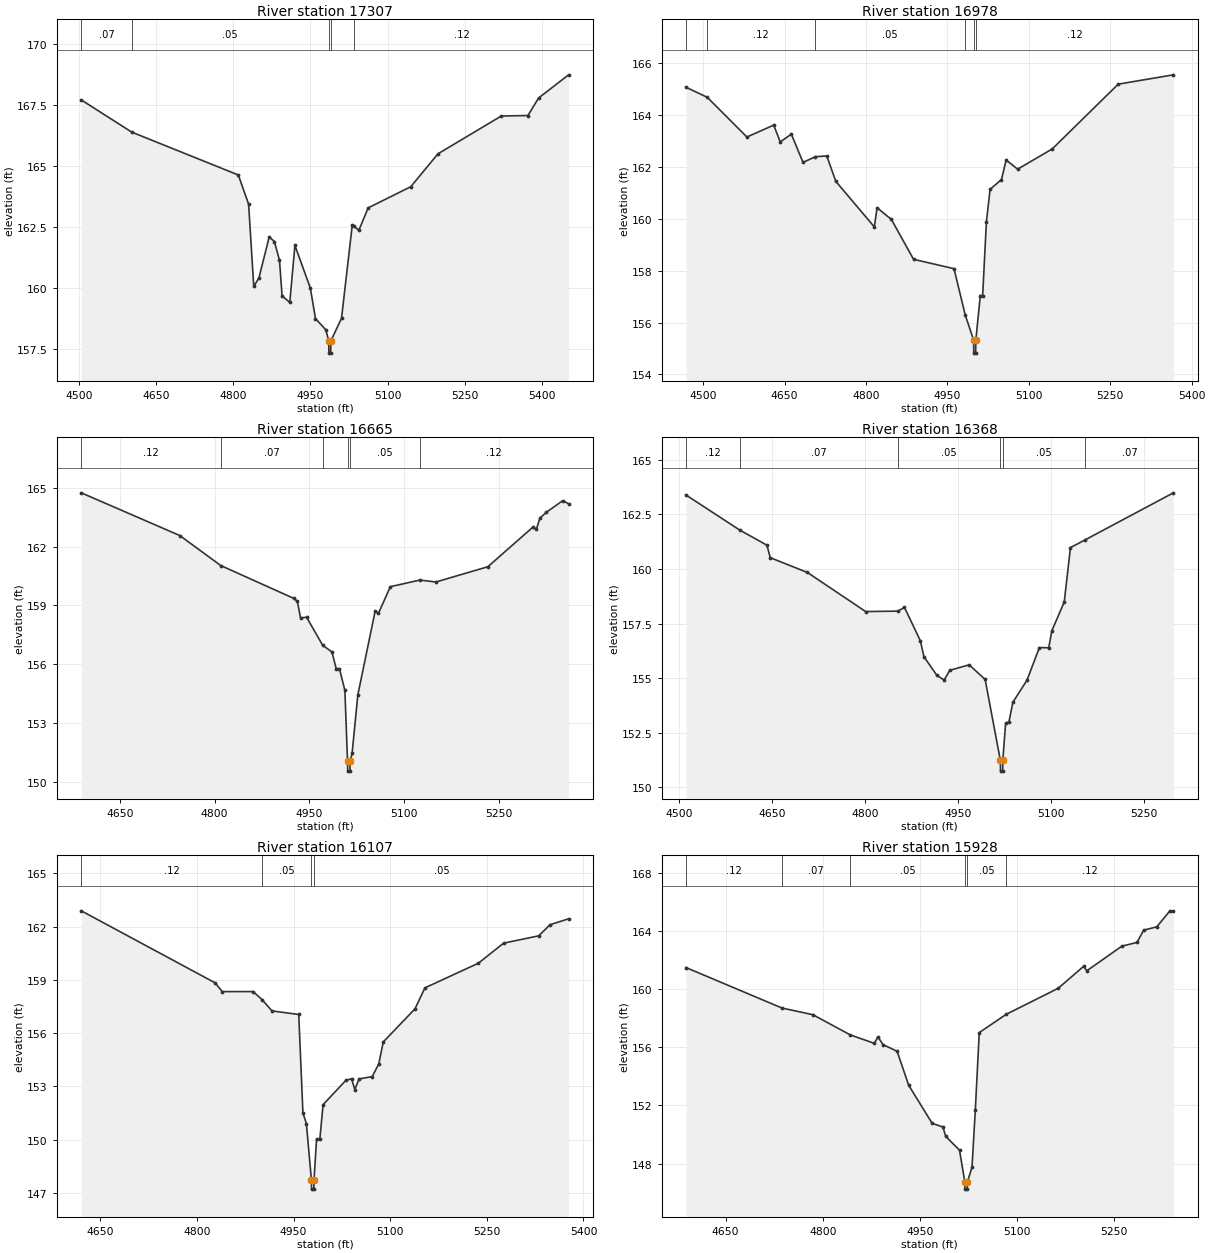
Type RM Length L Ch R = 1 ,17307   ,329,329,329
BEGIN DESCRIPTION:
Mapping XS 55d4ca56
END DESCRIPTION:
XS GIS Cut Line= 3
      2534256.05     13477970.42      2534273.41     13477484.35
      2534152.24     13477038.61
#Sta/Elev= 30
  4504.1  167.71  4602.2  166.39  4809.7  164.63  4829.7  163.43  4839.7  160.06
  4849.7   160.4  4869.8  162.09  4879.8   161.9  4889.8  161.13  4894.8  159.67
  4909.8   159.4  4919.8  161.74  4949.8  159.99  4959.8  158.74  4979.8  158.28
  4985.7  157.82  4985.9  157.32  4989.4  157.32  4989.7  157.82  5010.5  158.75
  5031.3  162.56  5035.2  162.52  5044.2  162.36  5062.3  163.28  5145.3  164.15
  5198.2   165.5  5321.4  167.05  5373.2  167.07    5394  167.79  5452.4  168.74
#Mann= 5 ,-1 , 0
  4504.1     .07       0  4602.2     .05       0  4985.7     .05       0
  4989.7     .05       0  5035.2     .12       0
Bank Sta=4985.7,4989.7
XS Rating Curve= 0 ,0
Exp/Cntr=0.3,0.1

Type RM Length L Ch R = 1 ,16978   ,313,313,313
BEGIN DESCRIPTION:
Mapping XS 5bdac861
END DESCRIPTION:
XS GIS Cut Line= 3
      2534655.36     13477844.59      2534538.17     13477310.74
      2534339.25     13477021.02
#Sta/Elev= 30
  4468.3  165.08  4507.6  164.69  4580.5  163.16  4629.9  163.62  4641.9  162.97
  4662.4  163.27  4683.9  162.18  4706.7   162.4  4727.7  162.43  4744.3  161.45
  4815.3  159.69  4820.4  160.43  4846.7  159.98  4887.6  158.44  4962.1  158.08
  4982.7   156.3  4998.3  155.32  4998.5  154.82    5002  154.82  5002.3  155.32
  5010.6  157.04  5014.9  157.04  5021.8  159.89  5028.6  161.14  5049.6  161.52
  5058.2  162.27  5079.4  161.92  5143.1   162.7  5264.7   165.2  5366.3  165.56
#Mann= 6 ,-1 , 0
  4468.3     .05       0  4507.6     .12       0  4706.7     .05       0
  4982.7     .12       0  4998.3     .05       0  5002.3     .12       0
Bank Sta=4998.3,5002.3
XS Rating Curve= 0 ,0
Exp/Cntr=0.3,0.1

Type RM Length L Ch R = 1 ,16665   ,297,297,297
BEGIN DESCRIPTION:
Mapping XS 35186845
END DESCRIPTION:
XS GIS Cut Line= 3
      2534859.35     13477740.42      2534824.63     13477336.78
      2534737.81     13476980.85
#Sta/Elev= 30
  4588.9  164.74  4744.9  162.56  4809.7  161.03  4925.6  159.35    4931   159.2
    4936  158.36  4945.6  158.39  4971.1  156.96  4985.8  156.62  4992.4  155.77
  4997.5  155.77  5006.2  154.66  5010.4  151.04  5010.7  150.54  5014.2  150.54
  5014.4  151.04  5017.6  151.44  5026.7  154.43  5054.1   158.7  5059.3  158.59
  5078.2  159.95    5125  160.29  5150.3  160.19  5232.6  160.97  5304.2     163
  5309.4  162.88    5315  163.45  5325.2  163.75  5351.1  164.34  5360.4  164.18
#Mann= 6 ,-1 , 0
  4588.9     .12       0  4809.7     .07       0  4971.1     .05       0
  5010.4     .05       0  5014.4     .05       0    5125     .12       0
Bank Sta=5010.4,5014.4
XS Rating Curve= 0 ,0
Exp/Cntr=0.3,0.1

Type RM Length L Ch R = 1 ,16368   ,261,261,261
BEGIN DESCRIPTION:
Mapping XS 08042908
END DESCRIPTION:
XS GIS Cut Line= 3
      2534941.82     13477692.66      2535093.73     13477184.87
       2535076.4     13476929.38
#Sta/Elev= 30
  4511.3  163.39  4598.2  161.78  4641.9  161.09  4647.1  160.52  4707.2  159.84
  4801.1  158.05  4852.7  158.07  4863.7  158.24  4889.3  156.71  4895.1  155.98
  4915.9  155.13  4927.6  154.91  4936.8  155.36  4968.1  155.61  4993.8  154.94
  5018.3  151.24  5018.6  150.74  5022.1  150.74  5022.3  151.24  5026.9  152.95
  5032.1  152.98  5038.6   153.9  5061.2   154.9  5081.3   156.4  5096.4  156.39
  5101.4  157.17  5121.4  158.49  5131.4  160.98  5155.4  161.34  5297.4  163.49
#Mann= 6 ,-1 , 0
  4511.3     .12       0  4598.2     .07       0  4852.7     .05       0
  5018.3     .05       0  5022.3     .05       0  5155.4     .07       0
Bank Sta=5018.3,5022.3
XS Rating Curve= 0 ,0
Exp/Cntr=0.3,0.1

Type RM Length L Ch R = 1 ,16107   ,179,179,179
BEGIN DESCRIPTION:
Mapping XS 67f02133
END DESCRIPTION:
XS GIS Cut Line= 3
      2535059.02     13477727.38      2535197.89     13477388.87
      2535280.35     13477006.96
#Sta/Elev= 30
  4620.4  162.89  4828.3  158.83  4839.2  158.34  4887.1  158.34    4901  157.89
  4916.5  157.25    4958  157.05  4964.5   151.5  4969.9   150.9  4977.7  147.71
  4977.9  147.21  4981.4  147.21  4981.7  147.71  4985.7  150.04  4990.8  150.04
  4995.8  151.97  5031.2  153.34    5040  153.43  5045.1  152.82  5051.6  153.42
  5072.1  153.55  5082.3  154.27  5089.2   155.5  5138.5  157.37  5153.9  158.55
    5237  159.94  5276.1  161.07  5330.5  161.48  5348.3  162.11    5377  162.44
#Mann= 4 ,-1 , 0
  4620.4     .12       0    4901     .05       0  4977.7     .05       0
  4981.7     .05       0
Bank Sta=4977.7,4981.7
XS Rating Curve= 0 ,0
Exp/Cntr=0.3,0.1

Type RM Length L Ch R = 1 ,15928   ,215,215,215
BEGIN DESCRIPTION:
Mapping XS a2be9f8a
END DESCRIPTION:
XS GIS Cut Line= 3
      2535206.56     13477705.74      2535362.82     13477332.44
      2535423.55     13476989.77
#Sta/Elev= 30
  4588.8  161.47  4736.9  158.69  4784.7  158.23  4842.6  156.84  4879.7  156.26
  4885.2  156.71  4893.1  156.17  4914.8  155.72  4932.7  153.38    4969  150.76
  4985.7  150.51  4989.8  149.87  5011.2  148.92  5019.4  146.74  5019.6  146.24
  5023.1  146.24  5023.4  146.74  5030.5  147.74  5035.6  151.65  5041.7     157
  5083.5  158.26  5163.5  160.04  5202.8  161.55  5207.9  161.25  5261.9  162.94
  5285.4   163.2  5295.6  164.04  5315.9  164.27  5336.2  165.37  5341.5  165.35
#Mann= 6 ,-1 , 0
  4588.8     .12       0  4736.9     .07       0  4842.6     .05       0
  5019.4     .05       0  5023.4     .05       0  5083.5     .12       0
Bank Sta=5019.4,5023.4
XS Rating Curve= 0 ,0
Exp/Cntr=0.3,0.1

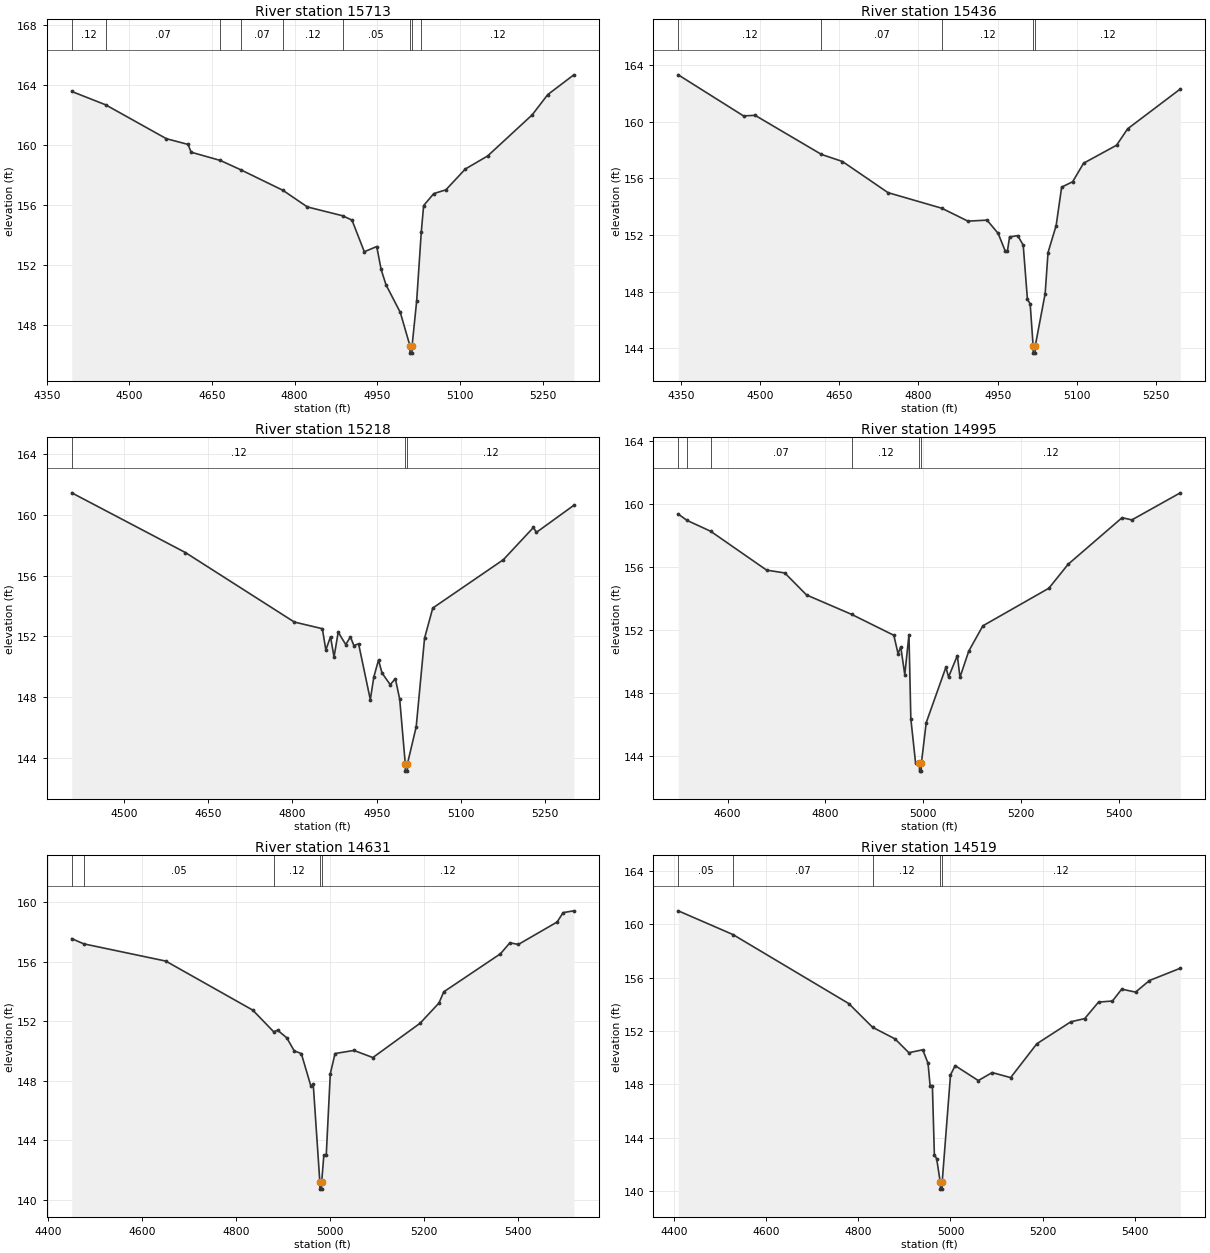
Type RM Length L Ch R = 1 ,15713   ,277,277,277
BEGIN DESCRIPTION:
Mapping XS 1da31097
END DESCRIPTION:
XS GIS Cut Line= 3
      2535296.18     13477918.39      2535560.07     13477383.66
      2535639.68     13477079.09
#Sta/Elev= 30
  4395.5  163.58    4457  162.69  4567.2  160.43  4606.5  160.05  4612.1  159.53
  4665.1  158.98    4702  158.36  4778.6  156.99    4823  155.88  4887.1  155.29
    4904     155  4926.4  152.89  4948.9  153.24  4956.9  151.71  4965.7  150.69
  4991.7  148.84  5009.1  146.63  5009.3  146.13  5012.8  146.13  5013.1  146.63
  5021.4  149.62  5029.7  154.18    5034  155.97  5052.4  156.77  5074.4  157.02
  5109.7  158.41  5150.2  159.28    5231  162.02  5259.2  163.37  5306.6  164.69
#Mann= 9 ,-1 , 0
  4395.5     .12       0    4457     .07       0  4665.1     .12       0
    4702     .07       0  4778.6     .12       0  4887.1     .05       0
  5009.1     .05       0  5013.1     .05       0  5029.7     .12       0
Bank Sta=5009.1,5013.1
XS Rating Curve= 0 ,0
Exp/Cntr=0.3,0.1

Type RM Length L Ch R = 1 ,15436   ,218,218,218
BEGIN DESCRIPTION:
Mapping XS 375a39fe
END DESCRIPTION:
XS GIS Cut Line= 3
      2535421.18     13478064.22      2535778.82      13477553.8
      2535868.78     13477238.94
#Sta/Elev= 30
  4345.1  163.31  4468.7  160.41  4490.7  160.45  4616.3  157.69  4656.1  157.19
  4742.4  154.99  4844.2  153.89  4893.6  152.98  4929.8  153.05  4950.8  152.12
  4964.6  150.84  4968.3  150.84  4972.5  151.86  4987.9  151.96  4998.3  151.29
  5006.3  147.46  5011.5  147.14  5017.1  144.16  5017.3  143.66  5020.8  143.66
  5021.1  144.16  5039.9  147.87  5045.3  150.76  5060.7  152.67  5071.1  155.38
  5091.9  155.76  5112.7  157.07  5175.1  158.34  5196.1   159.5  5295.8  162.31
#Mann= 5 ,-1 , 0
  4345.1     .12       0  4616.3     .07       0  4844.2     .12       0
  5017.1     .05       0  5021.1     .12       0
Bank Sta=5017.1,5021.1
XS Rating Curve= 0 ,0
Exp/Cntr=0.3,0.1

Type RM Length L Ch R = 1 ,15218   ,223,223,223
BEGIN DESCRIPTION:
Mapping XS 28d92512
END DESCRIPTION:
XS GIS Cut Line= 3
      2535570.49      13478154.5      2535914.24     13477696.16
      2536035.27     13477398.77
#Sta/Elev= 30
    4407  161.45  4609.4  157.52  4803.2  152.95  4853.2  152.51  4859.4  151.11
  4867.7  151.98    4874  150.65  4881.4  152.28  4894.8  151.47  4903.2  151.97
  4909.4   151.4  4917.7  151.52  4938.6  147.84  4944.8  149.33  4953.2  150.45
  4959.4   149.6    4974  148.83  4983.2  149.22  4990.9  147.88  5000.8  143.64
    5001  143.14  5004.5  143.14  5004.8  143.64  5020.3  146.06  5035.2  151.89
  5049.8  153.87  5175.5  157.05    5229  159.17  5234.4  158.85    5301  160.63
#Mann= 3 ,-1 , 0
    4407     .12       0  5000.8     .05       0  5004.8     .12       0
Bank Sta=5000.8,5004.8
XS Rating Curve= 0 ,0
Exp/Cntr=0.3,0.1

Type RM Length L Ch R = 1 ,14995   ,364,364,364
BEGIN DESCRIPTION:
Mapping XS 6a2b343a
END DESCRIPTION:
XS GIS Cut Line= 4
       2535778.8     13478300.37      2535990.63     13477873.25
      2536150.35     13477508.66      2536157.29     13477355.93
#Sta/Elev= 30
  4498.8  159.34  4516.7  158.94  4565.1  158.25  4679.7  155.78  4716.9   155.6
  4761.5   154.2  4853.6  152.97  4940.1  151.64  4948.7  150.48  4954.3   150.9
  4962.5  149.14  4971.1  151.68  4974.9  146.34  4984.6  143.54  4992.5  143.51
  4992.7  143.01  4996.2  143.01  4996.5  143.51  5006.4  146.09  5046.7  149.61
  5052.1  148.99  5070.1  150.35  5075.5  148.97  5093.4  150.63  5122.3  152.24
  5257.5  154.63  5296.8  156.15  5407.3  159.11  5427.3  158.97  5526.5  160.69
#Mann= 6 ,-1 , 0
  4498.8    .035       0  4516.7     .12       0  4565.1     .07       0
  4853.6     .12       0  4992.5     .05       0  4996.5     .12       0
Bank Sta=4992.5,4996.5
XS Rating Curve= 0 ,0
Exp/Cntr=0.3,0.1

Type RM Length L Ch R = 1 ,14631   ,112,112,112
BEGIN DESCRIPTION:
Mapping XS 83c6a7ab
END DESCRIPTION:
XS GIS Cut Line= 3
      2536160.76     13478408.01      2536296.18     13477887.14
       2536237.2     13477359.72
#Sta/Elev= 30
  4449.8  157.55  4475.2   157.2  4649.9  156.04  4835.2  152.74  4879.8  151.28
    4888  151.39  4907.5  150.88  4923.4     150  4938.5  149.82  4958.7  147.65
  4963.9  147.75  4977.9   141.2  4978.1   140.7  4981.6   140.7  4981.9   141.2
  4986.5     143  4991.6     143  5000.2  148.46  5010.3  149.82  5050.5  150.03
  5090.8  149.55  5191.4  151.86  5231.6  153.22  5241.7  153.97  5362.4  156.53
  5382.6  157.27  5400.6  157.16  5483.2  158.67  5495.9   159.3  5518.7  159.42
#Mann= 5 ,-1 , 0
  4449.8     .07       0  4475.2     .05       0  4879.8     .12       0
  4977.9     .05       0  4981.9     .12       0
Bank Sta=4977.9,4981.9
XS Rating Curve= 0 ,0
Exp/Cntr=0.3,0.1

Type RM Length L Ch R = 1 ,14519   ,383,383,383
BEGIN DESCRIPTION:
Mapping XS addaec5b
END DESCRIPTION:
XS GIS Cut Line= 3
      2536362.16     13478463.49      2536410.77     13477918.39
       2536362.3     13477378.32
#Sta/Elev= 30
  4409.2  161.02  4527.9  159.24  4779.2  154.06  4830.9  152.28  4879.5  151.41
  4909.7  150.37  4939.8  150.59  4951.3  149.57  4955.7   147.9  4960.7   147.9
    4965  142.72    4970  142.41  4977.9  140.63  4978.2  140.13  4981.7  140.13
  4981.9  140.63    5000   148.7  5010.1   149.4  5060.3  148.28  5090.4  148.88
  5130.5   148.5  5187.3  151.04  5261.1  152.69  5291.2  152.93  5321.3  154.17
  5351.4  154.25  5371.5  155.14  5401.6  154.92  5431.8  155.79  5498.7  156.71
#Mann= 5 ,-1 , 0
  4409.2     .05       0  4527.9     .07       0  4830.9     .12       0
  4977.9     .05       0  4981.9     .12       0
Bank Sta=4977.9,4981.9
XS Rating Curve= 0 ,0
Exp/Cntr=0.3,0.1

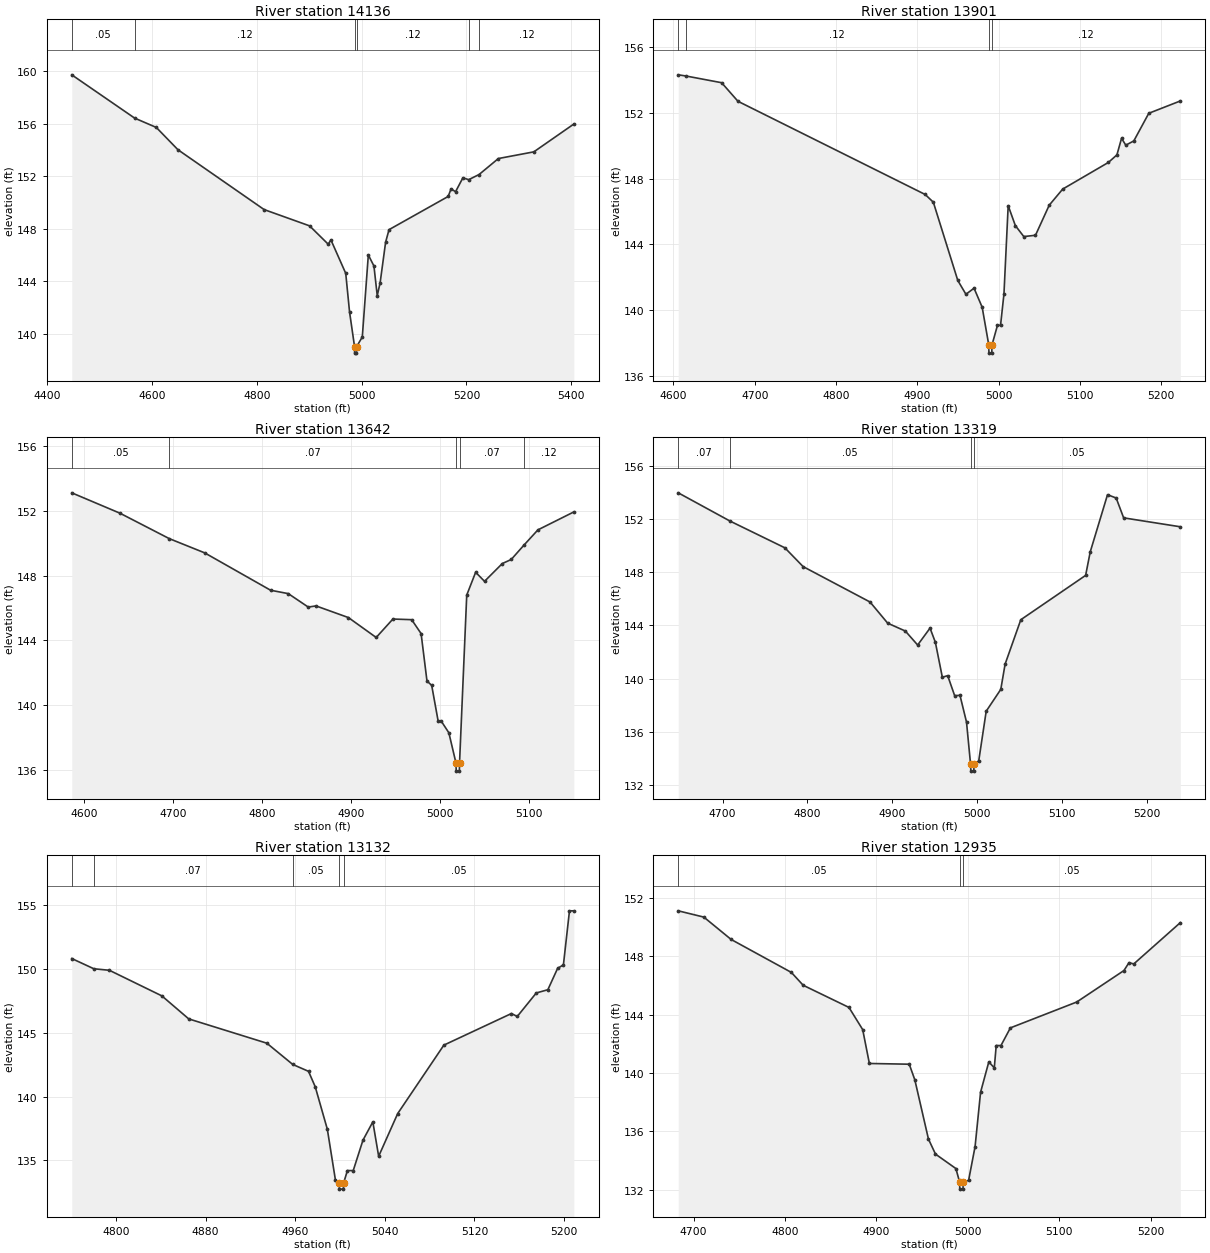
Type RM Length L Ch R = 1 ,14136   ,235,235,235
BEGIN DESCRIPTION:
Mapping XS 0482672d
END DESCRIPTION:
XS GIS Cut Line= 3
      2536782.29     13478241.26      2536646.88     13477713.53
      2536466.33     13477342.01
#Sta/Elev= 30
    4447  159.72    4567  156.42  4608.3  155.71  4649.6  154.01    4814  149.45
  4900.7  148.21  4936.3  146.81  4941.4  147.14  4969.7  144.59    4977  141.64
  4986.5  139.01  4986.7  138.51  4990.2  138.51  4990.5  139.01  5001.3  139.74
  5012.8  145.99  5023.5  145.15  5029.8  142.89  5035.3  143.87  5045.8  146.97
  5052.3  147.92  5165.1  150.45  5170.7  151.03  5179.2  150.81  5193.2  151.87
  5204.3  151.73    5224  152.12  5260.9  153.34  5328.6  153.85  5404.9  155.97
#Mann= 6 ,-1 , 0
    4447     .05       0    4567     .12       0  4986.5     .05       0
  4990.5     .12       0  5204.3     .07       0    5224     .12       0
Bank Sta=4986.5,4990.5
XS Rating Curve= 0 ,0
Exp/Cntr=0.3,0.1

Type RM Length L Ch R = 1 ,13901   ,259,259,259
BEGIN DESCRIPTION:
Mapping XS 68259ce5
END DESCRIPTION:
XS GIS Cut Line= 3
      2536875.95     13478018.33      2536851.65     13477622.49
      2536789.97     13477410.05
#Sta/Elev= 30
  4605.9  154.32  4615.3  154.25  4659.3  153.84  4679.4  152.71  4909.8  147.04
  4919.8  146.57  4949.9  141.81  4959.9  140.97  4969.9  141.34  4979.9  140.18
    4988  137.89  4988.2  137.39  4991.7  137.39    4992  137.89  4998.7  139.08
  5002.5  139.08  5006.7  140.99  5011.9  146.36  5020.7  145.15  5031.1  144.48
  5045.5  144.56  5062.4  146.39    5079  147.37  5135.2  148.99  5145.7  149.45
  5151.4  150.46  5156.6  150.04  5166.5   150.3  5184.9  151.98  5223.7  152.73
#Mann= 4 ,-1 , 0
  4605.9     .07       0  4615.3     .12       0    4988     .05       0
    4992     .12       0
Bank Sta=4988,4992
XS Rating Curve= 0 ,0
Exp/Cntr=0.3,0.1

Type RM Length L Ch R = 1 ,13642   ,323,323,323
BEGIN DESCRIPTION:
Mapping XS ed6c7da8
END DESCRIPTION:
XS GIS Cut Line= 3
      2536959.29     13477966.23       2537094.7     13477573.88
      2537091.23     13477424.58
#Sta/Elev= 30
  4585.9  153.11  4640.1  151.85  4695.5  150.28  4735.3   149.4  4809.4  147.09
  4829.3  146.88  4851.7  146.05  4860.5  146.12  4896.9   145.4  4928.1  144.17
  4946.9  145.31    4968  145.27  4978.6  144.41  4985.2  141.48  4990.5  141.21
  4997.7  139.02    5001  139.02  5009.8  138.28  5017.8  136.41  5018.1  135.91
  5021.6  135.91  5021.8  136.41  5029.9  146.79  5039.9   148.2  5049.9  147.64
  5069.9  148.74  5079.9  148.99  5094.1  149.87  5109.9  150.82  5150.3  151.93
#Mann= 5 ,-1 , 0
  4585.9     .05       0  4695.5     .07       0  5017.8     .05       0
  5021.8     .07       0  5094.1     .12       0
Bank Sta=5017.8,5021.8
XS Rating Curve= 0 ,0
Exp/Cntr=0.3,0.1

Type RM Length L Ch R = 1 ,13319   ,187,187,187
BEGIN DESCRIPTION:
Mapping XS fecd5c85
END DESCRIPTION:
XS GIS Cut Line= 3
      2537119.01     13478014.85      2537334.29      13477733.6
      2537382.89       13477501.
#Sta/Elev= 30
  4647.7  153.95  4708.7  151.83  4773.4  149.82  4794.9  148.41  4873.8  145.75
  4894.6  144.16  4915.4  143.57  4929.9  142.52  4944.5  143.79  4950.8  142.72
    4959   140.1  4965.3  140.22  4973.5  138.72  4979.8  138.74  4987.5  136.73
  4992.3  133.55  4992.6  133.05  4996.1  133.05  4996.3  133.55  5001.9  133.82
  5010.7  137.55  5027.9  139.19    5033  141.09  5051.5  144.42  5127.9  147.75
  5133.3  149.51  5153.7  153.81  5163.9  153.56  5172.7  152.07  5239.5   151.4
#Mann= 4 ,-1 , 0
  4647.7     .07       0  4708.7     .05       0  4992.3     .05       0
  4996.3     .05       0
Bank Sta=4992.3,4996.3
XS Rating Curve= 0 ,0
Exp/Cntr=0.3,0.1

Type RM Length L Ch R = 1 ,13132   ,197,197,197
BEGIN DESCRIPTION:
Mapping XS 33f05cdb
END DESCRIPTION:
XS GIS Cut Line= 3
      2537400.25     13478046.13      2537494.01     13477816.94
      2537542.63     13477622.45
#Sta/Elev= 30
  4760.6  150.79  4780.3  149.99  4794.2  149.87    4841  147.87    4865  146.07
  4934.7  144.17  4957.8  142.51  4971.9  141.97  4977.9  140.76  4988.7  137.44
  4995.9  133.48  4999.3  133.26  4999.5  132.76    5003  132.76  5003.3  133.26
  5006.6  134.21  5011.8  134.21  5020.5  136.59  5029.3  138.02  5034.5  135.33
  5051.5  138.67  5092.7  144.02    5153  146.49  5158.2  146.26  5175.2   148.1
  5185.5  148.35  5194.2  150.02  5199.4   150.3  5204.8  154.52  5208.7  154.52
#Mann= 5 ,-1 , 0
  4760.6     .05       0  4780.3     .07       0  4957.8     .05       0
  4999.3     .05       0  5003.3     .05       0
Bank Sta=4999.3,5003.3
XS Rating Curve= 0 ,0
Exp/Cntr=0.3,0.1

Type RM Length L Ch R = 1 ,12935   ,198,198,198
BEGIN DESCRIPTION:
Mapping XS bf9334d9
END DESCRIPTION:
XS GIS Cut Line= 3
      2537507.88     13478098.21      2537702.34     13477809.99
      2537754.43     13477615.53
#Sta/Elev= 30
  4683.3  151.11  4711.3  150.68  4741.1  149.15    4807  146.89  4819.9  146.01
    4870  144.49    4885  142.97  4892.3  140.65  4935.9   140.6    4942  139.53
  4956.9  135.47  4964.6  134.44  4986.9  133.45  4990.9  132.54  4991.2  132.04
  4994.7  132.04  4994.9  132.54  5000.8  132.64  5007.9  134.96  5013.9  138.68
  5022.9  140.76  5028.9  140.35    5031  141.88  5036.2  141.88  5046.5  143.09
    5119  144.86  5170.7  147.02  5176.2  147.56  5181.4  147.47  5232.3   150.3
#Mann= 3 ,-1 , 0
  4683.3     .05       0  4990.9     .05       0  4994.9     .05       0
Bank Sta=4990.9,4994.9
XS Rating Curve= 0 ,0
Exp/Cntr=0.3,0.1

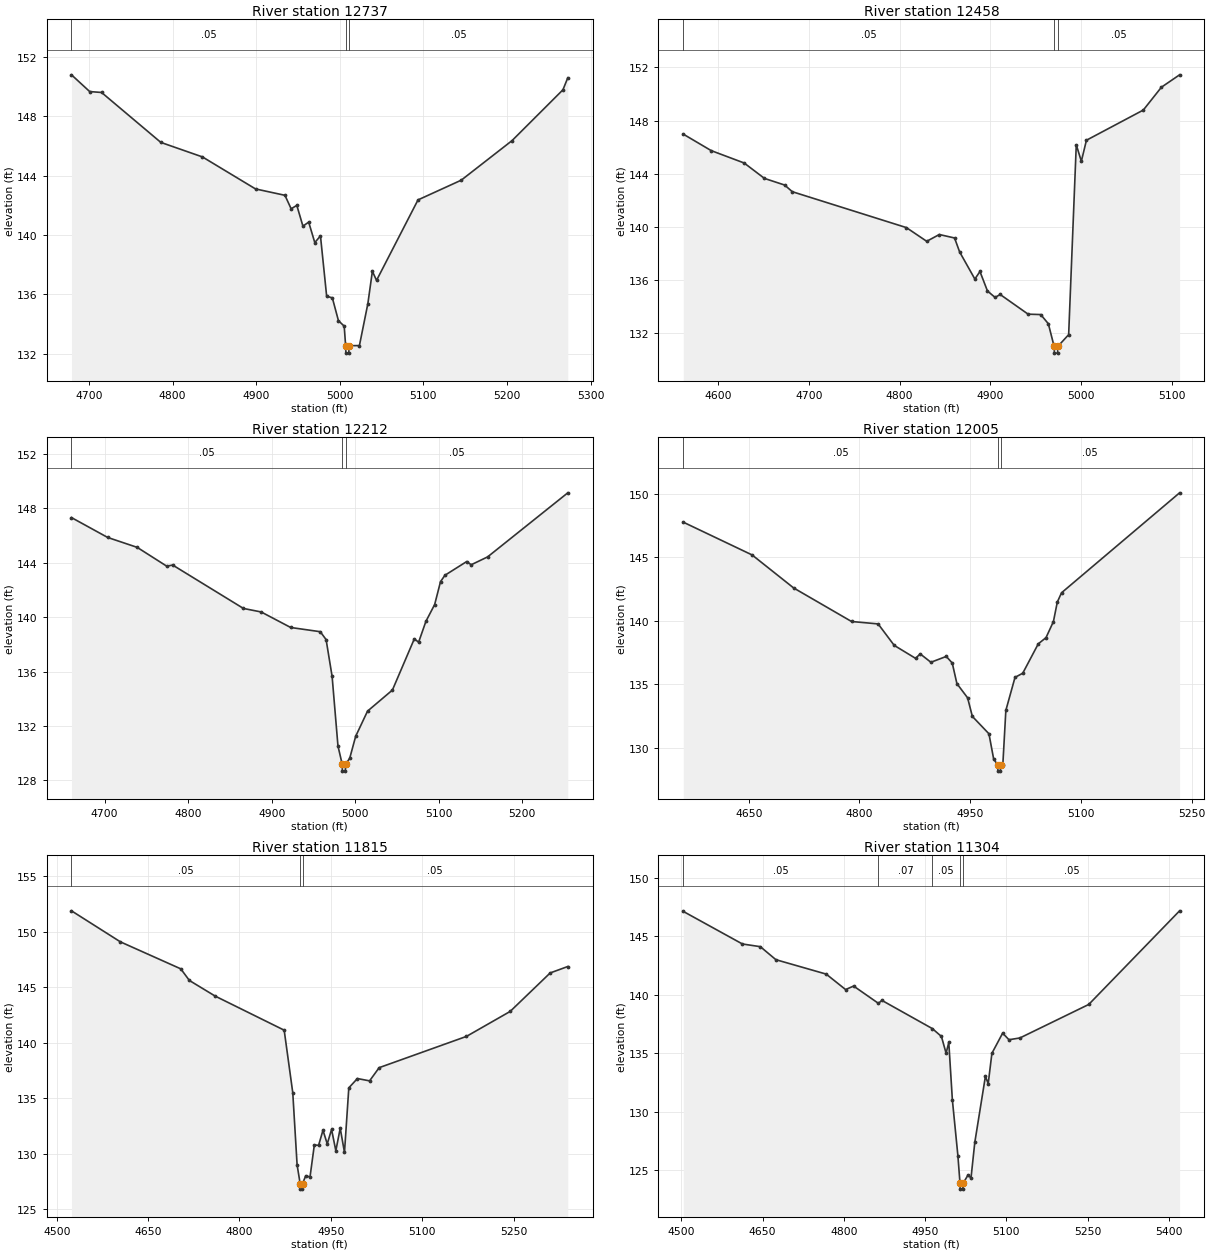
Type RM Length L Ch R = 1 ,12737   ,279,279,279
BEGIN DESCRIPTION:
Mapping XS 2bad3bbc
END DESCRIPTION:
XS GIS Cut Line= 3
      2537629.45     13478160.66      2537855.12     13477917.63
      2537899.89     13477659.33
#Sta/Elev= 30
    4679  150.81  4700.8  149.68    4715  149.62  4785.9  146.25  4835.7  145.27
  4899.2  143.11  4934.4  142.68  4941.8  141.77  4948.6     142  4955.9   140.6
  4962.8  140.87  4970.1  139.49  4976.9  139.94  4984.3  135.87  4991.1  135.76
  4998.4  134.22  5005.3  133.85    5007  132.53  5007.3  132.03  5010.8  132.03
    5011  132.53  5023.5  132.54  5033.6  135.37    5039  137.55    5044  136.94
  5093.6  142.37  5145.3   143.7  5206.1  146.37    5267   149.8  5272.8  150.61
#Mann= 3 ,-1 , 0
    4679     .05       0    5007     .05       0    5011     .05       0
Bank Sta=5007,5011
XS Rating Curve= 0 ,0
Exp/Cntr=0.3,0.1

Type RM Length L Ch R = 1 ,12458   ,246,246,246
BEGIN DESCRIPTION:
GOBBLER CREEK 27.0
END DESCRIPTION:
XS GIS Cut Line= 3
      2537874.99     13478175.03        2538075.       13477775.
        2538075.     13477675.05
#Sta/Elev= 30
  4561.5  146.98  4592.3  145.74  4628.6  144.81    4651  143.65  4673.3  143.15
  4681.7  142.65  4807.5  139.95  4829.9  138.92  4843.8  139.43  4860.6  139.17
  4866.2  138.12    4883  136.08  4888.6  136.65  4896.9  135.18  4905.3   134.7
  4910.9  134.92  4941.7  133.44  4955.6  133.41    4964  132.72  4970.4  131.01
  4970.7  130.51  4974.2  130.51  4974.4  131.01  4986.4   131.9  4994.8  146.18
  5000.4  144.94    5006  146.52  5068.7  148.79  5088.7  150.51  5108.7  151.44
#Mann= 3 ,-1 , 0
  4561.5     .05       0  4970.4     .05       0  4974.4     .05       0
Bank Sta=4970.4,4974.4
XS Rating Curve= 0 ,0
Exp/Cntr=0.3,0.1

Type RM Length L Ch R = 1 ,12212   ,207,207,207
BEGIN DESCRIPTION:
Mapping XS dc8a307b
END DESCRIPTION:
XS GIS Cut Line= 3
      2537938.44     13478219.73      2538191.93     13477969.71
      2538268.31     13477744.03
#Sta/Elev= 30
  4660.3  147.32  4703.6  145.86    4739  145.13  4774.3  143.75  4781.5  143.83
  4866.2  140.64  4887.5  140.38  4922.8  139.24  4958.2  138.93  4965.2  138.35
  4972.4  135.64  4979.4  130.53  4984.5  129.18  4984.7  128.68  4988.2  128.68
  4988.5  129.18  4993.5  129.63  5000.6  131.24  5014.8  133.09  5044.6  134.64
  5070.8   138.4    5076  138.16  5084.7  139.69  5095.2  140.93  5102.2  142.61
  5107.5  143.08  5133.6  144.09  5138.9  143.85  5158.6  144.43  5254.6  149.14
#Mann= 3 ,-1 , 0
  4660.3     .05       0  4984.5     .05       0  4988.5     .05       0
Bank Sta=4984.5,4988.5
XS Rating Curve= 0 ,0
Exp/Cntr=0.3,0.1

Type RM Length L Ch R = 1 ,12005   ,190,190,190
BEGIN DESCRIPTION:
Mapping XS 0e91989c
END DESCRIPTION:
XS GIS Cut Line= 3
      2538017.46     13478248.13      2538357.75     13477980.75
      2538430.35      13477752.6
#Sta/Elev= 30
  4561.4  147.75  4654.6  145.17  4710.9  142.57  4789.3  139.93  4825.3  139.74
  4847.1  138.05    4876  137.03  4882.3  137.38  4896.8  136.72  4917.6  137.18
  4925.7  136.66    4932  135.04  4946.5  133.92  4952.9  132.46  4975.4  131.09
  4981.8   129.1  4987.2  128.65  4987.5  128.15    4991  128.15  4991.2  128.65
  4994.2  128.65  4998.3  132.93  5010.7  135.53  5021.2  135.86  5042.2  138.17
  5052.7  138.66  5062.7  139.92    5068  141.46  5073.7  142.19  5233.6  150.06
#Mann= 3 ,-1 , 0
  4561.4     .05       0  4987.2     .05       0  4991.2     .05       0
Bank Sta=4987.2,4991.2
XS Rating Curve= 0 ,0
Exp/Cntr=0.3,0.1

Type RM Length L Ch R = 1 ,11815   ,511,511,511
BEGIN DESCRIPTION:
Mapping XS 0adc132a
END DESCRIPTION:
XS GIS Cut Line= 3
       2538077.8     13478451.61      2538421.09     13478101.66
      2538605.13     13477834.29
#Sta/Elev= 30
  4524.2   151.9  4604.6   149.1  4703.6  146.67  4717.8  145.62  4760.2  144.21
  4873.4  141.14  4887.5   135.5  4894.6     129  4899.6  127.31  4899.9  126.81
  4903.4  126.81  4903.6  127.31  4908.8  128.02  4915.8   127.9  4922.9  130.79
  4929.9  130.76  4937.1  132.12  4944.1  130.89  4951.2  132.19  4958.2  130.27
  4965.4   132.3  4972.4  130.12  4979.5  135.94  4993.6  136.78  5013.6  136.57
  5029.3  137.76  5172.7  140.58  5244.4  142.83  5310.1   146.3    5339  146.88
#Mann= 3 ,-1 , 0
  4524.2     .05       0  4899.6     .05       0  4903.6     .05       0
Bank Sta=4899.6,4903.6
XS Rating Curve= 0 ,0
Exp/Cntr=0.3,0.1

Type RM Length L Ch R = 1 ,11304   ,175,175,175
BEGIN DESCRIPTION:
Mapping XS b5bb5e42
END DESCRIPTION:
XS GIS Cut Line= 3
      2538772.27      13478715.5      2538854.28     13478206.45
      2538729.65     13477825.64
#Sta/Elev= 30
  4503.6  147.11  4612.8  144.33  4645.9   144.1  4674.6  142.99  4767.5  141.76
  4803.3  140.44  4818.1  140.74    4864  139.26  4870.2  139.52  4963.4  137.11
  4980.2  136.44  4988.8  135.01  4993.8  135.93  5000.4  131.03  5010.6  126.27
  5014.5  123.91    5015  123.41  5019.9  123.41  5020.3  123.91  5029.5  124.63
  5034.8  124.35  5041.8  127.39  5061.4  133.03  5066.6  132.42  5073.4     135
  5093.2  136.72  5104.9  136.16  5125.1  136.31  5252.2  139.17  5419.9  147.16
#Mann= 5 ,-1 , 0
  4503.6     .05       0    4864     .07       0  4963.4     .05       0
  5014.5     .05       0  5020.3     .05       0
Bank Sta=5014.5,5020.3
XS Rating Curve= 0 ,0
Exp/Cntr=0.3,0.1