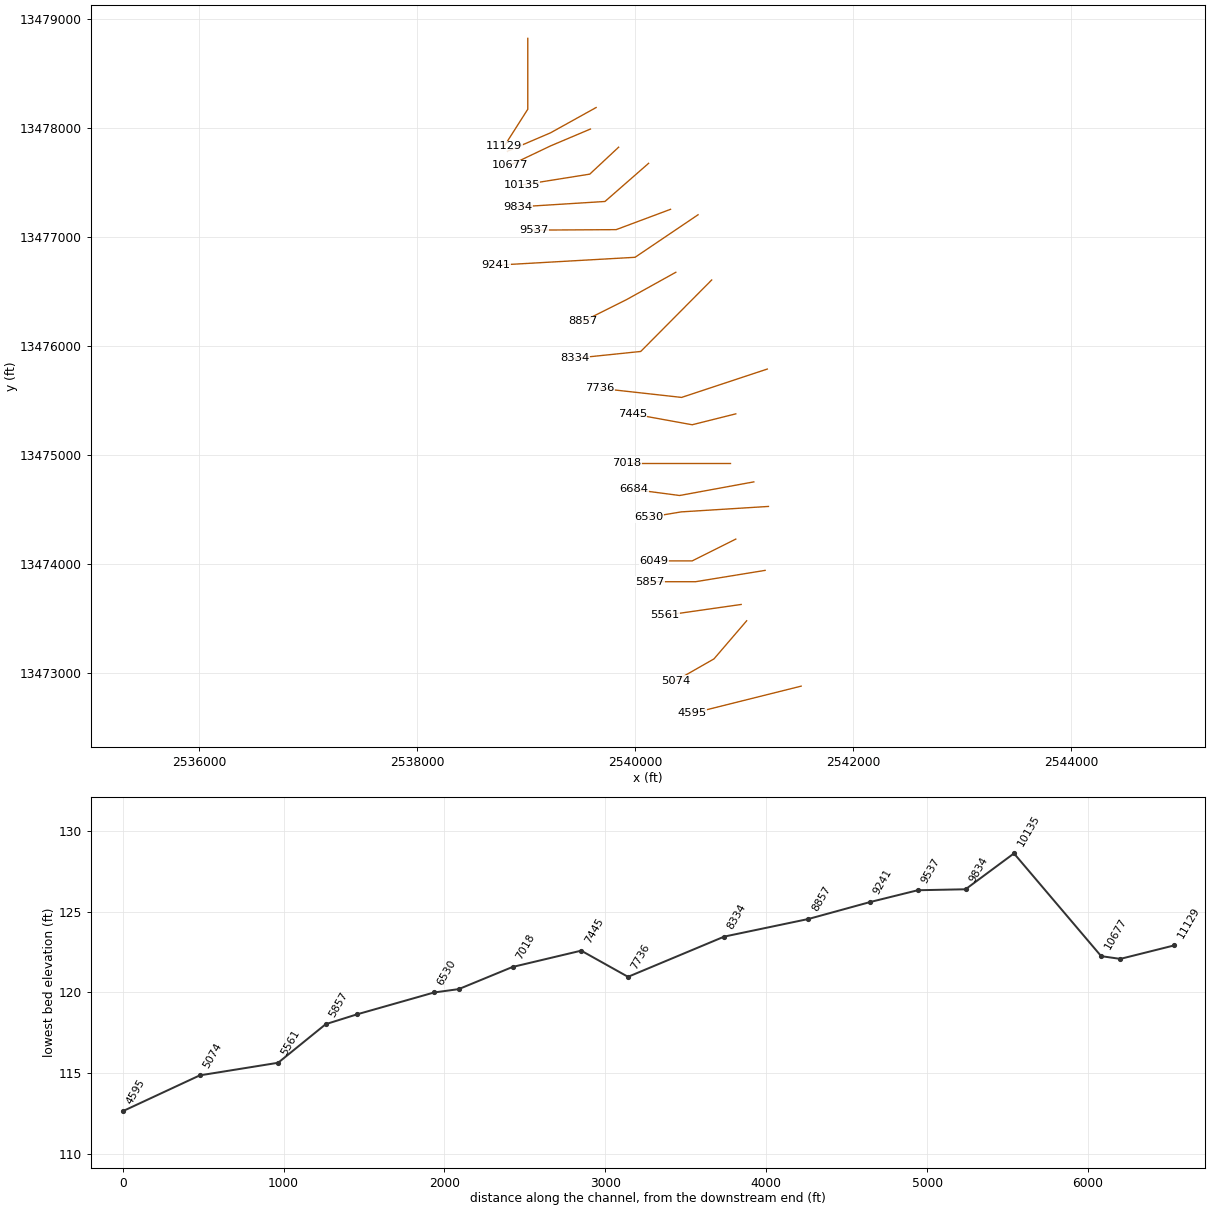
HEC-RAS study GOBBLER CREEK.prj: GOBBLER CREEK Base Level Engineering

--- GOBBLER CREEK.g01 (geometry) --- (continued)

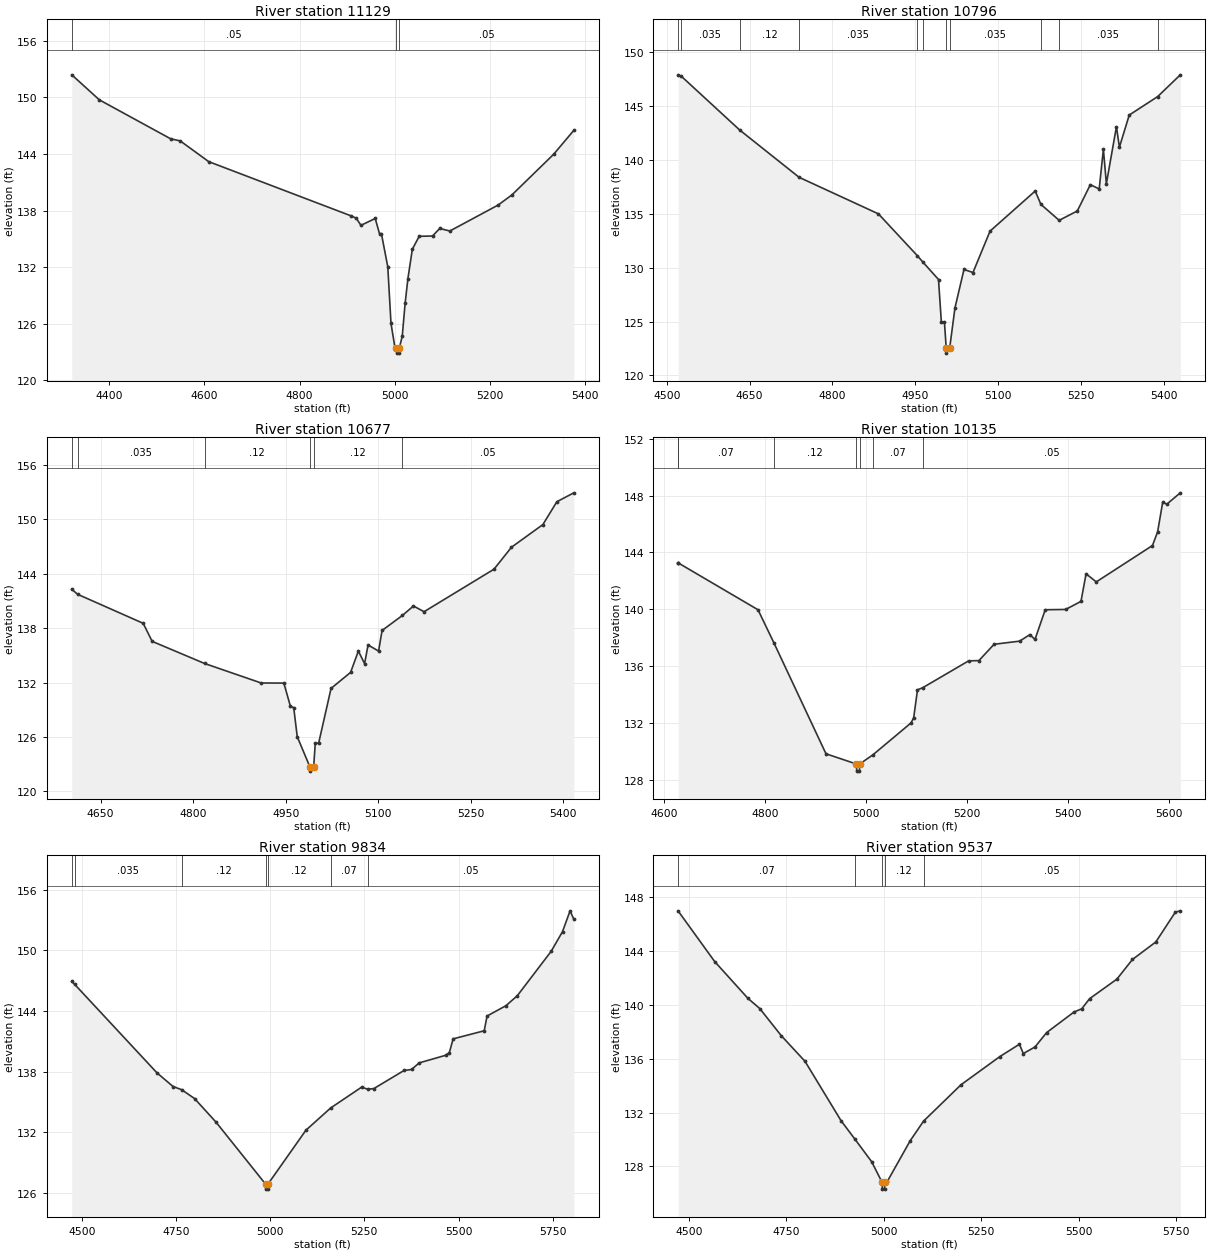
Type RM Length L Ch R = 1 ,11129   ,333,333,333
BEGIN DESCRIPTION:
Mapping XS b723673a
END DESCRIPTION:
XS GIS Cut Line= 3
      2539016.67      13478822.9      2539016.67     13478171.86
      2538799.58     13477830.72
#Sta/Elev= 30
    4321  152.39  4378.9  149.74  4528.9  145.61  4548.9  145.39  4608.9  143.19
  4908.9  137.43  4918.9   137.2  4928.9  136.44  4958.9  137.17    4968  135.53
    4972  135.53  4985.3  132.04    4992  126.06  5000.5  123.44  5003.5   123.4
    5004   122.9  5008.9   122.9  5009.3   123.4  5015.7  124.69  5021.7  128.16
  5027.6   130.8  5036.9  133.91  5051.3  135.28  5079.3  135.31  5094.5  136.11
  5115.7  135.84  5217.2  138.59  5246.1  139.66  5334.1  143.98  5376.4  146.51
#Mann= 3 ,-1 , 0
    4321     .05       0  5003.5     .05       0  5009.3     .05       0
Bank Sta=5003.5,5009.3
XS Rating Curve= 0 ,0
Exp/Cntr=0.3,0.1

Type RM Length L Ch R = 1 ,10796   ,119,119,119
BEGIN DESCRIPTION:
Mapping XS a336d041
END DESCRIPTION:
XS GIS Cut Line= 3
      2539643.75      13478187.6      2539224.92     13477954.97
      2538829.99     13477786.14
#Sta/Elev= 30
  4520.9  147.84  4525.8  147.79  4632.1  142.77  4739.7  138.38  4883.2  134.99
  4953.6  131.11  4964.3  130.48  4991.9   128.9  4997.1  124.92  5002.7  124.92
  5005.8  122.57  5006.3  122.07  5012.2  122.57  5021.7  126.27    5038  129.83
  5054.3  129.55  5085.2  133.39  5166.9  137.11  5177.2  135.87  5210.3  134.39
  5243.1  135.26  5266.7   137.7  5282.7   137.3  5290.3  140.98  5295.7  137.79
  5313.9  143.07  5319.3  141.18  5337.1  144.16  5388.5  145.87  5429.5  147.89
#Mann= 11 ,-1 , 0
  4520.9     .12       0  4525.8    .035       0  4632.1     .12       0
  4739.7    .035       0  4953.6     .12       0  4964.3    .035       0
  5005.8    .035       0  5012.2    .035       0  5177.2     .05       0
  5210.3    .035       0  5388.5     .05       0
Bank Sta=5005.8,5012.2
XS Rating Curve= 0 ,0
Exp/Cntr=0.3,0.1

Type RM Length L Ch R = 1 ,10677   ,542,542,542
BEGIN DESCRIPTION:
Mapping XS 0b9174b8
END DESCRIPTION:
XS GIS Cut Line= 3
      2539591.65     13477990.11      2539226.21      13477835.5
       2538849.7     13477656.02
#Sta/Elev= 30
  4603.2   142.3  4612.7  141.74    4719  138.54  4733.5  136.55  4818.5  134.11
  4910.2  131.96    4947  131.95  4957.6   129.4    4963  129.24  4968.7  126.04
    4989  122.74  4989.5  122.24  4995.4  122.74  4997.9  125.32  5003.4  125.32
  5023.5  131.36  5055.2  133.13  5067.8  135.48  5077.9  134.09  5083.5  136.15
  5100.6  135.48  5106.2  137.75  5139.2  139.41  5157.1  140.45  5174.3  139.82
  5287.7  144.51    5316  146.93  5366.9  149.43  5389.6  151.95  5417.1  152.93
#Mann= 6 ,-1 , 0
  4603.2     .12       0  4612.7    .035       0  4818.5     .12       0
    4989     .05       0  4995.4     .12       0  5139.2     .05       0
Bank Sta=4989,4995.4
XS Rating Curve= 0 ,0
Exp/Cntr=0.3,0.1

Type RM Length L Ch R = 1 ,10135   ,301,301,301
BEGIN DESCRIPTION:
Mapping XS f8fec2e8
END DESCRIPTION:
XS GIS Cut Line= 3
       2539850.3      13477823.5      2539585.51     13477576.07
      2538960.53     13477476.25
#Sta/Elev= 30
  4627.5  143.27  4627.8  143.25  4785.6  139.96  4816.9  137.65  4920.4  129.82
  4980.8   129.1  4981.3   128.6  4986.7   128.6  4987.2   129.1  5013.5  129.75
  5089.2     132  5094.3  132.37  5101.8  134.32  5112.6  134.48  5203.1  136.36
  5223.5  136.38  5253.7  137.53  5304.3  137.75  5324.6  138.21  5334.7  137.87
    5355  139.96  5395.5  139.98  5425.9  140.55    5436  142.49  5456.2  141.92
  5567.6  144.48  5577.8  145.44  5587.9  147.53    5596  147.39  5622.8  148.19
#Mann= 7 ,-1 , 0
  4627.5    .035       0  4627.8     .07       0  4816.9     .12       0
  4980.8     .05       0  4987.2     .12       0  5013.5     .07       0
  5112.6     .05       0
Bank Sta=4980.8,4987.2
XS Rating Curve= 0 ,0
Exp/Cntr=0.3,0.1

Type RM Length L Ch R = 1 ,9834    ,297,297,297
BEGIN DESCRIPTION:
GOBBLER CREEK 21.0
END DESCRIPTION:
XS GIS Cut Line= 3
      2540125.02     13477675.02        2539725.       13477325.
        2538925.       13477275.
#Sta/Elev= 30
  4473.1  146.93  4480.4  146.66  4699.5  137.88  4742.2  136.53  4764.9  136.22
  4799.2  135.34  4856.1  133.01  4987.6  126.88  4988.1  126.38  4993.6  126.38
  4994.1  126.88  5094.8  132.21  5160.5  134.41  5242.6  136.47  5258.8  136.27
  5275.2  136.33  5355.3  138.12  5375.4  138.22  5395.4  138.87  5465.5  139.62
  5475.6  139.88  5485.6  141.25  5568.2  142.05  5575.8  143.51  5625.8  144.53
  5655.9  145.51  5746.1  149.92  5776.1  151.86  5796.2  153.92  5806.2  153.08
#Mann= 7 ,-1 , 0
  4473.1     .07       0  4480.4    .035       0  4764.9     .12       0
  4987.6     .05       0  4994.1     .12       0  5160.5     .07       0
  5258.8     .05       0
Bank Sta=4987.6,4994.1
XS Rating Curve= 0 ,0
Exp/Cntr=0.3,0.1

Type RM Length L Ch R = 1 ,9537    ,296,296,296
BEGIN DESCRIPTION:
Mapping XS 776f5815
END DESCRIPTION:
XS GIS Cut Line= 3
      2540326.57     13477253.07      2539827.48     13477066.45
      2539072.24     13477062.11
#Sta/Elev= 30
  4473.1  146.95  4566.5  143.21  4652.1  140.47  4682.3  139.72  4737.6   137.7
  4798.2  135.81  4891.2  131.38  4926.9  130.01  4969.2  128.36  4996.2  126.82
  4996.7  126.32  5002.3  126.32  5002.8  126.82  5009.7   126.9  5068.4  129.92
  5102.6  131.37  5198.4  134.06  5298.4  136.16  5348.4  137.07  5358.4  136.38
  5388.4  136.87  5418.4  137.94  5488.4  139.46  5508.4   139.7  5528.4  140.45
  5598.4   141.9  5638.4  143.36  5698.4  144.66  5748.4  146.87  5761.2  146.97
#Mann= 5 ,-1 , 0
  4473.1     .07       0  4926.9     .12       0  4996.2     .05       0
  5002.8     .12       0  5102.6     .05       0
Bank Sta=4996.2,5002.8
XS Rating Curve= 0 ,0
Exp/Cntr=0.3,0.1

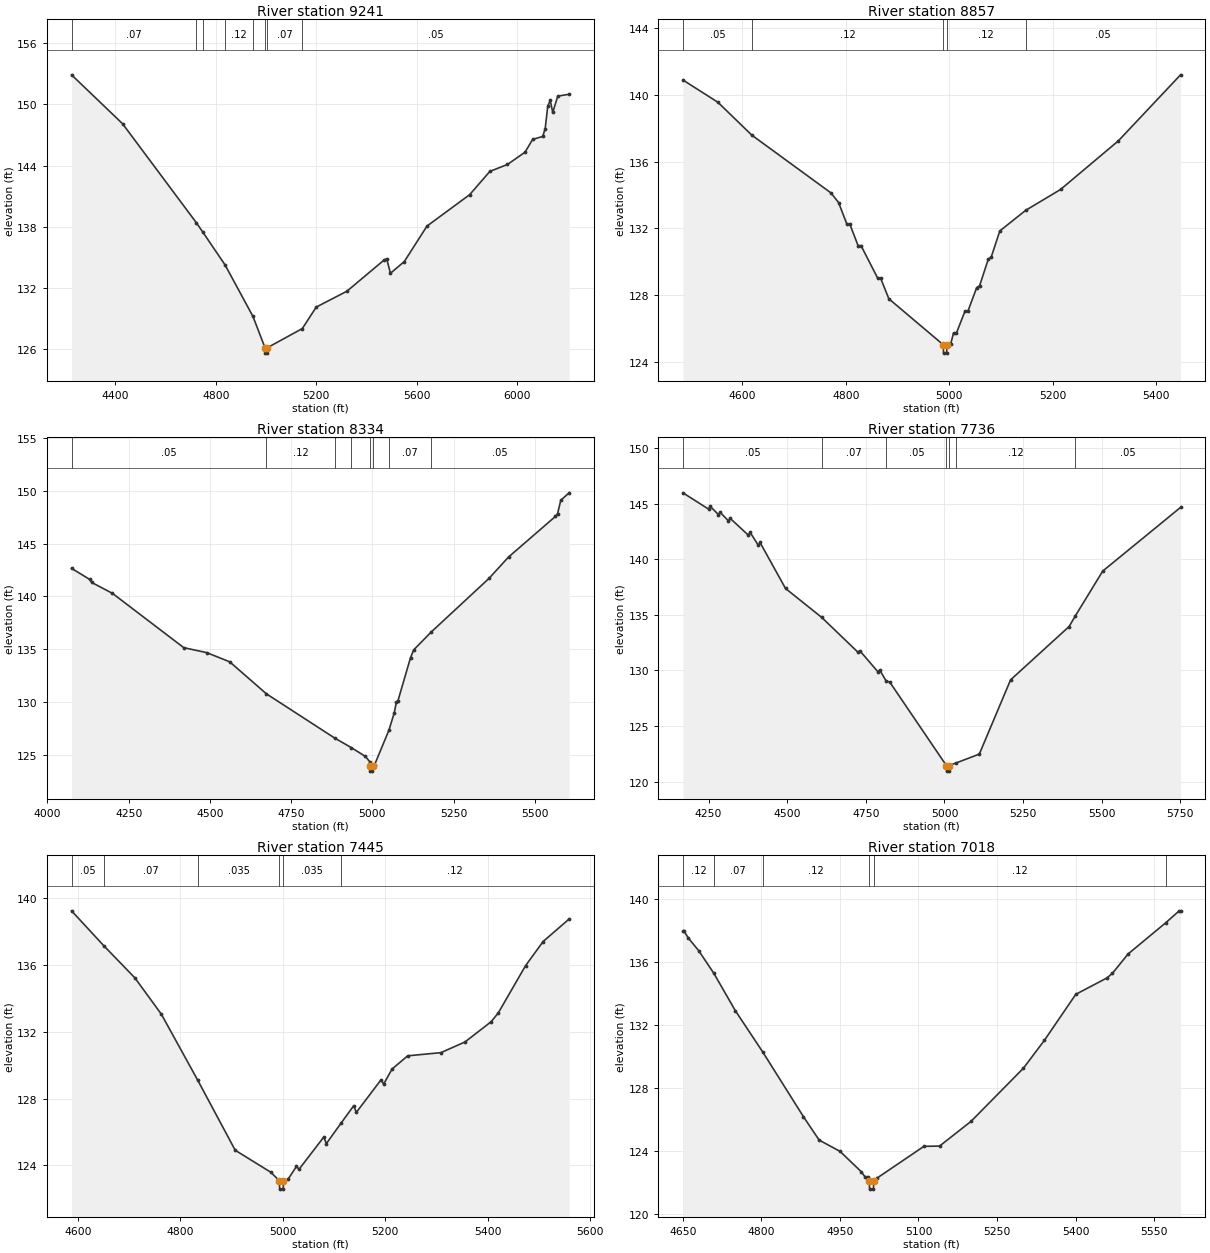
Type RM Length L Ch R = 1 ,9241    ,384,384,384
BEGIN DESCRIPTION:
Mapping XS 6f65ecc9
END DESCRIPTION:
XS GIS Cut Line= 3
      2540579.19     13477203.12      2540001.05     13476812.48
      2538719.87     13476739.57
#Sta/Elev= 30
  4226.1  152.91  4429.2  148.11  4722.4  138.41  4748.5  137.48  4837.3  134.25
  4948.2   129.2  4996.7  126.09  4997.2  125.59  5002.8  125.59  5003.3  126.09
  5144.8     128  5200.3  130.11  5322.6  131.67  5470.8  134.74  5480.8  134.85
  5495.7  133.43  5550.9  134.58  5641.1  138.06  5811.3  141.15  5891.5  143.43
  5961.6  144.11  6031.7  145.32  6061.7  146.57  6101.8  146.86  6111.8  147.62
  6121.8  149.81  6131.8   150.4  6141.9  149.22  6161.9  150.82  6207.1     151
#Mann= 8 ,-1 , 0
  4226.1     .07       0  4722.4     .12       0  4748.5     .07       0
  4837.3     .12       0  4948.2     .07       0  4996.7     .05       0
  5003.3     .07       0  5144.8     .05       0
Bank Sta=4996.7,5003.3
XS Rating Curve= 0 ,0
Exp/Cntr=0.3,0.1

Type RM Length L Ch R = 1 ,8857    ,523,523,523
BEGIN DESCRIPTION:
GOBBLER CREEK 19.0
END DESCRIPTION:
XS GIS Cut Line= 3
      2540374.99       13476675.        2539925.       13476425.
      2539524.99     13476224.99
#Sta/Elev= 30
  4485.2  140.88  4552.7  139.55  4618.4  137.58  4771.2  134.13  4786.1  133.55
  4802.1  132.26  4807.8  132.26  4823.8  130.97  4829.5  130.97  4861.6  129.03
  4867.3  129.03  4883.3  127.79  4988.5  125.04    4989  124.54    4995  124.54
  4995.5  125.04  5002.8  125.09  5008.4  125.75  5013.9  125.74  5030.7  127.07
  5036.3  127.06  5053.1  128.46  5058.7  128.57  5075.4  130.15    5081  130.27
  5097.8  131.85  5147.7  133.08  5215.2  134.33    5327  137.24  5447.2  141.19
#Mann= 5 ,-1 , 0
  4485.2     .05       0  4618.4     .12       0  4988.5     .05       0
  4995.5     .12       0  5147.7     .05       0
Bank Sta=4988.5,4995.5
XS Rating Curve= 0 ,0
Exp/Cntr=0.3,0.1

Type RM Length L Ch R = 1 ,8334    ,598,598,598
BEGIN DESCRIPTION:
Mapping XS 39a697e5
END DESCRIPTION:
XS GIS Cut Line= 3
      2540704.14     13476604.12      2540053.13      13475947.9
      2539449.51     13475885.46
#Sta/Elev= 30
  4074.1  142.65  4129.4  141.61  4136.5  141.31  4200.1  140.28  4419.4  135.14
  4490.1  134.67  4560.8   133.8  4673.7  130.77  4883.4  126.59  4934.8  125.68
    4978  124.85  4992.1  124.33  4993.4  123.95  4993.9  123.45    5000  123.45
  5000.5  123.95  5006.6  124.05  5050.8  127.33  5066.9  128.94  5073.6  129.96
  5078.6  130.12  5117.2  134.19  5127.3  134.94  5180.5  136.61  5358.5  141.69
  5418.8  143.72  5562.9  147.56  5569.6  147.81  5579.7   149.1  5605.3   149.8
#Mann= 8 ,-1 , 0
  4074.1     .05       0  4673.7     .12       0  4883.4     .07       0
  4934.8     .12       0  4993.4     .05       0  5000.5     .12       0
  5050.8     .07       0  5180.5     .05       0
Bank Sta=4993.4,5000.5
XS Rating Curve= 0 ,0
Exp/Cntr=0.3,0.1

Type RM Length L Ch R = 1 ,7736    ,291,291,291
BEGIN DESCRIPTION:
Mapping XS 4cfdc319
END DESCRIPTION:
XS GIS Cut Line= 3
      2541214.57     13475786.44      2540428.13     13475526.03
      2539679.08     13475609.25
#Sta/Elev= 30
  4168.5  145.96  4249.8   144.5  4255.1  144.75  4281.5     144  4286.8  144.21
  4313.2  143.44  4318.5  143.67  4376.7  142.15  4381.9  142.42  4408.4  141.23
  4413.6   141.5  4494.6  137.37  4609.7  134.77  4725.4  131.63  4730.7  131.78
  4788.9  129.87  4794.1  130.05  4814.9  129.04  4825.8  128.97  5006.1  121.46
  5006.6  120.96  5013.6  120.96  5014.1  121.46  5036.7  121.69  5110.8  122.49
  5210.2  129.16  5396.3  133.95  5416.2  134.91  5503.2  138.93  5750.6  144.65
#Mann= 7 ,-1 , 0
  4168.5     .05       0  4609.7     .07       0  4814.9     .05       0
  5006.1     .05       0  5014.1     .05       0  5036.7     .12       0
  5416.2     .05       0
Bank Sta=5006.1,5014.1
XS Rating Curve= 0 ,0
Exp/Cntr=0.3,0.1

Type RM Length L Ch R = 1 ,7445    ,427,427,427
BEGIN DESCRIPTION:
GOBBLER CREEK 16.0
END DESCRIPTION:
XS GIS Cut Line= 3
      2540924.99       13475375.        2540525.       13475275.
      2539975.02       13475375.
#Sta/Elev= 30
  4587.7  139.26  4650.3  137.18  4711.4  135.24  4762.9  133.07  4833.8  129.12
  4907.2  124.91  4976.8  123.59  4993.4  123.08  4993.9  122.58  5000.9  122.58
  5001.4  123.08  5010.2  123.17  5026.7  123.94  5031.8  123.77    5080   125.7
  5085.1  125.31  5114.4  126.56  5138.5  127.58  5143.6  127.18  5191.8  129.13
  5196.9  128.87  5213.4  129.78  5243.9  130.57  5308.7  130.76  5355.7   131.4
  5406.6  132.61  5420.5  133.13  5473.9  135.97  5508.2  137.42    5559  138.77
#Mann= 6 ,-1 , 0
  4587.7     .05       0  4650.3     .07       0  4833.8    .035       0
  4993.4    .035       0  5001.4    .035       0  5114.4     .12       0
Bank Sta=4993.4,5001.4
XS Rating Curve= 0 ,0
Exp/Cntr=0.3,0.1

Type RM Length L Ch R = 1 ,7018    ,334,334,334
BEGIN DESCRIPTION:
GOBBLER CREEK 15.0
END DESCRIPTION:
XS GIS Cut Line= 3
      2540875.05       13474925.        2540525.       13474925.
      2539925.05       13474925.
#Sta/Elev= 30
  4650.3  137.96  4652.8  137.96  4660.3  137.55  4680.3  136.74  4709.4  135.29
  4750.3  132.92  4802.3  130.31  4880.3  126.18  4910.3  124.69  4950.3  123.97
  4990.3  122.69  4997.8  122.36  5002.8  122.36  5006.1  122.07  5006.6  121.57
    5014  121.57  5014.5  122.07  5020.3  122.26  5110.3  124.29  5140.3  124.31
  5200.3  125.88  5300.3  129.26  5340.3  131.03  5400.3  133.96  5460.3  135.01
  5470.3   135.3  5500.3  136.53    5572  138.51  5597.8  139.27  5600.3  139.27
#Mann= 6 ,-1 , 0
  4650.3     .12       0  4709.4     .07       0  4802.3     .12       0
  5006.1     .05       0  5014.5     .12       0    5572     .07       0
Bank Sta=5006.1,5014.5
XS Rating Curve= 0 ,0
Exp/Cntr=0.3,0.1

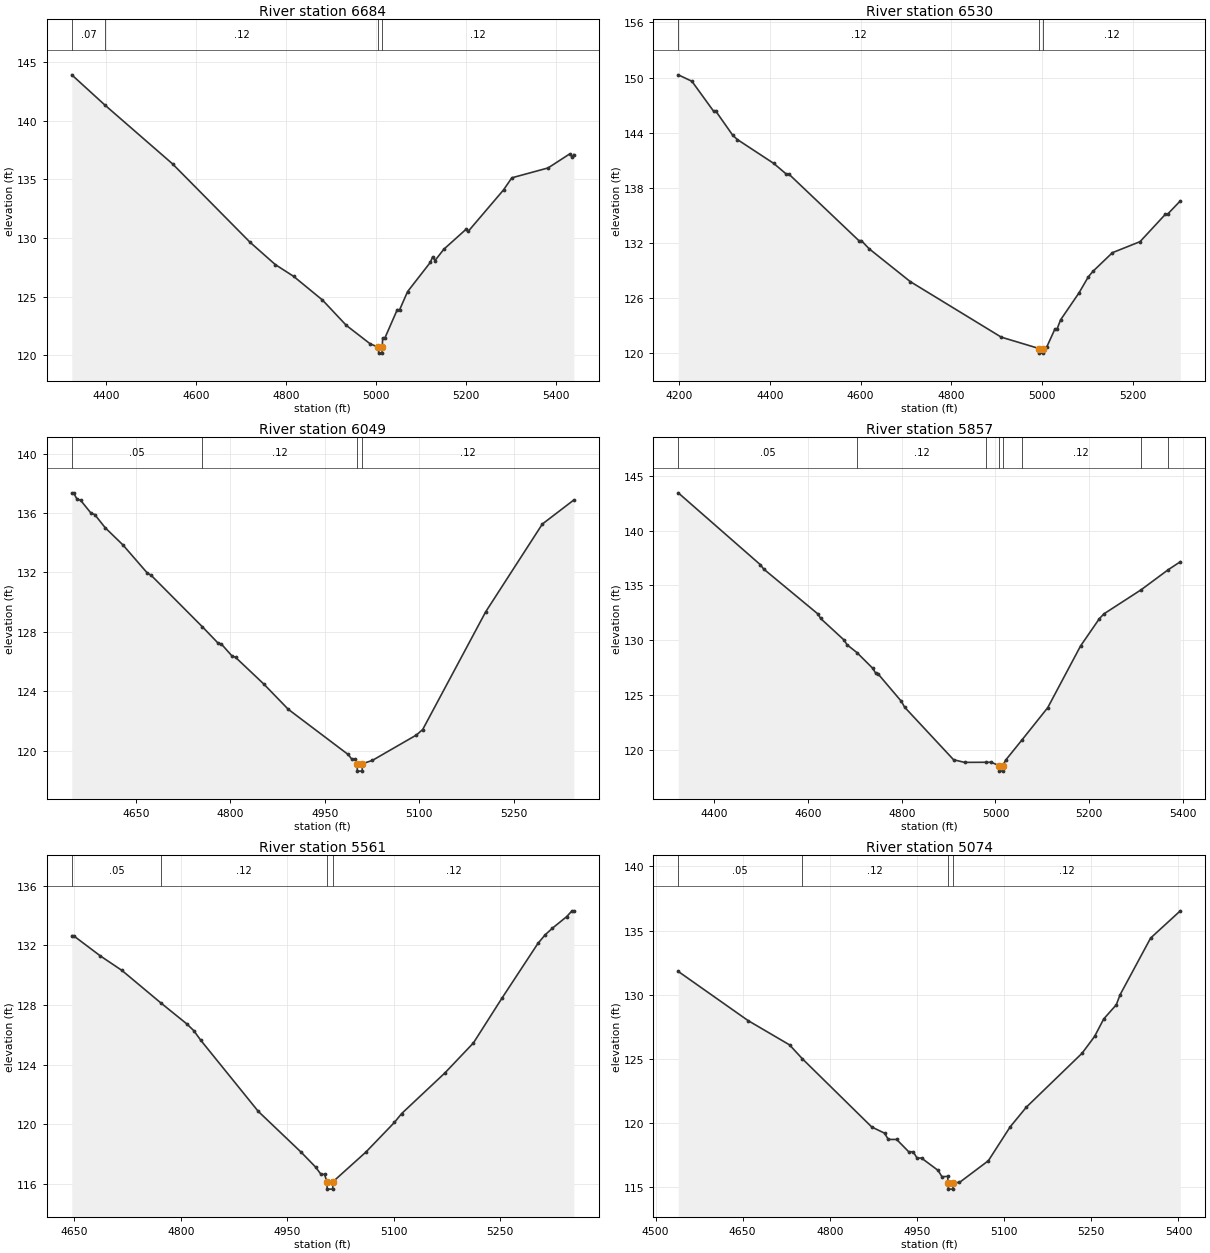
Type RM Length L Ch R = 1 ,6684    ,154,154,154
BEGIN DESCRIPTION:
Mapping XS 82baa610
END DESCRIPTION:
XS GIS Cut Line= 3
      2541090.53     13474750.48      2540409.94     13474625.48
      2539988.13      13474680.8
#Sta/Elev= 30
  4323.3   143.9  4397.2  141.32  4547.5  136.32  4720.4  129.63  4776.3  127.74
    4817  126.74  4881.3  124.72  4934.4  122.56  4987.5  120.99  5005.9   120.7
  5006.4   120.2  5013.8   120.2  5014.3   120.7  5015.2   121.5  5020.3   121.5
  5047.8  123.91  5052.8  123.88  5070.7  125.44  5121.1  127.92  5126.6  128.41
  5131.6  128.08  5151.4  129.05  5200.3  130.73  5205.4  130.56  5284.2   134.1
  5302.7  135.13  5383.3  135.97  5431.7  137.17  5436.7  136.91  5440.7  137.11
#Mann= 4 ,-1 , 0
  4323.3     .07       0  4397.2     .12       0  5005.9     .05       0
  5014.3     .12       0
Bank Sta=5005.9,5014.3
XS Rating Curve= 0 ,0
Exp/Cntr=0.3,0.1

Type RM Length L Ch R = 1 ,6530    ,481,481,481
BEGIN DESCRIPTION:
GOBBLER CREEK 14.0
END DESCRIPTION:
XS GIS Cut Line= 3
      2541225.02       13474525.        2540425.       13474475.
      2540125.02       13474425.
#Sta/Elev= 30
  4198.4   150.3  4228.5   149.6  4276.1  146.35  4281.1  146.35  4318.7   143.7
  4328.7  143.25  4408.8  140.65  4436.4  139.49  4441.4  139.52  4596.7  132.22
  4601.7  132.24  4619.2  131.34  4709.4  127.78  4909.8  121.73  4993.2  120.49
  4993.7  119.99  5001.2  119.99  5001.7  120.49  5010.1  120.67  5027.9  122.61
  5032.9  122.65  5040.5  123.62  5081.1  126.56  5101.4  128.29  5111.5  128.89
  5154.6  130.93  5215.4  132.13  5271.2  135.11  5276.2  135.13  5304.1  136.57
#Mann= 3 ,-1 , 0
  4198.4     .12       0  4993.2     .05       0  5001.7     .12       0
Bank Sta=4993.2,5001.7
XS Rating Curve= 0 ,0
Exp/Cntr=0.3,0.1

Type RM Length L Ch R = 1 ,6049    ,192,192,192
BEGIN DESCRIPTION:
GOBBLER CREEK 13.0
END DESCRIPTION:
XS GIS Cut Line= 3
      2540925.02     13474225.01        2540525.       13474025.
      2540175.03       13474025.
#Sta/Elev= 30
  4548.2  137.36    4551  137.36  4556.6  136.93  4562.2  136.86    4579  135.98
  4584.6   135.9  4601.3  135.01  4629.3  133.86  4668.4  131.95    4674  131.82
  4755.2  128.36  4780.2  127.26  4785.8  127.18  4802.6  126.38  4808.2  126.29
  4852.9   124.5    4892  122.79    4987  119.75  4992.6  119.45  4997.9  119.45
  5001.2  119.13  5001.7  118.63  5009.2  118.63  5009.7  119.13  5025.4  119.35
  5095.4  121.06  5105.4  121.43  5205.4  129.35  5295.4  135.26  5345.4  136.88
#Mann= 4 ,-1 , 0
  4548.2     .05       0  4755.2     .12       0  5001.2     .05       0
  5009.7     .12       0
Bank Sta=5001.2,5009.7
XS Rating Curve= 0 ,0
Exp/Cntr=0.3,0.1

Type RM Length L Ch R = 1 ,5857    ,296,296,296
BEGIN DESCRIPTION:
Mapping XS d132595b
END DESCRIPTION:
XS GIS Cut Line= 3
      2541194.68     13473937.98      2540555.78     13473833.81
      2540132.22     13473833.81
#Sta/Elev= 30
  4323.3  143.47  4498.7  136.89  4505.4  136.51  4621.7  132.38  4626.9  131.99
  4677.6  129.99  4683.1  129.59  4704.4  128.87  4738.4  127.42  4744.6  126.97
  4749.7  126.91  4799.2  124.41  4806.1  123.88  4910.6  119.07  4934.1  118.83
  4980.1  118.84  4991.4  118.84  5007.1  118.53  5007.6  118.03  5015.2  118.03
  5015.7  118.53  5021.4  119.02  5055.5  120.83  5111.4  123.83  5181.4  129.47
  5221.4  131.96  5231.4  132.41  5310.7  134.61    5368  136.43  5394.2  137.17
#Mann= 8 ,-1 , 0
  4323.3     .05       0  4704.4     .12       0  4980.1     .07       0
  5007.1     .05       0  5015.7     .07       0  5055.5     .12       0
  5310.7     .07       0    5368     .05       0
Bank Sta=5007.1,5015.7
XS Rating Curve= 0 ,0
Exp/Cntr=0.3,0.1

Type RM Length L Ch R = 1 ,5561    ,487,487,487
BEGIN DESCRIPTION:
GOBBLER CREEK 12.0
END DESCRIPTION:
XS GIS Cut Line= 3
      2540974.97       13473625.        2540625.       13473575.
      2540274.97       13473525.
#Sta/Elev= 29
  4646.5  132.64    4649  132.64  4686.9  131.28  4717.2  130.31    4772  128.13
  4808.1  126.74  4818.2  126.28  4828.3  125.62  4909.1  120.86  4969.7  118.11
  4989.9  117.12  4997.5  116.63  5002.5  116.63  5005.8  116.14  5006.3  115.64
  5013.9  115.64  5014.4  116.14  5060.6  118.12    5101  120.12  5111.1  120.71
  5171.7  123.42  5212.2  125.45  5252.6  128.47  5303.1  132.13  5313.2   132.7
  5323.3  133.14  5343.5  133.92    5351  134.31  5353.6  134.31
#Mann= 4 ,-1 , 0
  4646.5     .05       0    4772     .12       0  5005.8     .05       0
  5014.4     .12       0
Bank Sta=5005.8,5014.4
XS Rating Curve= 0 ,0
Exp/Cntr=0.3,0.1

Type RM Length L Ch R = 1 ,5074    ,479,479,479
BEGIN DESCRIPTION:
GOBBLER CREEK 11.0
END DESCRIPTION:
XS GIS Cut Line= 3
      2541024.98     13473474.98        2540725.       13473125.
      2540374.97     13472924.98
#Sta/Elev= 30
  4539.1  131.82  4659.3  127.99  4730.6   126.1  4752.6  125.02  4872.2   119.7
  4894.1  119.22  4900.7  118.73    4915  118.73  4935.8  117.77  4943.5  117.77
  4950.1  117.28  4957.8  117.28  4986.3  116.32  4992.9  115.83  5002.9  115.85
  5003.6  115.36  5004.1  114.86  5011.8  114.86  5012.3  115.36  5023.1  115.38
  5072.8  117.07  5110.2   119.7  5138.3  121.25    5234  125.44  5255.6  126.75
  5271.4  128.12    5293  129.22  5299.5     130  5352.1  134.42  5403.2  136.54
#Mann= 4 ,-1 , 0
  4539.1     .05       0  4752.6     .12       0  5003.6     .05       0
  5012.3     .12       0
Bank Sta=5003.6,5012.3
XS Rating Curve= 0 ,0
Exp/Cntr=0.3,0.1

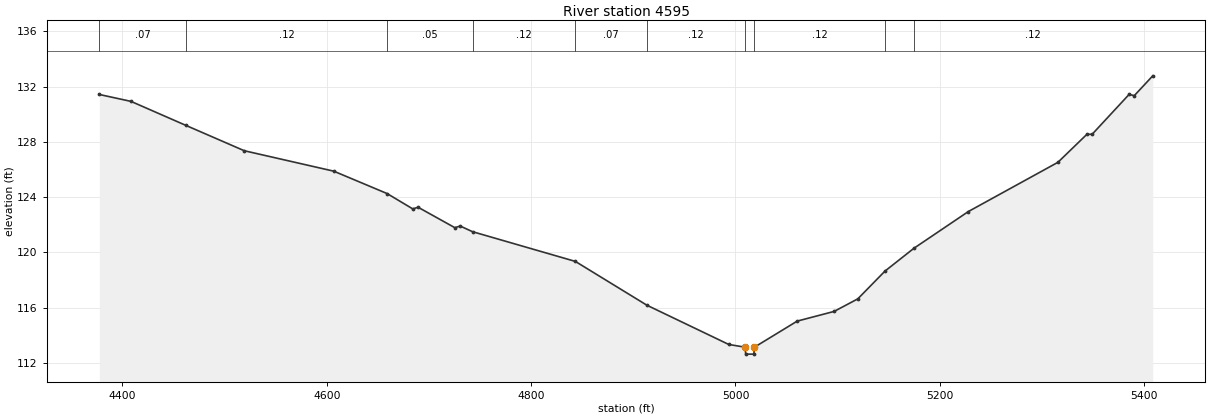
Type RM Length L Ch R = 1 ,4595    ,437,437,437
BEGIN DESCRIPTION:
GOBBLER CREEK 10.0
END DESCRIPTION:
XS GIS Cut Line= 3
      2541525.04     13472875.01        2540925.       13472725.
      2540525.02       13472625.
#Sta/Elev= 30
  4377.5  131.43  4408.5  130.93  4462.3  129.19  4519.3  127.36  4606.9  125.88
  4659.1  124.26  4684.2  123.15  4689.4  123.27  4725.4  121.79  4730.6  121.91
  4742.7   121.5  4843.3  119.35  4913.3  116.18  4993.4  113.34  5009.5  113.14
    5010  112.64    5018  112.64  5018.5  113.14  5060.4  115.03  5096.5  115.73
  5119.7  116.64  5146.3  118.65  5174.6   120.3  5227.9  122.96  5315.5  126.52
  5343.9  128.55    5349  128.55  5385.1  131.43  5390.3  131.35  5408.3  132.78
#Mann= 10 ,-1 , 0
  4377.5     .07       0  4462.3     .12       0  4659.1     .05       0
  4742.7     .12       0  4843.3     .07       0  4913.3     .12       0
  5009.5     .05       0  5018.5     .12       0  5146.3     .07       0
  5174.6     .12       0
Bank Sta=5009.5,5018.5
XS Rating Curve= 0 ,0
Exp/Cntr=0.3,0.1