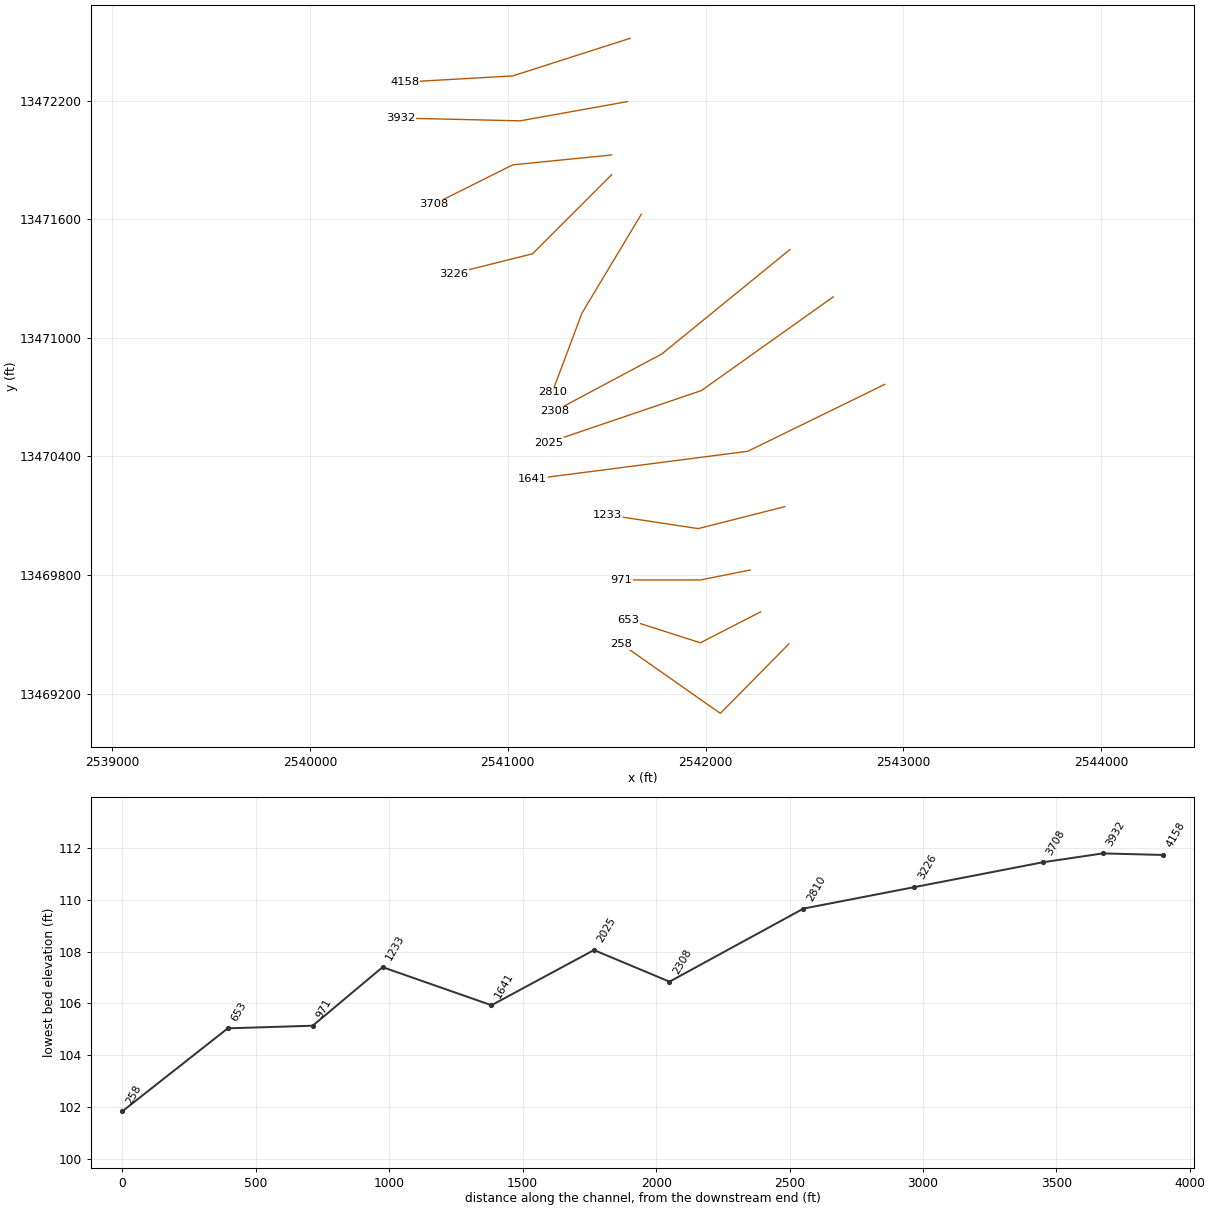
HEC-RAS study GOBBLER CREEK.prj: GOBBLER CREEK Base Level Engineering

--- GOBBLER CREEK.g01 (geometry) --- (continued)

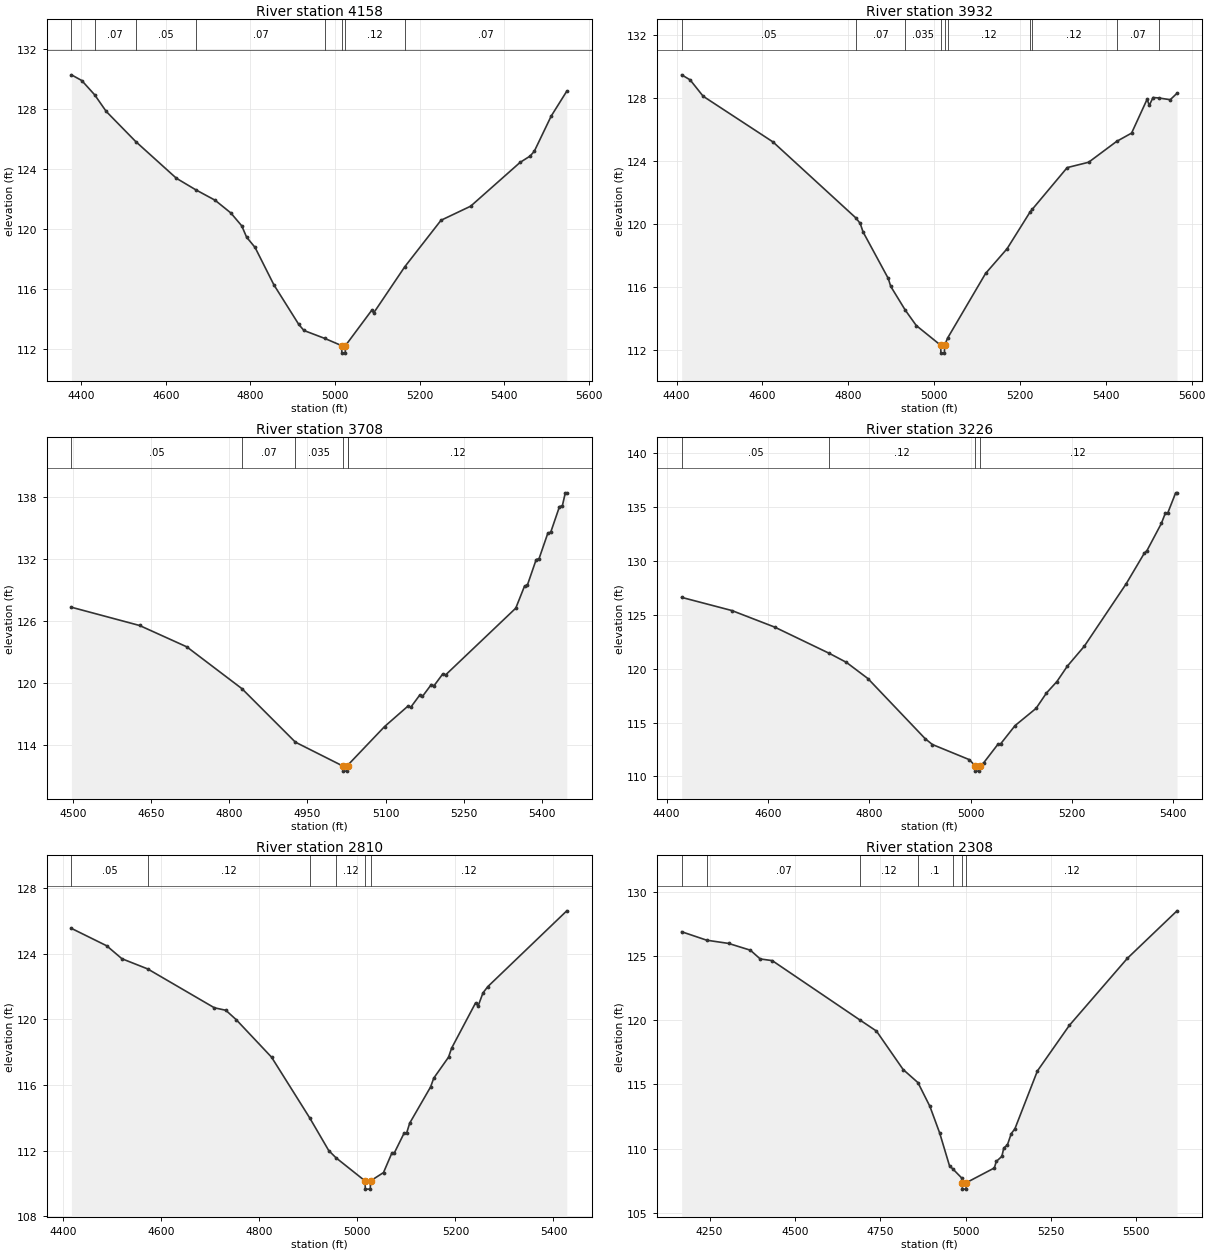
Type RM Length L Ch R = 1 ,4158    ,226,226,226
BEGIN DESCRIPTION:
GOBBLER CREEK 9.0
END DESCRIPTION:
XS GIS Cut Line= 3
      2541618.21     13472515.08        2541025.       13472325.
      2540478.31     13472293.81
#Sta/Elev= 30
  4377.1  130.29  4401.5  129.91  4431.9  128.96  4459.3  127.85    4529  125.84
  4625.2  123.39  4671.1  122.62  4716.4  121.93  4753.7  121.08  4779.5  120.22
  4791.1  119.46    4811  118.78  4855.4  116.29  4914.4  113.64  4926.5  113.24
  4975.8  112.71  5015.6  112.23  5016.1  111.73  5024.1  111.73  5024.6  112.23
  5086.5  114.58  5091.5  114.42  5164.8  117.49  5250.4  120.59  5320.5  121.53
  5437.3  124.45  5460.8  124.87  5470.8  125.19  5510.8  127.54  5547.6   129.2
#Mann= 8 ,-1 , 0
  4377.1     .05       0  4431.9     .07       0    4529     .05       0
  4671.1     .07       0  4975.8     .12       0  5015.6     .05       0
  5024.6     .12       0  5164.8     .07       0
Bank Sta=5015.6,5024.6
XS Rating Curve= 0 ,0
Exp/Cntr=0.3,0.1

Type RM Length L Ch R = 1 ,3932    ,224,224,224
BEGIN DESCRIPTION:
Mapping XS 61160312
END DESCRIPTION:
XS GIS Cut Line= 3
      2541604.34     13472194.91      2541062.72      13472097.7
      2540459.26     13472111.57
#Sta/Elev= 30
    4412  129.46  4431.7  129.14  4462.1   128.1  4624.7   125.2  4817.2  120.39
  4827.9  120.03  4834.5  119.49  4893.3  116.53    4899  116.03  4932.9  114.52
  4958.6  113.54  5015.4  112.29  5015.9  111.79  5024.1  111.79  5024.6  112.29
  5031.6  112.75    5120  116.85  5170.1  118.42  5224.3  120.78  5228.4  120.91
  5310.1  123.57  5360.1  123.91  5425.1  125.23  5460.1  125.76  5496.3  127.91
  5501.3  127.52  5510.1  128.02  5523.5  127.99  5550.2  127.88  5565.9  128.29
#Mann= 10 ,-1 , 0
    4412     .05       0  4817.2     .07       0  4932.9    .035       0
  5015.4    .035       0  5024.6    .035       0  5031.6     .12       0
  5224.3    .035       0  5228.4     .12       0  5425.1     .07       0
  5523.5     .12       0
Bank Sta=5015.4,5024.6
XS Rating Curve= 0 ,0
Exp/Cntr=0.3,0.1

Type RM Length L Ch R = 1 ,3708    ,482,482,482
BEGIN DESCRIPTION:
GOBBLER CREEK 8.0
END DESCRIPTION:
XS GIS Cut Line= 3
        2541525.       13471925.        2541025.       13471875.
      2540625.01       13471675.
#Sta/Elev= 30
  4497.5  127.35  4628.1  125.58  4718.6  123.51  4824.4  119.45  4926.9  114.26
  5017.7  111.95  5018.2  111.45  5026.5  111.45    5027  111.95  5027.9  112.06
  5097.8  115.77  5142.5  117.75  5148.1  117.65  5164.9   118.8  5170.5   118.7
  5187.3  119.84  5192.9  119.75  5209.6  120.89  5215.2   120.8  5349.4  127.26
  5366.2   129.4  5371.7   129.5  5388.5  131.97  5394.1  132.07  5410.9  134.54
  5416.5  134.64  5433.2  137.11  5438.8  137.21  5444.4  138.45  5447.2  138.45
#Mann= 6 ,-1 , 0
  4497.5     .05       0  4824.4     .07       0  4926.9    .035       0
  5017.7    .035       0    5027    .035       0  5027.9     .12       0
Bank Sta=5017.7,5027
XS Rating Curve= 0 ,0
Exp/Cntr=0.3,0.1

Type RM Length L Ch R = 1 ,3226    ,416,416,416
BEGIN DESCRIPTION:
GOBBLER CREEK 7.0
END DESCRIPTION:
XS GIS Cut Line= 3
      2541524.99     13471824.99        2541125.       13471425.
      2540724.98       13471325.
#Sta/Elev= 30
  4429.7  126.61  4528.7  125.39  4613.5  123.85  4721.5  121.41    4755  120.58
  4797.4  119.08  4910.5   113.5  4924.7  112.96  4997.9  111.55  5008.8  110.99
  5009.3  110.49  5017.6  110.49  5018.1  110.99  5026.3  111.28  5054.6  113.01
  5059.8  113.04  5088.1  114.72  5129.4  116.31    5150  117.74  5170.6   118.8
  5191.2  120.23  5224.7  122.08  5307.2  127.86  5343.3  130.72  5348.4  130.95
  5376.8  133.47  5384.5   134.4  5389.6  134.46  5405.1  136.31  5407.7  136.31
#Mann= 4 ,-1 , 0
  4429.7     .05       0  4721.5     .12       0  5008.8     .05       0
  5018.1     .12       0
Bank Sta=5008.8,5018.1
XS Rating Curve= 0 ,0
Exp/Cntr=0.3,0.1

Type RM Length L Ch R = 1 ,2810    ,502,502,502
BEGIN DESCRIPTION:
GOBBLER CREEK 6.0
END DESCRIPTION:
XS GIS Cut Line= 3
      2541675.01     13471625.02        2541375.       13471125.
      2541225.01     13470725.02
#Sta/Elev= 30
  4416.8  125.55  4488.7  124.49  4519.8   123.7  4572.3  123.08  4708.4  120.71
  4731.7  120.56  4753.1  119.98    4825   117.7  4903.2  113.98  4941.6  112.01
  4956.4  111.57  5015.7  110.16  5016.2  109.66  5026.3  109.66  5026.8  110.16
  5053.3  110.67  5070.2  111.85  5075.6  111.88  5095.1  113.06  5100.5  113.08
  5106.7  113.68  5149.4  115.89  5155.7  116.42  5185.9   117.7  5192.2  118.25
  5241.1  121.01  5246.4  120.83  5256.2  121.62    5266     122  5427.1  126.62
#Mann= 6 ,-1 , 0
  4416.8     .05       0  4572.3     .12       0  4903.2      .1       0
  4956.4     .12       0  5015.7     .05       0  5026.8     .12       0
Bank Sta=5015.7,5026.8
XS Rating Curve= 0 ,0
Exp/Cntr=0.3,0.1

Type RM Length L Ch R = 1 ,2308    ,283,283,283
BEGIN DESCRIPTION:
Mapping XS 8d7f4f56
END DESCRIPTION:
XS GIS Cut Line= 3
      2542426.79     13471446.57      2541778.39     13470917.95
      2541236.76     13470628.91
#Sta/Elev= 30
  4168.4   126.9  4241.8  126.24  4305.8  125.99  4369.7  125.46  4398.4  124.78
  4433.6  124.65  4690.5  120.02  4738.8  119.16    4817  116.16  4860.4  115.14
  4895.3  113.29    4924  111.21  4952.8  108.65  4961.5  108.44    4988  107.72
    4990  107.34  4990.5  106.84  5001.3  106.84  5001.8  107.34    5084  108.49
  5089.7     109    5106  109.39  5111.7  110.05  5122.2  110.28  5133.6  111.17
  5144.2  111.54  5210.1  116.05  5303.6   119.6  5473.6  124.83  5618.9  128.53
#Mann= 7 ,-1 , 0
  4168.4     .12       0  4241.8     .07       0  4690.5     .12       0
  4860.4      .1       0  4961.5     .12       0    4990     .05       0
  5001.8     .12       0
Bank Sta=4990,5001.8
XS Rating Curve= 0 ,0
Exp/Cntr=0.3,0.1

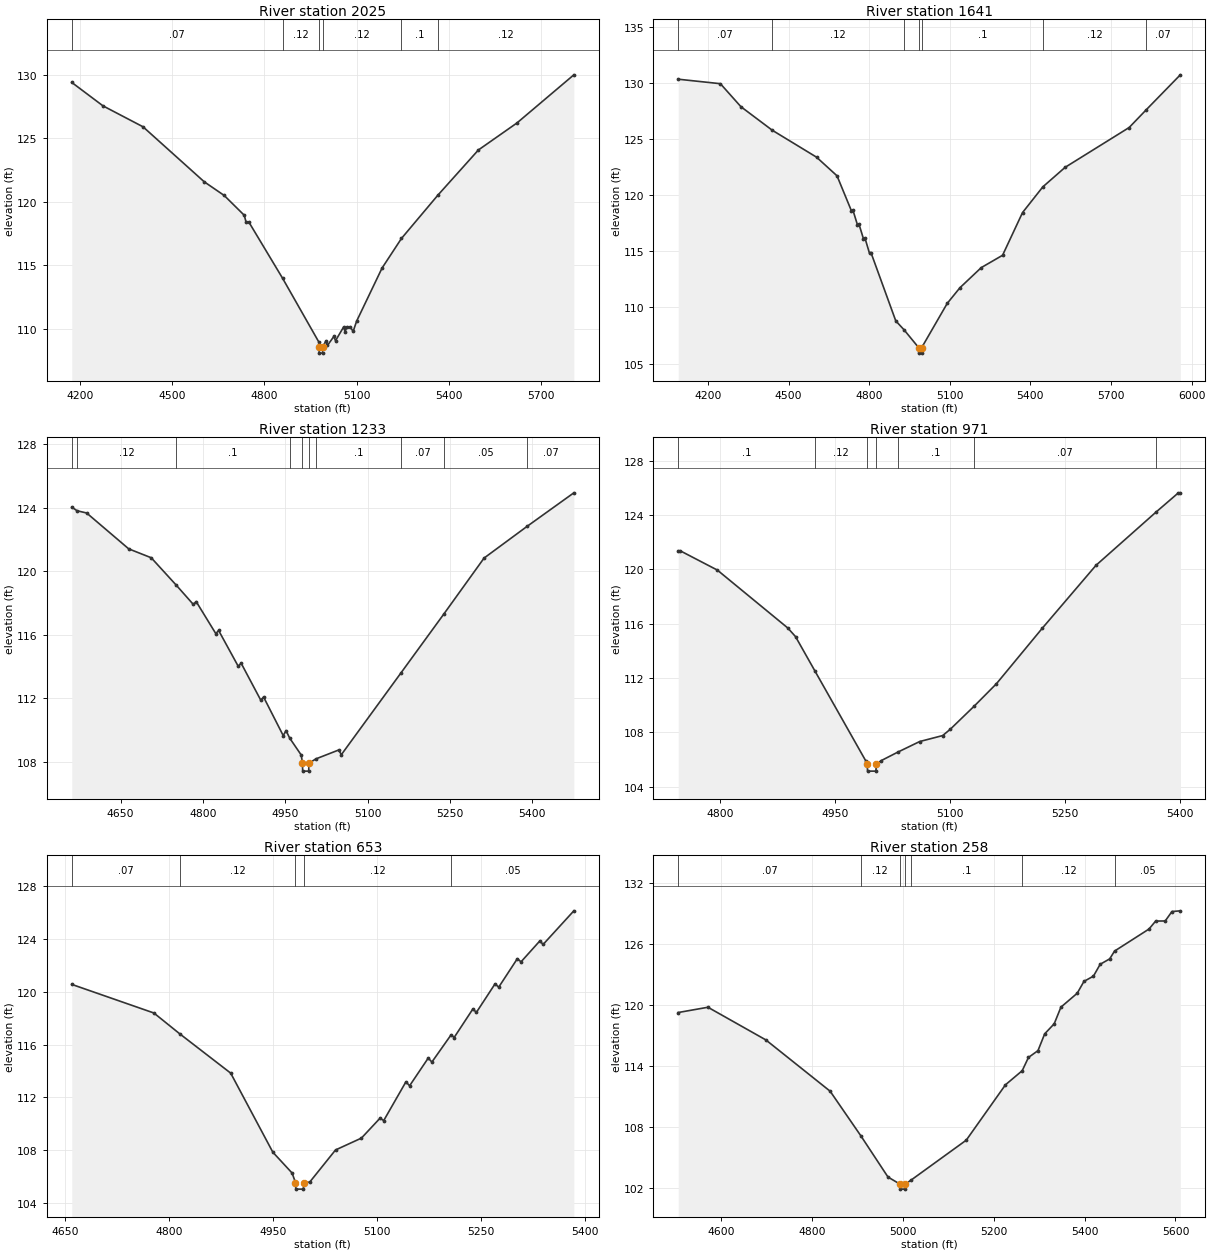
Type RM Length L Ch R = 1 ,2025    ,384,384,384
BEGIN DESCRIPTION:
Mapping XS 7cb5be0e
END DESCRIPTION:
XS GIS Cut Line= 3
      2542645.55     13471206.99      2541978.91     13470733.06
      2541205.45     13470470.03
#Sta/Elev= 30
  4172.7  129.42  4274.4  127.57  4404.7  125.92    4604  121.58  4669.1   120.5
  4734.3  118.94  4740.5  118.38  4749.1  118.41  4859.1  113.97  4977.8  108.91
  4978.1  108.56  4978.6  108.06  4989.4  108.06  4989.9  108.56  5000.1  109.01
  5005.4  108.67  5026.2  109.38  5031.5  109.04  5057.6  110.11  5062.8  109.76
  5068.7  110.12  5079.3  110.14  5088.9  109.77  5100.4  110.59    5183  114.77
  5246.3  117.11  5364.7  120.52  5496.8  124.09  5622.3  126.22  5807.6  130.02
#Mann= 6 ,-1 , 0
  4172.7     .07       0  4859.1     .12       0  4978.1     .05       0
  4989.9     .12       0  5246.3      .1       0  5364.7     .12       0
Bank Sta=4978.1,4989.9
XS Rating Curve= 0 ,0
Exp/Cntr=0.3,0.1

Type RM Length L Ch R = 1 ,1641    ,408,408,408
BEGIN DESCRIPTION:
Mapping XS 90f67e59
END DESCRIPTION:
XS GIS Cut Line= 3
      2542905.99     13470764.31      2542213.28     13470425.77
      2541124.74     13470285.14
#Sta/Elev= 30
  4089.6  130.31  4246.5  129.91    4323  127.86  4439.4  125.77  4604.4  123.37
  4680.6  121.71  4733.9  118.61  4739.5  118.68  4756.4  117.36    4762  117.43
  4778.9  116.11  4784.5  116.18  4801.5  114.81    4807  114.87  4899.2   108.8
  4929.5  108.02  4984.1  106.43  4984.6  105.93  4995.4  105.93  4995.9  106.43
  5090.8  110.36    5138  111.75  5217.3  113.54  5296.7  114.64    5371  118.44
  5446.6  120.73  5529.7  122.47  5767.8  126.01  5831.4  127.59  5958.2   130.7
#Mann= 7 ,-1 , 0
  4089.6     .07       0  4439.4     .12       0  4929.5      .1       0
  4984.1     .05       0  4995.9      .1       0  5446.6     .12       0
  5831.4     .07       0
Bank Sta=4984.1,4995.9
XS Rating Curve= 0 ,0
Exp/Cntr=0.3,0.1

Type RM Length L Ch R = 1 ,1233    ,262,262,262
BEGIN DESCRIPTION:
Mapping XS 59ebfb26
END DESCRIPTION:
XS GIS Cut Line= 3
      2542400.36     13470145.63      2541962.89     13470034.53
      2541504.58     13470103.97
#Sta/Elev= 30
  4561.1  124.03  4570.8   123.8  4588.2  123.66  4664.9   121.4  4705.9  120.84
  4751.6  119.11  4782.6   117.9  4787.8  118.08  4823.6  116.06  4828.7  116.26
  4864.5     114  4869.7   114.2  4905.5  111.87  4910.6  112.07  4946.4  109.64
  4951.6  109.95  4958.2  109.48  4979.3  108.41  4981.4   107.9  4981.9   107.4
  4992.8   107.4  4993.3   107.9  5005.9  108.17  5047.4  108.73  5052.4  108.44
  5160.4  113.56  5239.6  117.32  5312.4  120.82  5390.9  122.82    5476  124.93
#Mann= 10 ,-1 , 0
  4561.1     .07       0  4570.8     .12       0  4751.6      .1       0
  4958.2     .12       0  4981.4     .05       0  4993.3     .12       0
  5005.9      .1       0  5160.4     .07       0  5239.6     .05       0
  5390.9     .07       0
Bank Sta=4981.4,4993.3
XS Rating Curve= 0 ,0
Exp/Cntr=0.3,0.1

Type RM Length L Ch R = 1 ,971     ,318,318,318
BEGIN DESCRIPTION:
GOBBLER CREEK 2.0
END DESCRIPTION:
XS GIS Cut Line= 3
      2542225.04     13469825.01        2541975.       13469775.
        2541575.       13469775.
#Sta/Elev= 23
    4745  121.37  4747.6  121.37    4796  119.95  4887.8  115.69    4898  115.05
  4923.6  112.49  4989.8  105.88  4991.5  105.64    4992  105.14  5002.9  105.14
  5003.4  105.64    5010  105.92  5031.1  106.53    5060  107.32    5090  107.76
    5100  108.23  5130.8  109.91    5160  111.57    5220  115.67    5290   120.3
  5367.9   124.2  5397.5  125.64    5400  125.64
#Mann= 7 ,-1 , 0
    4745      .1       0  4923.6     .12       0  4991.5     .05       0
  5003.4     .12       0  5031.1      .1       0  5130.8     .07       0
  5367.9     .05       0
Bank Sta=4991.5,5003.4
XS Rating Curve= 0 ,0
Exp/Cntr=0.3,0.1

Type RM Length L Ch R = 1 ,653     ,395,395,395
BEGIN DESCRIPTION:
Mapping XS 7969e0b2
END DESCRIPTION:
XS GIS Cut Line= 3
      2542277.62     13469613.14      2541973.84     13469456.91
      2541608.54     13469573.63
#Sta/Elev= 30
  4659.2  120.57  4777.8   118.4  4814.9  116.83  4888.7  113.84  4949.6  107.84
  4977.4  106.26  4982.3  105.54  4982.8  105.04  4993.7  105.04  4994.2  105.54
  5002.8  105.57  5040.1  108.01  5077.5  108.91  5104.4  110.42  5109.7  110.24
  5141.8  113.18  5147.1  112.88    5174  114.98  5179.3  114.68  5207.1  116.75
  5211.4  116.54  5238.4   118.7  5243.6  118.45  5270.5  120.61  5275.8  120.36
  5302.7  122.52    5308  122.28  5334.9  123.85  5340.1  123.61  5384.3  126.15
#Mann= 5 ,-1 , 0
  4659.2     .07       0  4814.9     .12       0  4982.3     .05       0
  4994.2     .12       0  5207.1     .05       0
Bank Sta=4982.3,4994.2
XS Rating Curve= 0 ,0
Exp/Cntr=0.3,0.1

Type RM Length L Ch R = 1 ,258     ,0,0,0
BEGIN DESCRIPTION:
GOBBLER CREEK 1.0
END DESCRIPTION:
XS GIS Cut Line= 3
       2542421.2     13469451.16      2542074.67     13469099.79
      2541574.88     13469450.57
#Sta/Elev= 30
  4506.5  119.26  4571.8  119.78  4699.1  116.56  4840.5   111.5  4907.9  107.11
  4967.8  103.03  4993.9  102.34  4994.4  101.84  5005.4  101.84  5005.9  102.34
  5017.9  102.71  5139.9  106.67  5226.1  112.13  5262.9  113.52  5276.7  114.83
  5297.6   115.5  5312.4  117.16  5333.3  118.15  5348.1  119.79  5383.9  121.16
  5398.7  122.33  5419.6  122.85  5434.4  124.02  5455.3  124.55    5466  125.32
  5541.6  127.49  5556.4  128.28  5577.4  128.29  5592.2  129.22  5610.6  129.29
#Mann= 7 ,-1 , 0
  4506.5     .07       0  4907.9     .12       0  4993.9     .05       0
  5005.9     .12       0  5017.9      .1       0  5262.9     .12       0
    5466     .05       0
Bank Sta=4993.9,5005.9
XS Rating Curve= 0 ,0
Exp/Cntr=0.3,0.1

Chan Stop Cuts=-1
Use User Specified Reach Order=0
Composite Channel Slope=5