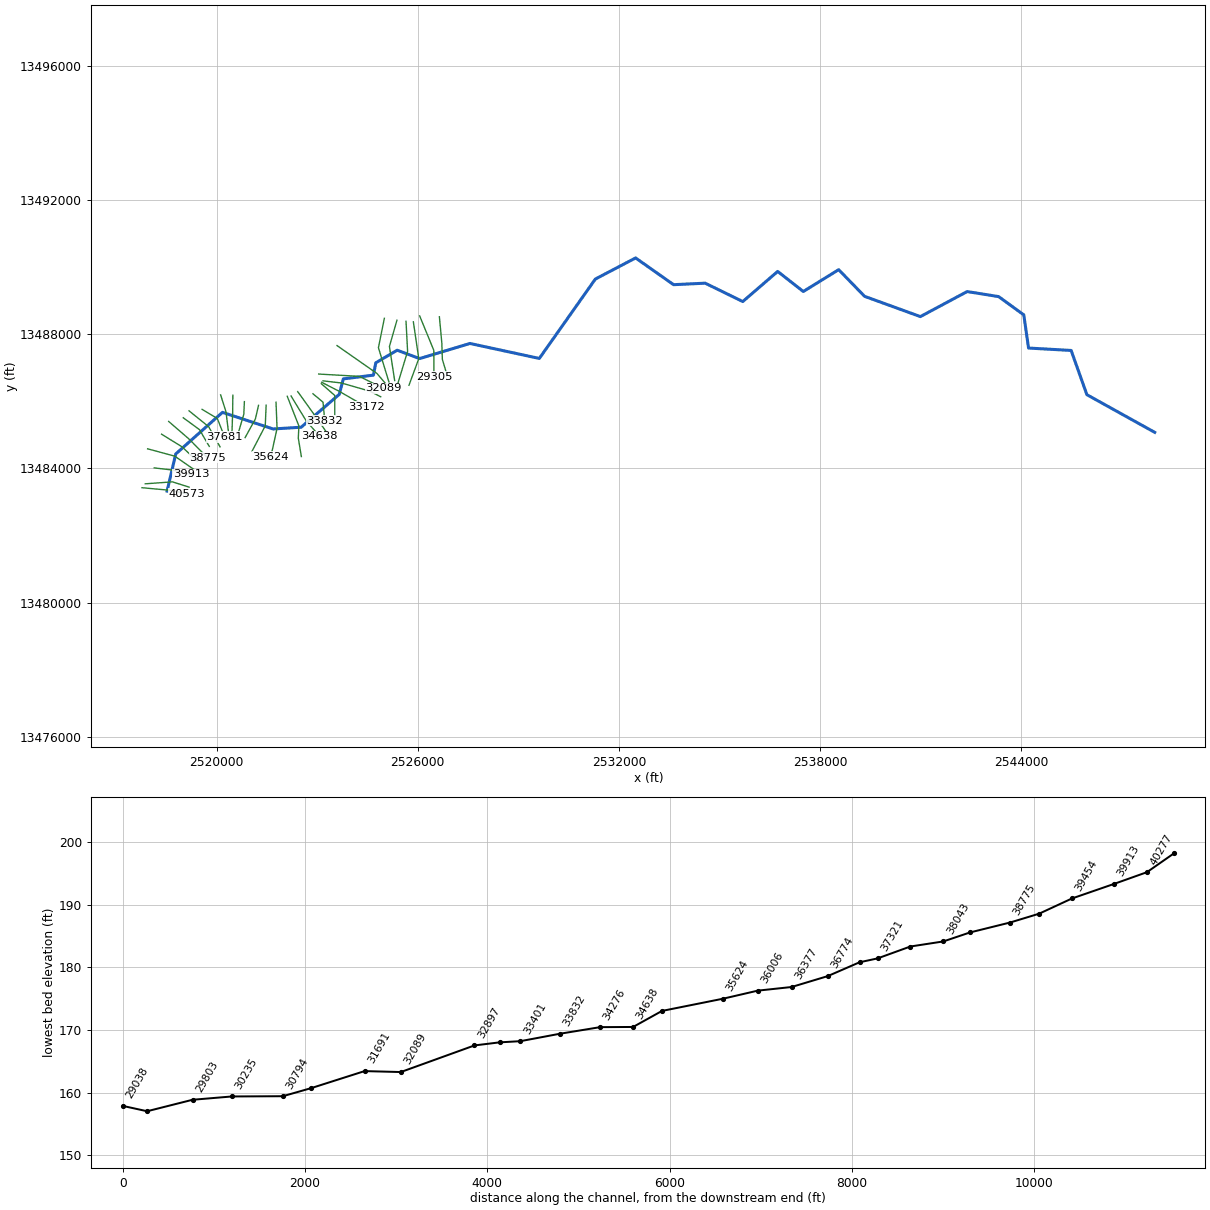
--- HOG THIEF CREEK.prj (project) ---

Proj Title=HOG THIEF CREEK Base Level Engineering
Current Plan=p01
Default Exp/Contr=0.3,0.1
English Units
Geom File=g01
Flow File=f01
Plan File=p01
Y Axis Title=Elevation
X Axis Title(PF)=Main Channel Distance
X Axis Title(XS)=Station
BEGIN DESCRIPTION:
HOG THIEF CREEK
END DESCRIPTION:
DSS Export Rating Curves= 0
DSS Export Rating Curve Sorted= 0
DSS Export Volume Flow Curves= 0
DXF OffsetX= 0
DXF OffsetY= 0
DXF ScaleX= 1
DXF ScaleY= 10

--- HOG THIEF CREEK.p01 (plan) ---

Plan Title=Multiple Run
Short Identifier=Multiple
Geom File=g01
Flow File=f01
Subcritical Flow
K Sum by GR= 0
Std Step Tol= 0.01
Critical Tol= 0.01
Num of Std Step Trials= 20
Max Error Tol= 0.3
Flow Tol Ratio= 0.001
Split Flow NTrial= 30
Split Flow Tol= 0.02
Split Flow Ratio= 0.02
Log Output Level= 0
Friction Slope Method= 1
Unsteady Friction Slope Method= 2
Unsteady Bridges Friction Slope Method= 1
Parabolic Critical Depth
Global Vel Dist=  1 , 1 , 1
Global Log Level= 0
CheckData=True
Encroach Param= -1, 0, 0, 0
BEGIN DESCRIPTION:
Multiple Run
END DESCRIPTION:

--- HOG THIEF CREEK.f01 (steady flow) ---

Flow Title=Multiple
Program Version=4.10
Number of Profiles= 7
Profile Names=10-year,25-year,50-year,1pct_min,100-year,1pct_plu,500-year
River Rch & RM=HOG THIEF CREEK,Reach-1         ,40573
     563     884    1167     745    1486    2966    2384
River Rch & RM=HOG THIEF CREEK,Reach-1         ,34955
    1042    1694    2284    1487    2967    5921    4955
River Rch & RM=HOG THIEF CREEK,Reach-1         ,28367
    1371    2254    3065    2009    4009    7999    6791
River Rch & RM=HOG THIEF CREEK,Reach-1         ,24031
    1780    2951    4035    2659    5304   10584    9072
River Rch & RM=HOG THIEF CREEK,Reach-1         ,19881
    1971    3284    4503    2974    5935   11841   10204
River Rch & RM=HOG THIEF CREEK,Reach-1         ,14808
    2140    3576    4915    3254    6492   12954   11210
River Rch & RM=HOG THIEF CREEK,Reach-1         ,12676
    2376    3990    5502    3653    7288   14542   12658
River Rch & RM=HOG THIEF CREEK,Reach-1         ,11410
    2822    4768    6602    4399    8776   17511   15352
River Rch & RM=HOG THIEF CREEK,Reach-1         ,4730
    3186    5402    7498    5006    9987   19927   17540
Boundary for River Rch & Prof#=HOG THIEF CREEK,Reach-1         , 1
Up Type= 0
Dn Type= 3
Dn Slope=0.001
Boundary for River Rch & Prof#=HOG THIEF CREEK,Reach-1         , 2
Up Type= 0
Dn Type= 3
Dn Slope=0.001
Boundary for River Rch & Prof#=HOG THIEF CREEK,Reach-1         , 3
Up Type= 0
Dn Type= 3
Dn Slope=0.001
Boundary for River Rch & Prof#=HOG THIEF CREEK,Reach-1         , 4
Up Type= 0
Dn Type= 3
Dn Slope=0.001
Boundary for River Rch & Prof#=HOG THIEF CREEK,Reach-1         , 5
Up Type= 0
Dn Type= 3
Dn Slope=0.001
Boundary for River Rch & Prof#=HOG THIEF CREEK,Reach-1         , 6
Up Type= 0
Dn Type= 3
Dn Slope=0.001
Boundary for River Rch & Prof#=HOG THIEF CREEK,Reach-1         , 7
Up Type= 0
Dn Type= 3
Dn Slope=0.001
DSS Import GetInterval= 0
DSS Import GetPeak= 0
DSS Import FillOption= 0

--- HOG THIEF CREEK.g01 (geometry) ---

Geom Title=Existing Conditions
Program Version=4.10

River Reach=HOG THIEF CREEK ,Reach-1
Reach XY= 30
        2518525.       13483325.      2518783.14     13484431.06
      2520176.25     13485671.55       2521685.5     13485176.22
      2522523.54     13485228.53      2523658.76     13486207.77
      2523780.27     13486670.02      2524677.31     13486780.83
      2524747.98     13487148.51      2525385.54     13487523.92
       2526054.9     13487274.89      2527554.83      13487725.3
      2529623.44     13487278.76      2531294.42     13489645.65
      2532495.04     13490274.95      2533626.63     13489478.13
      2534569.06     13489522.75      2535690.39     13488975.09
      2536730.97     13489872.86      2537495.43     13489274.47
      2538549.63     13489925.41      2539322.44     13489130.71
      2540985.51     13488526.22      2542380.97     13489272.86
      2543319.03     13489122.67       2544069.3     13488577.54
      2544211.76     13487588.61      2545481.19     13487517.19
      2545951.16     13486197.86        2547975.       13485075.

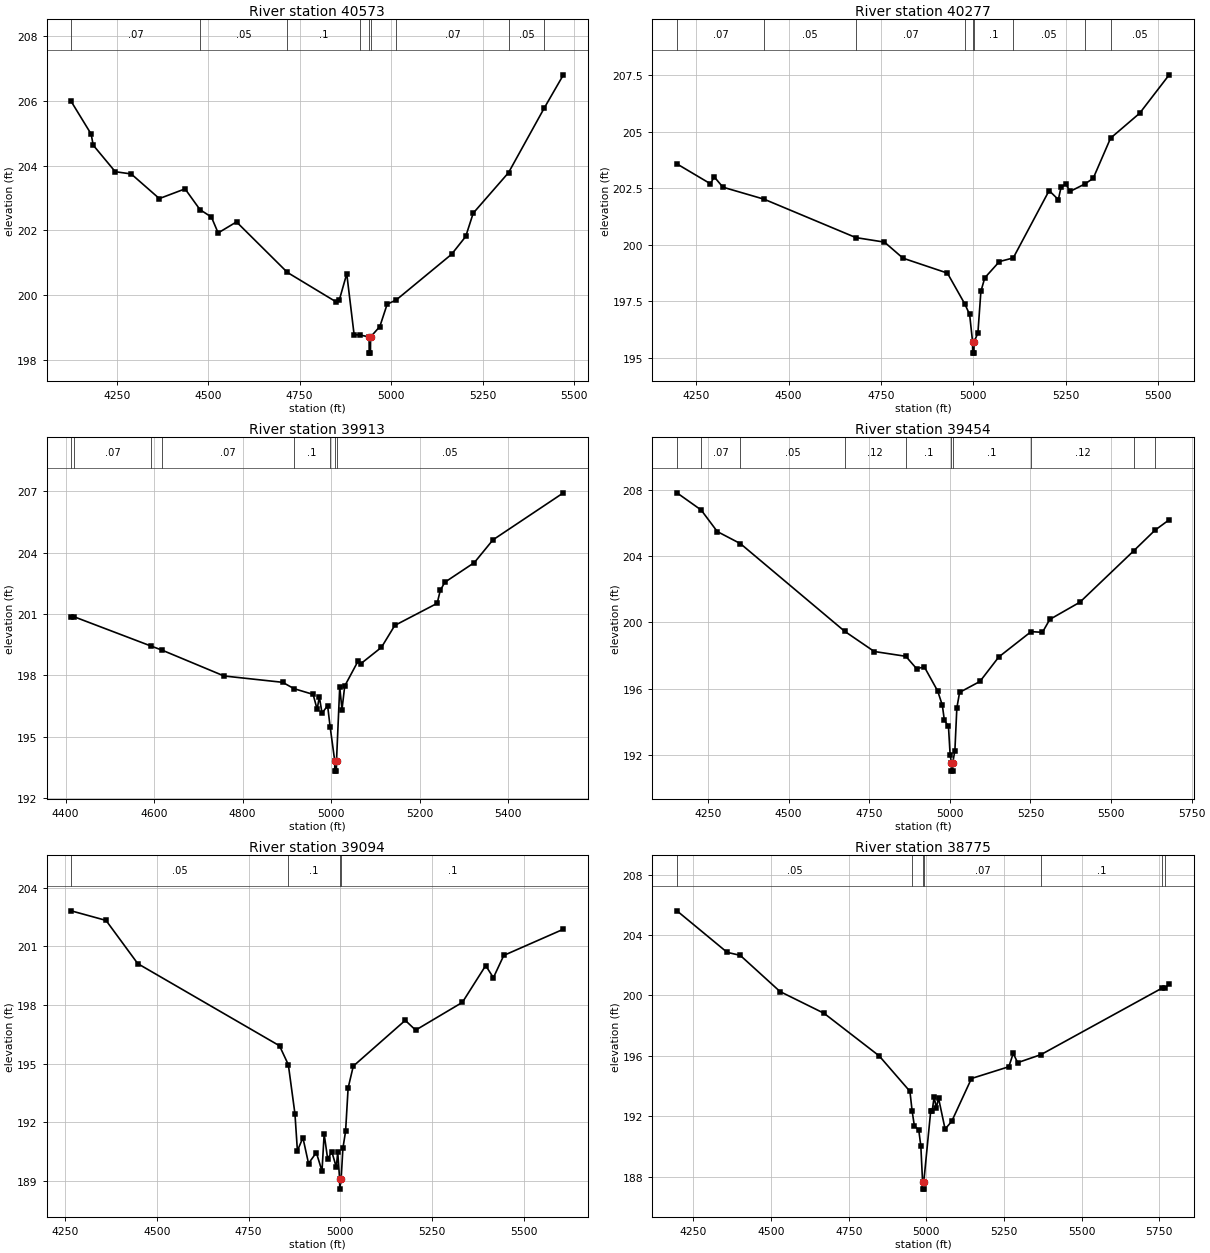
Type RM Length L Ch R = 1 ,40573   ,296,296,296
BEGIN DESCRIPTION:
HOG THIEF CREEK 85.0
END DESCRIPTION:
XS GIS Cut Line= 3
      2517775.03       13483425.      2518645.81     13483344.44
      2519105.87     13483244.44
#Sta/Elev= 30
  4125.5  205.98  4180.2  204.97  4185.7  204.63    4246  203.81  4289.7  203.74
  4366.5  202.98  4436.8  203.28  4477.5  202.64  4508.8  202.41  4527.2  201.92
  4577.4  202.26  4716.6   200.7  4848.5   199.8  4858.6  199.86  4878.7  200.66
  4898.8  198.78  4914.5  198.77  4939.8  198.71    4940  198.21  4943.5  198.21
  4943.8  198.71  4969.1  199.03  4989.1  199.72  5013.8  199.85  5165.1  201.26
  5203.8  201.81  5224.3  202.53  5320.8  203.78  5418.7  205.78  5470.8   206.8
#Mann= 9 ,-1 , 0
  4125.5     .07       0  4477.5     .05       0  4716.6      .1       0
  4914.5     .05       0  4939.8     .05       0  4943.8     .05       0
  5013.8     .07       0  5320.8     .05       0  5418.7    .035       0
Bank Sta=4939.8,4943.8
XS Rating Curve= 0 ,0
Exp/Cntr=0.3,0.1

Type RM Length L Ch R = 1 ,40277   ,364,364,364
BEGIN DESCRIPTION:
Mapping XS 7c3ac344
END DESCRIPTION:
XS GIS Cut Line= 3
      2517874.46     13483541.21      2518684.57     13483599.19
      2519181.32     13483442.68
#Sta/Elev= 30
  4197.5  203.58  4288.3   202.7  4298.3  203.01    4322  202.55  4433.3  202.02
  4682.1  200.32  4759.5  200.12  4809.6  199.41  4929.9  198.75  4977.2  197.38
  4990.1  196.92  4998.1  195.71  4998.3  195.21  5001.8  195.21  5002.1  195.71
  5012.5   196.1  5020.6  197.94  5031.1  198.54  5070.7  199.26  5108.2  199.42
  5205.4   202.4  5230.3     202  5237.7  202.55  5251.3  202.69  5261.8  202.36
  5301.9  202.69  5324.7  202.94  5371.8  204.72  5450.5  205.82  5530.5  207.52
#Mann= 9 ,-1 , 0
  4197.5     .07       0  4433.3     .05       0  4682.1     .07       0
  4977.2      .1       0  4998.1     .05       0  5002.1      .1       0
  5108.2     .05       0  5301.9    .035       0  5371.8     .05       0
Bank Sta=4998.1,5002.1
XS Rating Curve= 0 ,0
Exp/Cntr=0.3,0.1

Type RM Length L Ch R = 1 ,39913   ,459,459,459
BEGIN DESCRIPTION:
Mapping XS d33153d1
END DESCRIPTION:
XS GIS Cut Line= 3
      2518141.88      13484015.7      2518714.81     13483947.99
       2519235.6       13483823.
#Sta/Elev= 30
  4412.4  200.87  4419.4  200.86  4593.2  199.43  4618.1  199.23  4757.9  197.97
  4890.4  197.66    4916  197.35  4959.3  197.07  4968.3  196.34  4973.3  196.95
  4979.4  196.15    4992  196.52  4997.6   195.5  5008.1  193.82  5008.3  193.32
  5011.8  193.32  5012.1  193.82  5019.4  197.43  5024.5  196.33  5030.7  197.48
  5061.4  198.72  5066.5  198.56  5113.7  199.37  5143.8  200.44  5239.6  201.52
  5246.6  202.15  5256.9  202.55  5323.6  203.51  5365.6  204.62  5524.9  206.92
#Mann= 8 ,-1 , 0
  4412.4     .05       0  4419.4     .07       0  4593.2     .05       0
  4618.1     .07       0    4916      .1       0  4997.6     .05       0
  5008.1     .05       0  5012.1     .05       0
Bank Sta=5008.1,5012.1
XS Rating Curve= 0 ,0
Exp/Cntr=0.3,0.1

Type RM Length L Ch R = 1 ,39454   ,360,360,360
BEGIN DESCRIPTION:
Mapping XS 7fa43dd4
END DESCRIPTION:
XS GIS Cut Line= 3
      2517944.26     13484584.56      2518753.33      13484365.8
       2519319.3     13483973.43
#Sta/Elev= 30
  4153.5  207.83  4228.7  206.79  4278.6  205.49  4350.3  204.76  4673.8  199.46
  4765.5  198.24  4863.4  197.95  4896.9   197.2  4920.8  197.31  4962.3  195.85
  4976.7  194.99    4983  194.08  4995.7  193.72  5000.8  192.01  5004.9  191.51
  5005.1  191.01  5008.6  191.01  5008.9  191.51  5015.6  192.25  5021.7  194.83
  5030.2  195.77  5093.3  196.43  5151.8  197.91    5252  199.44  5287.2   199.4
    5310  200.18  5403.4  201.22  5571.1  204.34  5636.2  205.57  5680.3   206.2
#Mann= 10 ,-1 , 0
  4153.5     .12       0  4228.7     .07       0  4350.3     .05       0
  4673.8     .12       0  4863.4      .1       0  5004.9     .05       0
  5008.9      .1       0    5252     .12       0  5571.1     .07       0
  5636.2     .05       0
Bank Sta=5004.9,5008.9
XS Rating Curve= 0 ,0
Exp/Cntr=0.3,0.1

Type RM Length L Ch R = 1 ,39094   ,319,319,319
BEGIN DESCRIPTION:
Mapping XS 8ee5d064
END DESCRIPTION:
XS GIS Cut Line= 3
      2518360.67     13485020.89      2518975.22      13484640.7
      2519423.11     13484213.64
#Sta/Elev= 30
  4266.4  202.81  4361.4  202.32  4447.9  200.11  4834.2  195.91  4858.3  194.94
  4876.3  192.43    4883  190.54    4898  191.21  4913.3  189.89  4934.6  190.45
    4950   189.5  4955.9   191.4  4965.3  190.14  4977.1  190.47    4989   189.7
  4992.9  190.47  4998.1  189.08  4998.3  188.58  5002.1  189.08    5007  190.67
  5014.3  191.54  5021.2  193.75  5035.3  194.87  5176.9  197.21  5205.2  196.71
  5332.6  198.13  5396.1  200.01  5417.1  199.39  5445.4  200.53  5607.9  201.87
#Mann= 4 ,-1 , 0
  4266.4     .05       0  4858.3      .1       0  4998.1     .05       0
  5002.1      .1       0
Bank Sta=4998.1,5002.1
XS Rating Curve= 0 ,0
Exp/Cntr=0.3,0.1

Type RM Length L Ch R = 1 ,38775   ,441,441,441
BEGIN DESCRIPTION:
Mapping XS 6eab21b8
END DESCRIPTION:
XS GIS Cut Line= 3
      2518572.79      13485400.5      2519190.83      13484865.8
      2519729.83     13484319.89
#Sta/Elev= 30
    4197  205.61  4358.6  202.86  4400.7  202.66  4528.9  200.26  4670.5  198.82
  4847.9     196  4946.9  193.65    4954  192.35  4961.1  191.37  4975.4  191.08
    4982  190.03  4987.6  187.67  4987.9  187.17  4991.4  187.17  4991.6  187.67
  5013.7  192.32  5018.3  192.32  5024.8  193.27  5031.9  192.56    5039   193.2
  5060.1  191.15  5081.4  191.66    5145   194.5  5265.3  195.28  5279.4  196.17
  5293.6  195.55  5368.5  196.08  5758.5  200.49  5767.5  200.48  5781.4  200.77
#Mann= 7 ,-1 , 0
    4197     .05       0    4954     .07       0  4987.6     .05       0
  4991.6     .07       0  5368.5      .1       0  5758.5     .12       0
  5767.5      .1       0
Bank Sta=4987.6,4991.6
XS Rating Curve= 0 ,0
Exp/Cntr=0.3,0.1

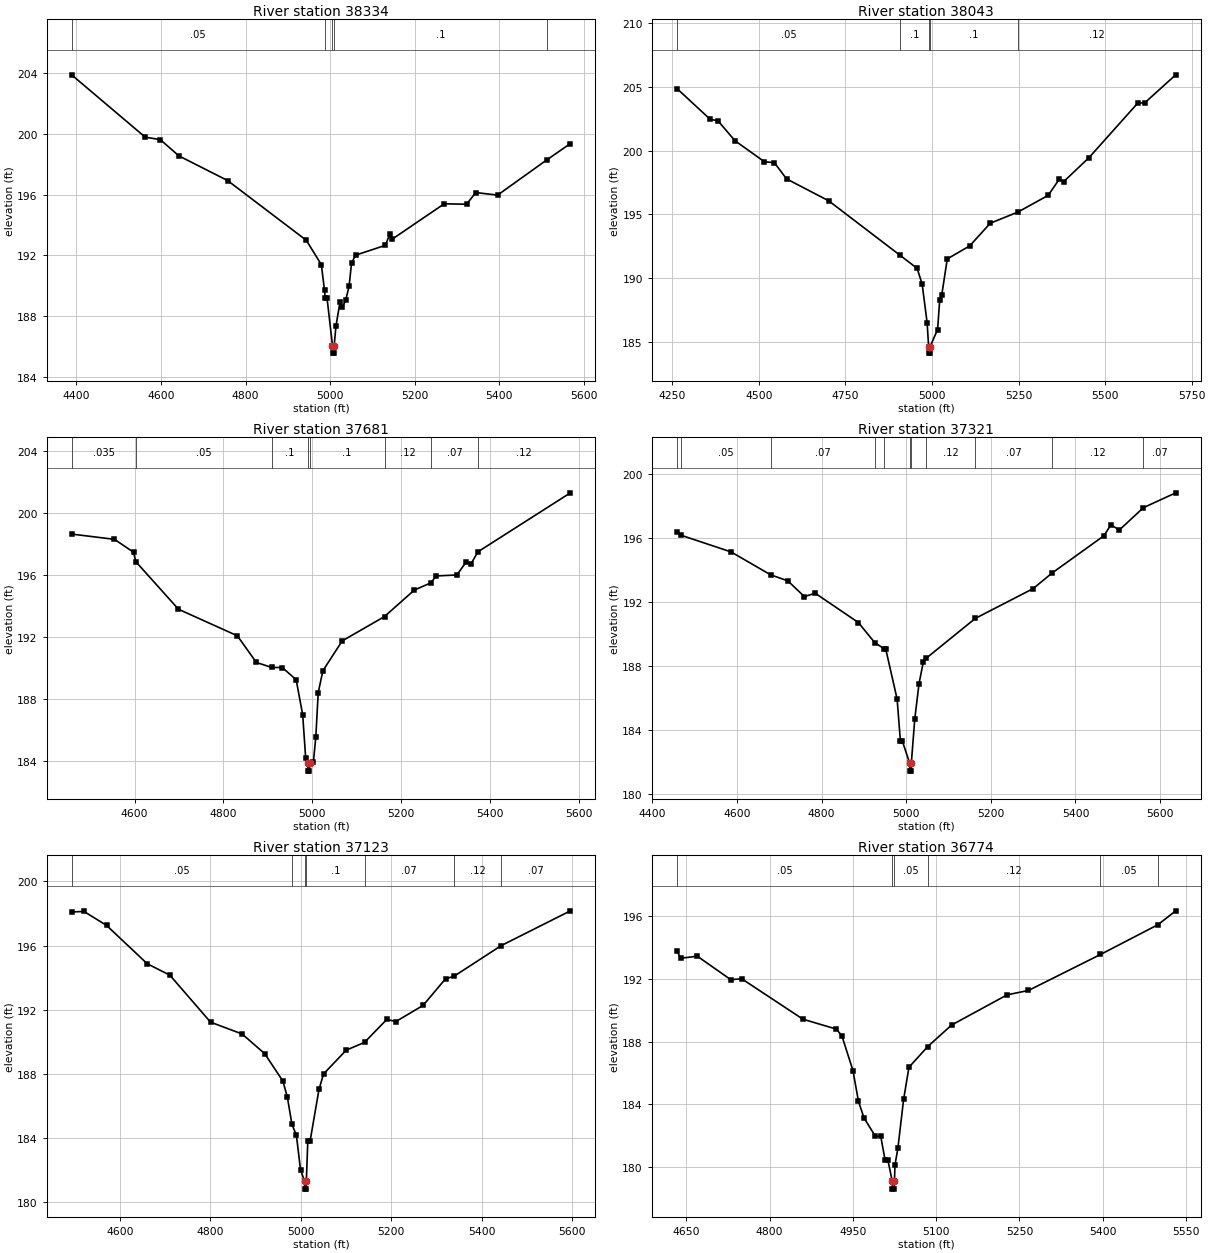
Type RM Length L Ch R = 1 ,38334   ,291,291,291
BEGIN DESCRIPTION:
Mapping XS d9719cbd
END DESCRIPTION:
XS GIS Cut Line= 3
      2519006.47     13485510.49      2519490.85     13485156.32
      2519782.52     13484656.32
#Sta/Elev= 30
    4389  203.88    4563  199.78  4598.6  199.62  4642.6  198.55  4757.6  196.93
  4943.7     193  4979.2   191.4  4986.8   189.7  4988.5   189.2  4992.7   189.2
  5005.6  186.08  5005.8  185.58  5009.3  185.58  5009.6  186.08  5013.7  187.34
  5023.3  188.93  5029.1   188.6  5036.9  189.08  5044.8  189.97  5050.6   191.5
    5060  192.02  5130.8  192.67  5140.7  193.39  5146.5  193.07  5269.7   195.4
  5322.6  195.37  5344.1  196.14  5395.8  195.97  5512.3  198.29  5567.9  199.36
#Mann= 5 ,-1 , 0
    4389     .05       0  4986.8      .1       0  5005.6     .05       0
  5009.6      .1       0  5512.3     .12       0
Bank Sta=5005.6,5009.6
XS Rating Curve= 0 ,0
Exp/Cntr=0.3,0.1

Type RM Length L Ch R = 1 ,38043   ,362,362,362
BEGIN DESCRIPTION:
Mapping XS b4e211d7
END DESCRIPTION:
XS GIS Cut Line= 3
      2519180.39     13485716.51      2519763.74     13485244.27
      2520104.01     13484643.59
#Sta/Elev= 30
  4263.1  204.85  4359.2  202.44  4381.5  202.33  4431.1  200.76  4515.9  199.12
  4544.6  199.05  4579.8  197.78  4701.3  196.07  4907.4  191.81  4957.1  190.78
  4971.5  189.55  4985.9  186.53  4990.3  184.65  4990.5  184.15    4994  184.15
  4994.3  184.65  5016.1  185.99  5022.4  188.34  5028.2   188.7  5044.1  191.52
    5109  192.54  5168.2  194.31  5247.9  195.18  5335.5  196.49  5367.3  197.74
  5380.6  197.57  5453.8  199.45  5593.8  203.69  5615.4  203.75    5704  205.92
#Mann= 5 ,-1 , 0
  4263.1     .05       0  4907.4      .1       0  4990.3     .05       0
  4994.3      .1       0  5247.9     .12       0
Bank Sta=4990.3,4994.3
XS Rating Curve= 0 ,0
Exp/Cntr=0.3,0.1

Type RM Length L Ch R = 1 ,37681   ,360,360,360
BEGIN DESCRIPTION:
Mapping XS 20d1a0a1
END DESCRIPTION:
XS GIS Cut Line= 3
      2519568.94     13485760.51       2520022.1     13485489.66
      2520240.86     13484937.55
#Sta/Elev= 30
  4458.5  198.63  4554.9  198.29  4597.7  197.46  4602.9  196.85  4698.9  193.78
  4831.2  192.07    4874  190.35  4908.1  190.03  4932.3  190.02  4963.5  189.24
  4978.2  186.97  4984.9  184.19  4989.6  183.84  4989.9  183.34  4993.4  183.34
  4993.6  183.84  5002.2   183.9  5007.7  185.52  5013.1   188.4  5023.7  189.82
  5067.1  191.74  5162.2  193.31  5229.3  195.02  5267.1  195.49  5277.9  195.93
  5324.9  195.99  5346.4  196.85  5356.3  196.68    5372  197.48  5580.3  201.29
#Mann= 8 ,-1 , 0
  4458.5    .035       0  4602.9     .05       0  4908.1      .1       0
  4989.6     .05       0  4993.6      .1       0  5162.2     .12       0
  5267.1     .07       0    5372     .12       0
Bank Sta=4989.6,4993.6
XS Rating Curve= 0 ,0
Exp/Cntr=0.3,0.1

Type RM Length L Ch R = 1 ,37321   ,198,198,198
BEGIN DESCRIPTION:
Mapping XS 9a77de9a
END DESCRIPTION:
XS GIS Cut Line= 3
      2520121.37     13486192.23      2520281.11     13485688.71
      2520360.97     13485042.88
#Sta/Elev= 30
    4458  196.36  4467.9  196.17    4586  195.13  4679.5   193.7  4720.3  193.32
  4759.3  192.34  4784.9  192.55  4886.9  190.72  4925.5  189.47  4948.5  189.07
  4951.5  189.08  4978.5  185.94  4986.2  183.34  4990.6  183.34  5008.1  181.94
  5008.4  181.44  5011.9  181.44  5012.1  181.94  5020.2  184.69  5030.3  186.91
  5040.4  188.25  5047.7   188.5  5163.5  190.98  5300.2  192.84  5344.7  193.81
  5467.4  196.14  5483.7  196.82  5503.9   196.5  5560.5  197.89    5637  198.82
#Mann= 11 ,-1 , 0
    4458     .07       0  4467.9     .05       0  4679.5     .07       0
  4925.5     .05       0  4948.5      .1       0  5008.1     .05       0
  5012.1      .1       0  5047.7     .12       0  5163.5     .07       0
  5344.7     .12       0  5560.5     .07       0
Bank Sta=5008.1,5012.1
XS Rating Curve= 0 ,0
Exp/Cntr=0.3,0.1

Type RM Length L Ch R = 1 ,37123   ,349,349,349
BEGIN DESCRIPTION:
Mapping XS 3ec41659
END DESCRIPTION:
XS GIS Cut Line= 3
      2520485.64      13486182.4      2520480.43     13485671.95
      2520459.63     13485079.09
#Sta/Elev= 30
  4492.7   198.1  4520.1  198.13  4570.1  197.26  4660.1  194.87  4710.1  194.16
  4800.1  191.23  4870.1  190.49  4920.1  189.26  4960.1  187.56  4970.1  186.56
  4980.2  184.86  4990.1  184.18  4999.2  182.03  5008.1  181.32  5008.4  180.82
  5011.9  180.82  5012.1  181.32  5015.3  183.79  5020.3   183.8  5040.1  187.04
  5050.2     188  5100.2  189.48  5140.8  189.97  5190.2   191.4  5210.3  191.27
  5270.3  192.27  5320.3  193.94  5338.3  194.08  5443.2     196  5596.4  198.17
#Mann= 7 ,-1 , 0
  4492.7     .05       0  4980.2      .1       0  5008.1     .05       0
  5012.1      .1       0  5140.8     .07       0  5338.3     .12       0
  5443.2     .07       0
Bank Sta=5008.1,5012.1
XS Rating Curve= 0 ,0
Exp/Cntr=0.3,0.1

Type RM Length L Ch R = 1 ,36774   ,397,397,397
BEGIN DESCRIPTION:
Mapping XS 05c427f0
END DESCRIPTION:
XS GIS Cut Line= 3
      2520829.92     13485991.78      2520812.56      13485614.2
      2520664.98     13485115.04
#Sta/Elev= 30
  4632.9  193.78  4639.7  193.31  4669.7  193.44  4729.8  191.95  4749.8     192
  4859.9  189.43    4920   188.8    4930  188.38    4950  186.16    4960  184.19
    4970  183.14  4990.1  181.99  5000.1  181.97    5008  180.44  5013.1  180.44
  5020.8  179.11  5021.1  178.61  5024.6  178.61  5024.8  179.11  5025.7  180.15
  5030.9   181.2  5041.3  184.33  5050.9  186.37  5084.8  187.69  5127.8  189.06
  5227.7  190.98  5266.2  191.26  5395.9  193.55  5499.6  195.45  5531.4  196.33
#Mann= 6 ,-1 , 0
  4632.9     .05       0  5020.8     .05       0  5024.8     .05       0
  5084.8     .12       0  5395.9     .05       0  5499.6     .07       0
Bank Sta=5020.8,5024.8
XS Rating Curve= 0 ,0
Exp/Cntr=0.3,0.1

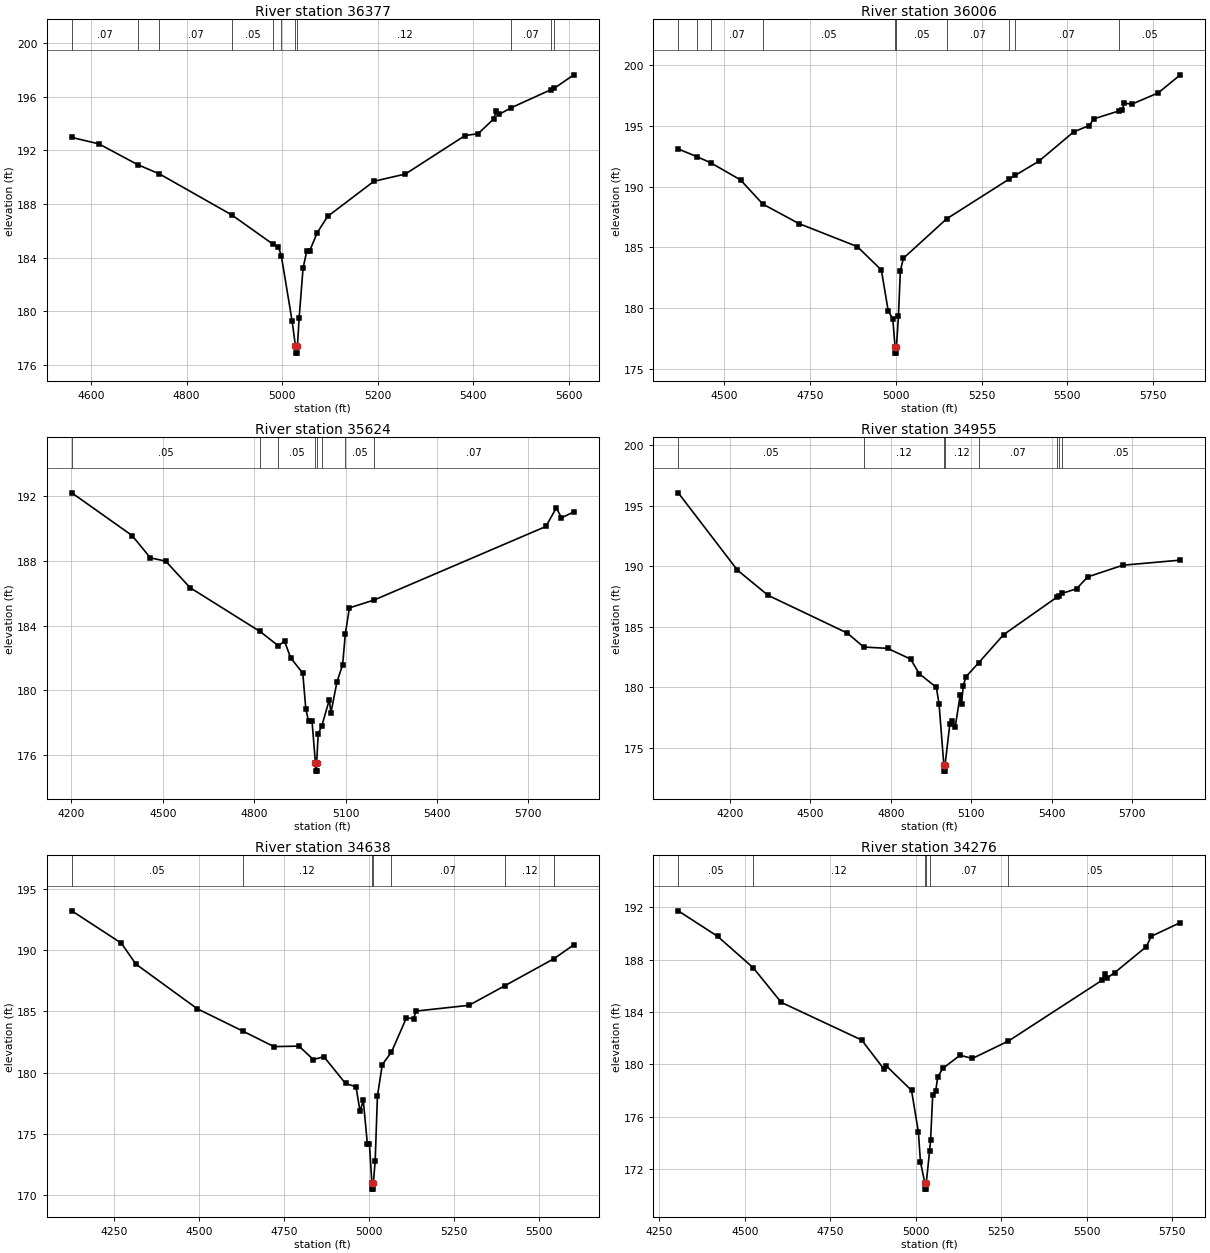
Type RM Length L Ch R = 1 ,36377   ,371,371,371
BEGIN DESCRIPTION:
Mapping XS 6f7d9cb9
END DESCRIPTION:
XS GIS Cut Line= 3
      2521251.26     13485880.24      2521157.52     13485474.03
      2520851.14     13484918.39
#Sta/Elev= 30
  4559.6  192.96  4616.3  192.48  4697.6  190.93  4743.1  190.24  4894.2  187.19
  4981.2  184.99  4992.3  184.82  4998.5  184.11  5021.1  179.25  5028.1  177.37
  5028.4  176.87  5031.9  176.87  5032.1  177.37  5035.8  179.52  5043.9   183.2
  5051.9  184.52  5057.6  184.48  5073.7  185.86  5095.4  187.07  5192.4  189.69
  5258.2  190.23  5383.2   193.1  5410.6  193.24  5442.8  194.33  5448.5   194.9
    5455  194.69  5480.2  195.18  5562.3  196.51  5570.4  196.64    5611  197.63
#Mann= 11 ,-1 , 0
  4559.6     .07       0  4697.6     .05       0  4743.1     .07       0
  4894.2     .05       0  4981.2     .07       0  4998.5     .12       0
  5028.1     .05       0  5032.1     .12       0  5480.2     .07       0
  5562.3     .05       0  5570.4     .07       0
Bank Sta=5028.1,5032.1
XS Rating Curve= 0 ,0
Exp/Cntr=0.3,0.1

Type RM Length L Ch R = 1 ,36006   ,382,382,382
BEGIN DESCRIPTION:
Mapping XS 64b89a5b
END DESCRIPTION:
XS GIS Cut Line= 3
       2521478.4     13485886.23      2521452.35     13485269.87
      2521062.01     13484519.54
#Sta/Elev= 30
  4366.3  193.12    4421  192.48  4460.3  191.99  4547.7  190.57  4612.4  188.58
  4717.8  186.97    4888  185.07  4958.1  183.14  4978.1  179.76  4991.3  179.13
    4998  176.79  4998.2  176.29  5001.7  176.29    5002  176.79  5007.8  179.31
  5013.4  183.09  5022.5  184.12  5148.3  187.36  5330.6  190.64  5348.7  190.96
  5416.5   192.1  5518.5  194.53  5563.6  195.05  5576.9   195.6  5649.7  196.25
  5659.7  196.31  5665.3   196.9  5687.6  196.81  5764.6  197.74    5829  199.23
#Mann= 10 ,-1 , 0
  4366.3     .07       0    4421     .05       0  4460.3     .07       0
  4612.4     .05       0    4998     .05       0    5002     .05       0
  5148.3     .07       0  5330.6     .12       0  5348.7     .07       0
  5649.7     .05       0
Bank Sta=4998,5002
XS Rating Curve= 0 ,0
Exp/Cntr=0.3,0.1

Type RM Length L Ch R = 1 ,35624   ,669,669,669
BEGIN DESCRIPTION:
Mapping XS c8ecb534
END DESCRIPTION:
XS GIS Cut Line= 3
      2521773.54     13485972.96      2521803.92     13485191.75
      2521617.28     13484345.38
#Sta/Elev= 30
    4201   192.2  4399.1  189.56  4459.2  188.18  4509.2  187.98  4589.3  186.34
  4819.1  183.63  4879.6  182.74  4899.5  183.04  4919.5  182.01  4959.5  181.05
  4969.5  178.83  4978.7  178.07  4989.7  178.12    5001   175.5  5001.3     175
  5004.8     175    5005   175.5  5010.2  177.32  5021.8  177.78  5046.7  179.42
  5051.8   178.6  5071.6   180.5  5090.4  181.58  5099.1  183.47  5112.6  185.09
    5193  185.57  5757.7  190.12    5792  191.27  5808.9  190.66  5849.5  191.02
#Mann= 8 ,-1 , 0
    4201     .05       0  4819.1     .07       0  4879.6     .05       0
    5001     .05       0    5005     .05       0  5021.8      .1       0
  5099.1     .05       0    5193     .07       0
Bank Sta=5001,5005
XS Rating Curve= 0 ,0
Exp/Cntr=0.3,0.1

Type RM Length L Ch R = 1 ,34955   ,317,317,317
BEGIN DESCRIPTION:
Mapping XS a942bdba
END DESCRIPTION:
XS GIS Cut Line= 4
      2522107.73     13486150.96      2522454.96     13485265.53
       2522437.6     13484905.29      2522528.74     13484354.11
#Sta/Elev= 30
  4008.1  196.08  4228.7  189.68  4342.6   187.6  4637.5  184.48    4699  183.32
  4787.9  183.21  4873.8  182.32    4906  181.11  4969.7  179.98  4979.7  178.62
  4997.6  173.55  4997.9  173.05  5001.7  173.05    5002  173.55  5019.8  176.93
  5029.8  177.22  5039.8  176.68  5058.5  179.34  5063.5  178.61  5069.8   180.1
  5079.9  180.86  5127.1  182.01    5220  184.34  5419.8  187.46  5425.2  187.56
  5436.4  187.75  5492.4  188.14    5533  189.12  5664.7  190.09  5878.5  190.51
#Mann= 8 ,-1 , 0
  4008.1     .05       0    4699     .12       0  4997.6     .05       0
    5002     .12       0  5127.1     .07       0  5419.8     .05       0
  5425.2     .07       0  5436.4     .05       0
Bank Sta=4997.6,5002
XS Rating Curve= 0 ,0
Exp/Cntr=0.3,0.1

Type RM Length L Ch R = 1 ,34638   ,362,362,362
BEGIN DESCRIPTION:
Mapping XS 186c64d0
END DESCRIPTION:
XS GIS Cut Line= 3
       2522220.6      13486159.6      2522676.31      13485413.1
      2523074.48     13484958.66
#Sta/Elev= 30
  4125.1   193.2  4271.1  190.56    4314  188.85  4494.1  185.22  4628.6  183.39
  4720.5  182.12  4794.1  182.16  4836.7  181.06  4867.6   181.3  4931.5  179.11
  4962.3  178.84  4974.2  176.84  4983.7  177.73  4995.7   174.2  5001.8   174.2
    5009  170.99  5009.3  170.49  5013.1  170.49  5013.4  170.99  5018.8  172.82
  5025.4  178.09  5039.7  180.65  5066.8  181.68  5110.9  184.47  5131.7   184.4
  5139.3  185.02    5295  185.49  5401.5   187.1  5545.7   189.3  5603.9  190.43
#Mann= 7 ,-1 , 0
  4125.1     .05       0  4628.6     .12       0    5009     .05       0
  5013.4     .12       0  5066.8     .07       0  5401.5     .12       0
  5545.7     .07       0
Bank Sta=5009,5013.4
XS Rating Curve= 0 ,0
Exp/Cntr=0.3,0.1

Type RM Length L Ch R = 1 ,34276   ,444,444,444
BEGIN DESCRIPTION:
Mapping XS 094eaafc
END DESCRIPTION:
XS GIS Cut Line= 3
      2522420.24     13486289.83       2522815.2     13485738.62
      2523270.44     13485092.62
#Sta/Elev= 30
  4305.3  191.74  4420.4  189.79  4524.8  187.38  4606.5  184.74  4841.8  181.86
  4906.8  179.64    4914  179.88  4987.6  178.01  5007.6  174.83  5013.8  172.52
  5026.3  170.96  5026.6  170.46  5030.5  170.46  5030.8  170.96  5040.5  173.39
  5043.4  174.24  5049.5  177.64  5058.1  177.94  5064.3  179.04  5079.1  179.69
  5129.6   180.7  5165.3  180.45  5270.8  181.78  5545.9  186.45    5552  186.94
  5560.7  186.63  5581.6  187.01  5673.9  188.99  5688.7  189.79  5773.7  190.84
#Mann= 6 ,-1 , 0
  4305.3     .05       0  4524.8     .12       0  5026.3     .05       0
  5030.8     .12       0  5040.5     .07       0  5270.8     .05       0
Bank Sta=5026.3,5030.8
XS Rating Curve= 0 ,0
Exp/Cntr=0.3,0.1

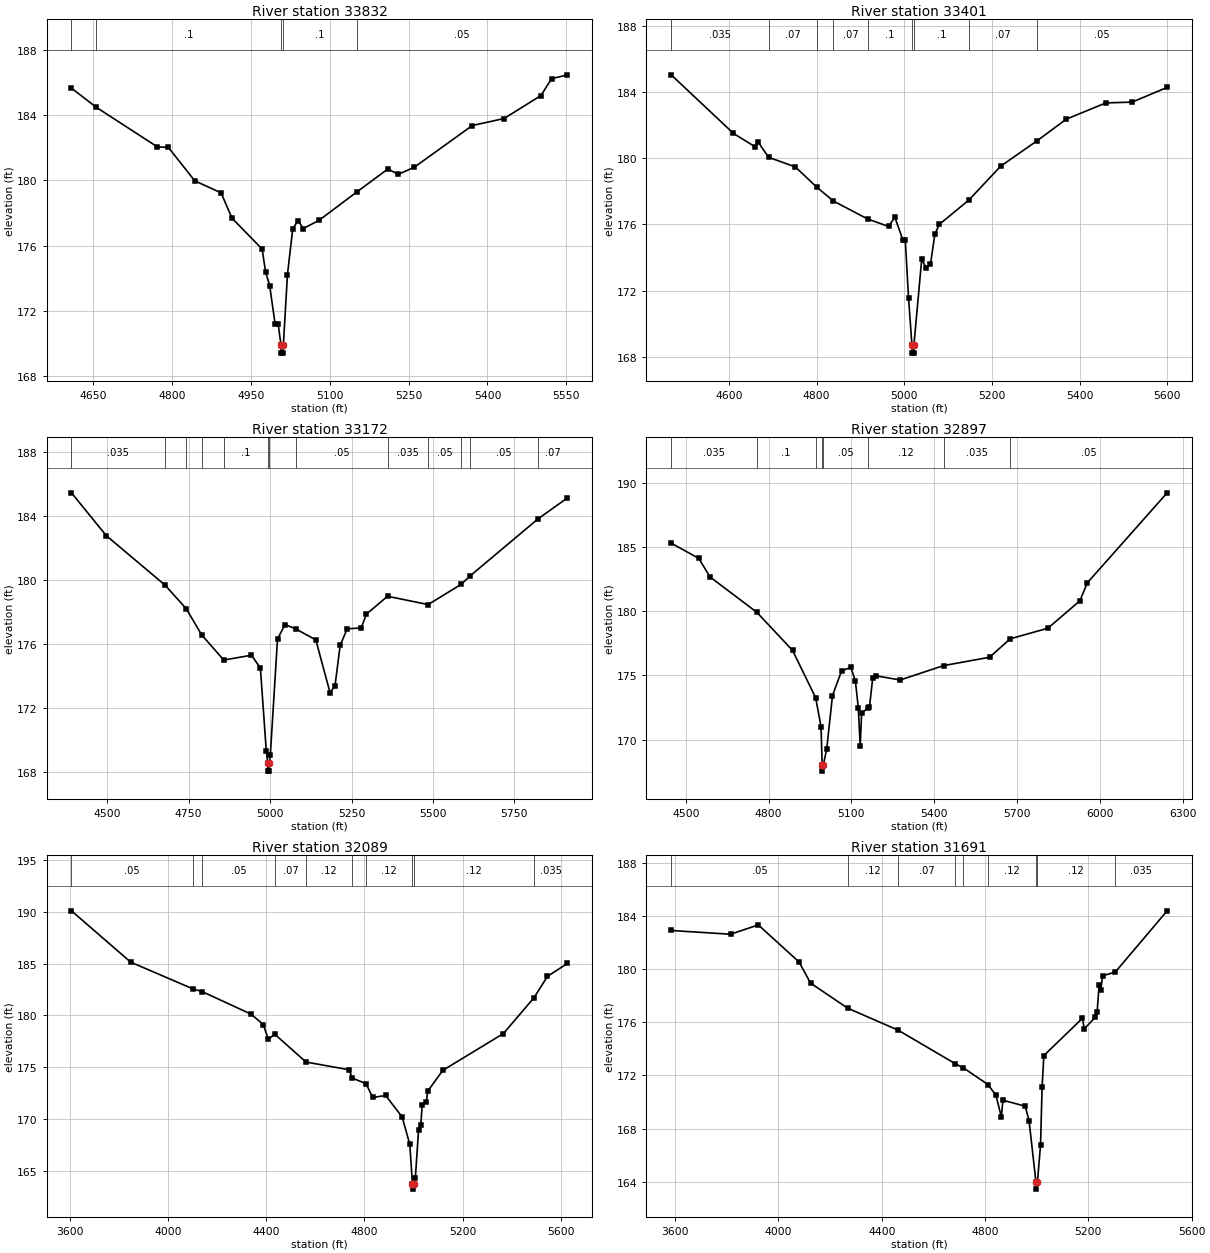
Type RM Length L Ch R = 1 ,33832   ,431,431,431
BEGIN DESCRIPTION:
HOG THIEF CREEK 71.0
END DESCRIPTION:
XS GIS Cut Line= 3
      2522875.02     13486224.98        2523175.       13485975.
        2523225.     13485424.95
#Sta/Elev= 30
  4609.2  185.65  4656.4  184.48  4772.5  182.05  4793.4  182.02  4843.5  179.97
  4893.6  179.23  4914.4  177.68  4971.7  175.78  4978.2  174.38    4986  173.54
  4996.4  171.17  5002.2  171.17  5007.5   169.9  5007.8   169.4  5011.7   169.4
    5012   169.9  5019.8  174.22  5029.8  177.02  5039.8  177.53  5049.9  177.04
    5080  177.55  5151.5  179.28  5210.5  180.69  5230.6  180.37  5260.8   180.8
  5371.2  183.36  5431.5  183.79  5501.7   185.2  5521.8  186.23    5552  186.47
#Mann= 5 ,-1 , 0
  4609.2     .05       0  4656.4      .1       0  5007.5     .05       0
    5012      .1       0  5151.5     .05       0
Bank Sta=5007.5,5012
XS Rating Curve= 0 ,0
Exp/Cntr=0.3,0.1

Type RM Length L Ch R = 1 ,33401   ,229,229,229
BEGIN DESCRIPTION:
HOG THIEF CREEK 70.0
END DESCRIPTION:
XS GIS Cut Line= 3
      2523124.99     13486525.01        2523525.       13486175.
        2523525.     13485575.02
#Sta/Elev= 30
  4468.4  185.05  4610.3  181.51  4659.7   180.7  4667.3  180.96  4690.8  180.06
  4751.7  179.48  4800.3  178.26  4838.4  177.42  4916.7  176.33  4964.3  175.88
  4978.6  176.44  4996.6  175.09  5002.4  175.09  5009.9  171.55  5017.6  168.72
    5018  168.22  5021.9  168.22  5022.2  168.72  5039.9  173.89  5049.9  173.38
  5059.9  173.59  5069.9  175.41  5079.9     176  5147.2  177.47  5219.9  179.52
  5303.1  181.06  5369.9  182.37  5459.9  183.35  5519.9   183.4  5599.9  184.29
#Mann= 9 ,-1 , 0
  4468.4    .035       0  4690.8     .07       0  4800.3      .1       0
  4838.4     .07       0  4916.7      .1       0  5017.6     .05       0
  5022.2      .1       0  5147.2     .07       0  5303.1     .05       0
Bank Sta=5017.6,5022.2
XS Rating Curve= 0 ,0
Exp/Cntr=0.3,0.1

Type RM Length L Ch R = 1 ,33172   ,275,275,275
BEGIN DESCRIPTION:
Mapping XS 01a82fdc
END DESCRIPTION:
XS GIS Cut Line= 3
      2523133.82     13486568.46       2523649.4     13486302.86
       2524467.1     13485834.11
#Sta/Elev= 30
  4390.3  185.44  4497.3  182.76  4677.3  179.67  4742.7  178.19  4789.5  176.57
  4857.8  174.98  4942.8  175.28  4970.3  174.48  4988.3   169.3  4992.8  168.53
  4993.1  168.03    4997  168.03  4997.4  168.53  5000.8  169.04  5022.8  176.29
  5045.9   177.2  5078.6  176.93  5140.4  176.24  5184.2  172.93  5199.3  173.37
  5215.2   175.9  5236.7  176.93  5279.9  176.99  5295.7  177.85  5360.6  178.97
    5485  178.45  5586.3  179.71  5615.2  180.26  5822.5  183.81  5912.8  185.12
#Mann= 13 ,-1 , 0
  4390.3    .035       0  4677.3     .07       0  4742.7      .1       0
  4789.5     .07       0  4857.8      .1       0  4992.8     .05       0
  4997.4      .1       0  5078.6     .05       0  5360.6    .035       0
    5485     .05       0  5586.3     .07       0  5615.2     .05       0
  5822.5     .07       0
Bank Sta=4992.8,4997.4
XS Rating Curve= 0 ,0
Exp/Cntr=0.3,0.1

Type RM Length L Ch R = 1 ,32897   ,808,808,808
BEGIN DESCRIPTION:
Mapping XS 43e342ea
END DESCRIPTION:
XS GIS Cut Line= 4
       2523175.4     13486610.15      2523722.32     13486547.65
      2524571.28     13486302.86      2524894.18      13486136.2
#Sta/Elev= 30
    4447   185.3  4547.2  184.11  4587.5  182.67    4757  179.92  4886.6  176.95
  4970.5  173.26  4990.1     171    4994  168.04  4994.3  167.54  4998.6  168.04
  5010.7  169.28  5031.5  173.42  5064.5  175.35  5098.2  175.62  5114.7  174.53
  5125.2  172.46  5131.9  169.51  5137.1  172.03  5160.2  172.48  5165.5  172.53
  5177.2  174.77  5187.6  174.97  5276.9  174.64  5434.1  175.76  5600.6  176.41
  5675.9  177.85    5812  178.67  5927.7   180.8  5955.5  182.22  6244.4  189.22
#Mann= 8 ,-1 , 0
    4447    .035       0    4757      .1       0  4970.5     .05       0
    4994     .05       0  4998.6     .05       0  5160.2     .12       0
  5434.1    .035       0  5675.9     .05       0
Bank Sta=4994,4998.6
XS Rating Curve= 0 ,0
Exp/Cntr=0.3,0.1

Type RM Length L Ch R = 1 ,32089   ,398,398,398
BEGIN DESCRIPTION:
Mapping XS fc8ce714
END DESCRIPTION:
XS GIS Cut Line= 3
      2523045.23     13486813.27      2524253.57     13486745.56
      2524977.54     13486386.18
#Sta/Elev= 30
  3607.8  190.07    3849  185.13  4102.1  182.56  4139.3   182.3  4338.7  180.13
  4388.8  179.12  4408.8  177.71  4435.1   178.2  4562.3  175.52  4736.6  174.78
  4751.5  173.97  4807.1  173.43  4833.5  172.11  4886.6   172.3  4953.6  170.24
  4984.8  167.59  4995.5  163.79    4996  163.29    5001  163.79  5007.2  164.32
  5020.6  169.01  5029.6  169.48  5035.2  171.41    5052  171.67  5057.6  172.71
  5119.2  174.72  5365.7  178.26    5490   181.7    5545  183.76  5626.3  185.01
#Mann= 10 ,-1 , 0
  3607.8     .05       0  4102.1    .035       0  4139.3     .05       0
  4435.1     .07       0  4562.3     .12       0  4751.5     .07       0
  4807.1     .12       0  4995.5     .05       0    5001     .12       0
    5490    .035       0
Bank Sta=4995.5,5001
XS Rating Curve= 0 ,0
Exp/Cntr=0.3,0.1

Type RM Length L Ch R = 1 ,31691   ,586,586,586
BEGIN DESCRIPTION:
Mapping XS be728f77
END DESCRIPTION:
XS GIS Cut Line= 3
      2523592.11     13487662.23      2524784.82      13486828.9
      2525086.91     13486474.72
#Sta/Elev= 30
  3584.6   182.9  3814.6  182.62  3921.9  183.32  4079.8  180.53  4124.3  178.94
  4267.6  177.06  4463.4   175.4  4684.3  172.88  4716.3  172.56  4811.3  171.31
  4842.1   170.5    4863  168.88  4869.1  170.13  4955.4  169.68  4970.3   168.6
  4997.2  163.94  4997.6  163.44  5002.7  163.94  5014.8  166.78  5020.9  171.15
  5027.6  173.49  5176.8  176.29  5184.5   175.5  5227.3  176.38  5233.9  176.77
  5241.6   178.8  5248.2  178.46    5255  179.49  5304.1  179.77  5505.1  184.38
#Mann= 9 ,-1 , 0
  3584.6     .05       0  4267.6     .12       0  4463.4     .07       0
  4684.3     .12       0  4716.3     .07       0  4811.3     .12       0
  4997.2     .05       0  5002.7     .12       0  5304.1    .035       0
Bank Sta=4997.2,5002.7
XS Rating Curve= 0 ,0
Exp/Cntr=0.3,0.1

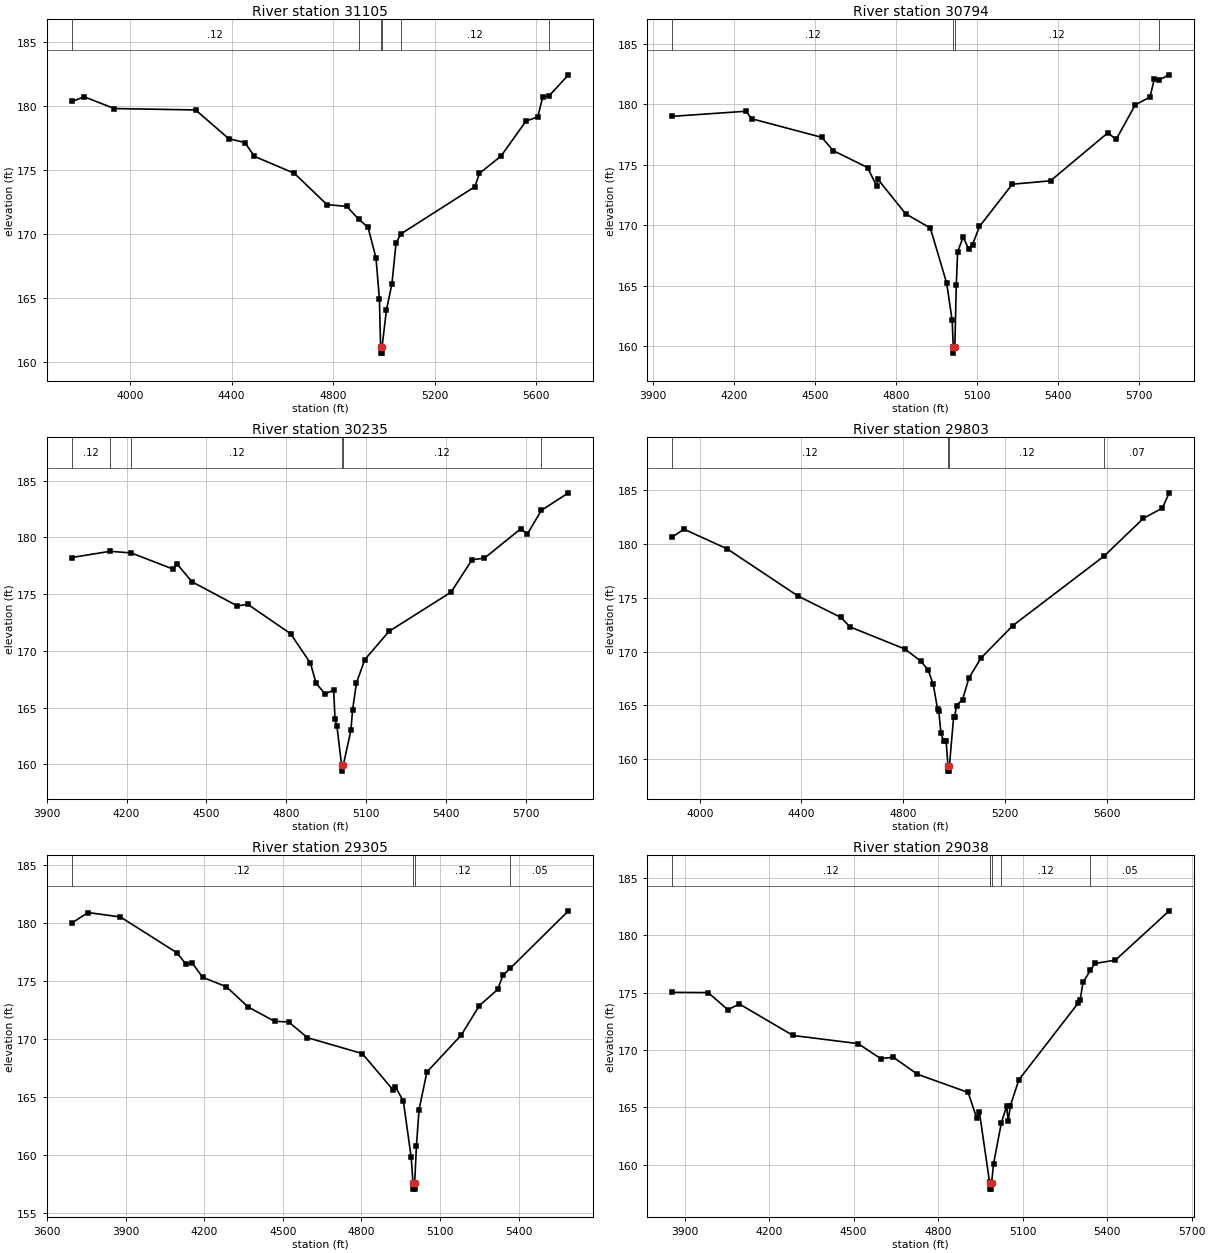
Type RM Length L Ch R = 1 ,31105   ,311,311,311
BEGIN DESCRIPTION:
Mapping XS d3f83d4e
END DESCRIPTION:
XS GIS Cut Line= 3
      2525003.56     13488474.71      2524826.49     13487599.73
      2525138.81     13486579.48
#Sta/Elev= 30
  3768.4  180.35  3819.1  180.71    3937   179.8  4257.8  179.69  4388.4  177.45
  4451.7  177.15  4489.8  176.07    4647  174.75  4775.7  172.31  4854.3  172.16
  4900.9  171.17    4938  170.53  4969.3  168.13  4982.8  164.91  4987.4  161.22
  4987.9  160.72  4992.7  160.72  4993.2  161.22  5010.4  164.09  5032.1  166.14
  5048.3  169.31  5067.3  170.02    5359   173.7  5377.2  174.74  5462.5   176.1
  5560.8  178.82  5607.3  179.15  5626.3  180.67  5652.9  180.81  5728.1  182.43
#Mann= 6 ,-1 , 0
  3768.4     .12       0  4900.9      .1       0  4987.4     .05       0
  4993.2      .1       0  5067.3     .12       0  5652.9    .035       0
Bank Sta=4987.4,4993.2
XS Rating Curve= 0 ,0
Exp/Cntr=0.3,0.1

Type RM Length L Ch R = 1 ,30794   ,559,559,559
BEGIN DESCRIPTION:
Mapping XS 05f41d61
END DESCRIPTION:
XS GIS Cut Line= 3
      2525378.57     13488417.42      2525154.61     13487636.19
      2525310.86     13486620.54
#Sta/Elev= 30
  3972.2     179  4245.2  179.42    4266   178.8  4526.1  177.26  4567.7  176.17
  4695.2  174.77    4729  173.24  4734.2  173.78  4836.7  170.94  4927.8  169.77
  4988.5   165.2  5008.7  162.13  5012.8  159.93  5013.2  159.43  5018.6  159.93
  5023.9  165.05  5028.9  167.79  5049.2  169.02  5069.4  168.07    5084   168.4
  5109.9   169.9  5231.3  173.39  5372.9  173.67  5585.4  177.64  5615.8  177.09
  5686.6  179.94  5741.6   180.6  5757.4  182.11  5775.9  182.02  5812.5  182.43
#Mann= 4 ,-1 , 0
  3972.2     .12       0  5012.8     .05       0  5018.6     .12       0
  5775.9    .035       0
Bank Sta=5012.8,5018.6
XS Rating Curve= 0 ,0
Exp/Cntr=0.3,0.1

Type RM Length L Ch R = 1 ,30235   ,432,432,432
BEGIN DESCRIPTION:
Mapping XS 539549b5
END DESCRIPTION:
XS GIS Cut Line= 3
       2525649.4     13488386.23      2525696.28     13487490.36
      2525415.03     13486563.28
#Sta/Elev= 30
  3993.2  178.23  4137.9  178.78  4217.1  178.64    4375  177.21  4388.7  177.69
  4445.1   176.1  4615.3  173.97  4655.3   174.1  4815.6  171.52  4890.3  168.92
  4911.8  167.14  4944.6  166.22  4977.5  166.52  4982.8  163.96    4990  163.33
  5007.5  159.89    5008  159.39  5013.4  159.89  5042.2  162.98  5048.6  164.79
  5063.1  167.17  5094.5  169.23  5185.4  171.72  5418.4  175.18  5497.1  178.03
  5543.8  178.18  5679.7  180.76    5705  180.31  5757.4  182.39  5859.1  183.94
#Mann= 6 ,-1 , 0
  3993.2     .12       0  4137.9     .07       0  4217.1     .12       0
  5007.5     .05       0  5013.4     .12       0  5757.4    .035       0
Bank Sta=5007.5,5013.4
XS Rating Curve= 0 ,0
Exp/Cntr=0.3,0.1

Type RM Length L Ch R = 1 ,29803   ,498,498,498
BEGIN DESCRIPTION:
Mapping XS eb553427
END DESCRIPTION:
XS GIS Cut Line= 3
      2525868.16     13488370.52      2526029.61     13487271.61
      2525737.94     13486479.94
#Sta/Elev= 30
  3891.9  180.67  3937.9  181.39  4107.8  179.56  4386.9  175.16  4554.5  173.18
  4591.2  172.29  4807.1  170.23  4870.3  169.08  4898.1  168.28  4918.3  166.93
    4935  164.67    4940  164.44  4948.6   162.4  4958.8  161.68  4968.9  161.68
    4976  159.36  4976.5  158.86  4981.4  158.86  4981.9  159.36  4998.4  163.91
  5002.6  163.91  5009.7  164.97  5033.4  165.52  5058.5  167.53  5105.6  169.38
  5230.5   172.4  5591.4  178.91    5745  182.41  5819.6  183.36  5846.3  184.78
#Mann= 4 ,-1 , 0
  3891.9     .12       0    4976     .05       0  4981.9     .12       0
  5591.4     .07       0
Bank Sta=4976,4981.9
XS Rating Curve= 0 ,0
Exp/Cntr=0.3,0.1

Type RM Length L Ch R = 1 ,29305   ,267,267,267
BEGIN DESCRIPTION:
Mapping XS b2631e0d
END DESCRIPTION:
XS GIS Cut Line= 3
      2526055.64     13488547.69      2526477.53     13487521.61
      2526482.74     13486735.15
#Sta/Elev= 30
  3693.8  179.96    3757  180.88  3880.5   180.5  4095.5  177.42  4130.3  176.44
  4154.3  176.53  4194.1   175.3  4284.9  174.48  4367.6  172.74  4468.8   171.5
  4522.2  171.45    4594  170.09  4803.2  168.72  4919.8  165.61  4929.8  165.84
  4959.8  164.63  4989.8  159.77  4996.7  157.53  4997.2  157.03  5002.5  157.03
    5003  157.53  5009.8  160.78  5019.8  163.89  5049.8  167.13  5180.7  170.31
  5249.8  172.85  5319.8  174.25  5339.8  175.47  5368.2  176.08  5589.7  181.03
#Mann= 4 ,-1 , 0
  3693.8     .12       0  4996.7     .05       0    5003     .12       0
  5368.2     .05       0
Bank Sta=4996.7,5003
XS Rating Curve= 0 ,0
Exp/Cntr=0.3,0.1

Type RM Length L Ch R = 1 ,29038   ,671,671,671
BEGIN DESCRIPTION:
Mapping XS 6e1dfb7c
END DESCRIPTION:
XS GIS Cut Line= 4
      2526644.19     13488521.63      2526717.11     13487740.36
      2526732.74     13487250.77      2526873.36     13486782.02
#Sta/Elev= 30
  3856.4  175.04  3983.6  175.02  4053.9  173.52  4094.1  174.03  4284.9  171.28
  4515.9  170.57  4596.2  169.26  4641.1  169.38  4726.5   167.9  4906.6  166.31
  4936.6   164.1  4946.6  164.59  4982.7  158.46  4983.5  158.38    4984  157.88
  4989.3  157.88  4989.8  158.38  4996.6  160.06  5024.5  163.67  5043.4  165.12
  5048.4  163.78  5056.6  165.17  5086.7  167.42  5297.1   174.1    5304  174.37
  5314.4  175.92  5340.7  176.96  5356.2  177.56  5429.3  177.85  5620.3  182.15
#Mann= 6 ,-1 , 0
  3856.4     .12       0  4982.7     .07       0  4983.5     .05       0
  4989.8     .07       0  5024.5     .12       0  5340.7     .05       0
Bank Sta=4983.5,4989.8
XS Rating Curve= 0 ,0
Exp/Cntr=0.3,0.1