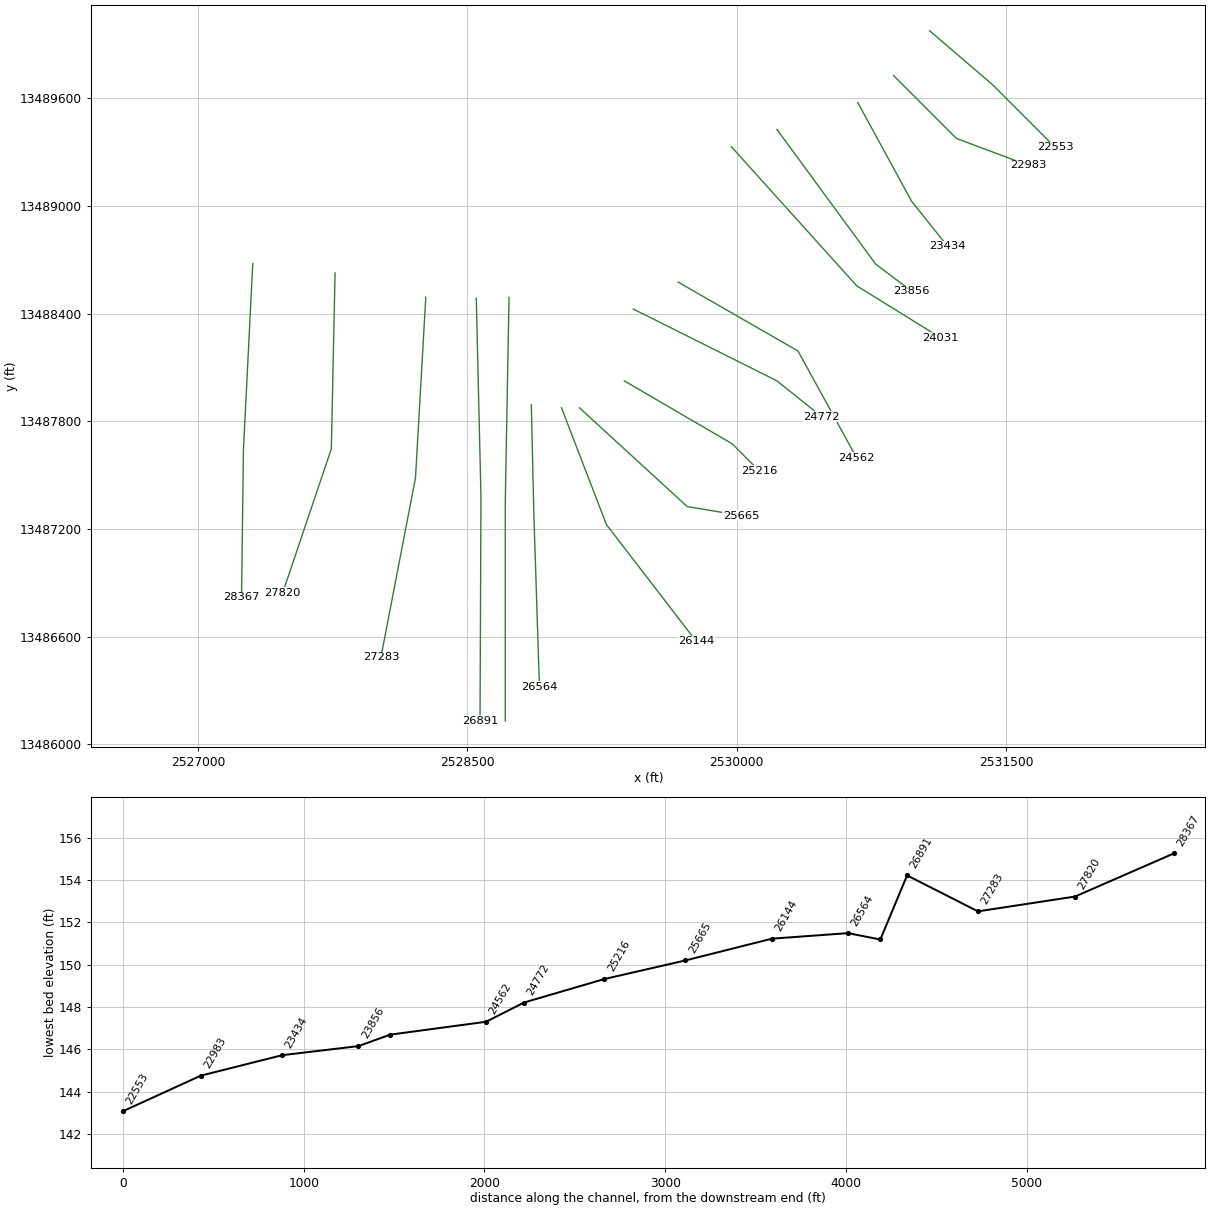
HEC-RAS study HOG THIEF CREEK.prj: HOG THIEF CREEK Base Level Engineering

--- HOG THIEF CREEK.g01 (geometry) --- (continued)

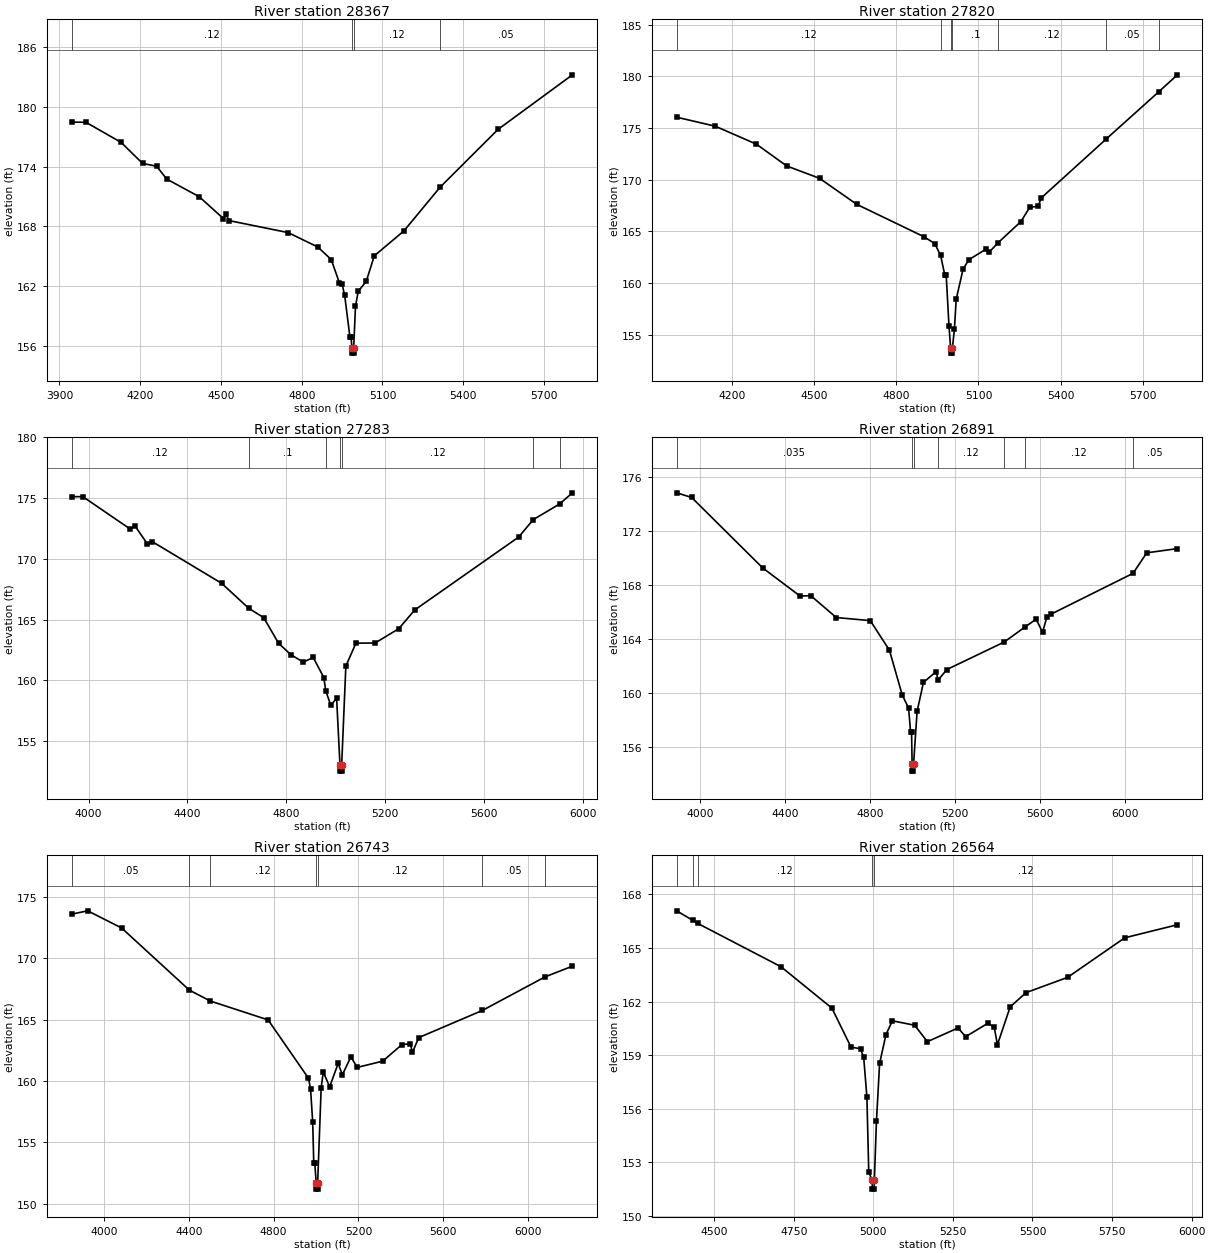
Type RM Length L Ch R = 1 ,28367   ,547,547,547
BEGIN DESCRIPTION:
Mapping XS 98583ac4
END DESCRIPTION:
XS GIS Cut Line= 3
      2527305.65     13488677.85      2527253.57      13487641.4
      2527243.16     13486819.23
#Sta/Elev= 30
  3945.6  178.47  3998.5  178.45  4128.7  176.44  4208.8  174.32  4260.7  174.04
  4298.9  172.74    4419  170.98  4509.2  168.78  4519.2  169.23  4529.2  168.58
  4749.5  167.37  4859.9  165.92  4909.7  164.66  4939.7  162.35  4949.7  162.24
  4959.7  161.05  4979.1  156.88  4983.4  156.88  4986.6  155.76  4987.1  155.26
  4992.5  155.26    4993  155.76  4999.8  159.96  5009.8  161.46  5039.8  162.48
  5069.8  165.04  5179.8  167.54    5314  171.93  5529.8  177.75  5805.6  183.22
#Mann= 4 ,-1 , 0
  3945.6     .12       0  4986.6     .05       0    4993     .12       0
    5314     .05       0
Bank Sta=4986.6,4993
XS Rating Curve= 0 ,0
Exp/Cntr=0.3,0.1

Type RM Length L Ch R = 1 ,27820   ,537,537,537
BEGIN DESCRIPTION:
Mapping XS d1af7a49
END DESCRIPTION:
XS GIS Cut Line= 3
      2527763.99     13488625.82      2527743.15     13487646.61
      2527472.32     13486844.53
#Sta/Elev= 30
  3999.4  176.04  4140.2  175.17  4290.3  173.43  4400.3  171.33  4520.3  170.13
  4656.2  167.61  4900.4  164.49  4940.4  163.82  4962.1  162.67  4977.1  160.77
  4982.3  160.77  4992.5  155.81  4998.3  153.72  4998.8  153.22  5004.5  153.22
    5005  153.72  5012.2  155.52  5018.7  158.42  5043.9  161.35    5065  162.26
  5128.3  163.29  5138.8  162.98  5172.1  163.91  5254.9  165.95  5286.6  167.31
  5318.3  167.44    5328  168.21  5564.9  173.91  5757.1  178.49  5825.4  180.14
#Mann= 7 ,-1 , 0
  3999.4     .12       0  4962.1      .1       0  4998.3     .05       0
    5005      .1       0  5172.1     .12       0  5564.9     .05       0
  5757.1     .12       0
Bank Sta=4998.3,5005
XS Rating Curve= 0 ,0
Exp/Cntr=0.3,0.1

Type RM Length L Ch R = 1 ,27283   ,392,392,392
BEGIN DESCRIPTION:
Mapping XS 97337d2a
END DESCRIPTION:
XS GIS Cut Line= 3
      2528269.19     13488490.36       2528211.9     13487485.15
       2528019.2     13486485.19
#Sta/Elev= 30
  3931.9  175.13  3977.3  175.12  4167.6  172.47  4187.7  172.72  4237.8  171.24
  4257.8  171.42  4538.2  167.99  4648.6  165.92  4708.5  165.16  4768.6  163.05
  4818.7   162.1  4868.8   161.5  4908.8  161.88  4951.5  160.23  4959.8  159.11
  4979.6  157.96  5003.4  158.51    5017  153.02  5017.5  152.52  5023.3  152.52
  5023.8  153.02  5040.7  161.17  5081.5  163.06    5159  163.07  5254.6  164.25
  5319.8   165.8  5739.9   171.8  5798.5  173.23  5905.1  174.52  5957.1  175.44
#Mann= 7 ,-1 , 0
  3931.9     .12       0  4648.6      .1       0  4959.8     .12       0
    5017     .05       0  5023.8     .12       0  5798.5     .07       0
  5905.1     .12       0
Bank Sta=5017,5023.8
XS Rating Curve= 0 ,0
Exp/Cntr=0.3,0.1

Type RM Length L Ch R = 1 ,26891   ,148,148,148
BEGIN DESCRIPTION:
Mapping XS 3570e35a
END DESCRIPTION:
XS GIS Cut Line= 3
      2528550.44     13488485.18      2528576.49     13487380.98
      2528571.28     13486130.99
#Sta/Elev= 30
  3889.6  174.82  3959.8  174.48  4294.9  169.25  4469.9  167.18    4520  167.21
    4640  165.59    4800  165.36  4890.1  163.17  4950.1  159.86  4980.1  158.89
  4989.6   157.1  4994.1   157.1  4996.7  154.72  4997.2  154.22    5003  154.22
  5003.5  154.72  5020.1  158.64  5050.1  160.79  5110.1  161.59  5118.4  160.95
  5160.1  161.74  5429.1  163.77  5527.7  164.89  5580.1  165.47  5610.1  164.49
  5630.1  165.62  5650.1  165.84  6035.5  168.86  6100.1  170.38  6244.1  170.69
#Mann= 7 ,-1 , 0
  3889.6    .035       0  4996.7    .035       0  5003.5    .035       0
  5118.4     .12       0  5429.1      .1       0  5527.7     .12       0
  6035.5     .05       0
Bank Sta=4996.7,5003.5
XS Rating Curve= 0 ,0
Exp/Cntr=0.3,0.1

Type RM Length L Ch R = 1 ,26743   ,179,179,179
BEGIN DESCRIPTION:
Mapping XS 7d2abbd4
END DESCRIPTION:
XS GIS Cut Line= 3
      2528732.74      13488490.4       2528711.9     13487349.73
       2528711.9     13486130.99
#Sta/Elev= 30
  3848.5   173.6  3923.9  173.87  4083.9  172.47  4402.7  167.41  4501.4  166.52
  4774.1  164.98  4964.1  160.23  4974.1  159.36  4984.1  156.67  4989.2  153.29
  4994.2  153.29  5000.6  151.69  5001.1  151.19    5007  151.19  5007.5  151.69
  5024.1  159.46  5034.1  160.74  5064.1  159.53  5104.1  161.43  5124.1  160.51
  5164.1  161.97  5194.1  161.11  5314.1  161.62  5404.1  162.96  5444.1  163.04
  5454.1  162.33  5484.1  163.54  5783.6  165.75  6079.4  168.49  6208.1  169.36
#Mann= 7 ,-1 , 0
  3848.5     .05       0  4402.7     .07       0  4501.4     .12       0
  5000.6     .05       0  5007.5     .12       0  5783.6     .05       0
  6079.4     .12       0
Bank Sta=5000.6,5007.5
XS Rating Curve= 0 ,0
Exp/Cntr=0.3,0.1

Type RM Length L Ch R = 1 ,26564   ,420,420,420
BEGIN DESCRIPTION:
Mapping XS b1aca258
END DESCRIPTION:
XS GIS Cut Line= 3
      2528857.05     13487892.57      2528870.94     13487288.36
      2528902.18     13486319.84
#Sta/Elev= 30
  4381.9  167.08    4433  166.54  4447.5  166.38  4709.6  163.95  4869.6  161.63
  4929.6  159.45  4959.6  159.35  4969.6  158.87  4979.6  156.66  4985.5  152.44
  4996.2  151.99  4996.7  151.49  5002.6  151.49  5003.1  151.99  5009.6  155.28
  5019.6  158.54  5039.7  160.15  5059.7  160.92  5129.7  160.67  5169.7  159.75
  5266.1  160.52  5289.8  160.03  5359.8  160.78  5379.8  160.56  5389.8  159.58
  5429.9   161.7  5479.9   162.5    5610  163.35    5790  165.57  5955.3   166.3
#Mann= 5 ,-1 , 0
  4381.9     .05       0    4433     .07       0  4447.5     .12       0
  4996.2     .05       0  5003.1     .12       0
Bank Sta=4996.2,5003.1
XS Rating Curve= 0 ,0
Exp/Cntr=0.3,0.1

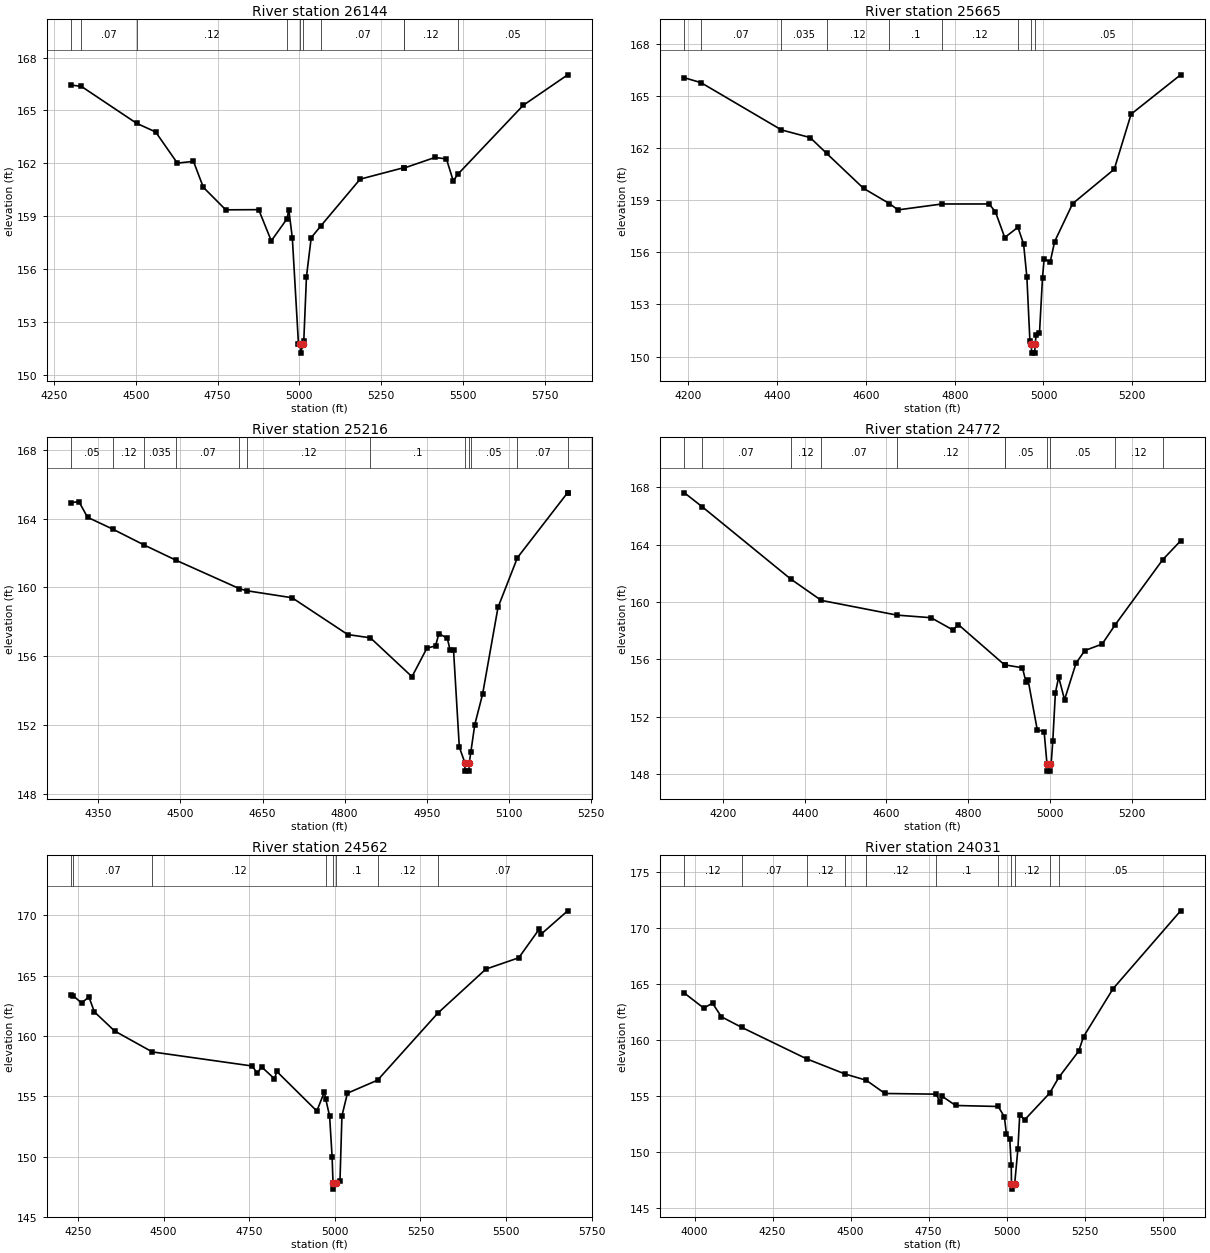
Type RM Length L Ch R = 1 ,26144   ,479,479,479
BEGIN DESCRIPTION:
HOG THIEF CREEK 54.0
END DESCRIPTION:
XS GIS Cut Line= 3
      2529024.99     13487875.04        2529275.       13487225.
      2529774.99     13486575.02
#Sta/Elev= 30
  4303.5  166.44  4334.1  166.36  4502.5  164.27  4560.7  163.78  4627.1  162.01
  4676.4  162.11  4706.4  160.64    4775  159.36  4875.7  159.37  4914.2   157.6
  4962.2  158.85  4967.8  159.36  4978.5  157.76  4997.3  151.74  5003.2  151.73
  5003.7  151.23  5011.2  151.73  5013.5  151.92  5021.7  155.57  5036.2  157.78
  5066.6  158.47  5185.7   161.1  5318.9  161.75  5320.1  161.73  5414.1  162.33
  5449.4  162.25  5470.2  161.01  5484.9  161.39  5684.1  165.29    5820  167.02
#Mann= 10 ,-1 , 0
  4303.5     .05       0  4334.1     .07       0  4502.5     .12       0
  4962.2     .05       0  5003.2     .05       0  5011.2     .05       0
  5066.6     .07       0  5318.9     .05       0  5320.1     .12       0
  5484.9     .05       0
Bank Sta=5003.2,5011.2
XS Rating Curve= 0 ,0
Exp/Cntr=0.3,0.1

Type RM Length L Ch R = 1 ,25665   ,449,449,449
BEGIN DESCRIPTION:
HOG THIEF CREEK 53.0
END DESCRIPTION:
XS GIS Cut Line= 3
      2529124.97     13487875.03        2529725.       13487325.
      2530024.98       13487275.
#Sta/Elev= 30
  4190.9  166.04  4228.3  165.76  4409.6  163.04  4474.3   162.6  4511.4  161.69
  4594.5  159.68    4653   158.8  4672.2  158.44  4771.1  158.78  4877.5  158.78
  4891.7  158.33  4912.7  156.85  4942.4  157.44  4955.2  156.48  4962.6  154.57
  4969.4  150.91  4972.7   150.7  4973.2   150.2  4980.4   150.2  4980.9   150.7
  4983.6  151.24    4991  151.34  4997.8  154.54  5001.5  155.63    5015  155.43
  5025.2  156.62  5065.7   158.8  5159.5  160.78  5197.5  163.95    5309  166.21
#Mann= 9 ,-1 , 0
  4190.9     .05       0  4228.3     .07       0  4409.6    .035       0
  4511.4     .12       0    4653      .1       0  4771.1     .12       0
  4942.4     .05       0  4972.7     .05       0  4980.9     .05       0
Bank Sta=4972.7,4980.9
XS Rating Curve= 0 ,0
Exp/Cntr=0.3,0.1

Type RM Length L Ch R = 1 ,25216   ,444,444,444
BEGIN DESCRIPTION:
HOG THIEF CREEK 52.0
END DESCRIPTION:
XS GIS Cut Line= 3
      2529375.03     13488024.98        2529975.       13487675.
      2530124.98     13487525.02
#Sta/Elev= 30
  4300.8  164.93  4314.4  164.99  4330.1  164.08  4376.2  163.39    4434  162.46
  4491.9  161.58  4607.6  159.93  4620.7  159.81  4703.9   159.4  4805.6  157.26
    4847  157.07    4923  154.81  4950.3  156.47    4966   156.6  4972.2  157.31
  4987.5  157.05  4992.5  156.38  4998.9  156.38  5009.5  150.72  5019.5  149.82
    5020  149.32  5027.3  149.32  5027.8  149.82  5030.7  150.46  5037.8  152.03
    5052  153.79  5080.2  158.84  5115.7  161.73  5207.2   165.5  5207.5   165.5
#Mann= 12 ,-1 , 0
  4300.8     .05       0  4376.2     .12       0    4434    .035       0
  4491.9     .07       0  4607.6    .035       0  4620.7     .12       0
    4847      .1       0  5019.5     .05       0  5027.8      .1       0
  5030.7     .05       0  5115.7     .07       0  5207.2     .05       0
Bank Sta=5019.5,5027.8
XS Rating Curve= 0 ,0
Exp/Cntr=0.3,0.1

Type RM Length L Ch R = 1 ,24772   ,210,210,210
BEGIN DESCRIPTION:
HOG THIEF CREEK 51.0
END DESCRIPTION:
XS GIS Cut Line= 3
      2529424.96     13488425.02        2530225.       13488025.
      2530474.98     13487825.02
#Sta/Elev= 30
  4105.5  167.62  4148.5  166.66  4365.2  161.62  4440.4  160.12  4625.9  159.09
  4709.3  158.91  4762.4  158.06  4776.4  158.42  4889.2  155.62  4889.5  155.62
  4932.9  155.42  4941.3  154.46  4946.9  154.54  4969.2  151.09    4986  150.97
    4993  148.71  4993.5  148.21  5000.9  148.21  5001.4  148.71  5003.2  148.71
  5007.2   150.3  5013.6  153.67  5021.6  154.77    5036  153.19    5064  155.73
  5085.6  156.62    5128  157.07  5159.8  158.41  5276.4  162.96  5320.1  164.27
#Mann= 11 ,-1 , 0
  4105.5     .05       0  4148.5     .07       0  4365.2     .12       0
  4440.4     .07       0  4625.9     .12       0  4889.2     .07       0
  4889.5     .05       0    4993     .05       0  5001.4     .05       0
  5159.8     .12       0  5276.4     .07       0
Bank Sta=4993,5001.4
XS Rating Curve= 0 ,0
Exp/Cntr=0.3,0.1

Type RM Length L Ch R = 1 ,24562   ,531,531,531
BEGIN DESCRIPTION:
HOG THIEF CREEK 50.0
END DESCRIPTION:
XS GIS Cut Line= 3
      2529675.04     13488574.98        2530342.     13488191.59
      2530669.14     13487595.57
#Sta/Elev= 30
  4230.7  163.42  4235.3  163.33  4260.1  162.73  4281.7  163.22  4297.5  161.99
  4356.4  160.41  4466.6  158.67  4758.9   157.5  4772.8  156.91  4786.3  157.42
  4823.6  156.44  4830.4  157.05  4947.3  153.77  4968.9  155.33  4973.2  154.78
  4984.6  153.35  4991.9  149.97  4994.6   147.8  4995.1   147.3    5003   147.8
  5014.9  147.98  5020.6  153.37  5036.7  155.25  5124.8  156.33  5300.2  161.87
    5441  165.53  5537.1  166.47  5596.8  168.84  5602.5  168.43  5679.9  170.36
#Mann= 8 ,-1 , 0
  4230.7     .12       0  4235.3     .07       0  4466.6     .12       0
  4973.2      .1       0  4994.6     .05       0    5003      .1       0
  5124.8     .12       0  5300.2     .07       0
Bank Sta=4994.6,5003
XS Rating Curve= 0 ,0
Exp/Cntr=0.3,0.1

Type RM Length L Ch R = 1 ,24031   ,175,175,175
BEGIN DESCRIPTION:
Mapping XS c617b9bb
END DESCRIPTION:
XS GIS Cut Line= 3
      2529971.27     13489328.75      2530669.16     13488554.47
      2531134.45     13488266.27
#Sta/Elev= 30
  3967.4  164.17  4029.1  162.84  4057.5  163.27  4085.9  162.06  4151.4  161.11
    4359  158.31  4481.8  156.96    4550   156.4  4609.8  155.22    4774  155.16
    4787  154.43  4793.7  154.96  4836.3  154.15  4972.7  154.06  4992.5  153.14
  4999.2  151.58  5009.8  151.14  5014.5  148.84  5015.2  147.19  5015.7  146.69
  5025.6  147.19  5035.8  150.27  5041.7  153.32    5057  152.86  5137.6  155.25
    5167  156.66  5230.7     159  5246.1  160.29  5340.6  164.56  5557.1  171.51
#Mann= 11 ,-1 , 0
  3967.4     .12       0  4151.4     .07       0    4359     .12       0
  4481.8     .07       0    4550     .12       0    4774      .1       0
  4972.7     .12       0  5015.2     .05       0  5025.6     .12       0
  5137.6     .07       0    5167     .05       0
Bank Sta=5015.2,5025.6
XS Rating Curve= 0 ,0
Exp/Cntr=0.3,0.1

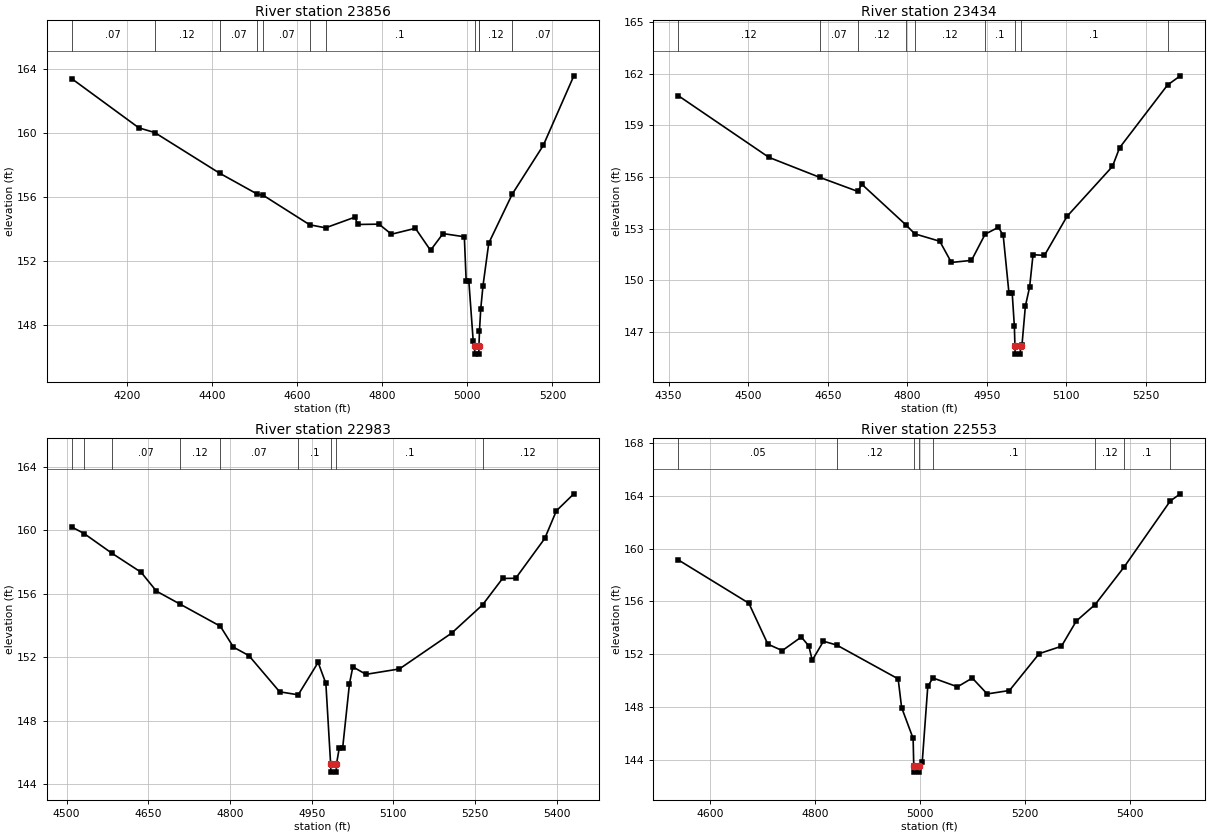
Type RM Length L Ch R = 1 ,23856   ,422,422,422
BEGIN DESCRIPTION:
HOG THIEF CREEK 49.0
END DESCRIPTION:
XS GIS Cut Line= 3
        2530225.       13489425.        2530775.       13488675.
      2530975.04     13488524.97
#Sta/Elev= 30
  4070.1   163.4  4227.9  160.32  4264.9  160.03  4417.7  157.48  4505.6  156.18
  4520.5  156.09  4629.4  154.25  4666.6  154.06  4735.8  154.73    4742  154.27
  4792.2  154.29  4821.5  153.66  4877.8  154.03  4913.3  152.65  4942.7   153.7
  4992.8   153.5  4997.1  150.76  5003.3  150.76  5013.7  146.95  5016.8  146.65
  5017.3  146.15  5026.7  146.15  5027.2  146.65  5028.4  147.61  5031.4  148.99
  5036.6  150.42  5050.2   153.1  5105.6  156.18  5178.3  159.22  5250.2  163.58
#Mann= 11 ,-1 , 0
  4070.1     .07       0  4264.9     .12       0  4417.7     .07       0
  4505.6     .12       0  4520.5     .07       0  4629.4     .12       0
  4666.6      .1       0  5016.8     .05       0  5027.2      .1       0
  5028.4     .12       0  5105.6     .07       0
Bank Sta=5016.8,5027.2
XS Rating Curve= 0 ,0
Exp/Cntr=0.3,0.1

Type RM Length L Ch R = 1 ,23434   ,451,451,451
BEGIN DESCRIPTION:
HOG THIEF CREEK 48.0
END DESCRIPTION:
XS GIS Cut Line= 3
        2530675.     13489574.99        2530975.       13489025.
      2531174.97     13488775.03
#Sta/Elev= 30
  4368.1  160.72    4539  157.14  4635.6  155.97  4706.8  155.16  4714.1  155.58
  4797.7  153.21  4814.1   152.7  4861.2  152.27  4883.1  151.04    4921  151.16
  4946.7  152.68  4971.8  153.08  4980.8  152.61  4991.7  149.24  4997.8  149.24
  5001.8  147.35  5002.9  146.22  5003.4  145.72  5012.9  145.72  5013.4  146.22
  5016.2  146.25  5022.6  148.51  5030.6  149.61    5037  151.49  5058.6  151.45
    5101  153.71  5186.7  156.61  5200.3   157.7  5290.7  161.34  5314.7  161.87
#Mann= 9 ,-1 , 0
  4368.1     .12       0  4635.6     .07       0  4706.8     .12       0
  4797.7     .07       0  4814.1     .12       0  4946.7      .1       0
  5002.9     .05       0  5013.4      .1       0  5290.7     .12       0
Bank Sta=5002.9,5013.4
XS Rating Curve= 0 ,0
Exp/Cntr=0.3,0.1

Type RM Length L Ch R = 1 ,22983   ,430,430,430
BEGIN DESCRIPTION:
HOG THIEF CREEK 47.0
END DESCRIPTION:
XS GIS Cut Line= 3
      2530875.01     13489724.99        2531225.       13489375.
      2531625.04     13489224.99
#Sta/Elev= 30
  4509.4  160.19    4532  159.78  4582.6  158.55  4636.7  157.34  4664.9  156.15
  4707.4  155.35  4782.3  153.94  4806.4  152.62  4834.7  152.09  4891.2  149.81
  4925.3  149.62  4961.9  151.66  4976.1  150.34  4984.9  145.25  4985.4  144.75
  4995.1  144.75  4995.6  145.25  5000.8  146.29    5007  146.29  5019.5  150.33
  5025.7  151.38  5049.8  150.91  5111.2  151.25  5207.3  153.51    5264  155.29
  5300.7  156.95  5324.8  156.96  5378.2  159.47  5399.5  161.21  5431.6  162.28
#Mann= 9 ,-1 , 0
  4509.4     .07       0    4532     .05       0  4582.6     .07       0
  4707.4     .12       0  4782.3     .07       0  4925.3      .1       0
  4984.9     .05       0  4995.6      .1       0    5264     .12       0
Bank Sta=4984.9,4995.6
XS Rating Curve= 0 ,0
Exp/Cntr=0.3,0.1

Type RM Length L Ch R = 1 ,22553   ,450,450,450
BEGIN DESCRIPTION:
HOG THIEF CREEK 46.0
END DESCRIPTION:
XS GIS Cut Line= 3
      2531075.04     13489974.97        2531425.       13489675.
        2531775.       13489325.
#Sta/Elev= 30
  4539.2  159.14  4673.6  155.86  4709.8  152.76  4737.3  152.27  4773.5   153.3
  4787.8  152.62  4794.3  151.54  4815.7  152.98    4841  152.69  4957.9  150.13
  4964.5  147.96  4986.4  145.62  4987.6  143.57  4988.1  143.07  4997.8  143.07
  4998.3  143.57  5003.7   143.8  5014.3  149.56  5024.1   150.2  5070.8  149.53
  5099.1  150.19  5127.4  148.99  5169.8  149.25  5226.4  152.04  5268.8   152.6
  5297.1  154.51    5333  155.76  5388.3  158.61    5476   163.6  5495.1  164.14
#Mann= 8 ,-1 , 0
  4539.2     .05       0    4841     .12       0  4987.6     .05       0
  4998.3     .12       0  5024.1      .1       0    5333     .12       0
  5388.3      .1       0    5476     .12       0
Bank Sta=4987.6,4998.3
XS Rating Curve= 0 ,0
Exp/Cntr=0.3,0.1