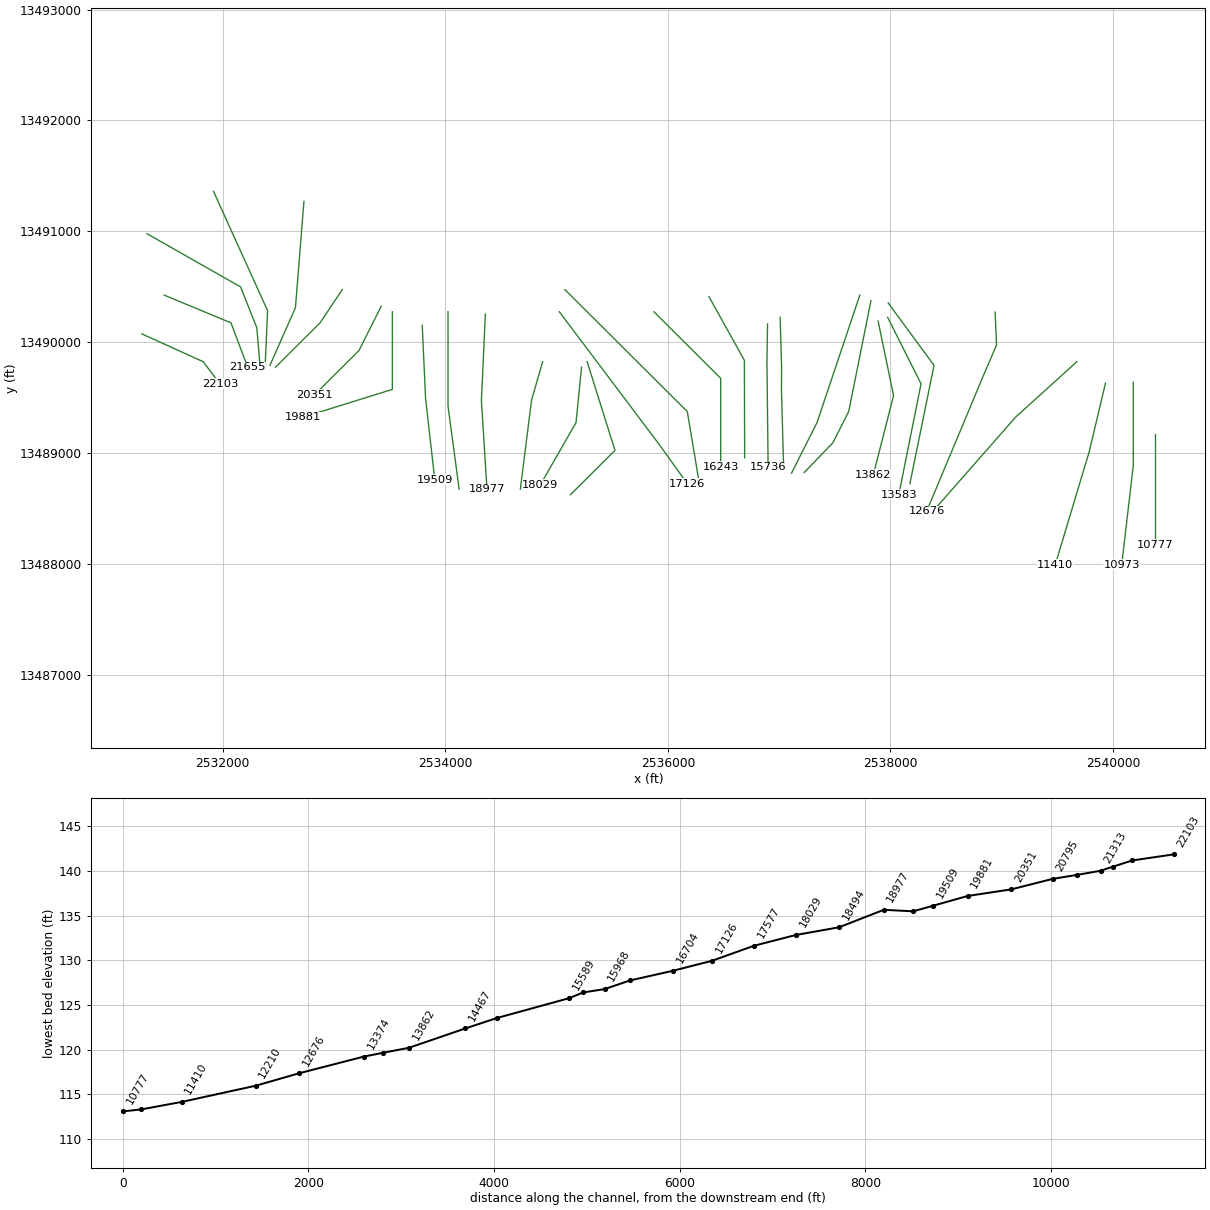
HEC-RAS study HOG THIEF CREEK.prj: HOG THIEF CREEK Base Level Engineering

--- HOG THIEF CREEK.g01 (geometry) --- (continued)

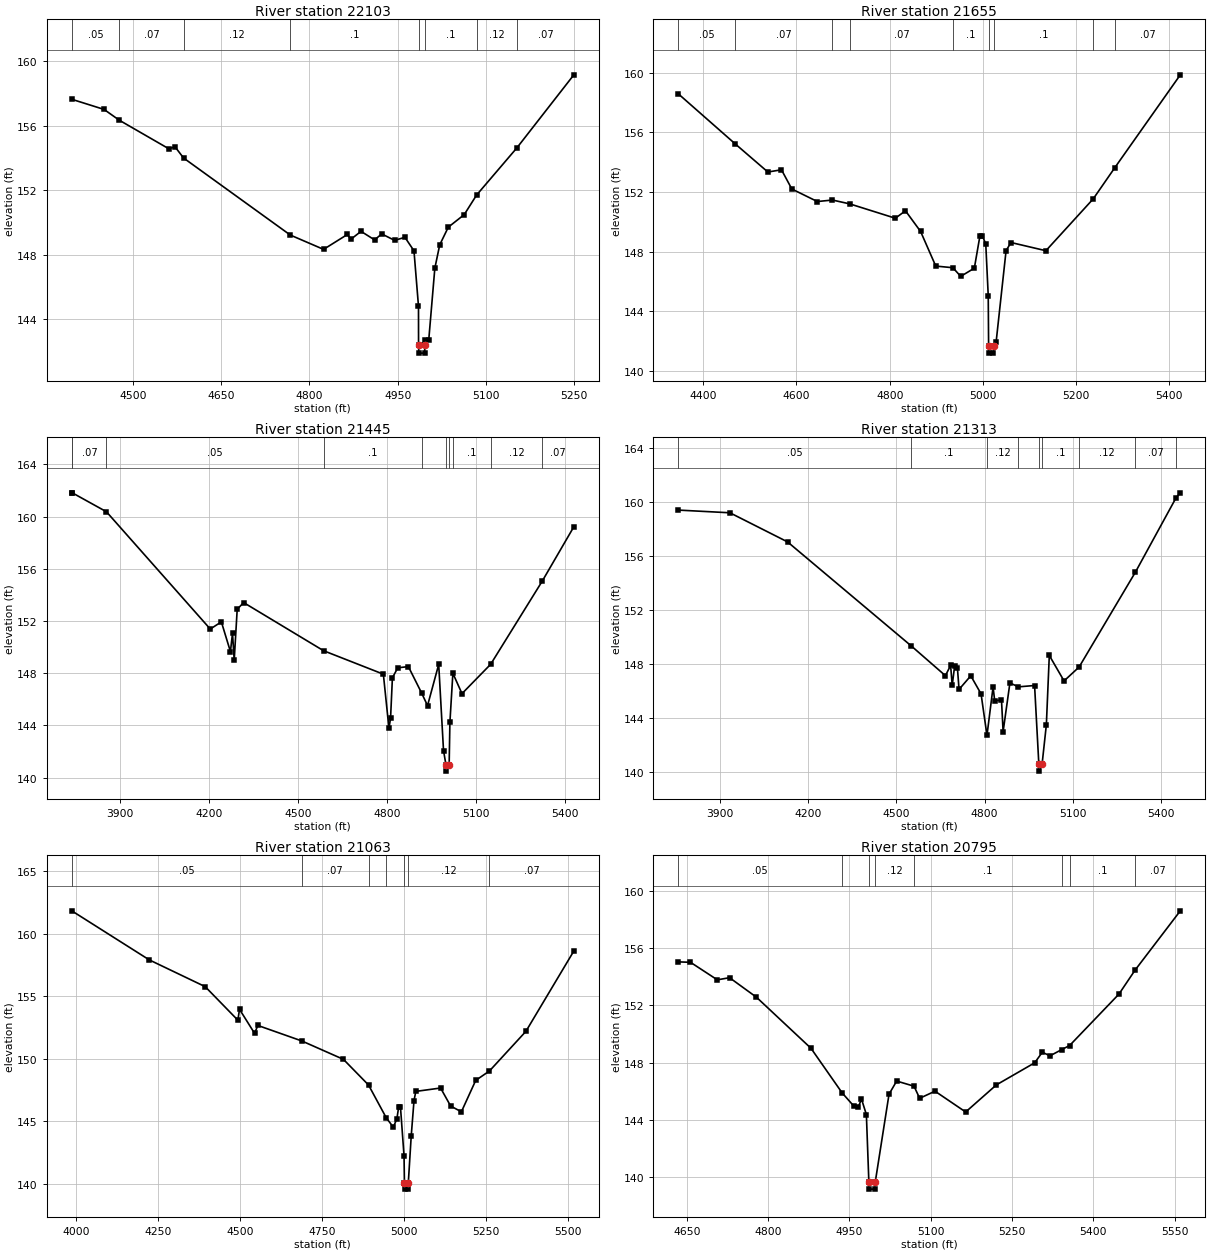
Type RM Length L Ch R = 1 ,22103   ,448,448,448
BEGIN DESCRIPTION:
HOG THIEF CREEK 45.0
END DESCRIPTION:
XS GIS Cut Line= 3
      2531274.98     13490075.01        2531825.       13489825.
      2531975.02     13489624.98
#Sta/Elev= 30
  4395.6  157.65  4450.5  157.02  4476.4  156.35  4560.4  154.58  4571.4  154.69
  4585.8     154  4767.4  149.21    4824  148.32  4864.7  149.25  4870.2  148.94
  4887.7  149.44  4910.8  148.91  4922.9  149.28  4944.9  148.88  4962.4  149.07
  4977.8  148.23  4985.5  144.78  4985.6  142.37  4986.1  141.87  4995.9  141.87
  4996.4  142.37    4997  142.67  5002.9  142.67  5013.3  147.15  5021.6   148.6
  5036.2   149.7  5063.3  150.48  5084.4   151.7  5152.9  154.63  5249.8  159.17
#Mann= 8 ,-1 , 0
  4395.6     .05       0  4476.4     .07       0  4585.8     .12       0
  4767.4      .1       0  4985.6     .05       0  4996.4      .1       0
  5084.4     .12       0  5152.9     .07       0
Bank Sta=4985.6,4996.4
XS Rating Curve= 0 ,0
Exp/Cntr=0.3,0.1

Type RM Length L Ch R = 1 ,21655   ,210,210,210
BEGIN DESCRIPTION:
HOG THIEF CREEK 44.0
END DESCRIPTION:
XS GIS Cut Line= 3
      2531475.03     13490424.99        2532075.       13490175.
      2532225.01     13489774.97
#Sta/Elev= 30
  4346.3  158.59  4468.8  155.22  4538.6  153.34  4567.8  153.49    4590   152.2
  4644.7  151.36  4677.2  151.46  4714.5   151.2  4812.1  150.24  4833.8  150.74
  4866.3  149.35  4898.8  147.03  4935.5  146.92  4952.4  146.34  4981.6  146.89
  4993.6  149.06  4998.9  149.06  5006.1  148.51  5011.4  145.05  5012.2  141.69
  5012.7  141.19  5022.6  141.19  5023.1  141.69  5028.3  141.93  5049.7  148.07
  5060.3  148.61  5135.1  148.06  5236.7  151.54  5282.5  153.61  5423.5  159.86
#Mann= 9 ,-1 , 0
  4346.3     .05       0  4468.8     .07       0  4677.2      .1       0
  4714.5     .07       0  4935.5      .1       0  5012.2     .05       0
  5023.1      .1       0  5236.7     .12       0  5282.5     .07       0
Bank Sta=5012.2,5023.1
XS Rating Curve= 0 ,0
Exp/Cntr=0.3,0.1

Type RM Length L Ch R = 1 ,21445   ,132,132,132
BEGIN DESCRIPTION:
Mapping XS c7875cad
END DESCRIPTION:
XS GIS Cut Line= 4
      2531320.85     13490978.74      2532161.12     13490499.58
      2532306.95     13490131.52      2532334.74     13489805.09
#Sta/Elev= 30
  3737.8  161.82  3739.5  161.82  3854.5  160.37  4204.2  151.38  4241.6  151.93
  4272.1  149.65  4279.1  151.06  4284.8  148.99  4294.9  152.89  4316.5  153.41
  4585.6  149.72  4787.1  147.92    4806  143.76  4811.4  144.56  4817.6  147.65
  4835.8  148.41  4871.4   148.5  4916.3  146.46  4935.9  145.51  4973.5  148.67
  4989.7  142.07  4997.8  140.99  4998.3  140.49  5008.7  140.99  5011.2  144.23
  5021.2  147.99  5051.9  146.43  5148.5  148.68  5322.1  155.05  5428.6  159.22
#Mann= 10 ,-1 , 0
  3737.8    .035       0  3739.5     .07       0  3854.5     .05       0
  4585.6      .1       0  4916.3     .12       0  4997.8     .05       0
  5008.7     .12       0  5021.2      .1       0  5148.5     .12       0
  5322.1     .07       0
Bank Sta=4997.8,5008.7
XS Rating Curve= 0 ,0
Exp/Cntr=0.3,0.1

Type RM Length L Ch R = 1 ,21313   ,250,250,250
BEGIN DESCRIPTION:
Mapping XS 648d1336
END DESCRIPTION:
XS GIS Cut Line= 3
      2531918.08     13491360.65      2532404.18      13490284.3
      2532380.74     13489760.45
#Sta/Elev= 30
  3759.5  159.39    3935  159.19  4130.9  157.03  4551.3  149.31    4667  147.11
  4684.7  147.87  4690.1  146.39  4698.4  147.84  4707.8  147.69  4713.3  146.09
  4753.2   147.1  4788.1  145.76  4808.2  142.68  4828.9  146.27  4834.4  145.25
  4857.5   145.3    4863  142.96  4886.1  146.57    4915  146.28  4969.9  146.38
  4984.4  140.53  4984.9  140.03  4995.3  140.53  5009.9  143.47  5019.9  148.61
    5070  146.72  5121.1  147.75  5312.2  154.78  5450.9  160.32  5464.9  160.67
#Mann= 9 ,-1 , 0
  3759.5     .05       0  4551.3      .1       0  4808.2     .12       0
    4915      .1       0  4984.4     .05       0  4995.3      .1       0
  5121.1     .12       0  5312.2     .07       0  5450.9     .12       0
Bank Sta=4984.4,4995.3
XS Rating Curve= 0 ,0
Exp/Cntr=0.3,0.1

Type RM Length L Ch R = 1 ,21063   ,268,268,268
BEGIN DESCRIPTION:
Mapping XS e610b344
END DESCRIPTION:
XS GIS Cut Line= 3
      2532730.57     13491270.45      2532654.18     13490312.08
      2532425.02     13489791.27
#Sta/Elev= 30
  3987.2  161.82  4223.4   157.9  4393.9  155.76  4493.5  153.08  4498.5  153.95
  4544.4  152.03  4554.4  152.66  4688.5  151.42  4815.3  149.95  4891.8   147.9
  4945.8  145.28  4967.3  144.53  4978.2   145.2  4983.7  146.16  4989.2  146.11
    5000  142.24  5001.2  140.08  5001.7  139.58  5012.5  139.58    5013  140.08
  5021.9  143.83  5030.4  146.66  5035.9  147.39  5111.4  147.66  5142.1  146.22
  5174.8  145.76  5218.5  148.27  5260.3  149.02  5371.5  152.19  5517.6  158.61
#Mann= 7 ,-1 , 0
  3987.2     .05       0  4688.5     .07       0  4891.8     .05       0
  4945.8     .12       0  5001.2     .05       0    5013     .12       0
  5260.3     .07       0
Bank Sta=5001.2,5013
XS Rating Curve= 0 ,0
Exp/Cntr=0.3,0.1

Type RM Length L Ch R = 1 ,20795   ,444,444,444
BEGIN DESCRIPTION:
HOG THIEF CREEK 42.0
END DESCRIPTION:
XS GIS Cut Line= 3
      2533075.02     13490475.03        2532875.       13490175.
      2532474.98     13489774.98
#Sta/Elev= 30
  4634.4  155.06    4657  155.03  4706.5   153.8  4729.1  153.95  4778.7  152.58
  4879.3     149  4936.8  145.87  4958.9  144.92  4966.4  144.85  4972.5  145.44
  4981.5  144.35  4986.1  139.62  4986.6  139.12  4997.4  139.12  4997.9  139.62
  5023.3  145.78  5037.4   146.7  5069.4  146.34  5079.8  145.49  5108.1  145.99
  5164.7  144.53  5221.3  146.43    5292  147.98  5306.1  148.72  5320.3  148.47
    5342  148.91  5356.4  149.19  5447.5   152.8  5477.2  154.48  5560.7  158.64
#Mann= 8 ,-1 , 0
  4634.4     .05       0  4936.8     .12       0  4986.1     .05       0
  4997.9     .12       0  5069.4      .1       0    5342     .12       0
  5356.4      .1       0  5477.2     .07       0
Bank Sta=4986.1,4997.9
XS Rating Curve= 0 ,0
Exp/Cntr=0.3,0.1

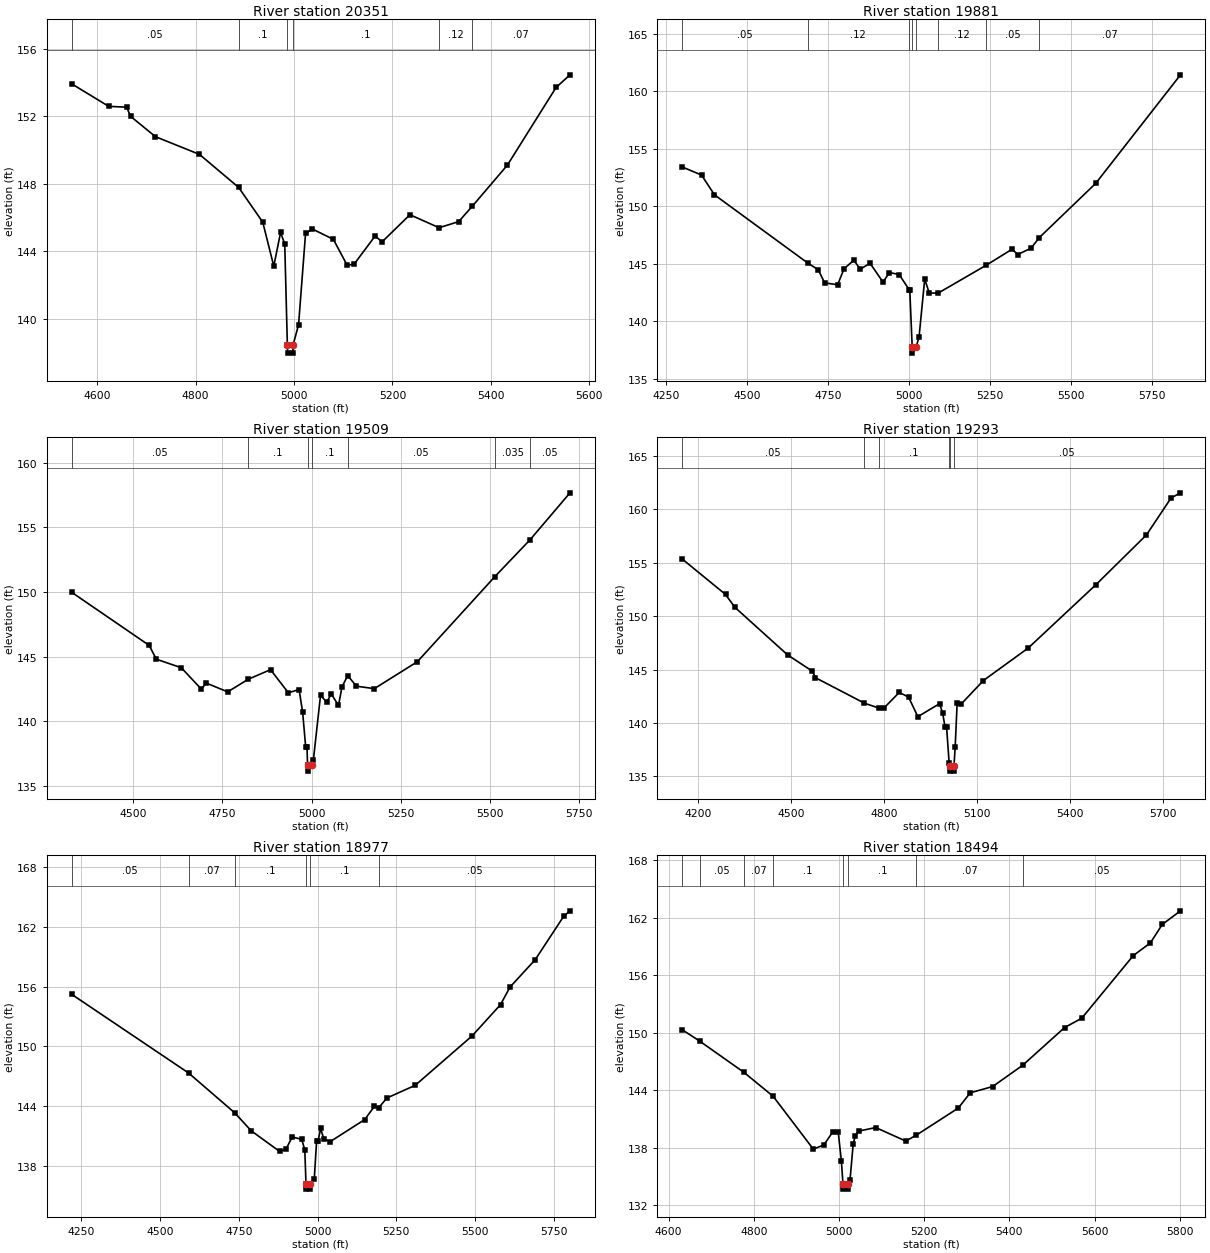
Type RM Length L Ch R = 1 ,20351   ,470,470,470
BEGIN DESCRIPTION:
HOG THIEF CREEK 41.0
END DESCRIPTION:
XS GIS Cut Line= 3
      2533424.99     13490324.98        2533225.       13489925.
      2532824.98     13489524.98
#Sta/Elev= 30
    4548  153.93  4623.4  152.59  4659.8  152.54  4668.2  151.99  4718.5  150.79
  4807.9  149.74  4887.5  147.78  4936.5  145.72  4958.9  143.11  4972.8  145.12
  4981.2  144.41  4986.5  138.45    4987  137.95  4997.8  137.95  4998.3  138.45
  5009.3  139.64  5023.5  145.05  5037.6  145.31    5080   144.7  5108.3  143.15
  5122.5  143.24  5164.9   144.9    5179  144.55  5235.6  146.16  5294.9  145.39
  5334.6  145.75  5362.5  146.67  5433.6   149.1  5532.6  153.71  5560.9  154.46
#Mann= 6 ,-1 , 0
    4548     .05       0  4887.5      .1       0  4986.5     .05       0
  4998.3      .1       0  5294.9     .12       0  5362.5     .07       0
Bank Sta=4986.5,4998.3
XS Rating Curve= 0 ,0
Exp/Cntr=0.3,0.1

Type RM Length L Ch R = 1 ,19881   ,372,372,372
BEGIN DESCRIPTION:
HOG THIEF CREEK 40.0
END DESCRIPTION:
XS GIS Cut Line= 3
        2533525.     13490274.95        2533525.       13489575.
      2532725.01       13489325.
#Sta/Elev= 30
    4300  153.41    4360   152.7    4400  150.98  4687.2  145.06    4720  144.47
    4740  143.32    4780  143.16    4800  144.56    4830  145.29    4850  144.51
    4880  145.03    4920  143.39    4940  144.22    4970  144.05  5000.6  142.73
  5002.6  142.73  5010.2  137.71  5010.7  137.21  5022.1  137.71  5031.4  138.65
  5048.7  143.65  5062.8  142.44  5090.1  142.43  5238.8  144.86    5319  146.26
  5335.2  145.78  5377.1  146.34  5402.4  147.26  5576.2  151.97  5838.1  161.42
#Mann= 8 ,-1 , 0
    4300     .05       0  4687.2     .12       0  5000.6      .1       0
  5010.2     .05       0  5022.1      .1       0  5090.1     .12       0
  5238.8     .05       0  5402.4     .07       0
Bank Sta=5010.2,5022.1
XS Rating Curve= 0 ,0
Exp/Cntr=0.3,0.1

Type RM Length L Ch R = 1 ,19509   ,216,216,216
BEGIN DESCRIPTION:
Mapping XS ac5e2c2a
END DESCRIPTION:
XS GIS Cut Line= 3
      2533793.22     13490152.48      2533823.61     13489492.73
      2533906.03     13488759.59
#Sta/Elev= 30
  4326.8  149.98  4544.5  145.86  4564.5  144.79  4634.6  144.13  4690.6  142.48
  4704.7  142.94  4764.7  142.26  4822.5  143.24  4884.9  143.98  4934.9  142.19
    4965  142.44    4975  140.68  4983.6  137.96  4987.2  137.96  4988.8  136.62
  4989.3  136.12  5001.3  136.62  5005.1  136.98  5025.2     142  5042.4  141.46
  5055.4   142.1  5075.5  141.21  5085.6  142.66  5101.5  143.52  5125.8   142.7
  5176.2  142.51  5296.9   144.6  5514.3  151.19  5613.2  154.05    5725  157.68
#Mann= 7 ,-1 , 0
  4326.8     .05       0  4822.5      .1       0  4988.8     .05       0
  5001.3      .1       0  5101.5     .05       0  5514.3    .035       0
  5613.2     .05       0
Bank Sta=4988.8,5001.3
XS Rating Curve= 0 ,0
Exp/Cntr=0.3,0.1

Type RM Length L Ch R = 1 ,19293   ,316,316,316
BEGIN DESCRIPTION:
HOG THIEF CREEK 39.0
END DESCRIPTION:
XS GIS Cut Line= 3
        2534025.     13490275.05        2534025.     13489424.85
        2534125.     13488674.99
#Sta/Elev= 30
  4149.8  155.37  4289.8  152.04  4319.8  150.84  4489.8  146.38  4569.8  144.85
  4579.8  144.24  4737.3  141.86  4783.5   141.4  4799.8  141.38  4849.8  142.86
  4879.8  142.43  4909.8  140.59  4979.8  141.81  4989.8  140.93  4997.4  139.63
  5002.4  139.63  5010.7  136.25  5013.8  135.99  5014.3  135.49  5025.8  135.49
  5026.3  135.99  5030.1  137.72  5036.5  141.88  5050.3   141.8  5120.9  143.97
    5266  147.03  5484.1  152.96  5646.8  157.62  5726.2  161.08  5756.5  161.56
#Mann= 6 ,-1 , 0
  4149.8     .05       0  4737.3     .07       0  4783.5      .1       0
  5010.7     .05       0  5013.8     .05       0  5026.3     .05       0
Bank Sta=5013.8,5026.3
XS Rating Curve= 0 ,0
Exp/Cntr=0.3,0.1

Type RM Length L Ch R = 1 ,18977   ,483,483,483
BEGIN DESCRIPTION:
HOG THIEF CREEK 38.0
END DESCRIPTION:
XS GIS Cut Line= 3
      2534360.59     13490254.42        2534325.       13489475.
        2534375.     13488674.99
#Sta/Elev= 30
  4219.4  155.23  4590.9  147.32  4737.6  143.31  4789.4  141.52  4879.5  139.45
  4899.5  139.65  4919.5  140.89  4949.6  140.67  4959.6   139.6  4963.3  136.16
  4963.8  135.66  4975.4  135.66  4975.9  136.16  4989.6  136.67  4997.1  140.53
  5002.1  140.53  5009.7  141.76  5019.7  140.72  5039.7  140.42  5149.9  142.65
    5180  143.96  5194.3  143.84  5220.1  144.81  5310.2  146.09  5490.6  151.05
  5580.8  154.19  5610.8  155.95    5691  158.71  5781.2  163.06  5801.2  163.61
#Mann= 6 ,-1 , 0
  4219.4     .05       0  4590.9     .07       0  4737.6      .1       0
  4963.3     .05       0  4975.9      .1       0  5194.3     .05       0
Bank Sta=4963.3,4975.9
XS Rating Curve= 0 ,0
Exp/Cntr=0.3,0.1

Type RM Length L Ch R = 1 ,18494   ,465,465,465
BEGIN DESCRIPTION:
HOG THIEF CREEK 37.0
END DESCRIPTION:
XS GIS Cut Line= 3
      2534874.99     13489824.96        2534775.       13489475.
        2534675.     13488674.99
#Sta/Elev= 30
  4631.7  150.33  4672.8  149.14  4776.2   145.9  4845.5  143.38  4939.8  137.87
  4964.5  138.31  4985.3  139.65  4998.2  139.67  5005.7  136.64  5009.5   134.2
    5010   133.7  5021.7   133.7  5022.2   134.2  5025.9  134.63  5033.5  138.43
  5038.5  139.28  5046.1  139.75  5086.4  140.12  5156.9  138.71  5181.8  139.33
  5280.4  142.16  5308.1  143.74    5361   144.4  5431.2  146.61  5529.8  150.55
  5570.1  151.52    5691  158.05  5731.3  159.38  5759.1   161.3  5801.9  162.72
#Mann= 8 ,-1 , 0
  4631.7     .07       0  4672.8     .05       0  4776.2     .07       0
  4845.5      .1       0  5009.5     .05       0  5022.2      .1       0
  5181.8     .07       0  5431.2     .05       0
Bank Sta=5009.5,5022.2
XS Rating Curve= 0 ,0
Exp/Cntr=0.3,0.1

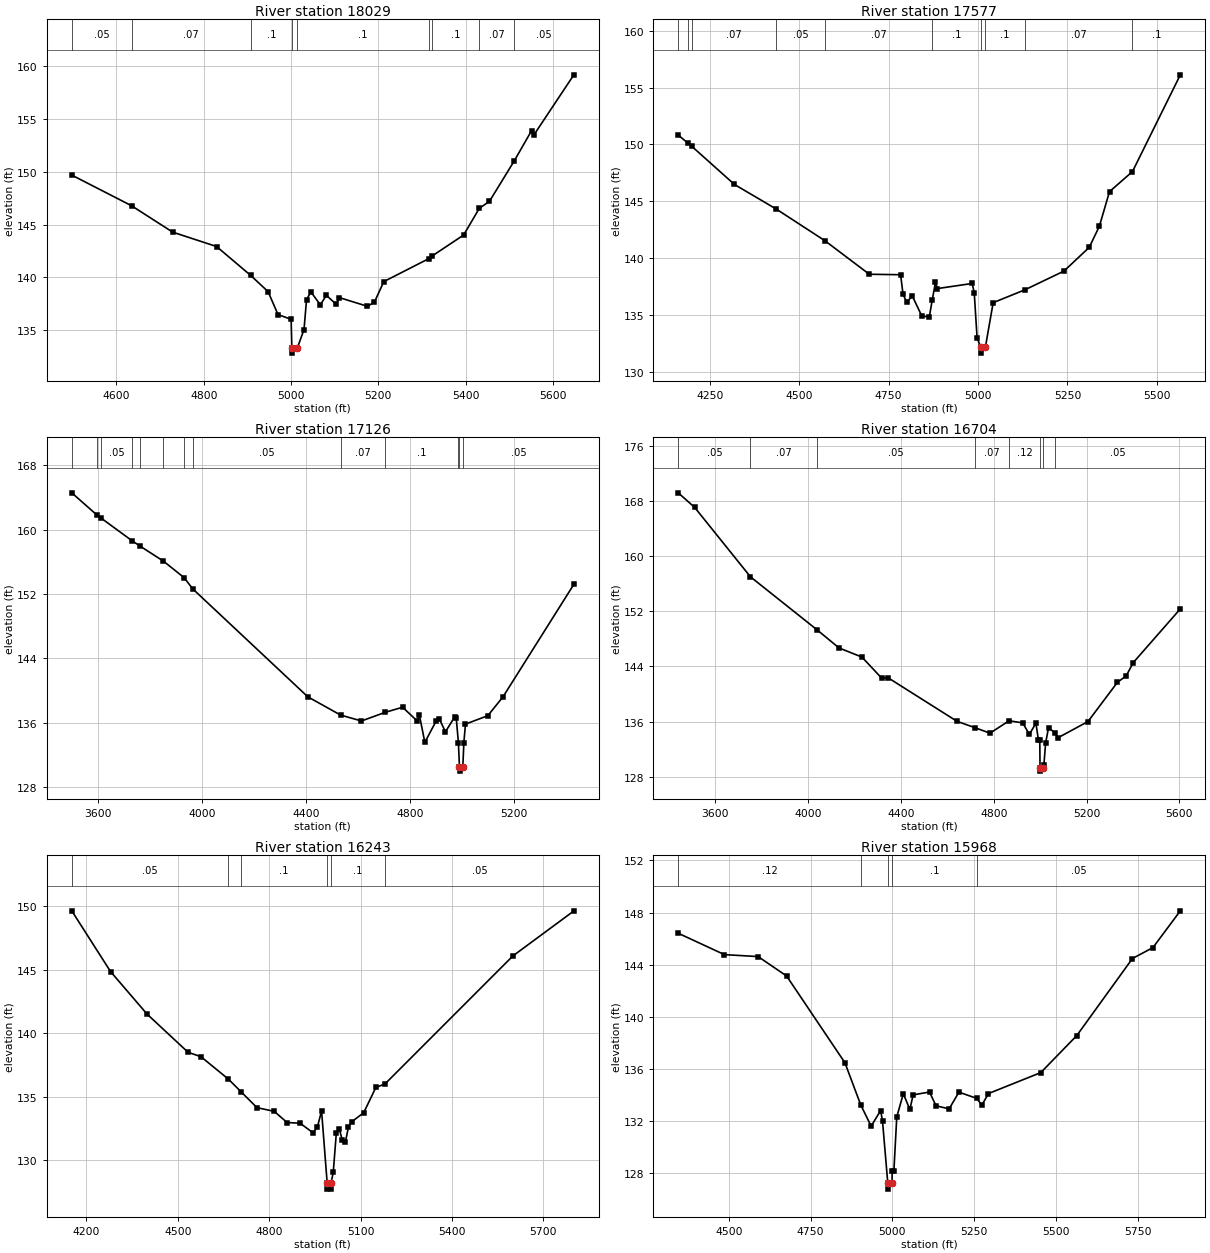
Type RM Length L Ch R = 1 ,18029   ,452,452,452
BEGIN DESCRIPTION:
HOG THIEF CREEK 36.0
END DESCRIPTION:
XS GIS Cut Line= 3
        2535225.     13489775.01        2535175.       13489275.
      2534853.65     13488712.76
#Sta/Elev= 30
  4497.8  149.69  4634.7  146.79    4729  144.29  4829.5  142.93  4907.8  140.19
  4947.5  138.66  4970.2  136.49  5000.3  136.04  5001.9  133.34  5002.4  132.84
  5014.6  133.34  5029.8  135.07  5035.6  137.91  5045.7  138.63  5067.2  137.41
  5080.9  138.31    5104  137.45  5110.4   138.1  5175.2  137.27  5191.1  137.67
  5212.6  139.61    5316  141.79  5322.4  142.01  5395.5  144.02  5431.4  146.55
  5454.5   147.2  5511.3  151.03    5551  153.89  5556.7  153.51  5647.9  159.18
#Mann= 9 ,-1 , 0
  4497.8     .05       0  4634.7     .07       0  4907.8      .1       0
  5001.9     .05       0  5014.6      .1       0    5316     .07       0
  5322.4      .1       0  5431.4     .07       0  5511.3     .05       0
Bank Sta=5001.9,5014.6
XS Rating Curve= 0 ,0
Exp/Cntr=0.3,0.1

Type RM Length L Ch R = 1 ,17577   ,451,451,451
BEGIN DESCRIPTION:
HOG THIEF CREEK 35.0
END DESCRIPTION:
XS GIS Cut Line= 3
      2535274.99     13489825.02        2535525.       13489025.
      2535124.97     13488624.97
#Sta/Elev= 30
  4161.8  150.82  4188.5  150.12  4199.3  149.84    4319  146.47  4435.8  144.31
    4572  141.52  4696.1  138.57  4783.6  138.53  4790.4   136.8  4800.9  136.11
  4816.1  136.67  4842.8   134.9  4863.8  134.81    4872  136.29  4881.1  137.87
  4886.3  137.31  4983.7  137.76  4989.5  136.94  4997.4  132.98  5007.8  132.13
  5008.3  131.63  5020.5  132.13  5042.4  136.07  5131.7  137.21  5240.4  138.85
  5311.1  140.94  5339.4   142.8  5367.7  145.84    5432  147.61  5565.7  156.12
#Mann= 10 ,-1 , 0
  4161.8     .12       0  4188.5     .05       0  4199.3     .07       0
  4435.8     .05       0    4572     .07       0    4872      .1       0
  5007.8     .05       0  5020.5      .1       0  5131.7     .07       0
    5432      .1       0
Bank Sta=5007.8,5020.5
XS Rating Curve= 0 ,0
Exp/Cntr=0.3,0.1

Type RM Length L Ch R = 1 ,17126   ,422,422,422
BEGIN DESCRIPTION:
HOG THIEF CREEK 34.0
END DESCRIPTION:
XS GIS Cut Line= 3
      2535025.02     13490274.97        2535925.       13489075.
      2536175.01     13488724.98
#Sta/Elev= 30
  3499.5  164.58  3595.1  161.85  3610.4  161.48  3731.1  158.62  3760.7  157.98
  3851.8  156.08  3930.9  154.04  3964.8  152.62  4406.8   139.2  4532.7  136.93
    4613  136.19  4704.8  137.27  4771.3   137.9  4827.6  136.19  4835.9  136.91
  4856.8  133.53  4899.5  136.14    4913  136.42  4935.9  134.84  4971.3  136.68
  4977.6  136.51  4985.8   133.5  4989.9  130.45  4990.4  129.95  5002.8  130.45
  5006.8  133.51    5013   135.8    5099  136.85    5158  139.23  5429.6  153.19
#Mann= 13 ,-1 , 0
  3499.5     .05       0  3595.1     .07       0  3610.4     .05       0
  3731.1     .12       0  3760.7     .07       0  3851.8     .12       0
  3930.9     .07       0  3964.8     .05       0  4532.7     .07       0
  4704.8      .1       0  4985.8     .05       0  4989.9     .05       0
  5002.8     .05       0
Bank Sta=4989.9,5002.8
XS Rating Curve= 0 ,0
Exp/Cntr=0.3,0.1

Type RM Length L Ch R = 1 ,16704   ,461,461,461
BEGIN DESCRIPTION:
HOG THIEF CREEK 33.0
END DESCRIPTION:
XS GIS Cut Line= 3
      2535074.99     13490475.01        2536175.       13489375.
        2536275.     13488775.02
#Sta/Elev= 30
  3439.9  169.18  3510.6  167.07  3751.2     157  4038.4  149.31  4132.9  146.69
  4231.9  145.36  4316.7  142.31    4345  142.35    4642  136.04  4720.5  135.11
  4783.4  134.33  4865.8  136.13  4924.8  135.82  4953.1  134.15  4981.4  135.79
    4992  133.41  4998.1  133.41  4999.2  129.33  4999.7  128.83  5012.1  129.33
  5015.8  129.68  5023.4  132.95  5036.1  135.14  5062.4   134.4  5076.6  133.67
  5205.9  136.02  5332.6   141.7  5370.6  142.64  5401.1  144.57  5603.8  152.35
#Mann= 8 ,-1 , 0
  3439.9     .05       0  3751.2     .07       0  4038.4     .05       0
  4720.5     .07       0  4865.8     .12       0  4999.2     .05       0
  5012.1     .12       0  5062.4     .05       0
Bank Sta=4999.2,5012.1
XS Rating Curve= 0 ,0
Exp/Cntr=0.3,0.1

Type RM Length L Ch R = 1 ,16243   ,275,275,275
BEGIN DESCRIPTION:
HOG THIEF CREEK 32.0
END DESCRIPTION:
XS GIS Cut Line= 3
        2535875.       13490275.        2536475.       13489675.
        2536475.     13488875.03
#Sta/Elev= 30
  4151.7  149.61    4279  144.84  4399.2  141.49  4533.5   138.5    4576  138.15
  4665.9  136.39  4707.8  135.39  4759.8  134.15  4816.4  133.86  4858.8  132.98
  4901.2  132.93  4943.7  132.18  4957.8   132.6  4971.9  133.89  4990.2  128.25
  4990.7  127.75  5002.7  127.75  5003.2  128.25  5010.2  129.06  5020.2  132.13
  5030.2  132.46  5040.2  131.58  5050.2  131.46  5060.2  132.63  5070.2  133.03
  5110.2  133.75  5150.2  135.74    5180  136.01  5600.2  146.07  5800.2   149.6
#Mann= 6 ,-1 , 0
  4151.7     .05       0  4665.9     .12       0  4707.8      .1       0
  4990.2     .05       0  5003.2      .1       0    5180     .05       0
Bank Sta=4990.2,5003.2
XS Rating Curve= 0 ,0
Exp/Cntr=0.3,0.1

Type RM Length L Ch R = 1 ,15968   ,232,232,232
BEGIN DESCRIPTION:
Mapping XS 5d6a45d4
END DESCRIPTION:
XS GIS Cut Line= 3
      2536369.92     13490410.48      2536687.65     13489837.52
      2536690.25     13488958.69
#Sta/Elev= 30
  4345.8  146.41  4486.9  144.77  4589.9  144.62  4676.9  143.13  4855.2  136.47
  4903.4  133.24  4935.2  131.61  4964.2  132.81  4969.9  132.01  4985.9  127.28
  4986.4  126.78    4999  127.28  4999.5   128.2  5004.7   128.2  5013.5  132.32
  5033.5   134.1  5053.5  132.89  5063.5  134.01  5113.5  134.23  5133.5  133.17
  5173.5  132.94  5203.5  134.22  5257.9  133.74  5273.5  133.22  5293.5  134.11
  5453.5  135.72  5563.5  138.56  5733.5  144.47  5796.2  145.31  5879.8  148.13
#Mann= 5 ,-1 , 0
  4345.8     .12       0  4903.4      .1       0  4985.9     .05       0
    4999      .1       0  5257.9     .05       0
Bank Sta=4985.9,4999
XS Rating Curve= 0 ,0
Exp/Cntr=0.3,0.1

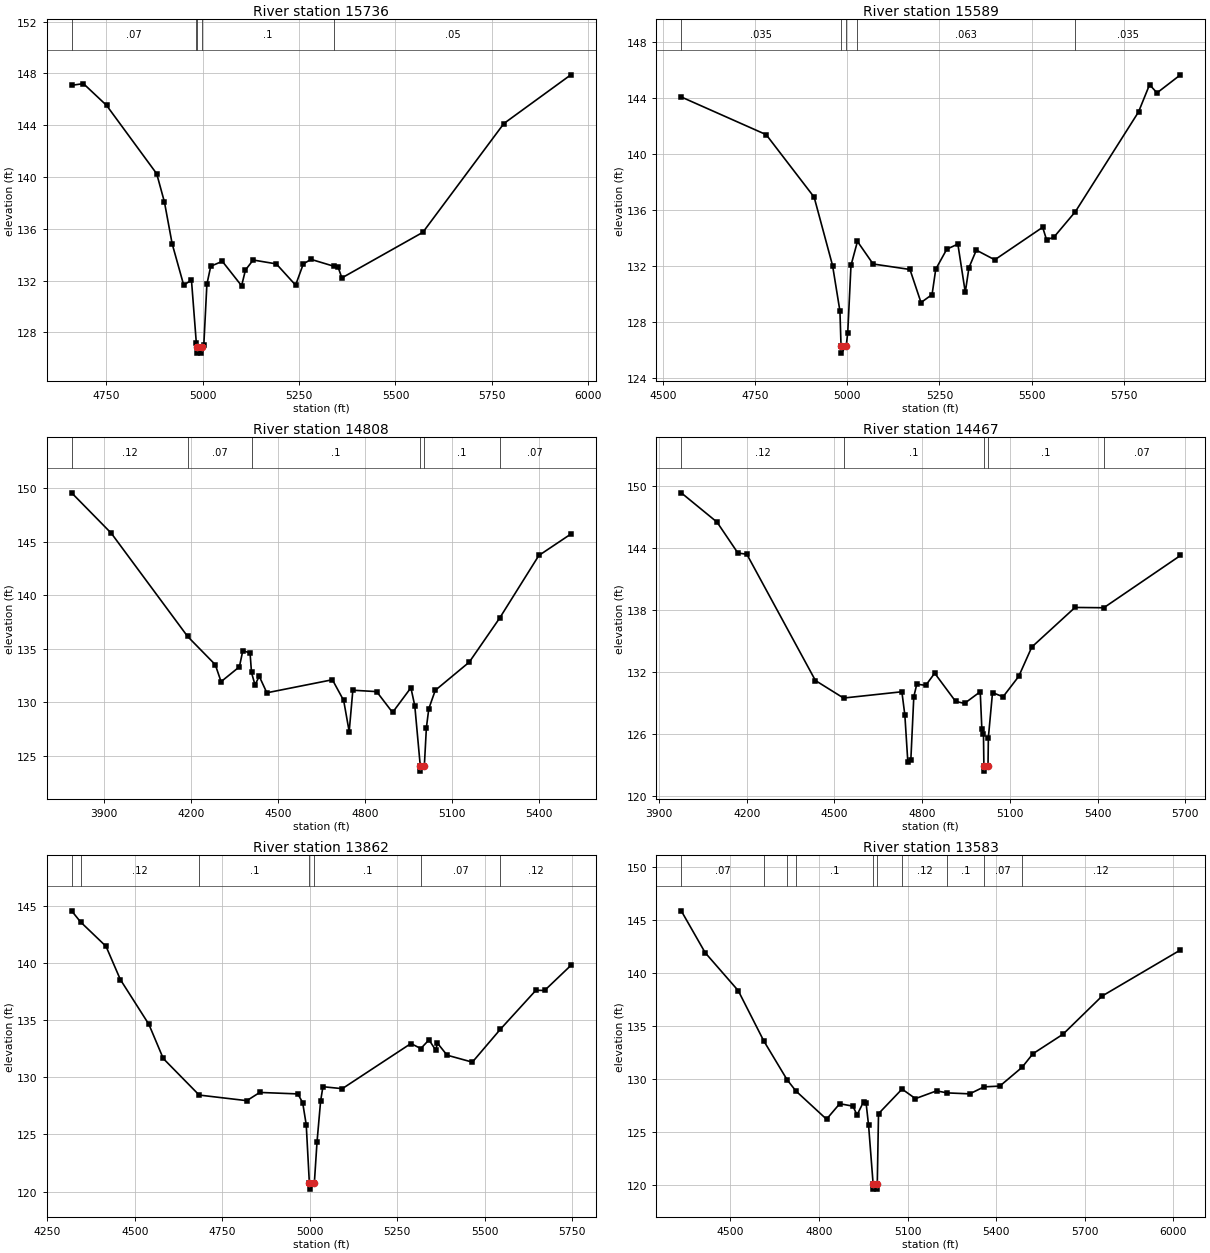
Type RM Length L Ch R = 1 ,15736   ,147,147,147
BEGIN DESCRIPTION:
HOG THIEF CREEK 31.0
END DESCRIPTION:
XS GIS Cut Line= 3
      2536895.99     13490165.61      2536890.39     13489825.95
       2536901.2     13488871.41
#Sta/Elev= 30
  4660.3  147.08  4690.9  147.21  4750.9  145.53  4880.9  140.25  4900.9  138.07
  4920.9  134.85  4950.9  131.65    4971  132.04  4983.6  127.18  4984.4   126.9
  4984.9   126.4    4997   126.4  4997.5   126.9    5003  127.02    5011  131.72
    5021  133.11    5051  133.49    5101   131.6    5111  132.82    5131  133.59
    5191  133.29    5241  131.65    5261  133.29    5281  133.64  5341.2   133.1
    5351  133.05    5361  132.21    5571  135.73    5781  144.13  5954.6  147.89
#Mann= 5 ,-1 , 0
  4660.3     .07       0  4983.6      .1       0  4984.4     .05       0
  4997.5      .1       0  5341.2     .05       0
Bank Sta=4984.4,4997.5
XS Rating Curve= 0 ,0
Exp/Cntr=0.3,0.1

Type RM Length L Ch R = 1 ,15589   ,781,781,781
BEGIN DESCRIPTION:
Mapping XS e953a4cb
END DESCRIPTION:
XS GIS Cut Line= 4
        2537009.     13490225.42      2537022.02     13489777.54
      2537020.86     13489567.05      2537040.25     13488871.28
#Sta/Elev= 30
  4549.4  144.05  4779.9  141.36    4910   136.9    4960  132.02    4980  128.77
    4983  126.27  4983.5  125.77    4997  126.27  5001.2  127.24    5010  132.03
  5027.5  133.74    5070  132.13    5170  131.74    5200  129.38    5230  129.95
    5240  131.76    5270  133.19    5300  133.55  5320.1  130.11  5330.1  131.87
  5350.1  133.12  5400.1  132.43  5530.1  134.75  5540.6  133.87  5560.1  134.03
    5619  135.87  5790.2  142.98  5820.2  144.93  5840.3  144.34    5904  145.63
#Mann= 5 ,-1 , 0
  4549.4    .035       0    4983    .035       0    4997    .035       0
  5027.5    .063       0    5619    .035       0
Bank Sta=4983,4997
XS Rating Curve= 0 ,0
Exp/Cntr=0.3,0.1

Type RM Length L Ch R = 1 ,14808   ,341,341,341
BEGIN DESCRIPTION:
HOG THIEF CREEK 30.0
END DESCRIPTION:
XS GIS Cut Line= 3
        2537725.     13490425.01      2537340.21      13489275.5
      2537111.44     13488819.58
#Sta/Elev= 30
  3787.8  149.58  3924.6   145.8    4188  136.14  4283.4   133.5  4303.4  131.91
  4366.6   133.3  4378.4  134.81  4403.4   134.6  4408.4  132.77  4420.5   131.6
    4435  132.42  4461.3  130.87  4687.5  132.09  4726.4  130.15  4745.4  127.24
    4758  131.11  4840.1  130.98  4895.1  129.03  4958.3  131.34  4971.7  129.66
  4990.6  124.04  4991.1  123.54  5004.7  124.04  5011.8  127.62  5020.1  129.38
  5042.4   131.1  5159.7  133.74  5264.3  137.85  5399.8  143.72  5510.1  145.72
#Mann= 6 ,-1 , 0
  3787.8     .12       0    4188     .07       0  4408.4      .1       0
  4990.6     .05       0  5004.7      .1       0  5264.3     .07       0
Bank Sta=4990.6,5004.7
XS Rating Curve= 0 ,0
Exp/Cntr=0.3,0.1

Type RM Length L Ch R = 1 ,14467   ,605,605,605
BEGIN DESCRIPTION:
HOG THIEF CREEK 29.0
END DESCRIPTION:
XS GIS Cut Line= 4
      2537824.99     13490374.96        2537625.       13489375.
      2537482.78     13489093.51      2537224.97     13488824.97
#Sta/Elev= 30
  3976.3  149.37  4098.6  146.53    4170  143.53  4200.6  143.41  4435.2  131.16
  4531.4  129.46  4730.9  130.07  4741.1   127.8  4751.3  123.24  4761.5  123.43
  4771.7  129.59  4781.9  130.81  4812.5  130.69  4843.1  131.87  4914.5  129.14
  4945.1  128.94  4998.9  130.07  5004.4  126.47    5010  125.93  5011.4  122.87
  5011.9  122.37  5025.5  122.87  5026.7  125.62  5040.9  129.99  5076.9  129.58
  5130.5  131.56  5175.3  134.41  5323.1  138.25  5421.5  138.22  5683.7  143.29
#Mann= 5 ,-1 , 0
  3976.3     .12       0  4531.4      .1       0  5011.4     .05       0
  5025.5      .1       0  5421.5     .07       0
Bank Sta=5011.4,5025.5
XS Rating Curve= 0 ,0
Exp/Cntr=0.3,0.1

Type RM Length L Ch R = 1 ,13862   ,279,279,279
BEGIN DESCRIPTION:
Mapping XS 26c63bda
END DESCRIPTION:
XS GIS Cut Line= 3
      2537889.06     13490191.27      2538027.95      13489518.5
      2537845.67     13488802.39
#Sta/Elev= 30
  4319.7  144.56  4345.1  143.59    4418  141.45  4458.8  138.55  4540.5  134.62
  4581.4  131.64    4684  128.44  4820.1  127.95  4857.1  128.67  4965.8  128.54
  4979.6  127.78  4989.8  125.85  4998.8  120.71  4999.3  120.21  5012.9  120.71
  5020.6  124.33  5030.9  127.92  5037.5  129.17  5092.8     129  5288.9  132.95
    5317  132.51  5340.5  133.27  5359.6  132.37  5364.7  132.98  5392.1  131.93
  5464.3  131.32  5544.1  134.19  5645.9  137.61  5670.7  137.59  5745.6  139.78
#Mann= 7 ,-1 , 0
  4319.7     .07       0  4345.1     .12       0    4684      .1       0
  4998.8     .05       0  5012.9      .1       0    5317     .07       0
  5544.1     .12       0
Bank Sta=4998.8,5012.9
XS Rating Curve= 0 ,0
Exp/Cntr=0.3,0.1

Type RM Length L Ch R = 1 ,13583   ,209,209,209
BEGIN DESCRIPTION:
HOG THIEF CREEK 28.0
END DESCRIPTION:
XS GIS Cut Line= 3
      2537974.98     13490225.03        2538275.       13489625.
      2538074.99     13488624.96
#Sta/Elev= 30
  4333.3  145.88  4414.4  141.93  4526.2  138.36  4612.8  133.62    4692  129.95
  4721.6   128.9  4825.3  126.24    4870   127.7  4914.7  127.47  4928.7  126.64
    4951  127.89  4959.4  127.75  4967.8  125.65  4983.1  120.15  4983.6  119.65
  4996.7  119.65  4997.2  120.15  5001.4  126.76  5081.1  129.08  5126.5  128.18
  5197.9  128.91  5234.2  128.72  5310.1  128.63    5359  129.29  5412.1  129.36
  5487.6  131.13  5524.3  132.41  5626.2  134.25  5758.8  137.85    6024  142.19
#Mann= 10 ,-1 , 0
  4333.3     .07       0  4612.8     .12       0    4692     .07       0
  4721.6      .1       0  4983.1     .05       0  4997.2      .1       0
  5081.1     .12       0  5234.2      .1       0    5359     .07       0
  5487.6     .12       0
Bank Sta=4983.1,4997.2
XS Rating Curve= 0 ,0
Exp/Cntr=0.3,0.1

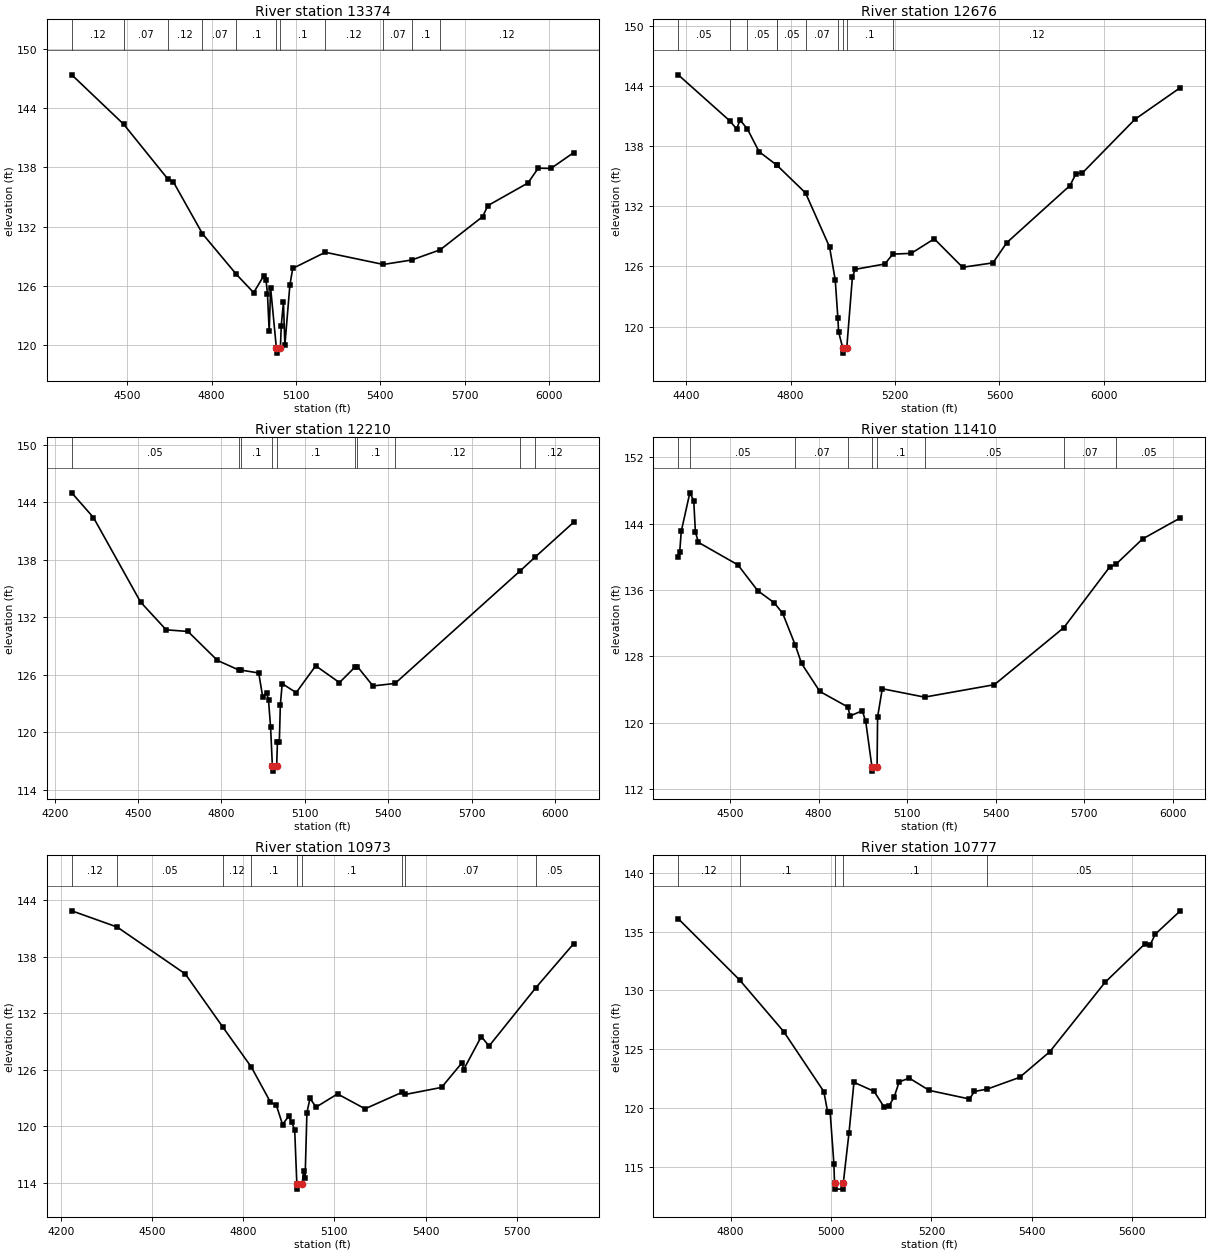
Type RM Length L Ch R = 1 ,13374   ,698,698,698
BEGIN DESCRIPTION:
HOG THIEF CREEK 27.0
END DESCRIPTION:
XS GIS Cut Line= 3
      2537979.71     13490354.62      2538391.58      13489791.7
      2538174.99     13488724.97
#Sta/Elev= 30
  4302.5  147.34  4487.3  142.34  4643.8  136.83  4663.1  136.56  4767.5  131.28
  4887.2  127.21  4949.5  125.33  4985.1  127.02  4993.5   126.6  4998.7  125.21
  5004.8  121.41  5009.9  125.79  5030.4  119.72  5030.9  119.22  5044.6  119.72
  5047.7     122  5055.5  124.37  5060.6  120.03  5078.3  126.08  5088.5  127.78
  5204.4  129.41  5410.6  128.18  5511.8  128.63    5613  129.66  5764.4  133.02
  5782.3  134.12  5925.2  136.41  5961.9  137.91  6006.8  137.88  6088.5  139.49
#Mann= 11 ,-1 , 0
  4302.5     .12       0  4487.3     .07       0  4643.8     .12       0
  4767.5     .07       0  4887.2      .1       0  5030.4     .05       0
  5044.6      .1       0  5204.4     .12       0  5410.6     .07       0
  5511.8      .1       0    5613     .12       0
Bank Sta=5030.4,5044.6
XS Rating Curve= 0 ,0
Exp/Cntr=0.3,0.1

Type RM Length L Ch R = 1 ,12676   ,466,466,466
BEGIN DESCRIPTION:
HOG THIEF CREEK 26.0
END DESCRIPTION:
XS GIS Cut Line= 4
      2538940.63     13490271.71      2538953.04     13489973.77
        2538825.       13489675.      2538325.02     13488475.05
#Sta/Elev= 30
  4369.5  145.13  4568.1  140.51    4593  139.72  4606.4  140.62  4634.8  139.71
  4679.1  137.46  4746.8  136.12  4748.5  136.08  4857.1  133.34  4949.2  127.94
    4971  124.62    4981  120.85  4983.7  119.49  4999.7  117.85  5000.2  117.35
    5015  117.85  5036.6  124.94  5046.9  125.71  5161.2  126.25  5191.1  127.23
    5262  127.31  5350.2  128.76  5458.6  125.92    5575  126.36  5628.1  128.38
  5870.2  134.08  5893.5  135.28  5917.4  135.33  6118.9  140.69  6292.7  143.85
#Mann= 10 ,-1 , 0
  4369.5     .05       0  4568.1     .07       0  4634.8     .05       0
  4746.8     .12       0  4748.5     .05       0  4857.1     .07       0
    4981      .1       0  4999.7     .05       0    5015      .1       0
  5191.1     .12       0
Bank Sta=4999.7,5015
XS Rating Curve= 0 ,0
Exp/Cntr=0.3,0.1

Type RM Length L Ch R = 1 ,12210   ,800,800,800
BEGIN DESCRIPTION:
HOG THIEF CREEK 25.0
END DESCRIPTION:
XS GIS Cut Line= 3
      2539675.02     13489825.02        2539125.       13489325.
      2538424.97     13488524.96
#Sta/Elev= 30
  4261.6  144.97  4339.7  142.39  4509.3  133.58  4601.2  130.69  4679.6  130.52
  4785.7   127.5  4862.7   126.5  4871.2  126.49  4934.3  126.19  4948.5   123.7
  4962.7  124.15  4969.5  123.33  4976.9  120.55  4983.4  116.46  4983.9  115.96
  4998.7  116.46  5001.6  118.96  5008.3  118.96  5012.1   122.9  5018.7  125.08
    5069  124.14  5139.2  126.94  5224.7  125.19    5280  126.79  5289.2  126.86
  5345.2  124.84  5424.7   125.1  5873.9  136.81  5928.3  138.26    6068  141.92
#Mann= 10 ,-1 , 0
  4261.6     .05       0  4862.7     .07       0  4871.2      .1       0
  4983.4     .05       0  4998.7      .1       0    5280     .12       0
  5289.2      .1       0  5424.7     .12       0  5873.9     .07       0
  5928.3     .12       0
Bank Sta=4983.4,4998.7
XS Rating Curve= 0 ,0
Exp/Cntr=0.3,0.1

Type RM Length L Ch R = 1 ,11410   ,437,437,437
BEGIN DESCRIPTION:
Mapping XS de1815e9
END DESCRIPTION:
XS GIS Cut Line= 3
      2539931.96     13489631.56      2539786.12     13489013.47
      2539480.58     13487992.68
#Sta/Elev= 30
  4324.7  139.99  4329.8  140.64  4334.9  143.07    4364  147.72  4377.2  146.79
  4382.8     143  4393.1  141.74  4526.7  139.03    4594  135.91    4650  134.45
  4678.6  133.17  4721.5  129.31  4742.4  127.13  4804.1  123.76  4899.1  121.88
  4906.8  120.79    4948  121.43  4959.8  120.13  4980.8  114.64  4981.3  114.14
  4998.2  114.64  4999.9  120.66  5015.8  124.08    5159  123.07  5395.5  124.57
  5630.7  131.45  5785.6  138.75  5808.7  139.15  5897.6  142.16  6025.3  144.69
#Mann= 9 ,-1 , 0
  4324.7     .12       0    4364     .05       0  4721.5     .07       0
  4899.1      .1       0  4980.8     .05       0  4998.2      .1       0
    5159     .05       0  5630.7     .07       0  5808.7     .05       0
Bank Sta=4980.8,4998.2
XS Rating Curve= 0 ,0
Exp/Cntr=0.3,0.1

Type RM Length L Ch R = 1 ,10973   ,196,196,196
BEGIN DESCRIPTION:
Mapping XS e33d9c32
END DESCRIPTION:
XS GIS Cut Line= 3
      2540181.95     13489638.45      2540181.95     13488888.47
      2540077.79     13487992.68
#Sta/Elev= 30
  4236.1  142.85  4385.4  141.13  4609.5  136.15    4733  130.51  4827.1  126.25
  4889.5  122.55  4909.5  122.18  4929.5  120.16  4949.5  121.03  4959.5  120.43
  4969.5  119.59  4976.6   113.8  4977.1   113.3    4994   113.8  4998.8  115.22
  5003.8   114.5  5009.7  121.42  5019.8  122.93  5039.9  122.01  5110.4  123.41
    5201  121.83  5323.5  123.59    5333  123.35  5452.7   124.1  5520.3  126.73
  5525.3  125.99  5583.5   129.5  5608.9  128.49    5763  134.69  5887.9  139.38
#Mann= 9 ,-1 , 0
  4236.1     .12       0  4385.4     .05       0    4733     .12       0
  4827.1      .1       0  4976.6     .05       0    4994      .1       0
  5323.5     .05       0    5333     .07       0    5763     .05       0
Bank Sta=4976.6,4994
XS Rating Curve= 0 ,0
Exp/Cntr=0.3,0.1

Type RM Length L Ch R = 1 ,10777   ,464,464,464
BEGIN DESCRIPTION:
HOG THIEF CREEK 22.0
END DESCRIPTION:
XS GIS Cut Line= 3
        2540375.     13489175.04        2540375.       13488875.
        2540375.     13488175.04
#Sta/Elev= 30
  4695.7  136.09  4817.9  130.88  4905.7  126.49  4985.7  121.38  4993.2  119.66
  4998.2  119.66  5005.7  115.24    5007  113.58  5007.5  113.08  5023.9  113.08
  5024.4  113.58  5035.7  117.82  5045.7  122.17  5085.7   121.4  5105.7  120.07
  5115.7  120.18  5125.7  120.91  5135.7   122.2  5155.7  122.53  5195.7  121.48
  5275.7  120.75  5285.7  121.39  5310.9  121.59  5375.7  122.59  5435.7  124.77
  5545.7  130.67  5625.7  133.97  5635.7  133.86  5645.7  134.77  5695.7  136.76
#Mann= 5 ,-1 , 0
  4695.7     .12       0  4817.9      .1       0    5007     .05       0
  5024.4      .1       0  5310.9     .05       0
Bank Sta=5007,5024.4
XS Rating Curve= 0 ,0
Exp/Cntr=0.3,0.1