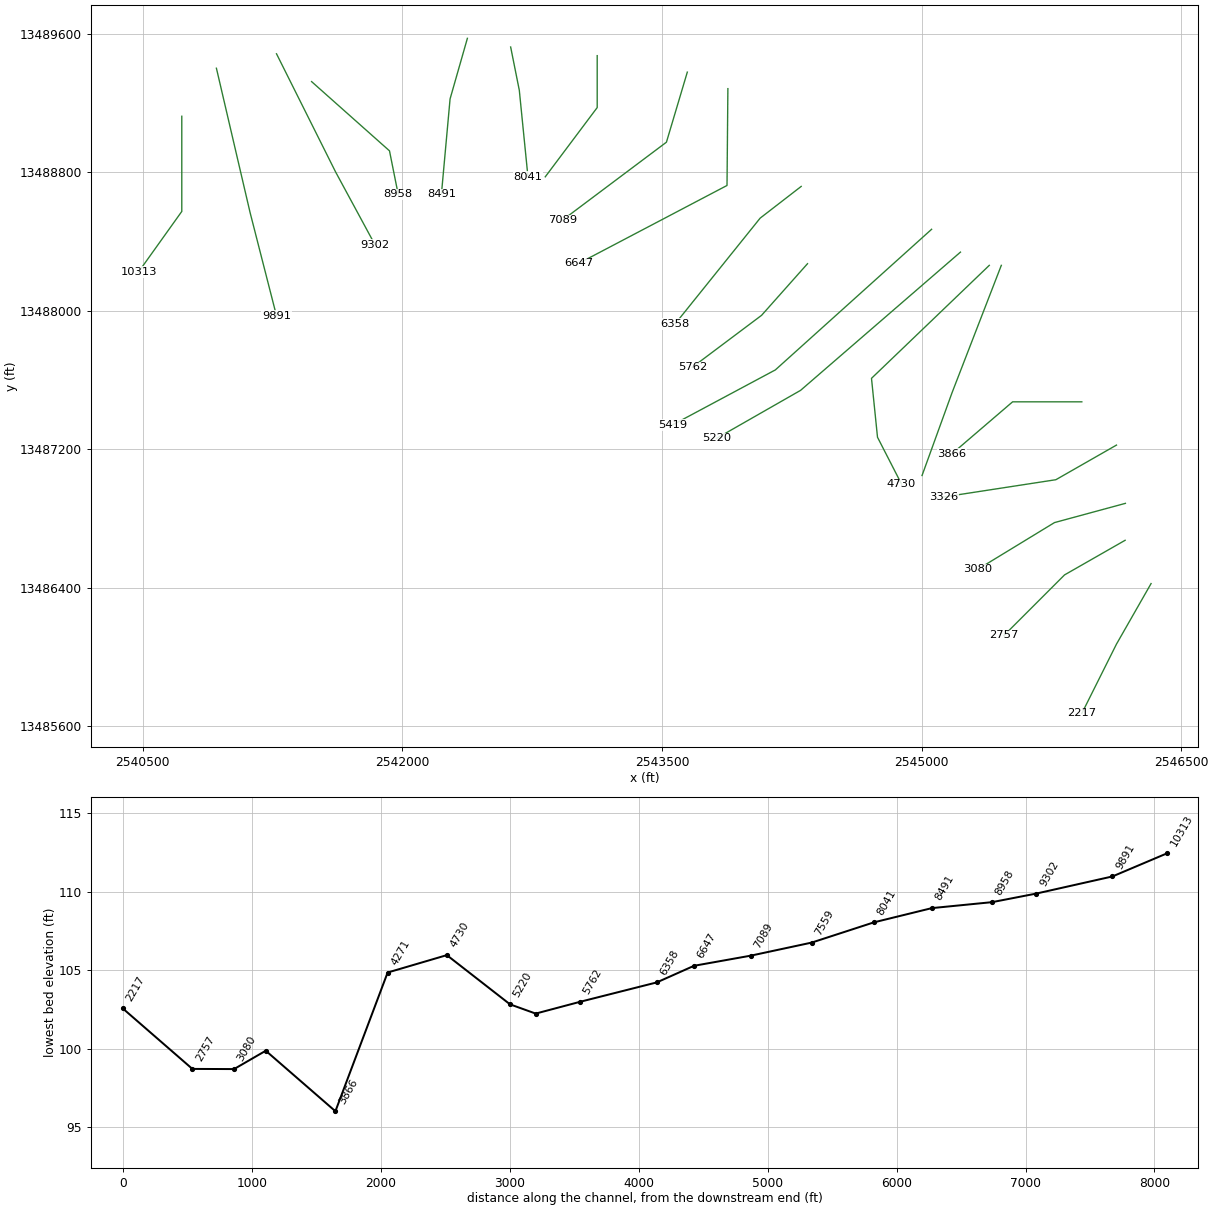
HEC-RAS study HOG THIEF CREEK.prj: HOG THIEF CREEK Base Level Engineering

--- HOG THIEF CREEK.g01 (geometry) --- (continued)

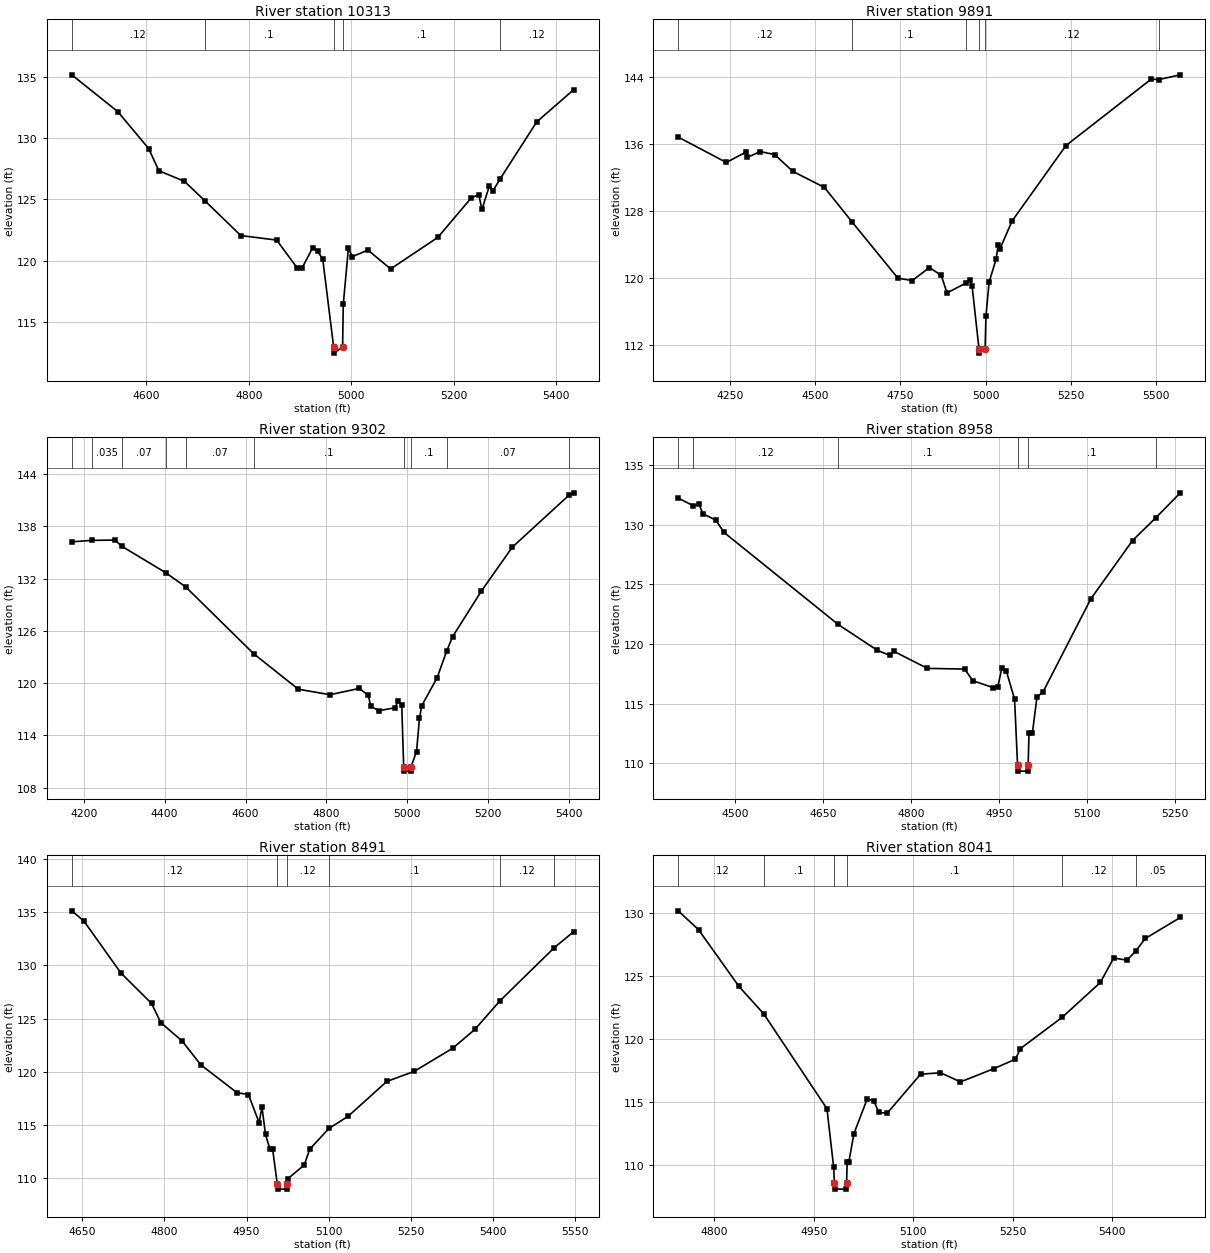
Type RM Length L Ch R = 1 ,10313   ,422,422,422
BEGIN DESCRIPTION:
HOG THIEF CREEK 21.0
END DESCRIPTION:
XS GIS Cut Line= 3
        2540725.     13489124.97        2540725.       13488575.
      2540474.99     13488224.99
#Sta/Elev= 30
  4454.3  135.15  4544.3  132.14  4604.3  129.14  4624.3  127.33  4674.3  126.46
  4713.8  124.89  4784.3  122.04  4854.3  121.67  4894.3   119.4  4904.3  119.43
  4924.3  121.02  4934.3  120.78  4944.3  120.09  4965.5  112.95    4966  112.45
    4983  112.95  4984.3  116.43  4994.3  121.01  5001.8  120.32  5032.5  120.85
  5076.8  119.32  5168.9  121.89  5234.1  125.11  5248.8  125.38    5255  124.17
  5269.7  126.12  5275.9  125.65  5290.2  126.64  5361.9  131.31  5434.4  133.95
#Mann= 5 ,-1 , 0
  4454.3     .12       0  4713.8      .1       0  4965.5     .05       0
    4983      .1       0  5290.2     .12       0
Bank Sta=4965.5,4983
XS Rating Curve= 0 ,0
Exp/Cntr=0.3,0.1

Type RM Length L Ch R = 1 ,9891    ,589,589,589
BEGIN DESCRIPTION:
Mapping XS 601c86a2
END DESCRIPTION:
XS GIS Cut Line= 3
      2540925.01     13489402.36      2541119.45     13488569.02
      2541272.24     13487971.77
#Sta/Elev= 30
  4098.4  136.79  4239.4  133.76  4296.2  134.98  4301.3  134.37  4338.7  135.06
  4381.2   134.7  4434.5  132.69    4527  130.78  4607.6  126.68  4742.6  119.93
  4784.6  119.65    4835  121.21  4869.7  120.27  4886.4  118.17  4943.4  119.38
  4953.6  119.74  4959.9  119.05  4980.3  111.48  4980.8  110.98  4998.2  111.48
  5000.7   115.4  5009.9  119.46  5030.5  122.22  5036.4  123.86  5041.5  123.41
  5077.2  126.76  5235.3  135.78  5485.4  143.72  5506.8  143.66  5570.6  144.23
#Mann= 6 ,-1 , 0
  4098.4     .12       0  4607.6      .1       0  4943.4     .12       0
  4980.3     .05       0  4998.2     .12       0  5506.8     .05       0
Bank Sta=4980.3,4998.2
XS Rating Curve= 0 ,0
Exp/Cntr=0.3,0.1

Type RM Length L Ch R = 1 ,9302    ,344,344,344
BEGIN DESCRIPTION:
Mapping XS f776a1f7
END DESCRIPTION:
XS GIS Cut Line= 3
      2541272.24     13489485.68      2541612.51     13488805.13
      2541840.82     13488383.11
#Sta/Elev= 30
  4170.6  136.23  4219.4   136.4  4277.5  136.43  4293.9  135.73  4402.6  132.69
  4452.2  131.05    4620  123.38  4730.4   119.3  4808.6  118.67  4881.2  119.39
  4903.5  118.59  4909.3  117.37  4928.8  116.83  4969.8  117.17  4977.1     118
    4986  117.45  4990.8  110.39  4991.3  109.89  5008.4  109.89  5008.9  110.39
  5022.6  112.14  5029.8  115.96  5035.5  117.41  5073.5  120.62    5097  123.68
  5111.6  125.33  5182.9  130.58  5259.1  135.61    5400  141.62  5411.3  141.86
#Mann= 10 ,-1 , 0
  4170.6     .12       0  4219.4    .035       0  4293.9     .07       0
  4402.6    .035       0  4452.2     .07       0    4620      .1       0
  4990.8     .05       0  5008.9      .1       0    5097     .07       0
    5400     .12       0
Bank Sta=4990.8,5008.9
XS Rating Curve= 0 ,0
Exp/Cntr=0.3,0.1

Type RM Length L Ch R = 1 ,8958    ,467,467,467
BEGIN DESCRIPTION:
HOG THIEF CREEK 18.0
END DESCRIPTION:
XS GIS Cut Line= 3
        2541475.       13489325.        2541925.       13488925.
      2541974.99     13488675.03
#Sta/Elev= 30
  4402.9  132.22  4428.9  131.57  4438.4  131.69  4445.1   130.9  4466.9  130.38
  4481.1  129.34  4675.9  121.63  4742.8  119.46  4764.1  119.04  4771.3  119.37
  4828.1  117.95  4891.7  117.89  4905.9  116.91    4941  116.33  4948.5  116.43
  4955.2  117.96  4962.7  117.77    4977  115.36  4982.1  109.84  4982.6  109.34
  4999.7  109.34  5000.2  109.84  5001.6  112.56  5007.5  112.56  5015.2  115.55
  5025.4  115.96    5107  123.76  5178.3  128.66  5218.3  130.58  5259.9  132.66
#Mann= 6 ,-1 , 0
  4402.9    .035       0  4428.9     .12       0  4675.9      .1       0
  4982.1     .05       0  5000.2      .1       0  5218.3     .07       0
Bank Sta=4982.1,5000.2
XS Rating Curve= 0 ,0
Exp/Cntr=0.3,0.1

Type RM Length L Ch R = 1 ,8491    ,450,450,450
BEGIN DESCRIPTION:
HOG THIEF CREEK 17.0
END DESCRIPTION:
XS GIS Cut Line= 3
      2542375.01     13489575.03        2542275.       13489225.
        2542225.       13488675.
#Sta/Elev= 30
    4631  135.14  4653.1  134.18  4720.7  129.29  4776.6  126.43  4793.5  124.62
  4832.5  122.89  4866.3  120.66  4932.6  118.03  4953.4  117.86  4972.9  115.21
  4978.1  116.69  4984.6   114.1  4992.4  112.76  4997.5  112.76    5006  109.46
  5006.5  108.96  5023.8  108.96  5024.3  109.46  5025.2  109.93  5055.3  111.23
  5065.3  112.72  5100.4  114.67  5135.6  115.82  5205.9  119.09  5256.1  120.04
  5326.4  122.22  5366.6  123.98  5412.4  126.67  5511.7  131.68  5547.3  133.19
#Mann= 6 ,-1 , 0
    4631     .12       0    5006     .05       0  5024.3     .12       0
  5100.4      .1       0  5412.4     .12       0  5511.7     .07       0
Bank Sta=5006,5024.3
XS Rating Curve= 0 ,0
Exp/Cntr=0.3,0.1

Type RM Length L Ch R = 1 ,8041    ,482,482,482
BEGIN DESCRIPTION:
HOG THIEF CREEK 16.0
END DESCRIPTION:
XS GIS Cut Line= 3
      2542625.01     13489524.96        2542675.       13489275.
        2542725.       13488775.
#Sta/Elev= 30
  4745.5  130.19  4776.1  128.69  4837.2  124.17  4874.5  121.99  4969.8  114.45
    4980  109.79  4981.1  108.55  4981.6  108.05  4998.9  108.05  4999.4  108.55
  5000.4  110.22  5002.9  110.22  5010.5  112.46  5030.6  115.23  5040.6  115.07
  5048.1  114.15  5060.7  114.09    5111  117.19  5141.1  117.31  5171.3  116.58
  5221.5  117.63  5254.2  118.39  5261.7  119.23  5324.5  121.71  5382.3  124.49
  5402.4  126.44  5422.5  126.26  5435.8     127  5450.1  127.99  5502.9  129.66
#Mann= 6 ,-1 , 0
  4745.5     .12       0  4874.5      .1       0  4981.1     .05       0
  4999.4      .1       0  5324.5     .12       0  5435.8     .05       0
Bank Sta=4981.1,4999.4
XS Rating Curve= 0 ,0
Exp/Cntr=0.3,0.1

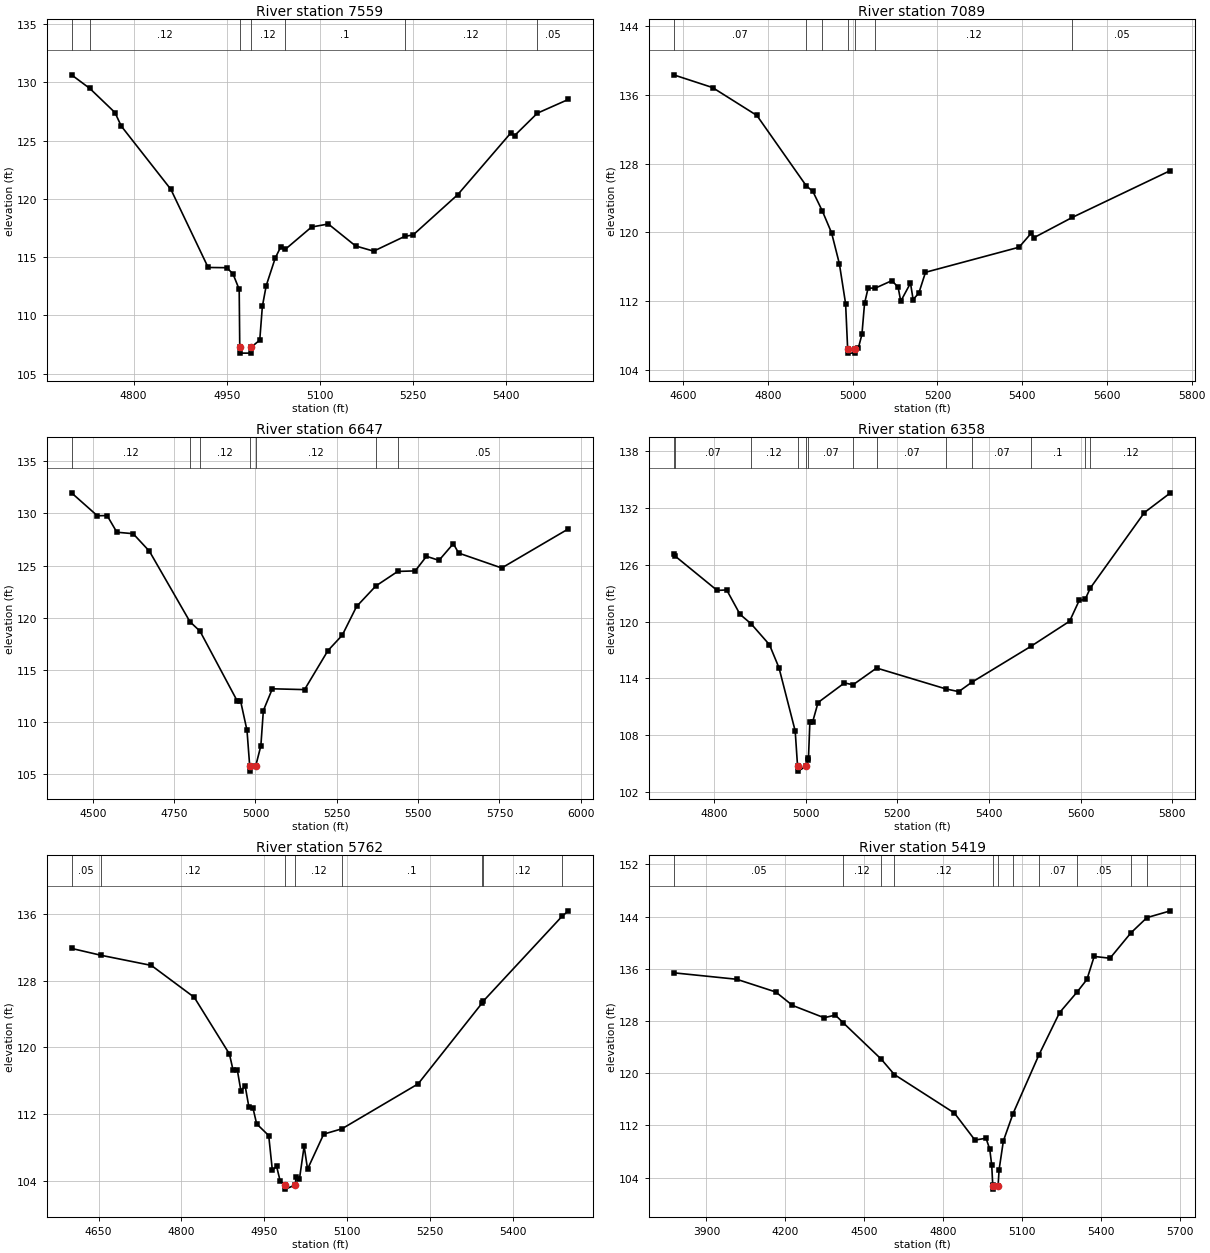
Type RM Length L Ch R = 1 ,7559    ,470,470,470
BEGIN DESCRIPTION:
HOG THIEF CREEK 15.0
END DESCRIPTION:
XS GIS Cut Line= 3
        2543125.       13489475.        2543125.       13489175.
        2542825.       13488775.
#Sta/Elev= 30
    4700  130.64  4729.5  129.47    4770   127.4    4780  126.25    4860  120.81
    4920  114.11    4950  114.09    4960  113.56    4970  112.23  4970.9  107.26
  4971.4  106.76  4988.7  106.76  4989.2  107.26  5003.1  107.88  5007.3  110.77
  5013.5  112.55  5028.1  114.93  5036.5  115.83  5044.3  115.67  5086.5  117.58
  5113.5  117.84  5157.3  115.96  5186.5  115.51  5236.6  116.78    5250   116.9
  5321.9  120.36  5407.3  125.65  5413.5  125.43  5450.1  127.35    5500  128.53
#Mann= 7 ,-1 , 0
    4700     .05       0  4729.5     .12       0  4970.9     .05       0
  4989.2     .12       0  5044.3      .1       0  5236.6     .12       0
  5450.1     .05       0
Bank Sta=4970.9,4989.2
XS Rating Curve= 0 ,0
Exp/Cntr=0.3,0.1

Type RM Length L Ch R = 1 ,7089    ,442,442,442
BEGIN DESCRIPTION:
HOG THIEF CREEK 14.0
END DESCRIPTION:
XS GIS Cut Line= 3
      2543645.66      13489379.9        2543525.       13488975.
        2542925.       13488525.
#Sta/Elev= 30
  4577.5  138.33  4669.3  136.85    4774   133.6  4890.5  125.41  4906.1  124.76
  4928.7  122.45  4950.3  119.93  4968.7  116.33  4983.4  111.67  4988.2  106.43
  4988.7  105.93  5006.1  105.93  5006.6  106.43  5013.5  106.53  5021.9  108.11
  5028.1  111.73  5036.5   113.5  5053.5   113.5  5092.7  114.37  5107.3   113.6
  5113.5  111.97  5136.5  114.08  5142.7  112.17  5156.2  112.92  5171.9  115.34
  5392.7  118.26  5421.9  119.92  5428.1  119.38  5518.3  121.73    5750  127.19
#Mann= 7 ,-1 , 0
  4577.5     .07       0  4890.5     .12       0  4928.7     .07       0
  4988.2     .05       0  5006.6     .07       0  5053.5     .12       0
  5518.3     .05       0
Bank Sta=4988.2,5006.6
XS Rating Curve= 0 ,0
Exp/Cntr=0.3,0.1

Type RM Length L Ch R = 1 ,6647    ,289,289,289
BEGIN DESCRIPTION:
HOG THIEF CREEK 13.0
END DESCRIPTION:
XS GIS Cut Line= 3
      2543880.03     13489284.38        2543875.       13488725.
      2543018.25     13488274.89
#Sta/Elev= 30
  4434.6  131.98    4514  129.78    4544   129.8    4574   128.2    4624  128.06
    4674  126.38  4798.7  119.61  4829.5  118.71    4944  112.01    4954  112.05
    4974  109.19  4982.3  105.78  4982.8  105.28  5000.8  105.78  5016.6  107.71
  5024.3  111.09  5051.9  113.18  5150.9   113.1  5222.7  116.84  5266.8  118.32
  5310.9  121.08  5369.9  123.04  5437.3  124.44    5491  124.49  5525.7  125.89
  5564.1   125.5  5608.2   127.1  5624.6   126.2  5756.9  124.77  5961.8  128.52
#Mann= 7 ,-1 , 0
  4434.6     .12       0  4798.7     .07       0  4829.5     .12       0
  4982.3     .05       0  5000.8     .12       0  5369.9     .07       0
  5437.3     .05       0
Bank Sta=4982.3,5000.8
XS Rating Curve= 0 ,0
Exp/Cntr=0.3,0.1

Type RM Length L Ch R = 1 ,6358    ,596,596,596
BEGIN DESCRIPTION:
HOG THIEF CREEK 12.0
END DESCRIPTION:
XS GIS Cut Line= 3
      2544303.46     13488719.41      2544066.47     13488536.21
      2543575.03     13487925.03
#Sta/Elev= 30
  4712.3  127.09  4716.2  126.89  4807.3  123.29  4828.1  123.34  4857.1  120.77
  4881.3  119.77  4921.4  117.56  4942.2  115.12  4977.5  108.46  4982.7  104.72
  4983.2  104.22  5001.3  104.72  5005.1   105.4  5006.5  105.65  5009.6  109.45
  5015.8  109.45  5027.4  111.46    5085  113.53  5103.6  113.33  5155.1   115.1
  5306.7  112.89  5334.2  112.61  5362.5  113.59    5492   117.4  5576.1  120.04
    5597  122.23  5609.9  122.34  5621.4  123.55  5739.3  131.51  5796.1  133.59
#Mann= 13 ,-1 , 0
  4712.3     .05       0  4716.2     .07       0  4881.3     .12       0
  4982.7     .05       0  5001.3     .12       0  5005.1     .07       0
  5103.6     .12       0  5155.1     .07       0  5306.7     .05       0
  5362.5     .07       0    5492      .1       0  5609.9     .07       0
  5621.4     .12       0
Bank Sta=4982.7,5001.3
XS Rating Curve= 0 ,0
Exp/Cntr=0.3,0.1

Type RM Length L Ch R = 1 ,5762    ,343,343,343
BEGIN DESCRIPTION:
HOG THIEF CREEK 11.0
END DESCRIPTION:
XS GIS Cut Line= 3
      2544340.13     13488273.15        2544075.       13487975.
      2543674.99     13487674.99
#Sta/Elev= 30
    4601  131.87    4654  131.05  4745.4  129.83  4823.1     126  4886.7   119.2
  4893.4  117.24  4900.9  117.32  4907.6  114.74  4915.1   115.4  4921.8  112.89
  4929.3  112.72    4936  110.81  4957.8  109.41  4964.4  105.24    4972  105.73
  4978.7  103.91  4987.3  103.48  4987.8  102.98  5005.9  103.48  5007.3  104.45
  5013.5  104.23  5021.9  108.14  5028.1  105.38  5057.3  109.58  5090.3  110.22
  5228.1  115.61  5344.6  125.37  5345.6  125.51  5488.4  135.71    5500  136.38
#Mann= 8 ,-1 , 0
    4601     .05       0    4654     .12       0  4987.3     .05       0
  5005.9     .12       0  5090.3      .1       0  5344.6     .05       0
  5345.6     .12       0  5488.4     .05       0
Bank Sta=4987.3,5005.9
XS Rating Curve= 0 ,0
Exp/Cntr=0.3,0.1

Type RM Length L Ch R = 1 ,5419    ,199,199,199
BEGIN DESCRIPTION:
Mapping XS 3a5e9e31
END DESCRIPTION:
XS GIS Cut Line= 3
      2545056.95      13488471.8      2544154.18      13487659.3
      2543558.59     13487340.73
#Sta/Elev= 30
  3775.2  135.39  4015.2   134.4  4163.9  132.45  4227.4  130.39  4347.8   128.5
  4390.4  128.91  4420.5  127.72  4564.8  122.16  4614.8   119.8  4843.3  113.89
  4921.4  109.75  4963.6  110.03  4977.8  108.35  4985.3  105.89  4989.2  102.81
  4990.9  102.73  4991.4  102.23  5009.5  102.73  5013.3   105.2  5029.6  109.62
  5066.5  113.82  5164.3  122.76  5243.3  129.28    5310  132.44  5347.4  134.37
    5375   137.9  5435.2  137.62  5514.7  141.51  5575.7  143.85  5665.2  144.89
#Mann= 11 ,-1 , 0
  3775.2     .05       0  4420.5     .12       0  4564.8    .035       0
  4614.8     .12       0  4990.9     .05       0  5009.5     .12       0
  5066.5      .1       0  5164.3     .07       0    5310     .05       0
  5514.7     .07       0  5575.7     .05       0
Bank Sta=4990.9,5009.5
XS Rating Curve= 0 ,0
Exp/Cntr=0.3,0.1

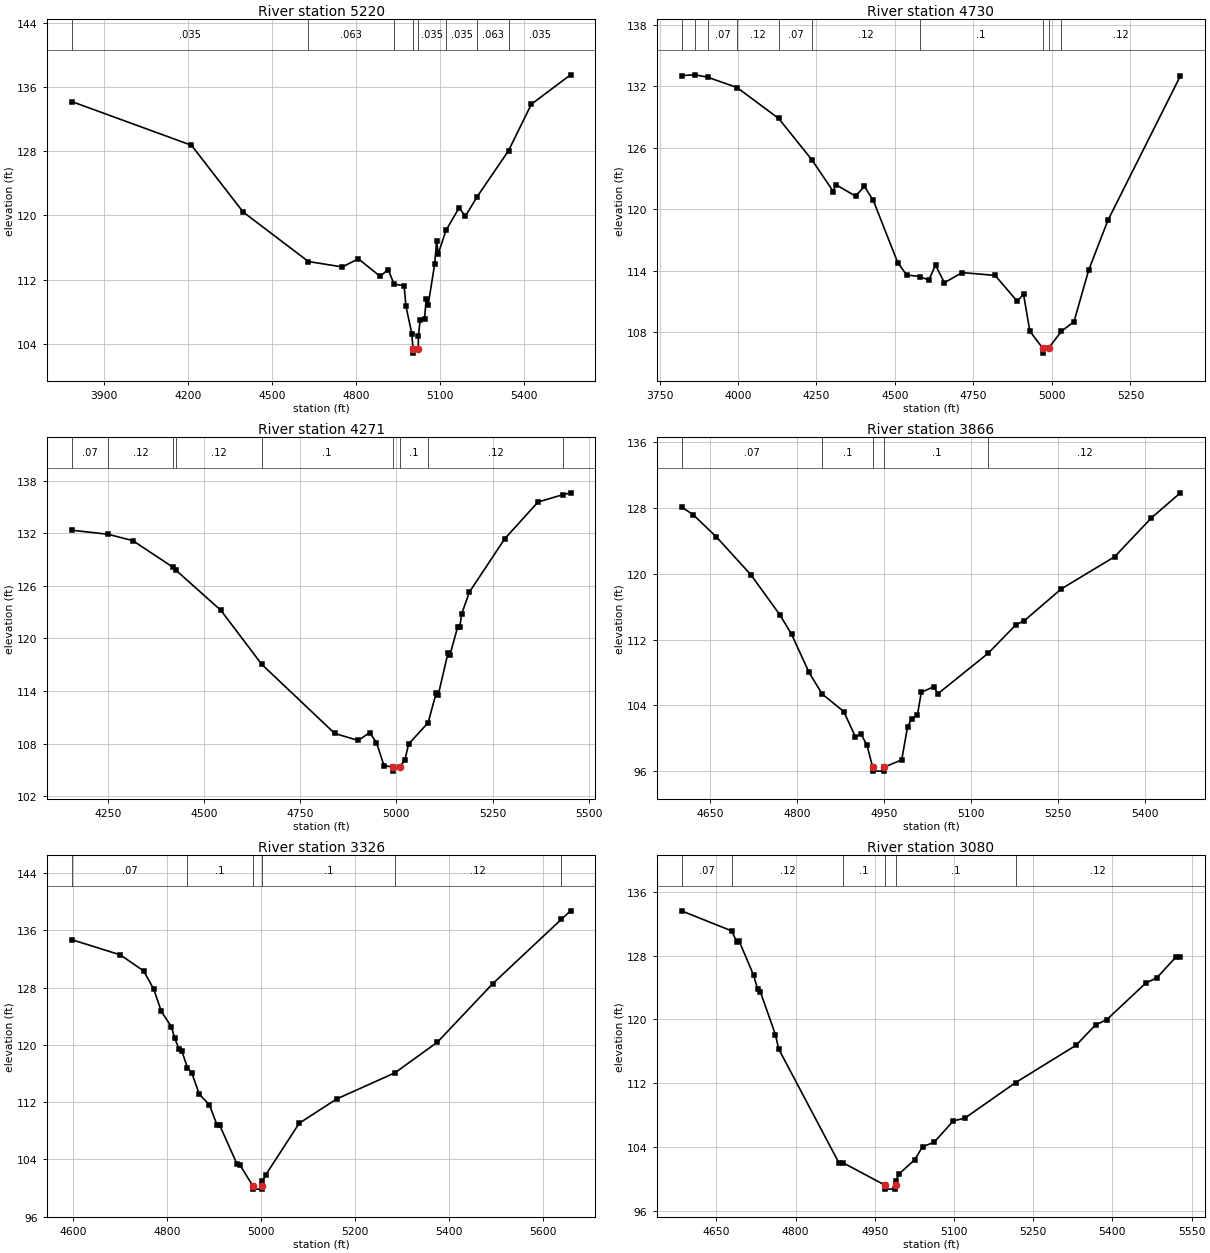
Type RM Length L Ch R = 1 ,5220    ,490,490,490
BEGIN DESCRIPTION:
Mapping XS b641aaf2
END DESCRIPTION:
XS GIS Cut Line= 3
      2545223.63     13488339.86      2544300.01     13487541.25
      2543813.89     13487263.46
#Sta/Elev= 30
  3785.4  134.21  4213.3  128.75  4397.5  120.43  4630.5  114.25  4751.8  113.57
  4808.8  114.59  4886.7   112.4  4915.2  113.25  4936.6  111.42  4972.2  111.24
  4978.9  108.67  4999.8  105.24  5004.1  103.32  5004.6  102.82  5022.7  103.32
  5023.5  104.96  5029.3  106.96  5045.1  107.06  5050.9  109.52  5058.2  108.83
  5081.3  113.94  5088.3  116.75  5094.1  115.22  5121.8  118.14  5168.9  120.97
  5190.5  119.88  5233.4  122.36  5344.9  128.07  5426.6  133.88  5566.3  137.54
#Mann= 8 ,-1 , 0
  3785.4    .035       0  4630.5    .063       0  4936.6    .035       0
  5004.1    .035       0  5022.7    .035       0  5121.8    .035       0
  5233.4    .063       0  5344.9    .035       0
Bank Sta=5004.1,5022.7
XS Rating Curve= 0 ,0
Exp/Cntr=0.3,0.1

Type RM Length L Ch R = 1 ,4730    ,459,459,459
BEGIN DESCRIPTION:
Mapping XS 50c6d791
END DESCRIPTION:
XS GIS Cut Line= 4
      2545390.31     13488263.49      2544709.73     13487610.69
      2544744.45     13487270.41      2544883.22     13486999.81
#Sta/Elev= 30
    3820  133.04  3864.3  133.11  3903.1  132.88    3997  131.87  4129.6  128.85
  4236.5  124.77  4303.6  121.72  4310.8  122.41  4374.3  121.28  4402.7  122.23
    4431  120.85  4508.6   114.8  4536.9  113.59  4578.6  113.43  4607.7  113.09
  4629.1  114.54  4657.4  112.83    4714  113.82    4819  113.54  4889.4  111.02
  4909.5   111.7  4929.6   108.1  4970.1  106.46  4970.6  105.96  4989.7  106.46
  5030.2  108.09  5070.3  109.04    5117  114.06    5178   118.9  5409.2  133.01
#Mann= 10 ,-1 , 0
    3820     .07       0  3864.3    .035       0  3903.1     .07       0
    3997     .12       0  4129.6     .07       0  4236.5     .12       0
  4578.6      .1       0  4970.1     .05       0  4989.7      .1       0
  5030.2     .12       0
Bank Sta=4970.1,4989.7
XS Rating Curve= 0 ,0
Exp/Cntr=0.3,0.1

Type RM Length L Ch R = 1 ,4271    ,405,405,405
BEGIN DESCRIPTION:
Mapping XS 10daa95e
END DESCRIPTION:
XS GIS Cut Line= 3
      2545459.74     13488263.48      2545175.01     13487527.36
      2545001.71     13487049.05
#Sta/Elev= 30
    4155  132.37  4249.2  131.91  4314.2  131.18  4419.4  128.12  4427.2  127.77
  4543.5  123.21  4649.6  117.05  4839.6  109.15  4900.6  108.36  4930.6  109.25
  4948.2  108.09    4968  105.45  4990.2  105.35  4990.7  104.85  5009.8  105.35
  5022.1  106.16  5031.9  107.95  5082.5  110.38  5103.4  113.77  5108.7  113.53
    5134  118.31  5139.3  118.12  5159.3  121.31  5164.6  121.26  5170.1  122.85
    5190  125.31  5281.8  131.39  5368.4  135.59  5432.5  136.42    5453  136.64
#Mann= 9 ,-1 , 0
    4155     .07       0  4249.2     .12       0  4419.4     .07       0
  4427.2     .12       0  4649.6      .1       0  4990.2     .05       0
  5009.8      .1       0  5082.5     .12       0  5432.5      .1       0
Bank Sta=4990.2,5009.8
XS Rating Curve= 0 ,0
Exp/Cntr=0.3,0.1

Type RM Length L Ch R = 1 ,3866    ,540,540,540
BEGIN DESCRIPTION:
HOG THIEF CREEK 7.0
END DESCRIPTION:
XS GIS Cut Line= 3
      2545924.96       13487475.        2545525.       13487475.
      2545175.03     13487175.03
#Sta/Elev= 30
  4600.4  128.14  4620.4  127.21  4660.4  124.51  4720.4  119.87  4770.4  114.99
  4790.4  112.64  4820.4  108.02    4843  105.39  4880.4  103.25  4900.4  100.19
  4910.4   100.5  4920.4   99.15  4930.2    96.5  4930.7      96    4950      96
  4950.5    96.5  4980.4   97.37  4990.4  101.37  4997.9   102.4  5007.5  102.82
  5014.1  105.58    5036  106.29  5042.6   105.4  5129.9  110.36  5177.6  113.82
  5191.9   114.3  5255.5  118.16  5347.7  122.08  5411.4  126.82  5461.3  129.86
#Mann= 5 ,-1 , 0
  4600.4     .07       0    4843      .1       0  4930.2     .05       0
  4950.5      .1       0  5129.9     .12       0
Bank Sta=4930.2,4950.5
XS Rating Curve= 0 ,0
Exp/Cntr=0.3,0.1

Type RM Length L Ch R = 1 ,3326    ,246,246,246
BEGIN DESCRIPTION:
HOG THIEF CREEK 6.0
END DESCRIPTION:
XS GIS Cut Line= 3
      2546124.99     13487224.99        2545775.       13487025.
      2545124.95     13486924.99
#Sta/Elev= 30
    4597  134.69  4700.6  132.56  4750.3  130.31  4771.9  127.74  4787.7  124.67
  4809.3  122.52  4815.8  120.99  4825.2  119.45  4830.9  119.21  4843.4   116.8
  4852.5   116.1  4868.4  113.11    4890  111.63  4905.8  108.87  4911.6  108.82
    4949  103.31  4954.8  103.23    4982  100.36  4982.5   99.86  5001.8   99.86
  5002.3  100.36  5002.6  100.93  5010.2   101.9    5081  109.06  5160.7  112.45
  5284.5   116.1  5374.5  120.36  5492.1  128.52  5637.9   137.5  5657.8  138.71
#Mann= 6 ,-1 , 0
    4597     .07       0  4843.4      .1       0    4982     .05       0
  5002.3      .1       0  5284.5     .12       0  5637.9      .1       0
Bank Sta=4982,5002.3
XS Rating Curve= 0 ,0
Exp/Cntr=0.3,0.1

Type RM Length L Ch R = 1 ,3080    ,323,323,323
BEGIN DESCRIPTION:
Mapping XS cb197fc7
END DESCRIPTION:
XS GIS Cut Line= 3
      2546176.68     13486888.42      2545766.96     13486777.31
       2545322.5     13486506.46
#Sta/Elev= 30
  4583.8  133.64  4679.1  131.11  4688.2  129.75  4693.3  129.79  4720.2  125.58
    4728  123.82  4733.2  123.46  4761.7  118.09  4767.8   116.3  4882.1  101.97
  4889.7     102  4969.1   99.19  4969.6   98.69    4989   98.69  4989.5   99.19
  4989.6   99.76  4996.4  100.63  5025.3  102.37  5040.7  104.03    5062  104.56
  5098.8  107.27  5120.1  107.59  5216.9  112.08  5331.2  116.76    5368  119.31
  5389.3  119.97  5462.9  124.55  5484.2  125.24    5521  127.88  5528.8  127.78
#Mann= 6 ,-1 , 0
  4583.8     .07       0  4679.1     .12       0  4889.7      .1       0
  4969.1    .035       0  4989.5      .1       0  5216.9     .12       0
Bank Sta=4969.1,4989.5
XS Rating Curve= 0 ,0
Exp/Cntr=0.3,0.1

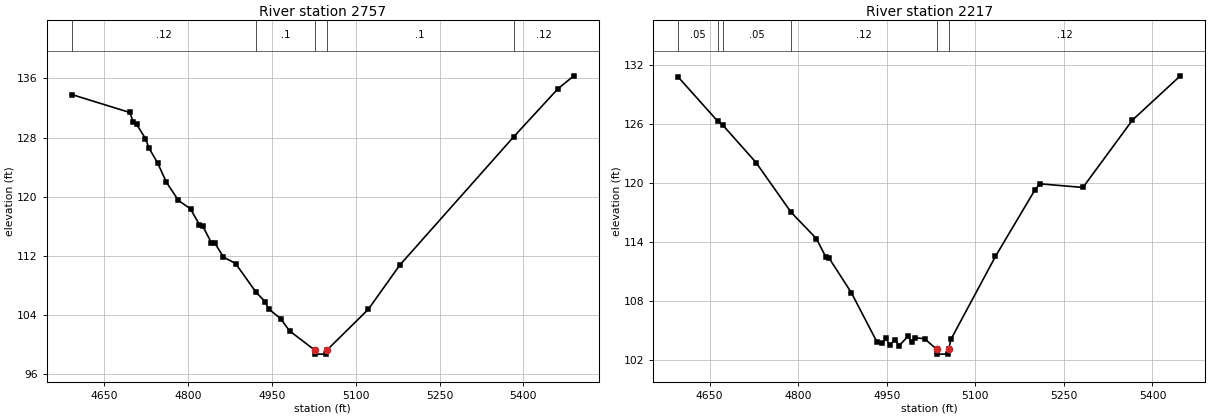
Type RM Length L Ch R = 1 ,2757    ,540,540,540
BEGIN DESCRIPTION:
HOG THIEF CREEK 5.0
END DESCRIPTION:
XS GIS Cut Line= 3
      2546175.04     13486675.02        2545825.       13486475.
      2545475.02     13486125.02
#Sta/Elev= 30
  4592.2  133.83  4695.9   131.4  4702.4   130.1  4708.1  129.81    4724  127.87
  4730.5  126.55  4745.6   124.6  4761.4  121.97    4783   119.5  4804.6  118.35
  4820.4  116.24  4826.2  116.08    4842  113.75  4847.8  113.76  4863.6  111.83
  4885.2  110.96  4922.1  107.05  4937.8  105.82  4944.2  104.83  4965.8   103.5
  4981.7  101.85  5027.6    99.2  5028.1    98.7  5047.5    98.7    5048    99.2
  5122.6  104.76  5179.2  110.77  5382.6   128.1    5462  134.62  5490.3  136.36
#Mann= 5 ,-1 , 0
  4592.2     .12       0  4922.1      .1       0  5027.6    .035       0
    5048      .1       0  5382.6     .12       0
Bank Sta=5027.6,5048
XS Rating Curve= 0 ,0
Exp/Cntr=0.3,0.1

Type RM Length L Ch R = 1 ,2217    ,541,541,541
BEGIN DESCRIPTION:
HOG THIEF CREEK 4.0
END DESCRIPTION:
XS GIS Cut Line= 3
      2546325.01     13486425.01        2546125.       13486075.
      2545925.02     13485675.03
#Sta/Elev= 30
  4596.9  130.75  4664.1  126.24  4672.6  125.85  4728.6  122.06    4788     117
  4830.9  114.31  4846.7  112.46  4852.5  112.32  4889.9  108.83  4933.1  103.84
  4942.4  103.65  4948.9  104.16  4954.7  103.51  4964.8  104.02  4970.5  103.38
  4986.3   104.4  4992.1  103.75  4997.1  104.23    5014  104.13  5034.5  103.06
    5035  102.56  5054.4  102.56  5054.9  103.06  5058.7  104.06  5134.2  112.51
  5201.3   119.3  5209.7  119.89  5282.3  119.52  5366.2  126.38  5447.2  130.88
#Mann= 6 ,-1 , 0
  4596.9     .05       0  4664.1     .07       0  4672.6     .05       0
    4788     .12       0  5034.5    .035       0  5054.9     .12       0
Bank Sta=5034.5,5054.9
XS Rating Curve= 0 ,0
Exp/Cntr=0.3,0.1