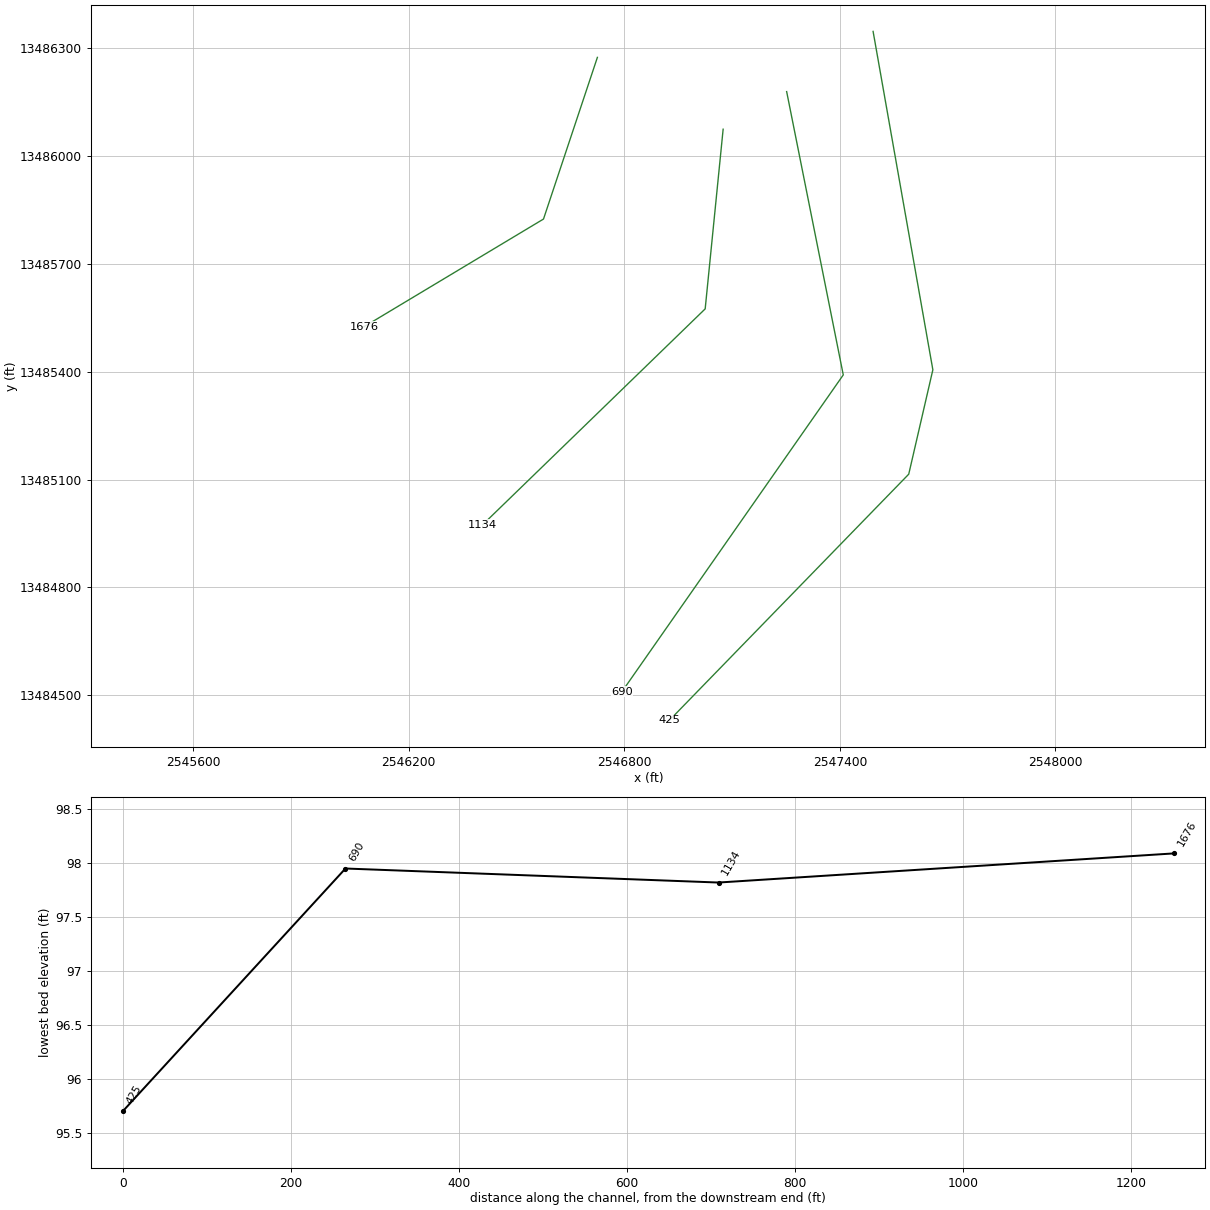
HEC-RAS study HOG THIEF CREEK.prj: HOG THIEF CREEK Base Level Engineering

--- HOG THIEF CREEK.g01 (geometry) --- (continued)

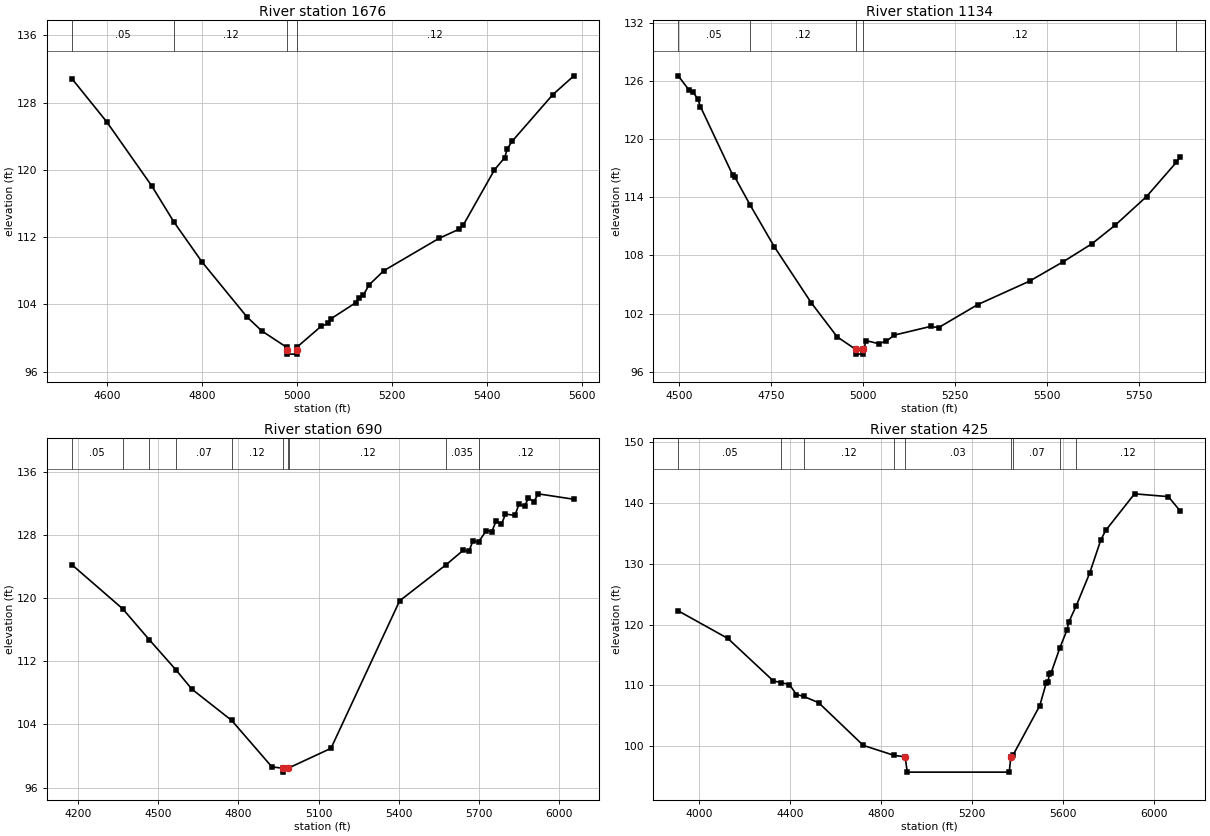
Type RM Length L Ch R = 1 ,1676    ,542,542,542
BEGIN DESCRIPTION:
HOG THIEF CREEK 3.0
END DESCRIPTION:
XS GIS Cut Line= 3
      2546724.99     13486274.96        2546575.       13485825.
        2546075.       13485525.
#Sta/Elev= 30
  4525.7  130.88  4599.4  125.72  4694.3  118.09  4740.6  113.83  4799.7  109.08
  4894.6  102.52  4926.2  100.84  4978.9   98.88  4979.2   98.59  4979.7   98.09
  4999.2   98.09  4999.7   98.59    5000   98.92  5050.5  101.39  5066.1  101.75
  5071.9  102.31  5124.4  104.23  5130.2  104.79  5139.9  105.11  5151.6  106.31
  5182.7  108.01  5299.3  111.87  5342.1  112.97  5349.9  113.41  5415.9  120.01
  5437.3  121.46  5443.2  122.53  5452.9   123.4  5538.4  128.94  5583.1   131.2
#Mann= 4 ,-1 , 0
  4525.7     .05       0  4740.6     .12       0  4979.2    .035       0
  4999.7     .12       0
Bank Sta=4979.2,4999.7
XS Rating Curve= 0 ,0
Exp/Cntr=0.3,0.1

Type RM Length L Ch R = 1 ,1134    ,444,444,444
BEGIN DESCRIPTION:
HOG THIEF CREEK 2.0
END DESCRIPTION:
XS GIS Cut Line= 3
        2547075.     13486075.04        2547025.       13485575.
      2546405.88     13484974.55
#Sta/Elev= 30
  4497.5  126.53  4527.7  125.02  4537.7  124.85  4550.3  124.16  4557.8  123.36
  4645.8  116.28  4650.8  116.12  4692.9  113.21  4758.8  108.89  4859.3  103.11
  4929.7    99.6  4979.7   98.32  4980.2   97.82  4999.8   97.82  5000.3   98.32
  5003.5   98.33  5007.1   99.22  5042.4    98.9  5063.7   99.17  5084.8   99.78
  5183.8  100.68  5205.2  100.55  5311.2  102.92  5452.6  105.35  5544.5  107.36
  5622.4  109.21    5686  111.14  5770.8  114.08  5851.3  117.59  5862.5  118.17
#Mann= 5 ,-1 , 0
  4497.5     .05       0  4692.9     .12       0  4979.7    .035       0
  5000.3     .12       0  5851.3    .035       0
Bank Sta=4979.7,5000.3
XS Rating Curve= 0 ,0
Exp/Cntr=0.3,0.1

Type RM Length L Ch R = 1 ,690     ,265,265,265
BEGIN DESCRIPTION:
Mapping XS 82e64696
END DESCRIPTION:
XS GIS Cut Line= 3
      2547251.73     13486179.76      2547409.33      13485391.2
      2546793.49     13484509.78
#Sta/Elev= 30
  4176.2  124.27  4366.7  118.67  4466.7  114.73  4566.7   110.9  4625.6  108.48
  4774.7  104.51  4925.5   98.61  4965.6   98.45  4966.1   97.95  4986.2   98.45
  4989.6    98.5  5146.5  100.97  5403.5  119.68  5577.1  124.25  5641.6  126.09
  5662.5  125.95  5677.4  127.22  5699.8  127.19    5728  128.59  5748.9  128.45
  5763.7  129.75  5784.6  129.37  5799.5  130.68  5835.2  130.52  5850.1  131.93
    5871  131.68  5885.8   132.7  5906.7  132.25  5921.6  133.25  6055.6  132.56
#Mann= 10 ,-1 , 0
  4176.2     .05       0  4366.7     .07       0  4466.7     .12       0
  4566.7     .07       0  4774.7     .12       0  4965.6    .035       0
  4986.2     .12       0  4989.6     .12       0  5577.1    .035       0
  5699.8     .12       0
Bank Sta=4965.6,4986.2
XS Rating Curve= 0 ,0
Exp/Cntr=0.3,0.1

Type RM Length L Ch R = 1 ,425     ,0,0,0
BEGIN DESCRIPTION:
HOG THIEF CREEK 1.0
END DESCRIPTION:
XS GIS Cut Line= 4
      2547492.34     13486347.25      2547658.67     13485405.47
      2547591.54     13485114.93      2546925.47     13484429.92
#Sta/Elev= 30
  3906.7  122.26  4125.3  117.71  4325.3  110.72  4358.6  110.45  4396.4  110.11
  4426.9  108.48  4458.2  108.18  4524.5  107.14  4721.4   100.1  4856.8   98.46
  4905.6   98.22  4914.8    95.7  5363.8    95.7  5370.8   98.27  5380.7   98.53
  5498.1  106.64  5526.4  110.37  5533.6  110.58  5540.6   111.8  5547.7  112.01
  5586.8   116.2  5618.5  119.16  5625.4  120.38  5658.4  123.07  5717.5  128.45
  5766.9  133.95  5788.2   135.5  5915.3  141.53    6064  141.07  6116.7  138.68
#Mann= 9 ,-1 , 0
  3906.7     .05       0  4358.6     .07       0  4458.2     .12       0
  4856.8    .033       0  4905.6     .03       0  5370.8     .03       0
  5380.7     .07       0  5586.8     .07       0  5658.4     .12       0
Bank Sta=4905.6,5370.8
XS Rating Curve= 0 ,0
Exp/Cntr=0.3,0.1

Chan Stop Cuts=-1
Use User Specified Reach Order=0
Composite Channel Slope=5