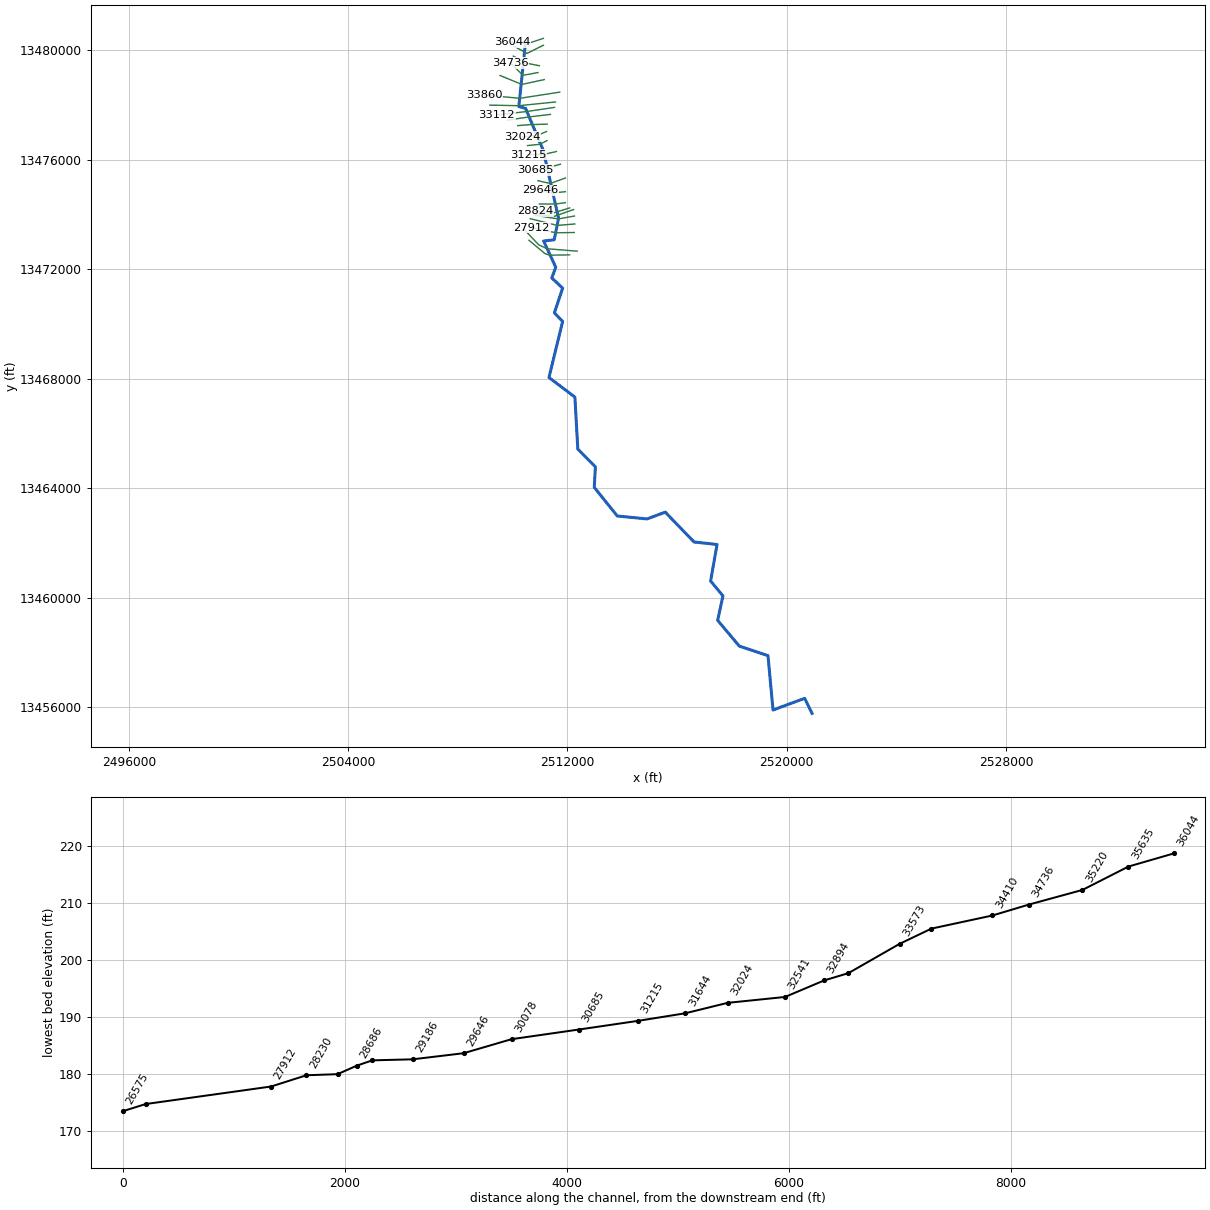
--- KILGORE CREEK.prj (project) ---

Proj Title=KILGORE CREEK Base Level Engineering
Current Plan=p01
Default Exp/Contr=0.3,0.1
English Units
Geom File=g01
Flow File=f01
Plan File=p01
Y Axis Title=Elevation
X Axis Title(PF)=Main Channel Distance
X Axis Title(XS)=Station
BEGIN DESCRIPTION:
KILGORE CREEK
END DESCRIPTION:
DSS Export Rating Curves= 0
DSS Export Rating Curve Sorted= 0
DSS Export Volume Flow Curves= 0
DXF OffsetX= 0
DXF OffsetY= 0
DXF ScaleX= 1
DXF ScaleY= 10

--- KILGORE CREEK.p01 (plan) ---

Plan Title=Multiple Run
Program Version=4.10
Short Identifier=Multiple
Geom File=g01
Flow File=f01
Subcritical Flow
K Sum by GR= 0
Std Step Tol= 0.01
Critical Tol= 0.01
Num of Std Step Trials= 20
Max Error Tol= 0.3
Flow Tol Ratio= 0.001
Split Flow NTrial= 30
Split Flow Tol= 0.02
Split Flow Ratio= 0.02
Log Output Level= 0
Friction Slope Method= 1
Unsteady Friction Slope Method= 2
Unsteady Bridges Friction Slope Method= 1
Parabolic Critical Depth
Global Vel Dist= 1 , 1 , 1
Global Log Level= 0
CheckData=True
Encroach Param=-1 ,0,0, 0
BEGIN DESCRIPTION:
Multiple Run
END DESCRIPTION:
Computation Interval=1HOUR
Output Interval=1HOUR
Run HTab= 0
Run UNet= 0
Run PostProcess= 0
Run WQNet= 0
UNET Theta= 1
UNET Theta Warmup= 1
UNET ZTol= 0.02
UNET ZSATol= 0.05
UNET MxIter= 20
UNET MaxInSteps= 0
UNET DtIC= 0
UNET DtMin= 0
UNET MaxCRTS= 20
UNET WFStab= 2
UNET SFStab= 1
UNET WFX= 1
UNET SFX= 1
UNET DSS MLevel= 4
UNET DZMax Abort= 100
UNET Convert EG Bridges= 0
UNET Use Existing IB Tables=-1
UNET Froude Reduction=False
UNET Froude Limit= 1
UNET Froude Power= 10
UNET Time Slicing=0,0, 5
UNET Junction Losses=0
Instantaneous Interval=1HOUR
Write IC File= 0
Write IC File at Sim End=0
Echo Input=False
Echo Parameters=False
Echo Output=False
Write Detailed= 0
WQ AD Non Conservative
WQ ULTIMATE=-1
WQ Max Comp Step=1HOUR
WQ Output Interval=15MIN
WQ Output Selected Increments= 0
WQ Output face flow=0
WQ Output face velocity=0
WQ Output face area=0
WQ Output face dispersion=0
WQ Output cell volume=0
WQ Output cell surface area=0
WQ Output cell continuity=0
WQ Output cumulative cell continuity=0
WQ Output face conc=0
WQ Output face dconc_dx=0
WQ Output face courant=0
WQ Output face peclet=0
WQ Output face adv mass=0
WQ Output face disp mass=0
WQ Output cell mass=0
WQ Output cell source sink temp=0
WQ Output cell source sink nsm=0
WQ Output MaxMinRange=-1
WQ Daily Max Min Mean=-1
WQ Daily Range=0
WQ Daily Time=0
WQ Create Restart=0
WQ Fixed Restart=0
WQ System Summary=0
WQ Use Fixed Temperature=0
Sorting and Armoring Iterations= 10
XS Update Threshold= 0.02
Hydraulics Update Threshold= 0.02
Energy Slope Method= 1
Volume Change Method= 0
XS Weighting Method= 0
Number of US Weighted Cross Sections= 1
Number of DS Weighted Cross Sections= 1
Upstream XS Weight=0.25
Main XS Weight=0.5
Downstream XS Weight=0.25
Number of DS XS's Weighted with US Boundary= 1
Upstream Boundary Weight= 1
Weight of XSs Associated with US Boundary= 0
Number of US XS's Weighted with DS Boundary= 1
Downstream Boundary Weight= 0.5
Weight of XSs Associated with DS Boundary= 0.5
Sediment Output Level= 4
Mass or Volume Output= 0
Output Increment Type= 1
Profile and TS Output Increment= 10
XS Output Flag= 0
XS Output Increment= 10
Disregard all LS=0
Disregard all Conn=0
Disregard all Breaches=0
Disregard all Pumps=0

--- KILGORE CREEK.f01 (steady flow) ---

Flow Title=Multiple
Number of Profiles=7
Profile Names=10-year,25-year,50-year,1pct_min,100-year,1pct_plu,500-year
River Rch & RM= KILGORE CREEK,Reach-1,36044
     601     955    1269     816    1629    3250    2653
River Rch & RM= KILGORE CREEK,Reach-1,30685
     871    1408    1894    1232    2457    4903    4090
River Rch & RM= KILGORE CREEK,Reach-1,25418
    1638    2730    3745    2477    4943    9862    8525
River Rch & RM= KILGORE CREEK,Reach-1,18125
    1828    3057    4203    2785    5556   11086    9615
River Rch & RM= KILGORE CREEK,Reach-1,11942
    2451    4149    5751    3838    7658   15280   13448
River Rch & RM= KILGORE CREEK,Reach-1,7679
    2529    4270    5910    3937    7855   15672   13739
Boundary for River Rch & Prof#=KILGORE CREEK,Reach-1,1
Up Type=0
Dn Type=3
Dn Slope=0.005
Boundary for River Rch & Prof#=KILGORE CREEK,Reach-1,2
Up Type=0
Dn Type=3
Dn Slope=0.005
Boundary for River Rch & Prof#=KILGORE CREEK,Reach-1,3
Up Type=0
Dn Type=3
Dn Slope=0.005
Boundary for River Rch & Prof#=KILGORE CREEK,Reach-1,4
Up Type=0
Dn Type=3
Dn Slope=0.005
Boundary for River Rch & Prof#=KILGORE CREEK,Reach-1,5
Up Type=0
Dn Type=3
Dn Slope=0.005
Boundary for River Rch & Prof#=KILGORE CREEK,Reach-1,6
Up Type=0
Dn Type=3
Dn Slope=0.005
Boundary for River Rch & Prof#=KILGORE CREEK,Reach-1,7
Up Type=0
Dn Type=3
Dn Slope=0.005

--- KILGORE CREEK.g01 (geometry) ---

Geom Title=Existing Conditions
Program Version=4.10

River Reach=KILGORE CREEK   ,Reach-1
Reach XY= 30
        2510475.       13480325.      2510225.87     13477935.33
      2510471.84      13477867.4      2511121.46     13476323.54
       2511675.3     13473854.66      2511516.98     13473068.56
      2511132.07     13473025.01      2511573.81      13472064.5
      2511428.43     13471676.22      2511825.23     13471300.07
      2511524.47     13470399.88      2511824.03     13470085.29
      2511325.51     13468040.21      2512271.56     13467323.75
      2512378.74     13465426.52      2513019.17      13464777.3
      2512978.74     13464026.56      2513818.81     13462982.81
      2514904.97     13462875.04      2515569.17     13463123.23
      2516618.94     13462033.14      2517458.59      13461941.8
      2517224.51      13460609.8       2517673.8      13460064.5
      2517480.82     13459172.68      2518268.95     13458233.12
      2519317.31     13457881.48      2519501.42     13455897.82
      2520655.12     13456325.09        2520925.       13455775.

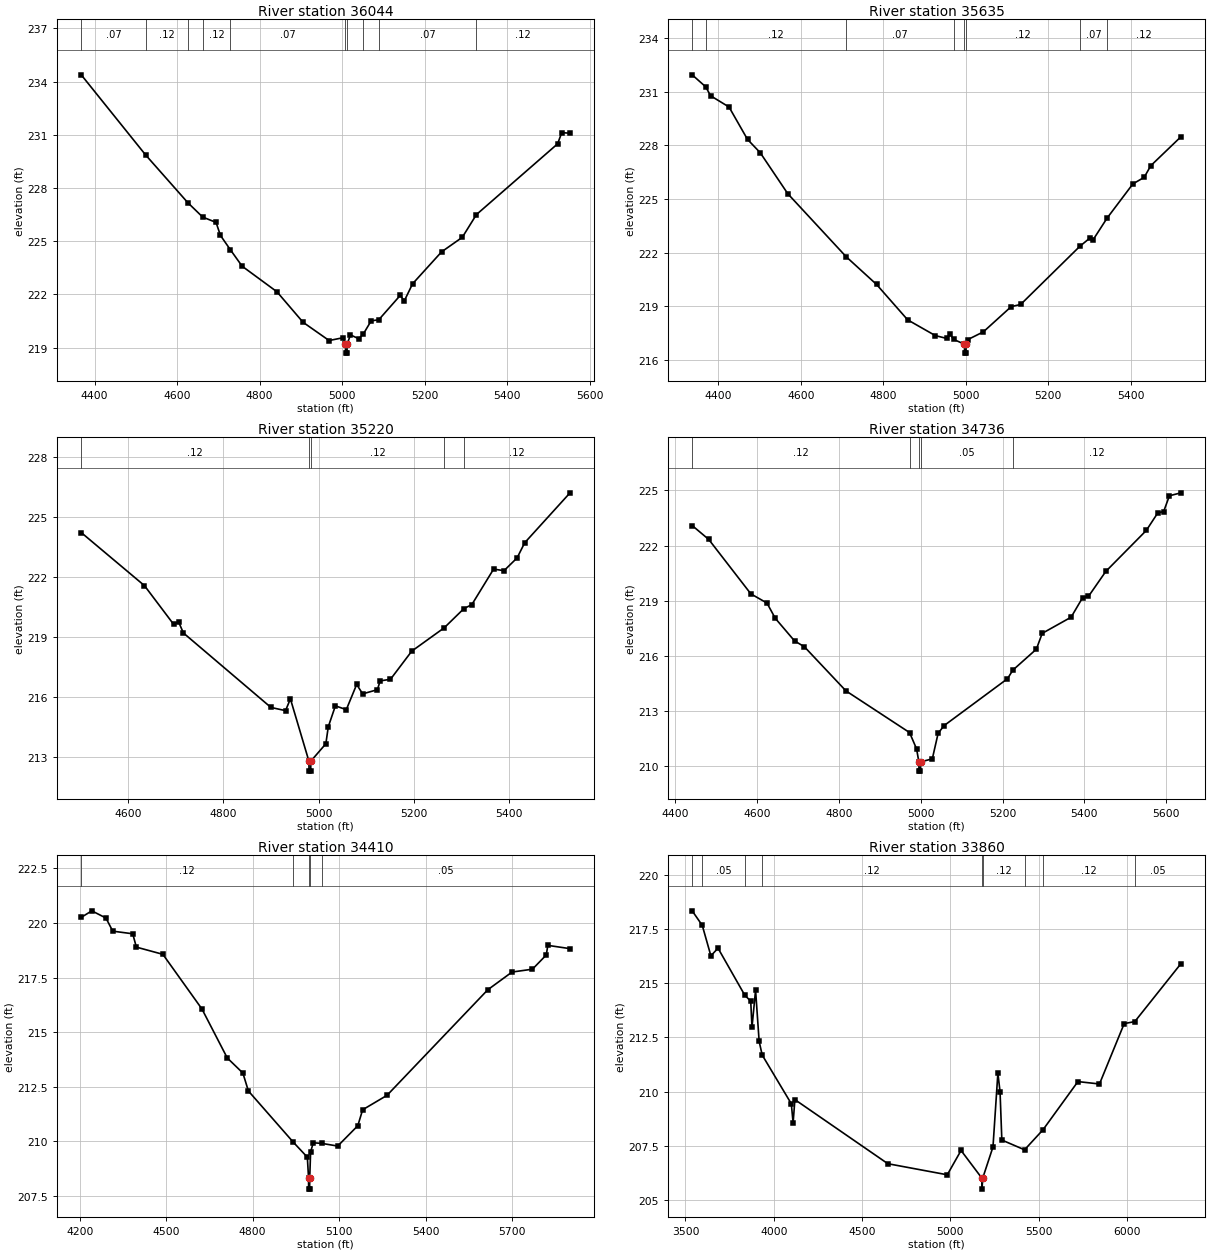
Type RM Length L Ch R = 1 ,36044   ,409,409,409
BEGIN DESCRIPTION:
KILGORE CREEK 72.0
END DESCRIPTION:
XS GIS Cut Line= 3
      2511124.98     13480424.99        2510525.       13480225.
      2509975.01       13480275.
#Sta/Elev= 30
  4367.7  234.38  4523.5  229.87  4626.1  227.17  4662.1  226.36  4694.5  226.06
    4705  225.33  4728.8  224.53  4757.7  223.59    4842  222.15  4905.3  220.43
  4968.5   219.4  5002.6  219.56  5008.2  219.19  5008.4  218.69  5011.9  218.69
  5012.2  219.19  5020.2  219.72  5040.3   219.5  5051.7  219.78  5070.4  220.51
  5088.8  220.57  5140.7  221.94  5150.8  221.64  5170.8   222.6  5241.1   224.4
  5291.3  225.22  5325.5   226.5  5522.3  230.49  5532.3  231.12  5552.4  231.09
#Mann= 10 ,-1 , 0
  4367.7     .07       0  4523.5     .12       0  4626.1     .07       0
  4662.1     .12       0  4728.8     .07       0  5008.2     .05       0
  5012.2     .07       0  5051.7     .12       0  5088.8     .07       0
  5325.5     .12       0
Bank Sta=5008.2,5012.2
XS Rating Curve= 0 ,0
Exp/Cntr=0.3,0.1

Type RM Length L Ch R = 1 ,35635   ,415,415,415
BEGIN DESCRIPTION:
KILGORE CREEK 71.0
END DESCRIPTION:
XS GIS Cut Line= 3
      2511125.01       13480175.        2510525.       13479875.
      2510075.01       13480125.
#Sta/Elev= 30
  4336.5  231.95  4369.3  231.28  4381.2  230.78  4425.9  230.15  4470.7  228.34
  4501.4   227.6  4568.5   225.3    4710  221.78  4783.7  220.23  4859.2  218.25
  4926.3  217.37  4954.2  217.21  4962.6  217.44  4970.4  217.16  4996.9  216.89
  4997.2  216.39  5000.7  216.39  5000.9  216.89  5004.5  217.14  5042.8  217.58
  5110.3  218.99  5133.2  219.11  5276.7  222.36  5302.5  222.85  5308.2   222.7
  5342.9  223.94  5405.4  225.85  5432.9  226.22  5448.9  226.87  5522.1  228.49
#Mann= 8 ,-1 , 0
  4336.5     .07       0  4369.3     .12       0    4710     .07       0
  4970.4     .12       0  4996.9     .05       0  5000.9     .12       0
  5276.7     .07       0  5342.9     .12       0
Bank Sta=4996.9,5000.9
XS Rating Curve= 0 ,0
Exp/Cntr=0.3,0.1

Type RM Length L Ch R = 1 ,35220   ,484,484,484
BEGIN DESCRIPTION:
KILGORE CREEK 70.0
END DESCRIPTION:
XS GIS Cut Line= 3
        2510975.       13479425.        2510475.       13479525.
      2510024.98     13479775.01
#Sta/Elev= 30
  4502.4  224.24    4635  221.58  4696.2  219.64  4706.4  219.77  4716.6  219.21
  4900.1  215.48  4930.7  215.32  4940.9  215.91  4979.7  212.79    4980  212.29
  4983.5  212.29  4983.7  212.79  5015.2  213.66  5020.3  214.51  5035.2  215.56
  5058.1  215.37  5079.8  216.63  5092.4  216.16  5123.3  216.37    5129  216.81
  5150.7  216.89  5195.3   218.3  5263.4  219.47  5304.6  220.43  5321.2  220.63
  5366.9  222.41  5388.7  222.33  5416.1  222.97  5432.1  223.73  5527.1  226.23
#Mann= 5 ,-1 , 0
  4502.4     .12       0  4979.7     .05       0  4983.7     .12       0
  5263.4     .07       0  5304.6     .12       0
Bank Sta=4979.7,4983.7
XS Rating Curve= 0 ,0
Exp/Cntr=0.3,0.1

Type RM Length L Ch R = 1 ,34736   ,326,326,326
BEGIN DESCRIPTION:
KILGORE CREEK 69.0
END DESCRIPTION:
XS GIS Cut Line= 3
      2510924.97     13479174.99        2510375.       13479075.
      2509924.99     13479525.01
#Sta/Elev= 30
    4441  223.09  4481.6  222.33  4584.5  219.37  4623.9  218.87  4644.2  218.04
  4691.3  216.81  4715.4  216.49    4817  214.09  4972.6  211.82  4989.8  210.93
  4995.4  210.22  4995.7  209.72  4999.2  209.72  4999.4  210.22  5028.3  210.39
  5042.4  211.77  5056.6  212.19  5212.1  214.75  5225.3  215.22  5282.8  216.36
    5297  217.22  5367.7   218.1    5396  219.17  5410.1  219.23  5452.5  220.59
  5551.5  222.82  5579.8  223.78    5594  223.85  5608.1  224.71  5636.4  224.87
#Mann= 5 ,-1 , 0
    4441     .12       0  4972.6     .05       0  4995.4     .05       0
  4999.4     .05       0  5225.3     .12       0
Bank Sta=4995.4,4999.4
XS Rating Curve= 0 ,0
Exp/Cntr=0.3,0.1

Type RM Length L Ch R = 1 ,34410   ,550,550,550
BEGIN DESCRIPTION:
Mapping XS d7baf0ca
END DESCRIPTION:
XS GIS Cut Line= 3
      2511151.89     13478918.68      2510339.43      13478741.6
      2509538.68     13479069.18
#Sta/Elev= 30
  4204.9  220.25  4241.6  220.55  4290.7  220.22  4314.3  219.62  4383.7   219.5
  4396.2  218.89  4488.3  218.56  4623.9  216.06  4711.8  213.82    4766  213.13
  4785.1  212.31  4940.8  209.97  4989.8  209.28    4994  208.32  4994.2  207.82
  4997.7  207.82    4998  208.32  5001.1  209.52  5010.3  209.94  5041.1  209.91
  5095.2  209.79  5164.9  210.72  5181.7  211.45  5266.3  212.11  5616.2  216.94
  5700.3  217.75  5771.1  217.88  5819.1  218.53  5824.5  218.97  5901.6  218.82
#Mann= 5 ,-1 , 0
  4204.9     .12       0  4940.8     .07       0    4994     .05       0
    4998     .07       0  5041.1     .05       0
Bank Sta=4994,4998
XS Rating Curve= 0 ,0
Exp/Cntr=0.3,0.1

Type RM Length L Ch R = 1 ,33860   ,287,287,287
BEGIN DESCRIPTION:
Mapping XS 6d7a017c
END DESCRIPTION:
XS GIS Cut Line= 3
      2511719.64     13478460.35      2510271.72     13478236.39
      2508974.81     13478350.98
#Sta/Elev= 30
  3538.2  218.33  3595.3  217.66  3644.1  216.26  3684.6  216.61  3835.7  214.45
  3869.7  214.17  3876.8  212.97  3897.1  214.68  3917.3  212.32  3934.7  211.69
  4099.4  209.45  4109.6  208.57  4119.7  209.64  4645.9  206.69  4982.3  206.18
  5060.3   207.3  5178.7  206.02    5179  205.52  5182.7  206.02    5241  207.46
  5268.8  210.86  5281.1     210  5291.2  207.78  5419.8  207.33    5524  208.25
  5721.9  210.47    5844  210.36  5983.9  213.14  6043.7  213.23  6305.3   215.9
#Mann= 9 ,-1 , 0
  3538.2     .07       0  3595.3     .05       0  3835.7    .035       0
  3934.7     .12       0  5178.7     .05       0  5182.7     .12       0
  5419.8      .1       0    5524     .12       0  6043.7     .05       0
Bank Sta=5178.7,5182.7
XS Rating Curve= 0 ,0
Exp/Cntr=0.3,0.1

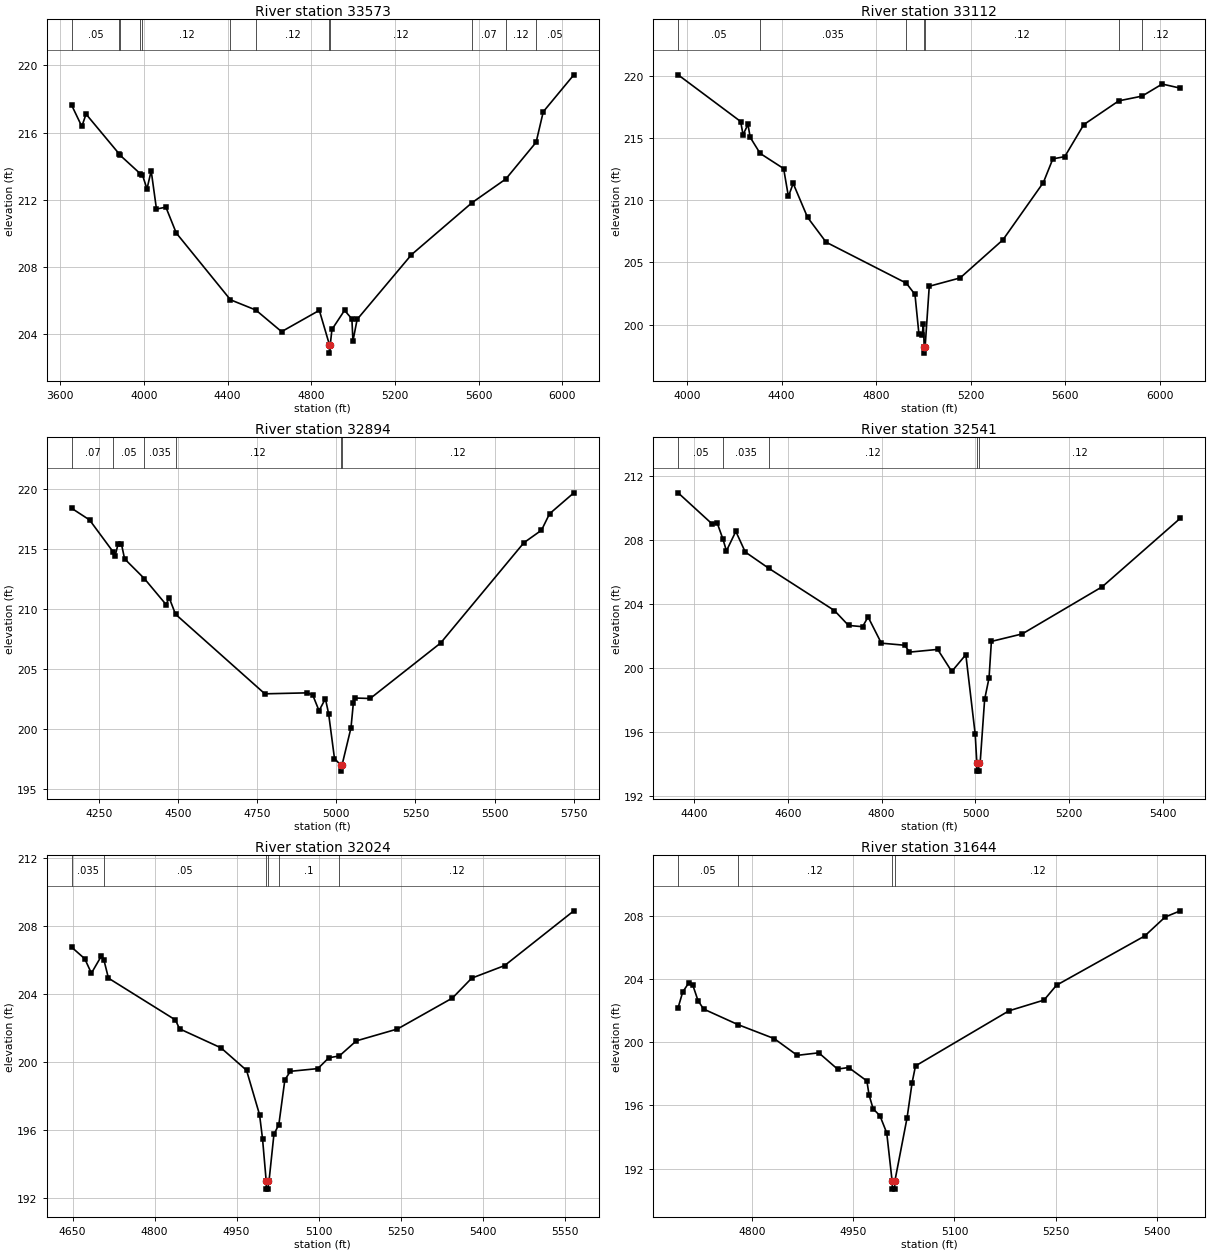
Type RM Length L Ch R = 1 ,33573   ,461,461,461
BEGIN DESCRIPTION:
Mapping XS 9c2842d2
END DESCRIPTION:
XS GIS Cut Line= 3
      2511563.43     13478100.98      2510230.05     13477965.56
      2509168.79     13477986.37
#Sta/Elev= 30
  3653.9  217.63  3702.6  216.36  3722.7   217.1  3881.6  214.72  3885.4  214.65
  3981.6  213.55  3991.9  213.49  4014.2  212.64  4034.3  213.72  4059.5  211.44
  4104.6  211.55  4154.2  210.01  4413.4  206.03  4534.6  205.42  4657.9  204.13
  4838.4   205.4  4886.7  203.35  4886.9  202.85  4890.7  203.35  4898.7  204.26
    4959   205.4  4994.1  204.89  4999.2  203.57  5019.2  204.86  5279.2  208.72
  5568.9  211.82  5730.3  213.23  5875.2  215.42  5909.4  217.24  6055.6  219.44
#Mann= 12 ,-1 , 0
  3653.9     .05       0  3881.6    .035       0  3885.4     .05       0
  3981.6    .035       0  3991.9     .12       0  4413.4     .07       0
  4534.6     .12       0  4886.7     .05       0  4890.7     .12       0
  5568.9     .07       0  5730.3     .12       0  5875.2     .05       0
Bank Sta=4886.7,4890.7
XS Rating Curve= 0 ,0
Exp/Cntr=0.3,0.1

Type RM Length L Ch R = 1 ,33112   ,218,218,218
BEGIN DESCRIPTION:
Mapping XS 57f29c34
END DESCRIPTION:
XS GIS Cut Line= 3
      2511526.88     13477903.05      2510516.51     13477752.02
      2509418.79     13477627.16
#Sta/Elev= 30
  3961.7  220.07  4226.5  216.32  4236.6  215.26  4257.4  216.09  4266.9  215.05
    4309  213.76  4408.5  212.54  4428.7   210.3  4448.9  211.35  4509.6  208.63
  4588.3  206.63  4927.9  203.34  4964.6  202.43  4981.5  199.23  4994.9  199.18
  5000.5  200.04  5003.6  198.22  5003.8  197.72  5007.6  198.22  5025.1  203.09
  5155.9  203.76  5337.1  206.82  5508.2  211.42  5548.4  213.32  5598.8   213.5
  5679.3  216.07  5827.5  217.98  5926.1  218.36  6011.4  219.33  6088.1     219
#Mann= 7 ,-1 , 0
  3961.7     .05       0    4309    .035       0  4927.9     .12       0
  5003.6     .05       0  5007.6     .12       0  5827.5     .07       0
  5926.1     .12       0
Bank Sta=5003.6,5007.6
XS Rating Curve= 0 ,0
Exp/Cntr=0.3,0.1

Type RM Length L Ch R = 1 ,32894   ,353,353,353
BEGIN DESCRIPTION:
Mapping XS 985d002d
END DESCRIPTION:
XS GIS Cut Line= 3
      2511381.07     13477647.85      2510552.97     13477548.89
      2509809.11     13477434.45
#Sta/Elev= 30
    4164  218.38  4220.5  217.41  4294.9  214.75    4301  214.37  4310.3  215.36
  4321.2  215.41  4331.3  214.16  4393.5  212.52  4462.2  210.35  4472.2  210.91
  4492.2  209.54  4774.4   202.9  4907.4  202.98  4925.4  202.82  4945.6  201.49
  4965.7  202.49  4975.8  201.25  4994.4   197.5  5014.2  196.95  5014.4  196.45
  5018.2  196.95  5046.5  200.06    5054  202.13  5059.1  202.55  5107.2  202.51
  5329.8  207.14  5592.9  215.51  5648.4  216.55  5673.8  217.92  5750.6  219.67
#Mann= 6 ,-1 , 0
    4164     .07       0  4294.9     .05       0  4393.5    .035       0
  4492.2     .12       0  5014.2     .05       0  5018.2     .12       0
Bank Sta=5014.2,5018.2
XS Rating Curve= 0 ,0
Exp/Cntr=0.3,0.1

Type RM Length L Ch R = 1 ,32541   ,517,517,517
BEGIN DESCRIPTION:
Mapping XS 128f5a27
END DESCRIPTION:
XS GIS Cut Line= 3
      2511257.98     13477293.09      2510619.07     13477272.25
      2510189.22     13477237.59
#Sta/Elev= 30
  4366.2  210.95  4439.2  208.99  4449.2  209.09  4461.8  208.05  4469.2  207.32
  4489.2  208.54  4509.3  207.25    4560  206.22  4699.4  203.59  4729.4  202.66
  4759.4  202.58  4771.1  203.19  4799.4  201.55  4849.4  201.42  4859.4  200.99
  4919.5  201.16  4949.5  199.78  4979.5  200.83  4999.5  195.85    5003  194.05
  5003.2  193.55  5006.7  193.55    5007  194.05    5010  194.05  5019.6  198.04
    5029  199.38    5034  201.66  5099.8  202.13  5270.4  205.08  5436.7  209.36
#Mann= 5 ,-1 , 0
  4366.2     .05       0  4461.8    .035       0    4560     .12       0
    5003     .05       0    5007     .12       0
Bank Sta=5003,5007
XS Rating Curve= 0 ,0
Exp/Cntr=0.3,0.1

Type RM Length L Ch R = 1 ,32024   ,380,380,380
BEGIN DESCRIPTION:
Mapping XS 7b0ed52f
END DESCRIPTION:
XS GIS Cut Line= 3
      2511237.16     13477022.27       2510903.8     13476883.36
      2510349.11     13476827.89
#Sta/Elev= 30
  4648.4  206.75  4672.4  206.07  4684.5  205.22  4702.9  206.24  4707.4     206
  4715.7  204.93  4838.3  202.47  4845.7  201.95  4921.6  200.83  4968.3  199.51
  4992.1   196.9  4997.6  195.47  5004.2  193.02  5004.4  192.52  5007.9  192.52
  5008.2  193.02  5009.5  193.02  5018.4  195.74  5027.4  196.32  5038.4  198.95
  5048.5  199.45  5098.8  199.61  5118.9  200.25  5137.9  200.35  5169.1  201.24
  5244.4  201.94  5344.9  203.76  5380.2  204.93  5440.4  205.67    5567  208.89
#Mann= 6 ,-1 , 0
  4648.4    .035       0  4707.4     .05       0  5004.2     .05       0
  5008.2     .05       0  5027.4      .1       0  5137.9     .12       0
Bank Sta=5004.2,5008.2
XS Rating Curve= 0 ,0
Exp/Cntr=0.3,0.1

Type RM Length L Ch R = 1 ,31644   ,429,429,429
BEGIN DESCRIPTION:
Mapping XS 3b4e27d7
END DESCRIPTION:
XS GIS Cut Line= 3
      2511251.05     13476688.93      2511001.02     13476556.97
       2510542.7     13476508.37
#Sta/Elev= 30
  4690.8  202.19  4697.6  203.18  4706.6  203.76  4712.3  203.65  4720.3  202.63
  4728.6   202.1  4779.2  201.12  4833.1  200.23  4867.2  199.17  4899.1  199.33
  4926.8   198.3  4943.2   198.4  4970.3  197.55  4973.5  196.67  4979.6  195.78
  4989.6  195.35  4999.7  194.26  5007.7   191.2    5008   190.7  5011.5   190.7
  5011.7   191.2  5029.8  195.21  5037.3  197.45  5042.3   198.5  5180.7  201.99
  5232.6  202.67  5251.1  203.61  5381.8  206.73    5412  207.93  5434.4  208.32
#Mann= 4 ,-1 , 0
  4690.8     .05       0  4779.2     .12       0  5007.7     .05       0
  5011.7     .12       0
Bank Sta=5007.7,5011.7
XS Rating Curve= 0 ,0
Exp/Cntr=0.3,0.1

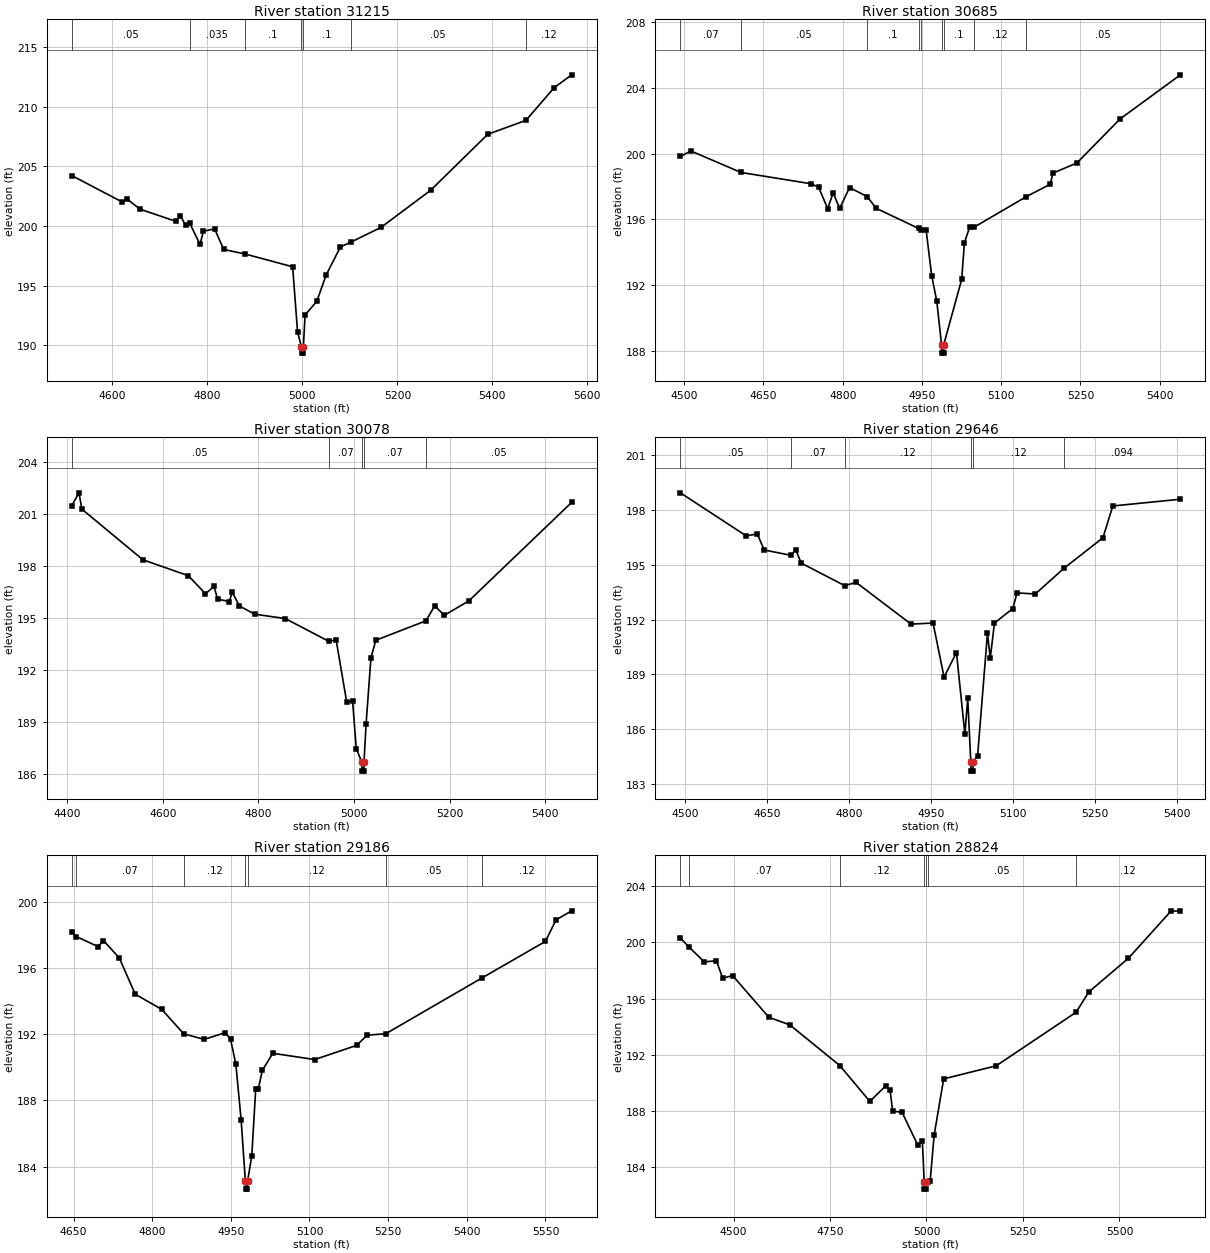
Type RM Length L Ch R = 1 ,31215   ,530,530,530
BEGIN DESCRIPTION:
Mapping XS eddb9235
END DESCRIPTION:
XS GIS Cut Line= 3
       2511598.2     13476293.08      2511119.07     13476181.97
      2510558.25     13476175.05
#Sta/Elev= 30
  4514.2  204.23  4620.8  202.01  4630.4  202.27  4658.3  201.41  4733.1   200.4
  4743.3  200.83  4753.9  200.08  4762.9  200.23  4784.4  198.46  4791.5  199.56
  4815.2  199.77  4834.1  198.04  4878.3  197.67  4979.4  196.59  4989.7  191.16
    4998  189.86  4998.2  189.36  5001.7  189.36    5002  189.86  5005.6  192.56
  5030.1  193.69  5050.1  195.91  5080.1  198.26  5101.4  198.64  5165.6  199.89
  5270.1     203  5390.1  207.68  5470.6  208.85  5530.1  211.59  5566.9  212.66
#Mann= 7 ,-1 , 0
  4514.2     .05       0  4762.9    .035       0  4878.3      .1       0
    4998     .05       0    5002      .1       0  5101.4     .05       0
  5470.6     .12       0
Bank Sta=4998,5002
XS Rating Curve= 0 ,0
Exp/Cntr=0.3,0.1

Type RM Length L Ch R = 1 ,30685   ,607,607,607
BEGIN DESCRIPTION:
Mapping XS f4bae183
END DESCRIPTION:
XS GIS Cut Line= 3
      2511744.11     13475827.82      2511230.18     13475688.92
      2510821.97     13475619.73
#Sta/Elev= 30
  4492.8  199.84  4512.6  200.17  4607.5  198.86  4740.5  198.17  4754.4  197.96
  4771.6  196.66  4781.9  197.61  4794.3  196.67    4813  197.94  4846.3  197.39
  4863.7  196.67  4943.7  195.45  4947.3  195.37    4958  195.33  4968.4  192.57
  4978.1  191.02  4987.1  188.35  4987.4  187.85  4990.9  187.85  4991.1  188.35
  5025.2  192.34  5030.4  194.57  5040.6  195.56  5047.9  195.51  5147.2  197.38
  5192.7  198.14    5198  198.82  5243.4  199.44  5324.6  202.11  5439.2  204.81
#Mann= 9 ,-1 , 0
  4492.8     .07       0  4607.5     .05       0  4846.3      .1       0
  4943.7     .12       0  4947.3      .1       0  4987.1     .05       0
  4991.1      .1       0  5047.9     .12       0  5147.2     .05       0
Bank Sta=4987.1,4991.1
XS Rating Curve= 0 ,0
Exp/Cntr=0.3,0.1

Type RM Length L Ch R = 1 ,30078   ,432,432,432
BEGIN DESCRIPTION:
KILGORE CREEK 59.0
END DESCRIPTION:
XS GIS Cut Line= 3
        2511925.       13475325.        2511375.       13475125.
      2510925.01       13475225.
#Sta/Elev= 30
  4409.4  201.46  4424.7  202.21  4430.7  201.27  4558.4  198.35  4653.5  197.43
  4689.4  196.39  4707.3  196.81  4714.7  196.08  4739.3  195.94  4745.2  196.49
  4760.5  195.68  4792.5  195.21  4856.3  194.96  4947.1  193.65  4962.7  193.73
  4984.7  190.17  4997.2  190.18  5004.9  187.45  5016.9  186.66  5017.2  186.16
  5020.8  186.16    5021  186.66  5025.4  188.88  5035.6  192.71  5045.9  193.71
  5150.8  194.83  5168.8  195.69  5189.3  195.15  5240.5  195.98  5455.6  201.66
#Mann= 5 ,-1 , 0
  4409.4     .05       0  4947.1     .07       0  5016.9     .05       0
    5021     .07       0  5150.8     .05       0
Bank Sta=5016.9,5021
XS Rating Curve= 0 ,0
Exp/Cntr=0.3,0.1

Type RM Length L Ch R = 1 ,29646   ,460,460,460
BEGIN DESCRIPTION:
KILGORE CREEK 58.0
END DESCRIPTION:
XS GIS Cut Line= 3
        2511925.       13474825.        2511425.       13474775.
        2511025.       13474875.
#Sta/Elev= 30
  4491.9  198.94  4612.5  196.58  4632.6  196.69  4645.2  195.81  4693.9  195.52
  4702.9  195.82    4713  195.09  4792.4  193.86  4813.5  194.03    4914  191.75
  4954.2  191.81  4974.3  188.85    4997  190.19  5012.4  185.73  5017.6  187.69
  5023.2   184.2  5023.5   183.7  5027.1   183.7  5027.4   184.2  5035.6  184.52
  5053.7  191.24  5058.8  189.89  5066.5  191.81    5100   192.6  5107.8  193.46
  5141.3   193.4  5193.3   194.8    5265  196.48    5283  198.22  5406.7  198.59
#Mann= 6 ,-1 , 0
  4491.9     .05       0  4693.9     .07       0  4792.4     .12       0
  5023.2     .05       0  5027.4     .12       0  5193.3    .094       0
Bank Sta=5023.2,5027.4
XS Rating Curve= 0 ,0
Exp/Cntr=0.3,0.1

Type RM Length L Ch R = 1 ,29186   ,362,362,362
BEGIN DESCRIPTION:
KILGORE CREEK 57.0
END DESCRIPTION:
XS GIS Cut Line= 3
      2511924.98       13474425.        2511575.       13474375.
      2510975.03       13474375.
#Sta/Elev= 30
  4646.5  198.23  4655.5  197.93    4697  197.32  4707.1  197.69  4737.4  196.63
  4767.7  194.44  4818.2  193.52  4860.2  192.04    4899   191.7  4939.4  192.11
  4949.5   191.7  4959.6   190.2  4969.7   186.8  4977.7  183.13    4978  182.63
  4981.7  182.63    4982  183.13  4989.9  184.63  4997.5  188.71  5002.5  188.71
    5010  189.82    5030  190.86    5110  190.48    5190  191.34    5210  191.96
  5245.2  192.04  5428.7  195.42    5550  197.64    5570  198.94    5600  199.49
#Mann= 7 ,-1 , 0
  4646.5     .05       0  4655.5     .07       0  4860.2     .12       0
  4977.7     .05       0    4982     .12       0  5245.2     .05       0
  5428.7     .12       0
Bank Sta=4977.7,4982
XS Rating Curve= 0 ,0
Exp/Cntr=0.3,0.1

Type RM Length L Ch R = 1 ,28824   ,138,138,138
BEGIN DESCRIPTION:
Mapping XS 8ecb7ea6
END DESCRIPTION:
XS GIS Cut Line= 3
      2512084.11     13474232.64      2511476.49     13474045.15
      2510820.24     13474114.59
#Sta/Elev= 30
  4362.2   200.3  4384.1  199.68  4424.1  198.61  4455.5  198.69    4472  197.44
  4497.3  197.64  4591.5  194.67  4645.8  194.13  4775.2  191.24  4853.1  188.69
    4895  189.81  4905.5  189.53  4912.2  188.01  4936.9   187.9  4977.6  185.57
  4989.2  185.89  4994.1  182.95  4994.4  182.45  4998.2  182.45  4998.4  182.95
  5004.7  182.99  5009.6  183.04  5019.7  186.27  5044.5  190.29  5180.6  191.22
  5387.8  195.03  5420.6  196.47  5523.4  198.87  5633.1  202.21    5658  202.24
#Mann= 7 ,-1 , 0
  4362.2     .12       0  4384.1     .07       0  4775.2     .12       0
  4994.1     .05       0  4998.4     .12       0  5004.7     .05       0
  5387.8     .12       0
Bank Sta=4994.1,4998.4
XS Rating Curve= 0 ,0
Exp/Cntr=0.3,0.1

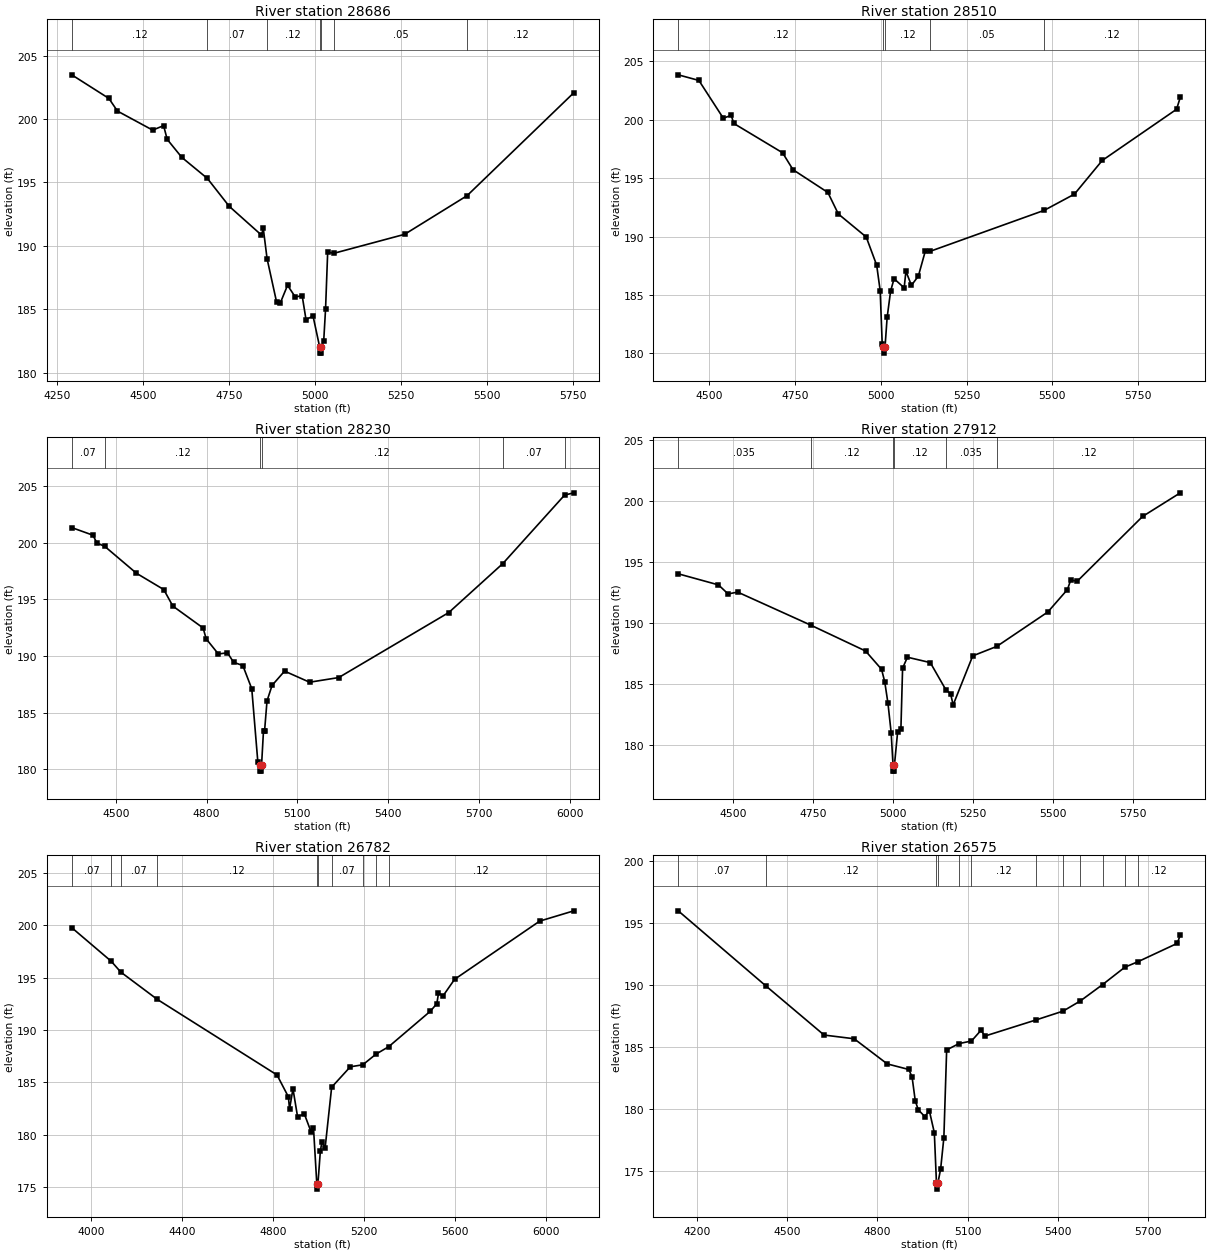
Type RM Length L Ch R = 1 ,28686   ,176,176,176
BEGIN DESCRIPTION:
Mapping XS 026ccb17
END DESCRIPTION:
XS GIS Cut Line= 3
      2512226.78     13474173.39      2511495.48     13473917.33
      2510818.08     13474012.55
#Sta/Elev= 30
  4293.4  203.49  4401.2  201.63  4426.2  200.63  4528.4  199.13  4560.2  199.48
  4570.7   198.4  4613.1  196.98  4687.4  195.32  4750.9  193.12  4844.6  190.85
  4849.9  191.37  4860.9  188.99  4888.6  185.56  4899.2  185.49  4920.4  186.89
    4943  185.96  4962.8  186.08    4974  184.19  4994.5  184.46  5013.6  182.04
  5013.9  181.54  5017.7  181.54  5017.9  182.04  5025.5  182.52  5030.8  184.99
    5037  189.51  5054.5  189.41  5260.6  190.91  5442.1  193.96  5752.3  202.08
#Mann= 7 ,-1 , 0
  4293.4     .12       0  4687.4     .07       0  4860.9     .12       0
  5013.6     .05       0  5017.9     .12       0  5054.5     .05       0
  5442.1     .12       0
Bank Sta=5013.6,5017.9
XS Rating Curve= 0 ,0
Exp/Cntr=0.3,0.1

Type RM Length L Ch R = 1 ,28510   ,280,280,280
BEGIN DESCRIPTION:
Mapping XS 375439d7
END DESCRIPTION:
XS GIS Cut Line= 3
      2512254.24     13473937.51      2511667.46     13473829.87
      2510809.92      13473961.8
#Sta/Elev= 30
  4409.2  203.85  4469.4  203.37  4540.6  200.14  4563.8  200.38  4571.1  199.69
  4713.4  197.18  4743.9  195.73  4845.6  193.78  4876.1  191.94  4957.4  189.97
  4987.9  187.56  4998.1  185.38  5004.1  180.79  5007.8  180.53  5008.1  180.03
  5012.2  180.53  5018.4  183.08  5028.5  185.33  5038.6   186.4  5068.1  185.62
  5073.2  187.04  5089.2  185.83  5109.4  186.62  5129.7  188.76  5144.4  188.75
  5476.4  192.25  5564.7  193.64  5645.7  196.52  5862.4   200.9  5873.4  201.93
#Mann= 5 ,-1 , 0
  4409.2     .12       0  5007.8     .05       0  5012.2     .12       0
  5144.4     .05       0  5476.4     .12       0
Bank Sta=5007.8,5012.2
XS Rating Curve= 0 ,0
Exp/Cntr=0.3,0.1

Type RM Length L Ch R = 1 ,28230   ,318,318,318
BEGIN DESCRIPTION:
Mapping XS 94c0d51f
END DESCRIPTION:
XS GIS Cut Line= 3
      2512268.12     13473645.84      2511632.74     13473593.76
      2510640.47     13473840.09
#Sta/Elev= 30
  4354.3  201.34  4424.2  200.67  4437.7  199.97    4463  199.69  4568.1  197.31
  4658.4  195.87  4688.5  194.41  4788.4  192.48  4798.9  191.51    4839  190.18
  4869.1  190.29  4889.2  189.45  4919.9  189.16  4949.4  187.11  4969.5  180.63
  4977.3  180.34  4977.6  179.84  4981.4  179.84  4981.7  180.34  4988.2  183.42
  4991.8  183.42  4999.8  186.04  5016.5  187.41  5057.8  188.67  5140.6  187.69
  5236.8   188.1  5600.7  193.84  5779.6  198.17  5983.6  204.21  6014.2  204.41
#Mann= 6 ,-1 , 0
  4354.3     .07       0    4463     .12       0  4977.3     .05       0
  4981.7     .12       0  5779.6     .07       0  5983.6     .05       0
Bank Sta=4977.3,4981.7
XS Rating Curve= 0 ,0
Exp/Cntr=0.3,0.1

Type RM Length L Ch R = 1 ,27912   ,1130,1130,1130
BEGIN DESCRIPTION:
Mapping XS 0aa26b89
END DESCRIPTION:
XS GIS Cut Line= 3
      2512250.87     13473335.35       2511573.8     13473324.94
      2510699.43      13473507.1
#Sta/Elev= 30
  4328.6  194.05  4454.5  193.14  4484.5   192.4  4514.5  192.55  4742.3  189.85
  4914.5  187.72  4964.5  186.22  4974.5  185.19  4984.5  183.44  4994.5  181.03
  5000.4  178.37  5000.7  177.87  5004.5  177.87  5004.8  178.37  5014.7  181.06
    5025  181.31  5030.3  186.31  5045.4  187.21  5116.9  186.77  5165.6  184.54
  5180.5  184.21  5188.4   183.3  5249.7  187.32  5325.1   188.1  5484.6  190.92
  5545.9  192.76  5556.1  193.54  5576.5  193.44  5780.8  198.75  5898.9  200.69
#Mann= 6 ,-1 , 0
  4328.6    .035       0  4742.3     .12       0  5000.4     .05       0
  5004.8     .12       0  5165.6    .035       0  5325.1     .12       0
Bank Sta=5000.4,5004.8
XS Rating Curve= 0 ,0
Exp/Cntr=0.3,0.1

Type RM Length L Ch R = 1 ,26782   ,207,207,207
BEGIN DESCRIPTION:
Mapping XS e208d35f
END DESCRIPTION:
XS GIS Cut Line= 4
      2512355.07     13472653.06       2511256.1      13472741.6
       2510948.8     13472887.44      2510422.78     13473444.71
#Sta/Elev= 30
  3915.5  199.76  4089.3  196.55  4131.2  195.52  4291.4  192.92  4818.5   185.7
  4868.6  183.61  4873.6  182.43  4888.7  184.38  4908.8  181.73  4938.9  181.97
    4969  180.23    4979  180.67  4993.6   175.3    4994   174.8  4998.5   175.3
  5009.1  178.41  5016.1  179.32  5030.3  178.76  5058.9  184.53    5141  186.48
  5195.9  186.67  5254.1  187.69    5310   188.4  5493.4  191.79  5521.7  192.51
    5529   193.5    5550  193.28  5599.8  194.83  5974.4  200.39  6124.5  201.37
#Mann= 10 ,-1 , 0
  3915.5     .07       0  4089.3    .035       0  4131.2     .07       0
  4291.4     .12       0  4993.6     .05       0  4998.5     .12       0
  5058.9     .07       0  5195.9     .12       0  5254.1     .07       0
    5310     .12       0
Bank Sta=4993.6,4998.5
XS Rating Curve= 0 ,0
Exp/Cntr=0.3,0.1

Type RM Length L Ch R = 1 ,26575   ,715,715,715
BEGIN DESCRIPTION:
Mapping XS fdc6c7ca
END DESCRIPTION:
XS GIS Cut Line= 4
      2512079.88     13472518.54      2511353.35     13472505.52
      2511176.27     13472565.42      2510596.98     13473051.19
#Sta/Elev= 30
  4137.6  196.01  4428.9  189.95  4622.6  185.98  4722.6  185.68  4832.6  183.65
  4904.4   183.2  4915.3  182.58  4925.8  180.67  4935.9  179.94  4957.5   179.4
  4972.6  179.87  4989.2   178.1  4996.3  174.04  4996.7  173.54  5001.2  174.04
  5010.3  175.19  5020.9  177.69  5030.2  184.78  5071.2  185.29  5112.8   185.5
  5144.2  186.36  5157.7   185.9    5326  187.19  5417.1  187.91  5474.5  188.73
  5548.5  190.05  5622.9  191.46  5665.3  191.89  5796.7  193.38  5807.2  194.05
#Mann= 12 ,-1 , 0
  4137.6     .07       0  4428.9     .12       0  4996.3     .05       0
  5001.2     .12       0  5071.2     .07       0  5112.8     .12       0
    5326     .07       0  5417.1      .1       0  5474.5     .07       0
  5548.5      .1       0  5622.9     .07       0  5665.3     .12       0
Bank Sta=4996.3,5001.2
XS Rating Curve= 0 ,0
Exp/Cntr=0.3,0.1