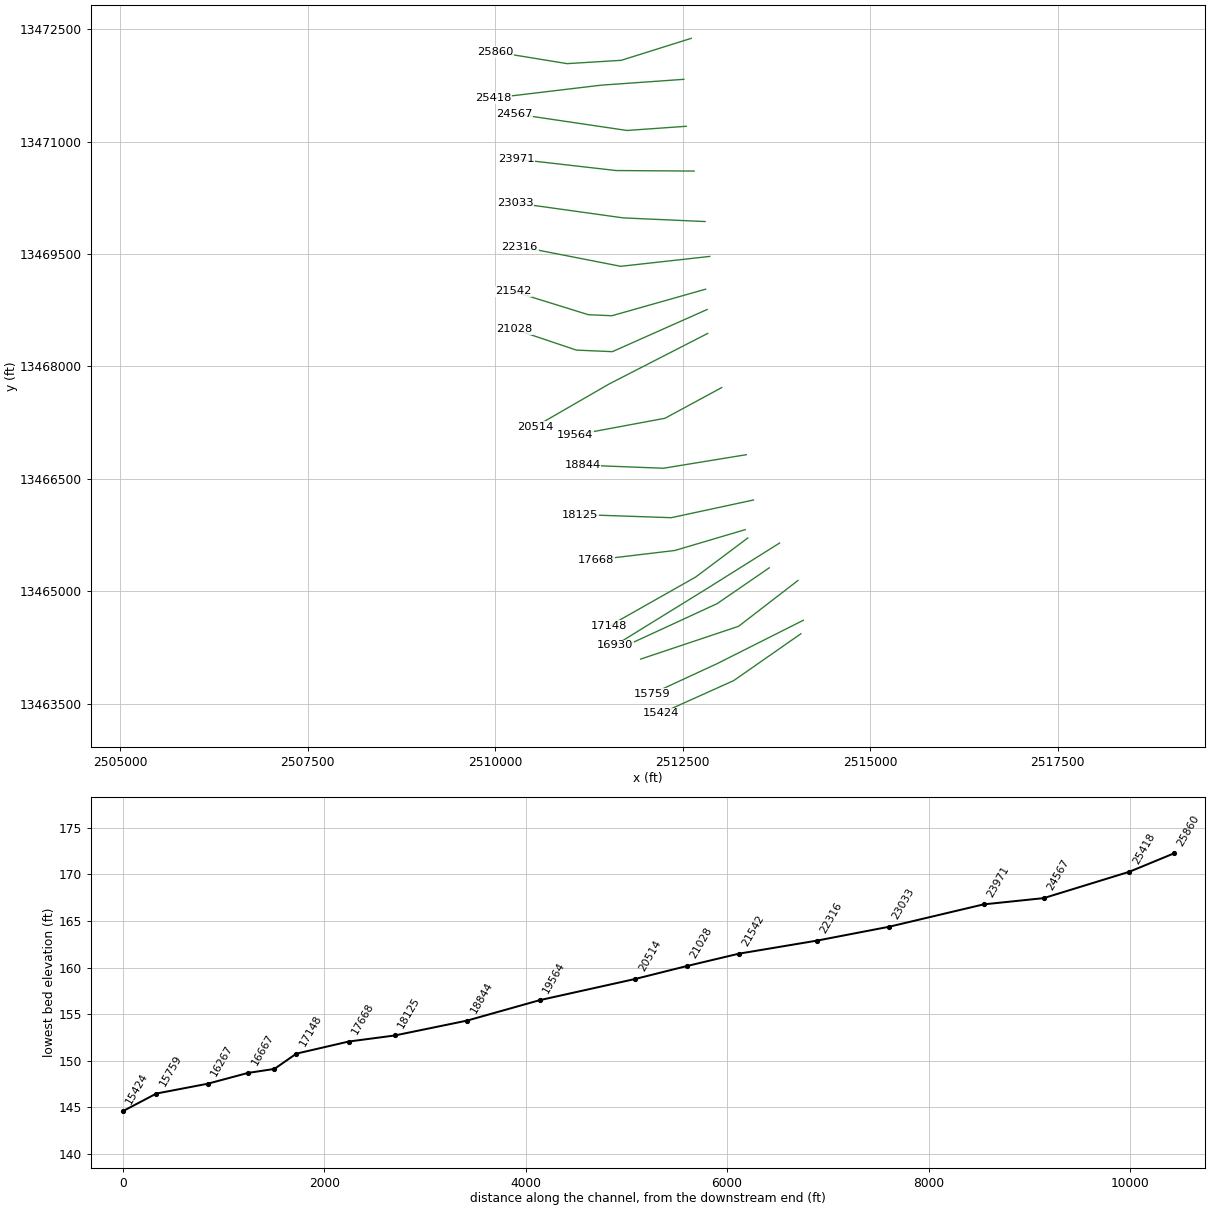
HEC-RAS study KILGORE CREEK.prj: KILGORE CREEK Base Level Engineering

--- KILGORE CREEK.g01 (geometry) --- (continued)

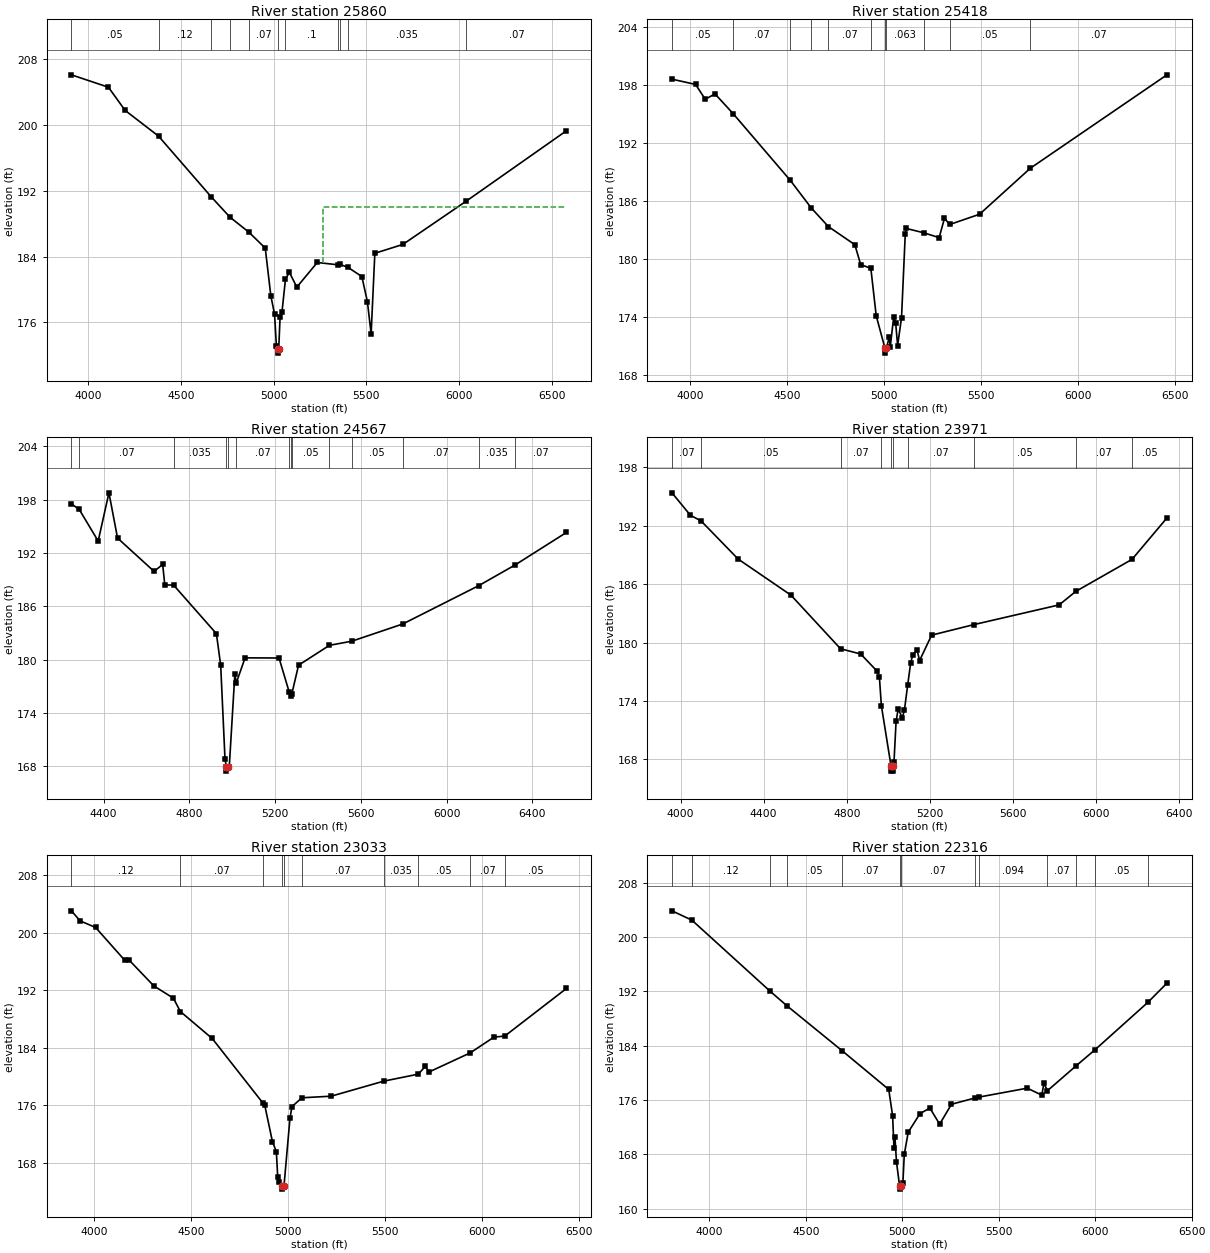
Type RM Length L Ch R = 1 ,25860   ,442,442,442
BEGIN DESCRIPTION:
Mapping XS a4e73e07
END DESCRIPTION:
XS GIS Cut Line= 4
      2512615.48     13472377.02      2511681.47     13472083.65
      2510960.12     13472039.38      2510004.42     13472195.62
#Sta/Elev= 30
  3908.9  206.12  4108.6  204.61  4198.5  201.79  4378.8  198.66  4661.9   191.3
    4764   188.8  4866.1  186.97  4954.5  185.03  4984.6  179.22  5004.6     177
  5014.6  173.11  5022.2  172.75  5022.5  172.25  5027.1  172.75  5034.6  176.69
  5044.7  177.24  5063.6  181.27  5084.7  182.08  5124.8  180.28    5235  183.28
  5346.4     183  5357.4  183.04  5399.4  182.71  5475.5  181.57  5505.5  178.51
  5525.6  174.59  5545.6   184.4  5696.9  185.48  6039.5  190.76    6579  199.31
#Mann= 11 ,-1 , 0
  3908.9     .05       0  4378.8     .12       0  4661.9    .035       0
    4764     .12       0  4866.1     .07       0  5022.2     .05       0
  5063.6      .1       0  5346.4    .035       0  5357.4      .1       0
  5399.4    .035       0  6039.5     .07       0
#XS Ineff= 2 , 0
       0                  5265.1       0     190
Permanent Ineff=
       F       F
Bank Sta=5022.2,5027.1
XS Rating Curve= 0 ,0
Exp/Cntr=0.3,0.1

Type RM Length L Ch R = 1 ,25418   ,851,851,851
BEGIN DESCRIPTION:
Mapping XS fe7641b2
END DESCRIPTION:
XS GIS Cut Line= 3
      2512516.51     13471830.14      2511412.35     13471752.02
      2509974.81     13471580.14
#Sta/Elev= 30
  3905.5   198.6  4027.3  198.06  4077.4  196.52  4127.6  197.08  4221.1  195.04
  4516.2  188.14  4624.4  185.29  4712.9  183.36  4849.4  181.49  4879.4  179.44
    4932  179.04  4959.6  174.15  5004.8  170.78  5005.3  170.28  5012.4  170.78
  5027.1  171.95  5032.2  170.93    5050  174.04  5060.1  173.39  5070.2  171.06
  5090.3  173.95  5109.6  182.61  5114.6  183.17  5205.2  182.72  5284.4  182.22
  5311.9  184.21  5339.4  183.58  5493.2  184.64  5755.5   189.4  6460.2  199.05
#Mann= 11 ,-1 , 0
  3905.5     .05       0  4221.1     .07       0  4516.2    .035       0
  4624.4     .12       0  4712.9     .07       0    4932    .063       0
  5004.8     .05       0  5012.4    .063       0  5205.2     .07       0
  5339.4     .05       0  5755.5     .07       0
Bank Sta=5004.8,5012.4
XS Rating Curve= 0 ,0
Exp/Cntr=0.3,0.1

Type RM Length L Ch R = 1 ,24567   ,596,596,596
BEGIN DESCRIPTION:
Mapping XS dcead758
END DESCRIPTION:
XS GIS Cut Line= 3
      2512549.52     13471203.41      2511757.83     13471147.85
      2510259.13     13471369.88
#Sta/Elev= 30
  4249.5  197.52  4285.5  196.92  4374.3  193.34  4424.5  198.77  4464.6  193.68
    4635  189.93  4675.1  190.71  4685.1   188.4  4725.9  188.39  4925.7  182.92
  4945.7  179.37  4965.8  168.83  4971.9  167.95  4972.4  167.45  4979.7  167.95
  4985.8  167.95  5011.7  178.38  5018.3  177.37  5059.5   180.2  5217.9  180.18
  5264.7  176.39  5272.4  175.96  5277.4  176.13  5308.8  179.37  5453.1  181.61
    5557  182.07  5795.1  184.01  6148.2  188.31  6318.1  190.64  6558.2  194.31
#Mann= 14 ,-1 , 0
  4249.5     .12       0  4285.5     .07       0  4725.9    .035       0
  4971.9     .05       0  4979.7    .035       0  5018.3     .07       0
  5264.7     .05       0  5272.4     .07       0  5277.4     .05       0
  5453.1     .07       0    5557     .05       0  5795.1     .07       0
  6148.2    .035       0  6318.1     .07       0
Bank Sta=4971.9,4979.7
XS Rating Curve= 0 ,0
Exp/Cntr=0.3,0.1

Type RM Length L Ch R = 1 ,23971   ,938,938,938
BEGIN DESCRIPTION:
Mapping XS 734f616a
END DESCRIPTION:
XS GIS Cut Line= 3
      2512653.71     13470606.19        2511612.     13470613.13
      2510279.36     13470765.83
#Sta/Elev= 30
  3958.5  195.39  4047.2  193.09  4099.2  192.49  4277.2  188.58  4531.4  184.87
    4770  179.36  4867.2  178.82  4947.2  177.03  4957.2  176.44  4966.7  173.51
  5013.4  167.28  5013.9  166.78  5020.8  166.78  5021.3  167.28  5027.4   167.7
  5037.5  171.89  5047.5  173.15  5067.7  172.28  5077.7  173.06  5093.4  175.64
  5107.9  177.93    5118  178.73  5138.1  179.26  5150.8  178.15  5208.6  180.76
  5413.5  181.85  5822.6  183.87  5902.3  185.25  6173.4  188.55  6341.6  192.81
#Mann= 10 ,-1 , 0
  3958.5     .07       0  4099.2     .05       0    4770     .07       0
  4966.7      .1       0  5013.4     .05       0  5021.3      .1       0
  5093.4     .07       0  5413.5     .05       0  5902.3     .07       0
  6173.4     .05       0
Bank Sta=5013.4,5021.3
XS Rating Curve= 0 ,0
Exp/Cntr=0.3,0.1

Type RM Length L Ch R = 1 ,23033   ,717,717,717
BEGIN DESCRIPTION:
Mapping XS 2c990f24
END DESCRIPTION:
XS GIS Cut Line= 3
      2512799.53     13469932.57      2511709.22     13469981.19
      2510264.78     13470182.57
#Sta/Elev= 30
  3884.1  203.01  3928.7  201.62  4008.7   200.7  4158.9  196.14  4178.9  196.24
    4309  192.58  4409.1  190.89  4445.4  189.03  4609.3  185.29  4869.1  176.38
  4879.6  176.07  4919.7  170.96  4939.7  169.59  4946.8  166.06  4951.8  165.42
  4970.9  164.88  4971.4  164.38  4979.3  164.88    5010  174.26  5020.1  175.83
  5071.2  177.06  5222.1  177.28  5493.2  179.37  5670.9  180.34  5706.7  181.41
  5726.9  180.65  5938.3  183.29  6060.1  185.47  6116.5  185.63  6433.9  192.23
#Mann= 10 ,-1 , 0
  3884.1     .12       0  4445.4     .07       0  4869.1    .035       0
  4970.9     .05       0  4979.3    .035       0  5071.2     .07       0
  5493.2    .035       0  5670.9     .05       0  5938.3     .07       0
  6116.5     .05       0
Bank Sta=4970.9,4979.3
XS Rating Curve= 0 ,0
Exp/Cntr=0.3,0.1

Type RM Length L Ch R = 1 ,22316   ,774,774,774
BEGIN DESCRIPTION:
Mapping XS 676e2aa5
END DESCRIPTION:
XS GIS Cut Line= 3
      2512862.02      13469467.3       2511674.5     13469335.35
       2510328.6     13469598.98
#Sta/Elev= 30
  3805.6  203.88  3908.8  202.51    4316     192  4401.8  189.89  4687.9  183.27
  4929.5  177.57  4949.6  173.69  4956.5  169.02  4961.5  170.52  4969.7  166.88
  4985.6  163.39  4986.1  162.89  4994.1  163.39  5002.7  163.74  5010.1  168.02
  5030.5  171.28  5091.6  174.01  5142.6  174.83  5193.5  172.46  5254.7  175.39
  5377.4  176.32    5396  176.44  5647.9  177.76  5723.4  176.72  5733.6  178.48
  5752.5  177.39  5899.6  181.02  6000.3  183.45  6272.6  190.39  6371.9  193.23
#Mann= 13 ,-1 , 0
  3805.6     .05       0  3908.8     .12       0    4316     .07       0
  4401.8     .05       0  4687.9     .07       0  4985.6     .05       0
  4994.1     .07       0  5377.4    .063       0    5396    .094       0
  5752.5     .07       0  5899.6    .094       0  6000.3     .05       0
  6272.6     .07       0
Bank Sta=4985.6,4994.1
XS Rating Curve= 0 ,0
Exp/Cntr=0.3,0.1

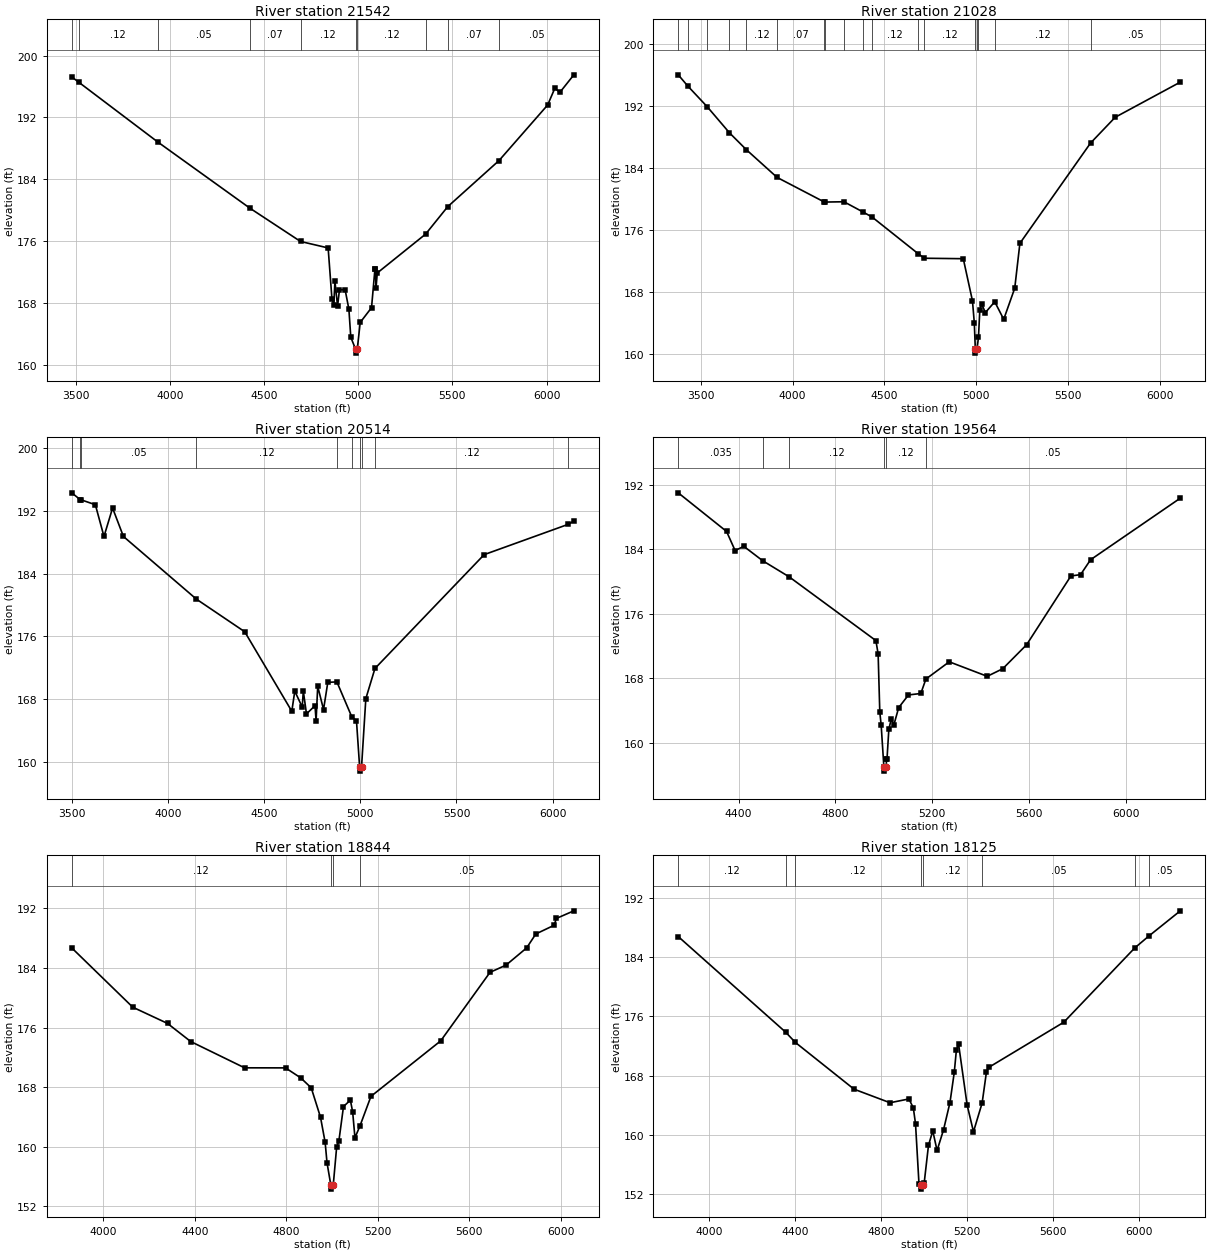
Type RM Length L Ch R = 1 ,21542   ,514,514,514
BEGIN DESCRIPTION:
Mapping XS abbfea54
END DESCRIPTION:
XS GIS Cut Line= 4
      2512806.47     13469029.81      2511556.44     13468675.63
      2511243.94     13468689.52      2510238.49     13469001.56
#Sta/Elev= 30
  3480.1  197.23  3516.3  196.56  3937.1   188.8  4425.9  180.24  4694.1  175.94
  4840.8   175.1  4860.9  168.54  4870.9  167.77  4876.8  170.78  4890.9  167.57
  4900.9  169.69  4930.9  169.69  4950.9  167.18    4961  163.55  4986.5  161.99
    4987  161.49  4995.4  161.99    5011  165.46  5071.1  167.37  5089.1  172.34
  5092.1  172.34    5095  169.93  5101.5  171.86  5358.1  176.89  5475.5  180.44
  5747.9  186.41    6006   193.6  6043.9  195.76  6071.1  195.24  6144.9   197.5
#Mann= 10 ,-1 , 0
  3480.1     .05       0  3516.3     .12       0  3937.1     .05       0
  4425.9     .07       0  4694.1     .12       0  4986.5     .05       0
  4995.4     .12       0  5358.1     .05       0  5475.5     .07       0
  5747.9     .05       0
Bank Sta=4986.5,4995.4
XS Rating Curve= 0 ,0
Exp/Cntr=0.3,0.1

Type RM Length L Ch R = 1 ,21028   ,514,514,514
BEGIN DESCRIPTION:
Mapping XS 52445414
END DESCRIPTION:
XS GIS Cut Line= 4
      2512827.29     13468758.97      2511563.39     13468196.46
      2511084.22      13468217.3      2510258.94      13468494.7
#Sta/Elev= 30
  3377.7  196.04  3429.9  194.59  3536.1  191.91  3656.8  188.56  3748.6  186.39
  3915.8  182.82  4173.6  179.64  4174.8  179.64  4279.9  179.68  4386.1  178.33
  4433.8   177.7  4683.8  172.99  4717.8   172.4  4929.7  172.34  4979.7  166.91
  4989.7  164.09  4995.3  160.67  4995.8  160.17  5004.2  160.67  5012.4  162.19
  5019.8  165.75  5029.8  166.51  5049.8  165.39  5100.9  166.79  5149.9  164.53
  5209.9  168.54  5237.9  174.32  5622.5  187.24  5756.9  190.57  6111.4   195.1
#Mann= 18 ,-1 , 0
  3377.7     .05       0  3429.9     .07       0  3536.1     .12       0
  3656.8     .07       0  3748.6     .12       0  3915.8     .07       0
  4173.6    .035       0  4174.8     .07       0  4279.9    .035       0
  4386.1     .07       0  4433.8     .12       0  4683.8     .07       0
  4717.8     .12       0  4995.3     .05       0  5004.2     .12       0
  5012.4     .07       0  5100.9     .12       0  5622.5     .05       0
Bank Sta=4995.3,5004.2
XS Rating Curve= 0 ,0
Exp/Cntr=0.3,0.1

Type RM Length L Ch R = 1 ,20514   ,950,950,950
BEGIN DESCRIPTION:
Mapping XS 20cfc608
END DESCRIPTION:
XS GIS Cut Line= 3
      2512834.23     13468439.52      2511521.72     13467765.91
       2510535.6     13467196.46
#Sta/Elev= 30
  3497.1   194.3    3542  193.41  3543.2  193.43  3619.9  192.78  3664.8  188.73
  3709.6  192.36    3766  188.73  4145.5  180.74  4397.5  176.57  4642.7  166.42
  4658.2  168.99    4697  166.95  4702.6  168.99  4719.1  166.09  4763.5  167.13
  4769.1  165.22  4777.6   169.6  4807.9  166.64  4830.1  170.11  4877.4  170.17
  4955.3  165.69  4979.3  165.23  4995.9  159.28  4996.4  158.78  5005.7  159.28
  5028.1  168.03  5075.5  171.88  5644.1  186.41  6080.7  190.27  6111.1  190.69
#Mann= 10 ,-1 , 0
  3497.1     .05       0    3542     .07       0  3543.2     .05       0
  4145.5     .12       0  4877.4     .07       0  4955.3      .1       0
  4995.9     .05       0  5005.7      .1       0  5075.5     .12       0
  6080.7     .07       0
Bank Sta=4995.9,5005.7
XS Rating Curve= 0 ,0
Exp/Cntr=0.3,0.1

Type RM Length L Ch R = 1 ,19564   ,720,720,720
BEGIN DESCRIPTION:
Mapping XS eff3c52d
END DESCRIPTION:
XS GIS Cut Line= 3
      2513021.73      13467717.3      2512264.78     13467307.58
       2511070.3     13467085.35
#Sta/Elev= 30
  4150.1  191.02  4349.9  186.23  4385.2  183.86  4421.3  184.38  4499.1   182.6
  4609.2  180.59  4967.3  172.69  4976.5  171.04  4983.4  163.83  4989.1  162.18
  5000.3     157  5000.8   156.5  5010.4     157  5010.8  158.06  5013.3  158.06
  5020.8  161.69  5030.9  162.98  5041.1  162.19  5061.5  164.38    5102  165.95
    5153  166.13    5174  167.92  5270.5  170.06  5427.6  168.26  5491.7   169.2
  5590.4  172.18  5773.5  180.71  5813.4  180.87  5854.8  182.72  6225.8  190.36
#Mann= 6 ,-1 , 0
  4150.1    .035       0  4499.1     .07       0  4609.2     .12       0
  5000.3     .05       0  5010.4     .12       0    5174     .05       0
Bank Sta=5000.3,5010.4
XS Rating Curve= 0 ,0
Exp/Cntr=0.3,0.1

Type RM Length L Ch R = 1 ,18844   ,719,719,719
BEGIN DESCRIPTION:
Mapping XS 14e413d3
END DESCRIPTION:
XS GIS Cut Line= 3
      2513348.11     13466821.46      2512243.94     13466640.91
      2511168.78     13466682.53
#Sta/Elev= 30
  3862.2   186.7  4128.8  178.74  4280.8  176.56  4382.1  174.13  4617.6   170.6
  4796.6  170.59  4863.1  169.25    4909  167.91  4949.6  163.96  4969.8  160.59
    4978  157.85  4994.9  154.81  4995.4  154.31  5005.1  154.81    5020  159.91
    5030  160.81    5050   165.4  5080.1  166.26  5090.1  164.68  5100.1  161.21
  5121.7  162.77  5170.1  166.77    5475  174.22  5690.5  183.42  5760.6  184.39
  5850.6   186.7  5890.7  188.57  5970.7  189.74  5980.7  190.66    6057  191.68
#Mann= 4 ,-1 , 0
  3862.2     .12       0  4994.9     .05       0  5005.1     .12       0
  5121.7     .05       0
Bank Sta=4994.9,5005.1
XS Rating Curve= 0 ,0
Exp/Cntr=0.3,0.1

Type RM Length L Ch R = 1 ,18125   ,457,457,457
BEGIN DESCRIPTION:
Mapping XS 94ffd553
END DESCRIPTION:
XS GIS Cut Line= 3
      2513445.37      13466217.3      2512348.11     13465981.19
       2511132.8     13466022.85
#Sta/Elev= 30
  3854.4  186.77  4354.9  173.87  4399.6   172.5  4673.1  166.19  4840.8  164.36
  4928.8  164.87  4949.3  163.67  4959.5  161.53  4975.8  153.37  4984.5  153.21
    4985  152.71  4995.2  153.21  4999.9  153.54  5019.9  158.61  5039.9  160.57
  5059.9  157.92    5090  160.71    5120  164.39    5140  168.45    5150   171.5
    5160  172.28    5200  164.04  5229.5  160.45  5269.8  164.33  5290.1  168.55
  5300.1  169.12  5650.3  175.22  5980.4  185.23  6047.1  186.86  6192.8  190.24
#Mann= 8 ,-1 , 0
  3854.4     .12       0  4354.9     .05       0  4399.6     .12       0
  4984.5     .05       0  4995.2     .12       0  5269.8     .05       0
  5980.4     .12       0  6047.1     .05       0
Bank Sta=4984.5,4995.2
XS Rating Curve= 0 ,0
Exp/Cntr=0.3,0.1

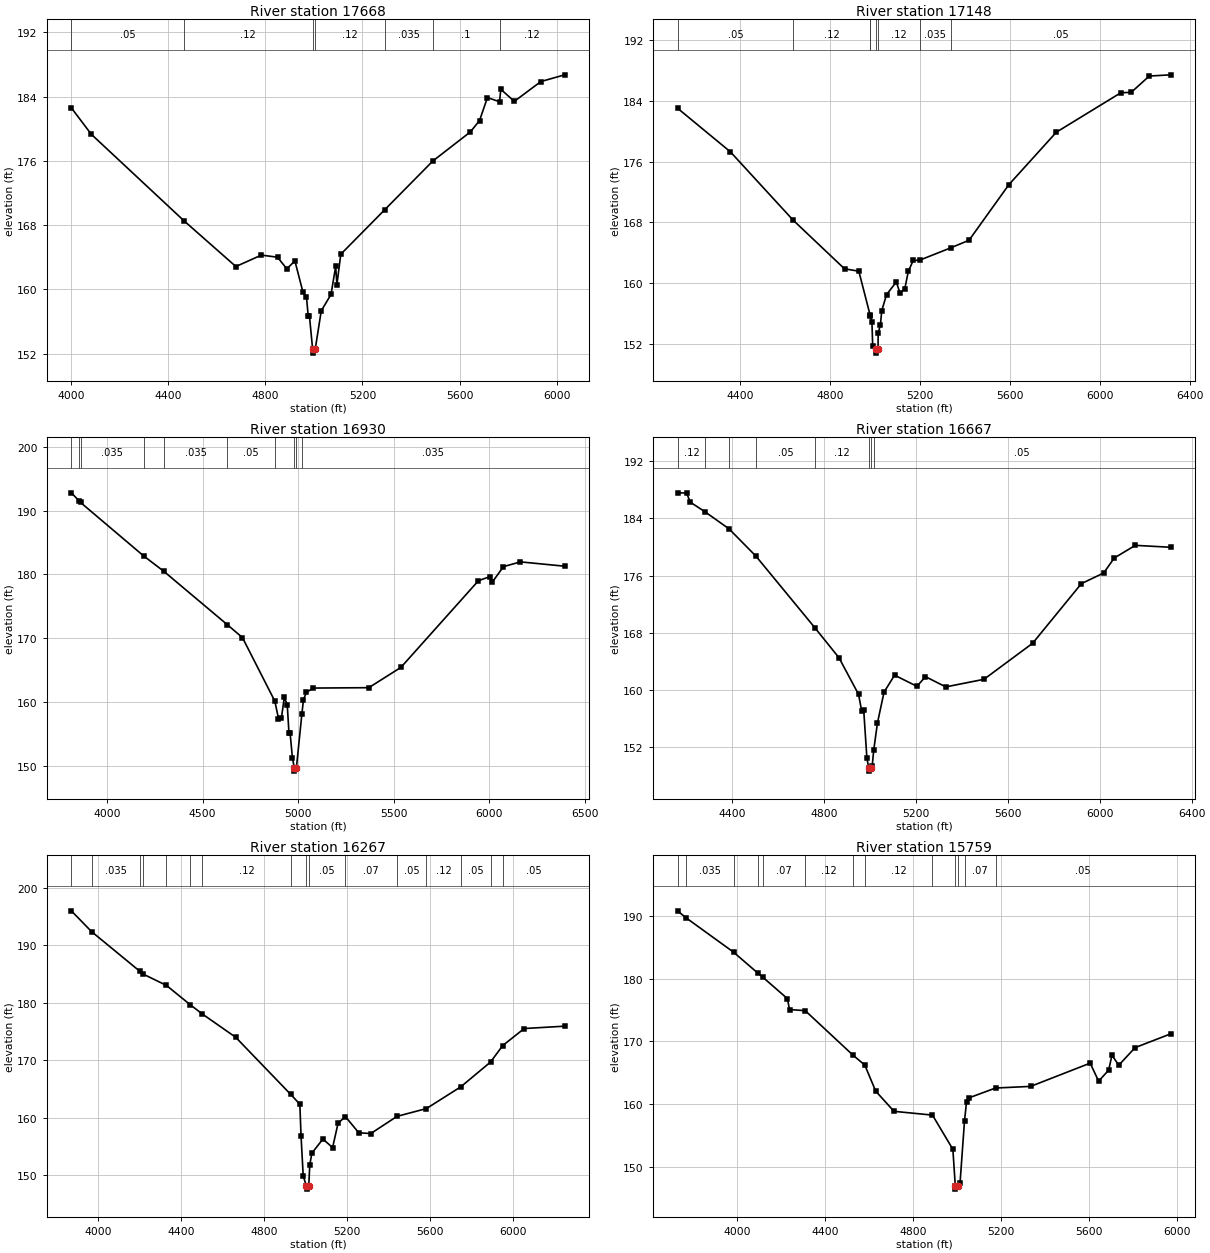
Type RM Length L Ch R = 1 ,17668   ,520,520,520
BEGIN DESCRIPTION:
Mapping XS fffce112
END DESCRIPTION:
XS GIS Cut Line= 3
      2513334.21     13465821.46      2512396.72     13465543.69
      2511349.01     13465418.79
#Sta/Elev= 30
  4000.3  182.59  4082.9  179.29  4463.9  168.55  4678.4  162.84  4783.4  164.26
  4849.9     164  4888.3  162.55  4921.6  163.54  4954.8  159.65  4969.4     159
  4976.4   156.7  4981.5   156.7  4994.6  152.56  4995.1  152.06  5005.4  152.56
  5030.2  157.33  5070.4  159.36  5089.6  162.85  5094.7  160.58  5110.7  164.37
  5291.2  169.89  5489.9  175.97  5644.5  179.59  5682.4     181    5715  183.87
    5765  183.35    5770   184.9  5825.8   183.4    5935  185.86  6033.2   186.7
#Mann= 7 ,-1 , 0
  4000.3     .05       0  4463.9     .12       0  4994.6     .05       0
  5005.4     .12       0  5291.2    .035       0  5489.9      .1       0
    5765     .12       0
Bank Sta=4994.6,5005.4
XS Rating Curve= 0 ,0
Exp/Cntr=0.3,0.1

Type RM Length L Ch R = 1 ,17148   ,218,218,218
BEGIN DESCRIPTION:
Mapping XS bd566afd
END DESCRIPTION:
XS GIS Cut Line= 3
      2513368.95     13465710.36       2512674.5     13465189.52
      2511521.75     13464536.76
#Sta/Elev= 30
  4121.8  183.04  4356.9  177.29  4635.9  168.28  4864.2  161.87  4927.7  161.56
  4977.5  155.82  4979.4  155.61    4986  154.84  4989.5  151.64  5002.4  151.26
  5002.9  150.76  5013.3  151.26  5013.6  153.39  5023.8   154.5  5029.5  156.34
  5051.1  158.48  5094.4  160.14  5110.3   158.7  5131.9  159.21  5147.8  161.55
  5169.5  162.97  5198.9  163.02  5336.6  164.64  5417.7  165.64  5595.2  172.98
  5805.8  179.88  6092.5  185.08  6138.5  185.13  6218.9  187.28  6314.6  187.44
#Mann= 8 ,-1 , 0
  4121.8     .05       0  4635.9     .12       0  4977.5    .035       0
  4979.4     .12       0  5002.4     .05       0  5013.3     .12       0
  5198.9    .035       0  5336.6     .05       0
Bank Sta=5002.4,5013.3
XS Rating Curve= 0 ,0
Exp/Cntr=0.3,0.1

Type RM Length L Ch R = 1 ,16930   ,263,263,263
BEGIN DESCRIPTION:
Mapping XS c1df8b45
END DESCRIPTION:
XS GIS Cut Line= 3
      2513792.95     13465642.96      2512827.28     13465036.74
      2511601.57      13464279.2
#Sta/Elev= 30
  3812.9  192.81  3852.7  191.57    3861   191.3  4191.4   182.9  4295.9  180.51
  4629.7  172.09  4708.1  170.09  4877.8   160.1  4896.7  157.37  4911.9  157.44
  4927.2  160.68  4942.5  159.57  4951.5  155.15  4957.4  155.15  4969.7  151.19
  4979.6  149.62  4980.1  149.12  4990.5  149.62  5018.9  158.03  5027.6  160.35
    5043   161.5  5079.6  162.16  5369.2  162.22  5537.1   165.4  5943.2  179.02
    6002  179.64  6015.9  178.81  6073.8  181.22  6162.5  181.97    6394  181.29
#Mann= 10 ,-1 , 0
  3812.9    .035       0  3852.7     .12       0    3861    .035       0
  4191.4     .12       0  4295.9    .035       0  4629.7     .05       0
  4877.8    .063       0  4979.6     .05       0  4990.5    .063       0
  5018.9    .035       0
Bank Sta=4979.6,4990.5
XS Rating Curve= 0 ,0
Exp/Cntr=0.3,0.1

Type RM Length L Ch R = 1 ,16667   ,400,400,400
BEGIN DESCRIPTION:
Mapping XS f1899f18
END DESCRIPTION:
XS GIS Cut Line= 3
      2513654.47     13465311.66        2512960.     13464834.21
      2511775.08     13464287.33
#Sta/Elev= 30
  4161.5  187.58  4201.5  187.55  4216.4  186.29    4283  184.89    4386  182.54
    4503  178.73  4759.4  168.73  4864.6  164.53  4949.7  159.42  4963.3  157.08
  4972.1  157.25  4986.1  150.49  4993.7  149.19  4994.2  148.69  5004.7  149.19
  5009.3  149.45  5015.7   151.6  5031.8  155.39  5060.7  159.73  5106.6   162.1
  5203.9  160.54  5241.1  161.89  5329.6  160.46  5495.7  161.52  5707.7  166.56
  5919.8  174.89    6017  176.38  6062.9  178.47  6154.7  180.24  6309.3  179.97
#Mann= 8 ,-1 , 0
  4161.5     .12       0    4283     .05       0    4386     .07       0
    4503     .05       0  4759.4     .12       0  4993.7     .05       0
  5004.7     .12       0  5015.7     .05       0
Bank Sta=4993.7,5004.7
XS Rating Curve= 0 ,0
Exp/Cntr=0.3,0.1

Type RM Length L Ch R = 1 ,16267   ,508,508,508
BEGIN DESCRIPTION:
Mapping XS 46b7b315
END DESCRIPTION:
XS GIS Cut Line= 3
      2514037.82     13465143.14      2513246.11       13464532.
      2511940.51     13464094.49
#Sta/Elev= 30
  3872.3     196  3969.5  192.39  4203.4  185.44  4218.6  184.98  4330.5  183.01
  4445.4  179.64    4504  178.02  4664.2  173.98  4929.4  164.03  4973.5  162.32
  4979.1  156.85  4989.6  149.84  5005.2  148.03  5005.7  147.53  5016.2  148.03
  5021.3  151.74  5031.3   153.8  5084.5  156.25  5131.3  154.77  5157.5     159
  5192.7  160.17  5257.5  157.34  5315.3  157.21  5441.4   160.2  5583.3  161.56
  5749.4  165.36  5892.2  169.66  5951.2  172.54  6054.8   175.5  6249.4  175.91
#Mann= 16 ,-1 , 0
  3872.3     .05       0  3969.5    .035       0  4203.4     .05       0
  4218.6     .07       0  4330.5     .12       0  4445.4     .07       0
    4504     .12       0  4929.4     .05       0  5005.2     .05       0
  5016.2     .05       0  5192.7     .07       0  5441.4     .05       0
  5583.3     .12       0  5749.4     .05       0  5892.2    .035       0
  5951.2     .05       0
Bank Sta=5005.2,5016.2
XS Rating Curve= 0 ,0
Exp/Cntr=0.3,0.1

Type RM Length L Ch R = 1 ,15759   ,335,335,335
BEGIN DESCRIPTION:
Mapping XS c704e2c9
END DESCRIPTION:
XS GIS Cut Line= 3
      2514110.13     13464612.84      2512964.34      13464035.6
      2512091.98     13463631.97
#Sta/Elev= 30
  3729.4  190.77  3767.8  189.67  3984.8  184.18  4093.4   180.9    4117  180.22
  4229.1   176.8    4239  175.06  4310.4  174.88  4527.4  167.81  4581.5  166.22
  4630.9  162.08  4714.3  158.86  4889.3  158.26    4982  152.82  4993.2  146.98
  4993.7  146.48  5004.3  146.98  5014.8   147.5    5035  157.34  5044.4  160.41
  5055.7  161.01  5176.1  162.57    5336  162.83  5606.7  166.53  5645.1  163.66
  5690.9  165.42  5705.8  167.79  5736.8   166.2    5811     169  5973.6   171.2
#Mann= 13 ,-1 , 0
  3729.4     .07       0  3767.8    .035       0  3984.8     .07       0
  4093.4     .12       0    4117     .07       0  4310.4     .12       0
  4527.4    .035       0  4581.5     .12       0  4889.3     .05       0
  4993.2     .05       0  5004.3     .05       0    5035     .07       0
  5176.1     .05       0
Bank Sta=4993.2,5004.3
XS Rating Curve= 0 ,0
Exp/Cntr=0.3,0.1

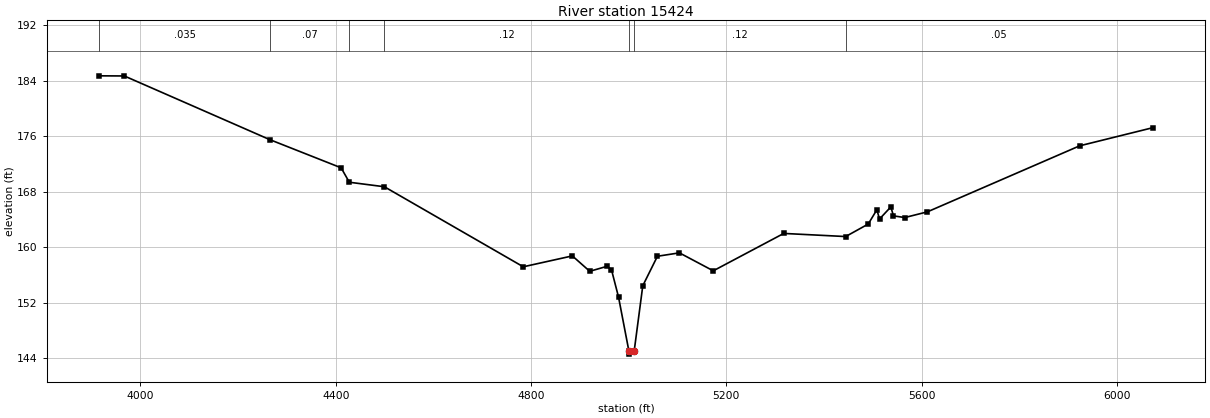
Type RM Length L Ch R = 1 ,15424   ,240,240,240
BEGIN DESCRIPTION:
Mapping XS 97f829cd
END DESCRIPTION:
XS GIS Cut Line= 3
       2514077.3     13464432.59      2513181.44     13463807.58
      2512209.64     13463370.26
#Sta/Elev= 30
  3915.7   184.7  3966.9  184.68  4264.6  175.51    4411  171.44  4427.8  169.36
  4499.6  168.71  4784.2  157.17  4884.7  158.74  4920.4  156.52  4956.2  157.25
  4964.9  156.74  4979.3  152.81  5000.4  145.08  5000.9  144.58  5011.5  145.08
    5029  154.44    5059  158.69    5104  159.18  5173.4  156.59  5317.8  161.98
  5444.6  161.53  5490.8  163.33  5508.5  165.39    5514  164.06  5537.1   165.8
  5542.6  164.51  5565.7  164.27    5612  165.09    5924  174.61  6073.7  177.22
#Mann= 7 ,-1 , 0
  3915.7    .035       0  4264.6     .07       0  4427.8    .035       0
  4499.6     .12       0  5000.4     .05       0  5011.5     .12       0
  5444.6     .05       0
Bank Sta=5000.4,5011.5
XS Rating Curve= 0 ,0
Exp/Cntr=0.3,0.1