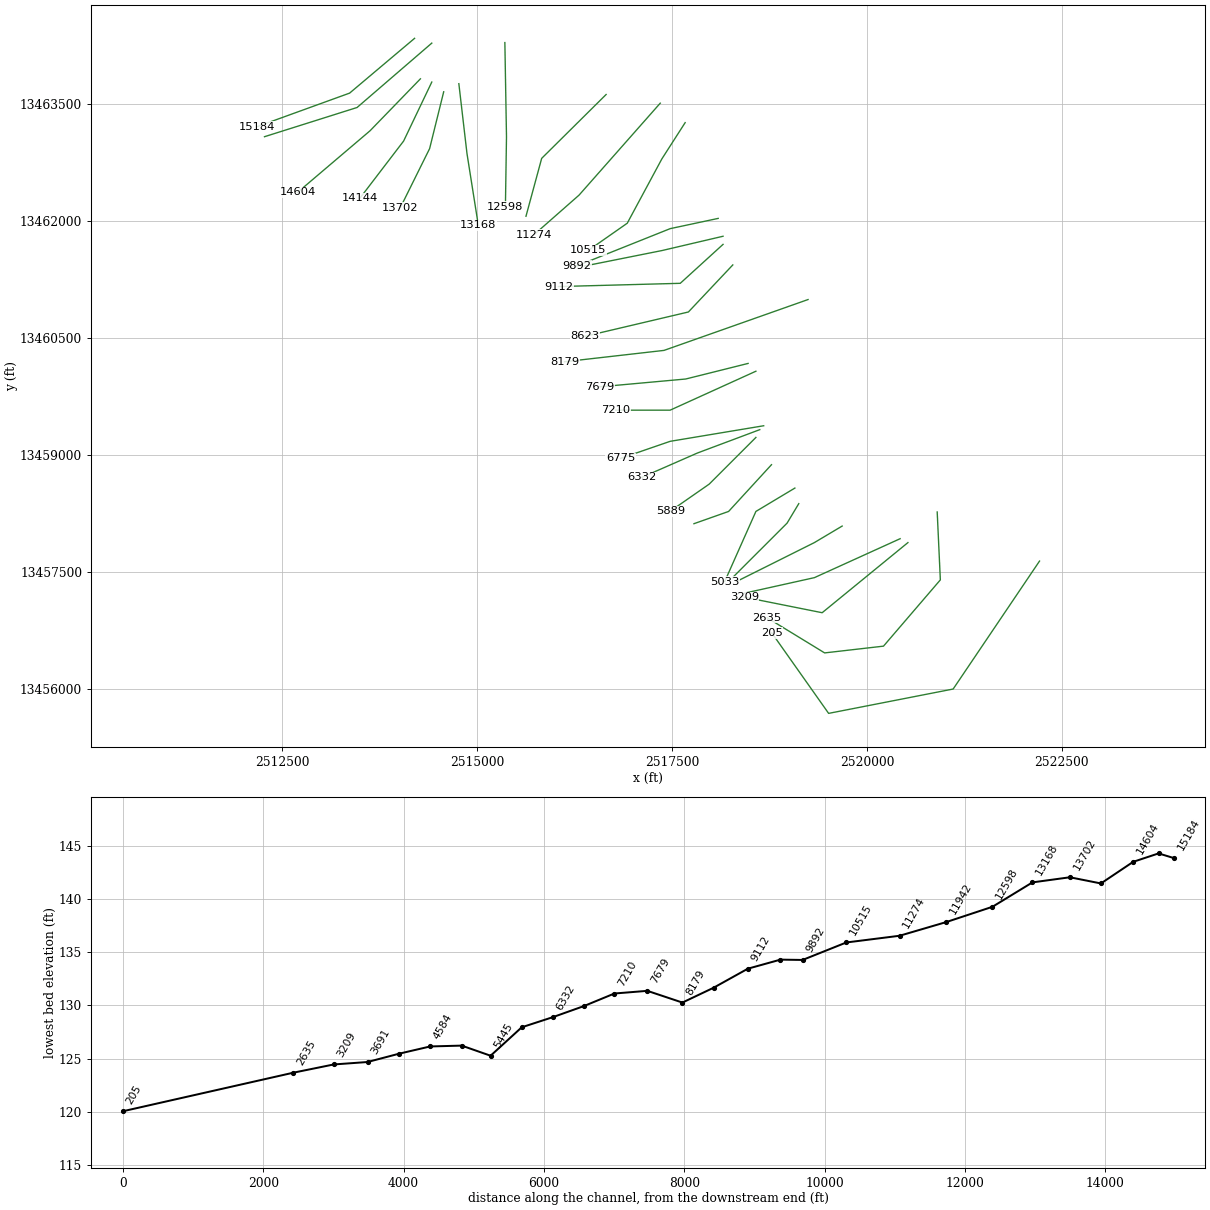
HEC-RAS study KILGORE CREEK.prj: KILGORE CREEK Base Level Engineering

--- KILGORE CREEK.g01 (geometry) --- (continued)

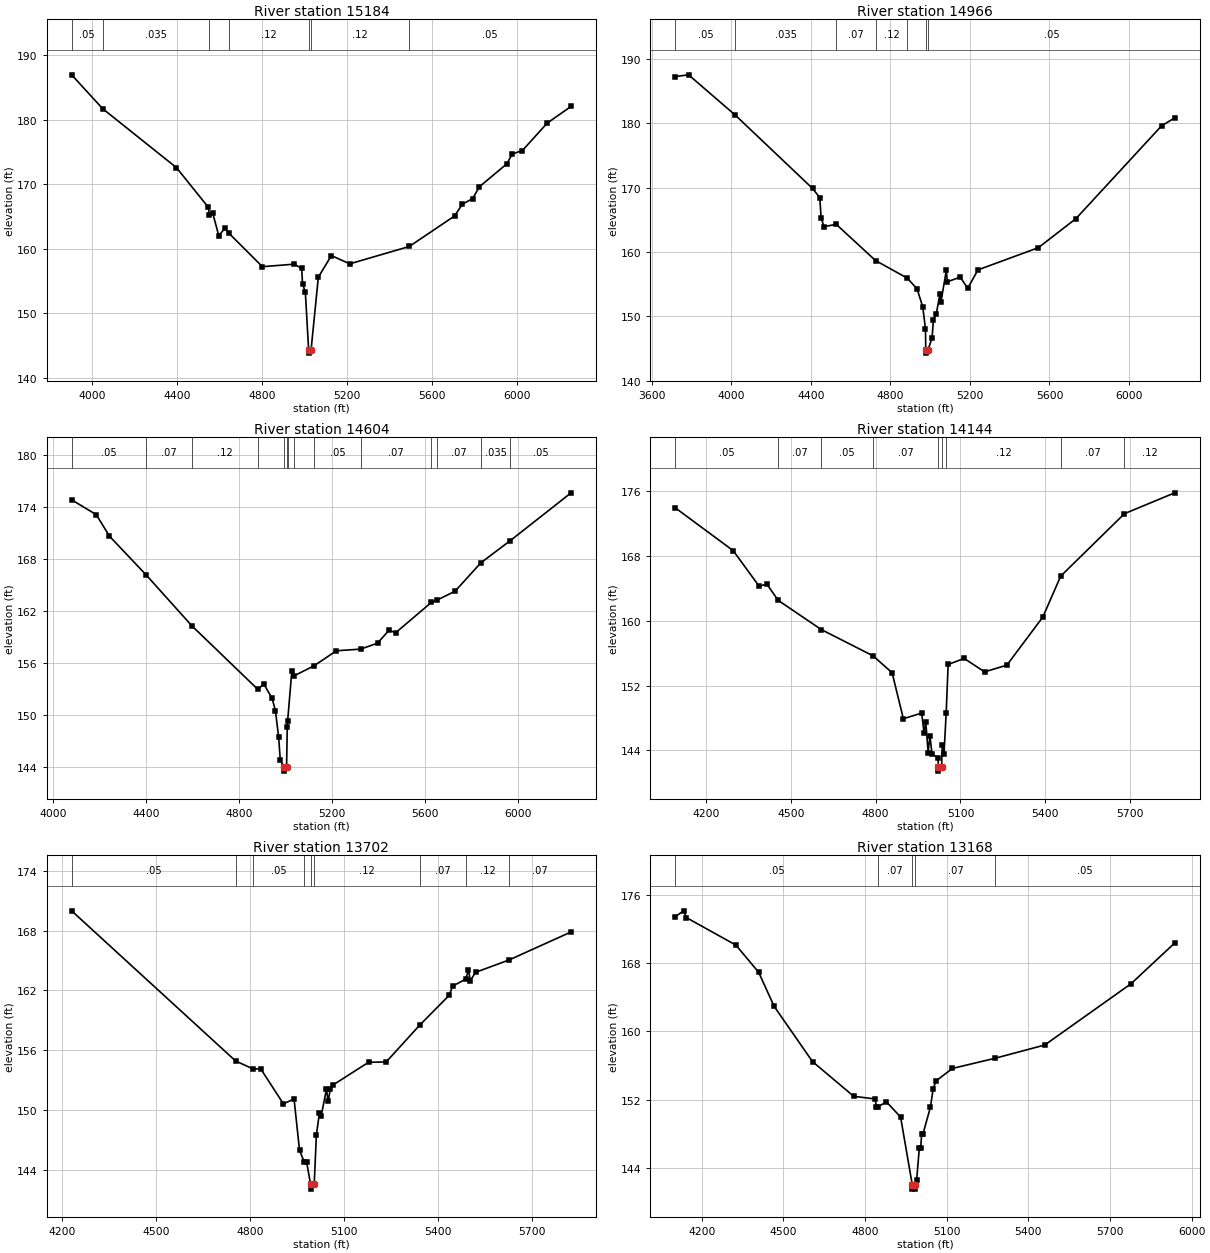
Type RM Length L Ch R = 1 ,15184   ,218,218,218
BEGIN DESCRIPTION:
Mapping XS 24b39622
END DESCRIPTION:
XS GIS Cut Line= 3
      2514196.99     13464348.12      2513363.64     13463644.98
      2512179.37     13463215.51
#Sta/Elev= 30
  3903.2  186.97  4049.1  181.72  4396.5  172.58    4546  166.45  4551.6  165.26
  4566.8  165.56  4595.4  162.05    4624  163.15  4643.1  162.42  4800.9  157.23
  4950.4  157.62  4985.5  156.97  4989.7   154.6  5002.8  153.27  5018.3  144.33
  5018.8  143.83  5029.7  144.33    5064  155.61  5125.3  158.95  5211.8  157.67
  5491.8  160.36  5704.8  165.09  5741.8  166.92  5789.9  167.78  5821.8  169.62
  5950.8  173.17  5976.1   174.7  6023.9  175.23  6140.9  179.49  6253.3  182.08
#Mann= 7 ,-1 , 0
  3903.2     .05       0  4049.1    .035       0  4551.6     .07       0
  4643.1     .12       0  5018.3     .05       0  5029.7     .12       0
  5491.8     .05       0
Bank Sta=5018.3,5029.7
XS Rating Curve= 0 ,0
Exp/Cntr=0.3,0.1

Type RM Length L Ch R = 1 ,14966   ,362,362,362
BEGIN DESCRIPTION:
Mapping XS 8a8281df
END DESCRIPTION:
XS GIS Cut Line= 3
      2514417.53     13464286.72      2513459.22     13463460.35
      2512271.72     13463085.35
#Sta/Elev= 30
  3718.9  187.27    3786  187.54  4021.5  181.25  4409.2  169.87  4445.4  168.45
    4452  165.34  4466.2  163.94  4528.3  164.29  4725.5  158.67  4886.3  155.91
  4934.7  154.24  4963.2  151.43  4976.7  148.05  4978.1  144.77  4978.6  144.27
  4989.5  144.77  5009.7  146.62  5016.8  149.47  5030.7  150.32  5049.1  153.42
  5054.4  152.22  5081.5  157.13  5086.7  155.36  5151.4  156.09    5189  154.34
  5240.4  157.21  5544.5  160.67  5733.3  165.19  6163.2   179.6  6229.6  180.85
#Mann= 7 ,-1 , 0
  3718.9     .05       0  4021.5    .035       0  4528.3     .07       0
  4725.5     .12       0  4886.3     .05       0  4978.1     .05       0
  4989.5     .05       0
Bank Sta=4978.1,4989.5
XS Rating Curve= 0 ,0
Exp/Cntr=0.3,0.1

Type RM Length L Ch R = 1 ,14604   ,460,460,460
BEGIN DESCRIPTION:
Mapping XS c3e1ac3b
END DESCRIPTION:
XS GIS Cut Line= 3
      2514271.69     13463828.37      2513625.89     13463161.74
      2512695.33     13462370.07
#Sta/Elev= 30
  4080.4  174.81  4186.5   173.1  4243.1  170.62  4401.7  166.12  4598.3  160.25
  4880.7  152.95  4907.8  153.52  4943.3  151.89  4957.4  150.47  4971.5  147.39
  4978.5  144.73  4994.1  143.98  4994.6  143.48  5005.6  143.98  5008.5  148.55
    5010  149.23    5028  155.01  5036.1  154.46  5124.8  155.66  5219.8  157.38
  5324.6  157.57    5397  158.26  5446.4  159.74    5475  159.46  5628.5  162.96
  5653.1  163.23  5730.9  164.26  5841.5  167.53    5968  170.09  6230.3  175.62
#Mann= 14 ,-1 , 0
  4080.4     .05       0  4401.7     .07       0  4598.3     .12       0
  4880.7     .07       0  4994.1     .05       0  5005.6     .07       0
    5010     .05       0  5036.1     .07       0  5124.8     .05       0
  5324.6     .07       0  5628.5     .05       0  5653.1     .07       0
  5841.5    .035       0    5968     .05       0
Bank Sta=4994.1,5005.6
XS Rating Curve= 0 ,0
Exp/Cntr=0.3,0.1

Type RM Length L Ch R = 1 ,14144   ,442,442,442
BEGIN DESCRIPTION:
Mapping XS c689c63b
END DESCRIPTION:
XS GIS Cut Line= 3
      2514417.53      13463786.7      2514056.44      13463029.8
      2513493.91     13462293.65
#Sta/Elev= 30
    4092  173.92  4297.1  168.63  4387.8  164.28  4416.1   164.5  4455.4  162.52
    4608  158.91  4791.4  155.66  4858.4  153.58  4898.1  147.91  4962.9  148.61
  4971.1  146.19  4977.4  147.51  4985.7  143.73    4992  145.77  4999.6  143.53
    5021   143.1  5021.5  141.95    5022  141.45  5033.1  141.95  5035.6  144.68
  5041.8  143.61  5049.4  148.57  5056.4   154.6  5112.9  155.35  5185.2  153.69
  5263.9  154.52    5391  160.45  5454.2   165.5  5679.5   173.2  5857.1  175.77
#Mann= 9 ,-1 , 0
    4092     .05       0  4455.4     .07       0    4608     .05       0
  4791.4     .07       0  5021.5     .05       0  5033.1     .07       0
  5049.4     .12       0  5454.2     .07       0  5679.5     .12       0
Bank Sta=5021.5,5033.1
XS Rating Curve= 0 ,0
Exp/Cntr=0.3,0.1

Type RM Length L Ch R = 1 ,13702   ,534,534,534
BEGIN DESCRIPTION:
Mapping XS 0e2aca4a
END DESCRIPTION:
XS GIS Cut Line= 3
      2514570.34     13463661.78      2514389.78     13462932.58
      2514014.76      13462175.6
#Sta/Elev= 30
    4230  169.99  4753.8  154.91  4808.5  154.12  4834.5   154.1  4906.6   150.6
  4940.7  151.09  4958.1  145.95  4973.2  144.75  4980.8  144.76  4993.4  142.53
  4993.9  142.03  5005.1  142.53    5012  147.45  5021.7  149.69  5027.3  149.36
  5044.1  152.06  5049.7  150.84  5056.6  152.12  5066.5  152.52  5178.6  154.77
  5235.2  154.81    5342   158.5  5436.5   161.5  5447.2  162.43  5489.3  163.12
  5498.1  164.07  5503.7  162.97  5520.6  163.81  5628.2  165.06    5826  167.87
#Mann= 9 ,-1 , 0
    4230     .05       0  4753.8     .07       0  4808.5     .05       0
  4973.2     .12       0  4993.4     .05       0  5005.1     .12       0
    5342     .07       0  5489.3     .12       0  5628.2     .07       0
Bank Sta=4993.4,5005.1
XS Rating Curve= 0 ,0
Exp/Cntr=0.3,0.1

Type RM Length L Ch R = 1 ,13168   ,570,570,570
BEGIN DESCRIPTION:
Mapping XS 516bdff9
END DESCRIPTION:
XS GIS Cut Line= 3
      2514764.77     13463765.94      2514868.94     13462870.08
       2515014.5     13461948.19
#Sta/Elev= 30
  4102.6  173.43  4133.7  174.11  4143.3  173.32  4325.5   170.1  4409.1  166.92
    4466  162.93  4606.9  156.47  4758.4  152.41    4837   152.1    4842  151.15
  4846.4  151.17  4878.7  151.76  4930.6  149.98  4973.5  142.05    4974  141.55
  4984.8  141.55  4985.3  142.05  4989.5   142.6  4999.5   146.4  5004.5   146.4
  5007.9  147.98    5013  148.03    5040  151.12  5050.1  153.24  5060.3   154.2
    5121  155.67  5278.9  156.87  5460.1  158.41  5777.3  165.58  5937.8  170.35
#Mann= 5 ,-1 , 0
  4102.6     .05       0  4846.4     .07       0  4973.5     .05       0
  4985.3     .07       0  5278.9     .05       0
Bank Sta=4973.5,4985.3
XS Rating Curve= 0 ,0
Exp/Cntr=0.3,0.1

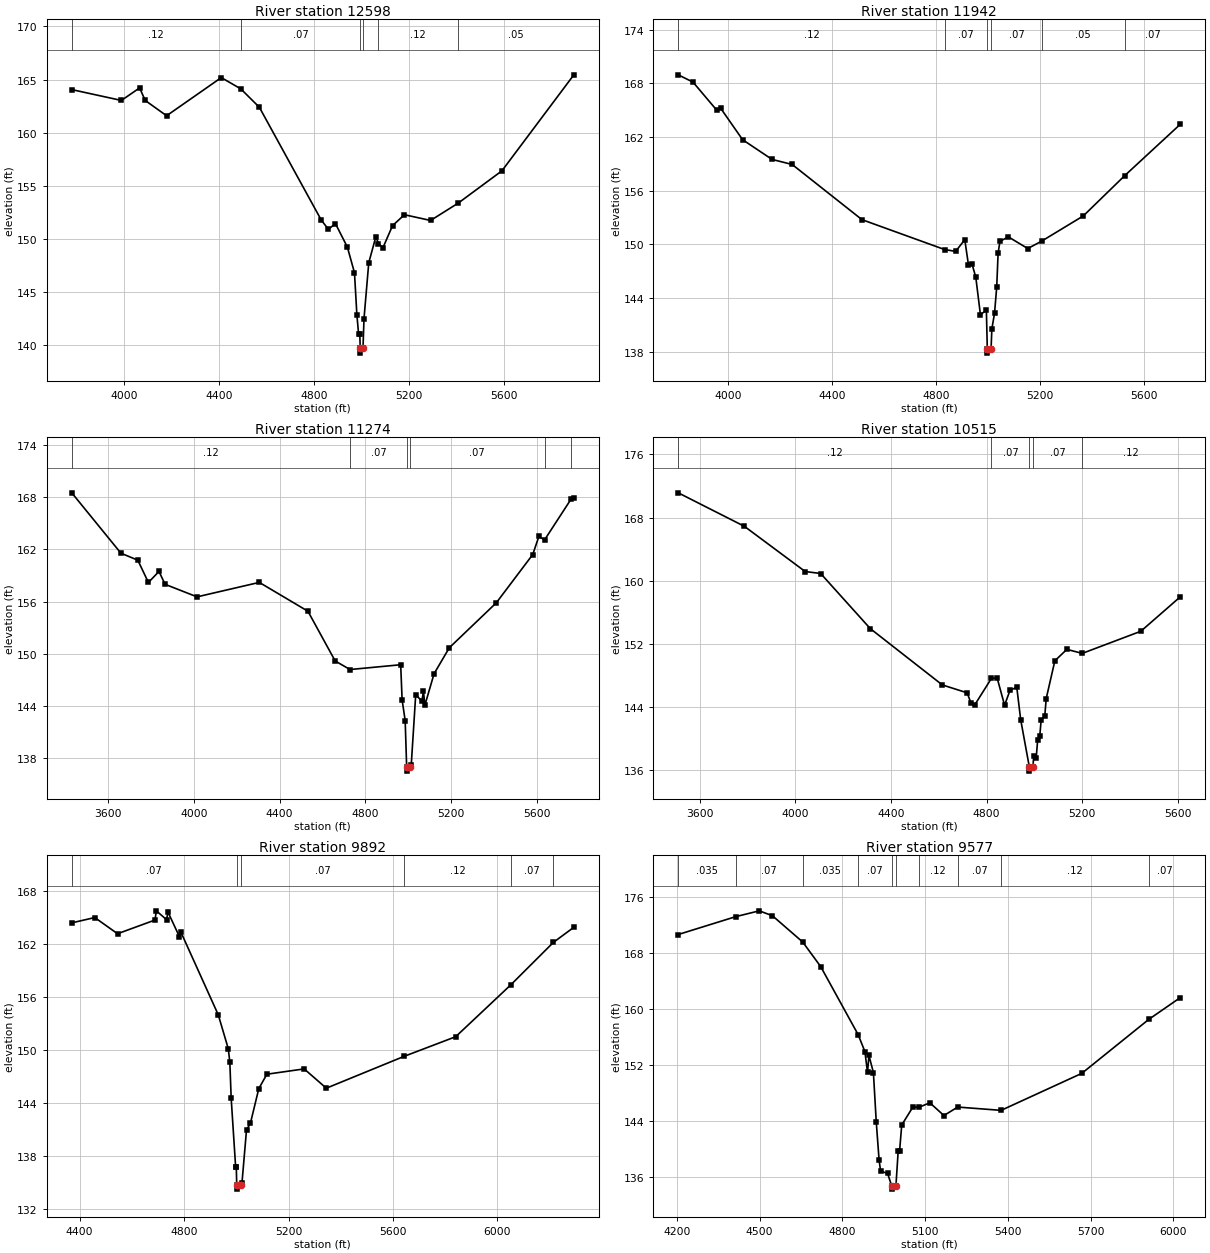
Type RM Length L Ch R = 1 ,12598   ,656,656,656
BEGIN DESCRIPTION:
Mapping XS eec5a480
END DESCRIPTION:
XS GIS Cut Line= 3
      2515355.05     13464293.71      2515375.89     13463085.35
        2515362.      13462182.6
#Sta/Elev= 30
  3781.1  164.05  3989.8  163.03  4066.4  164.21  4089.9  163.03  4179.9  161.59
  4409.9  165.18  4491.8  164.12  4569.9  162.39    4830  151.79    4860  150.91
    4890  151.44    4940  149.24    4970  146.82    4980  142.89  4987.3  141.06
  4992.3  141.06  4994.1  139.76  4994.6  139.26  5005.9  139.76    5010  142.49
    5030  147.76    5060  150.22    5071  149.55    5090  149.19    5130  151.25
    5180  152.28    5290  151.74  5406.1  153.37  5590.1  156.41  5892.5  165.44
#Mann= 6 ,-1 , 0
  3781.1     .12       0  4491.8     .07       0  4994.1     .05       0
  5005.9     .07       0    5071     .12       0  5406.1     .05       0
Bank Sta=4994.1,5005.9
XS Rating Curve= 0 ,0
Exp/Cntr=0.3,0.1

Type RM Length L Ch R = 1 ,11942   ,668,668,668
BEGIN DESCRIPTION:
Mapping XS 2bf8d2f1
END DESCRIPTION:
XS GIS Cut Line= 3
      2516653.69     13463627.04      2515827.28     13462807.58
      2515625.88     13462064.51
#Sta/Elev= 30
  3807.4  168.96  3864.5  168.14  3956.4  164.98  3970.6  165.23  4055.4   161.7
  4168.6   159.5  4246.3  158.93    4515  152.76    4833  149.42  4875.7  149.21
    4911  150.52  4925.2  147.69  4939.3  147.75  4953.4  146.32  4971.2  142.14
  4994.2  142.62  4997.7  138.33  4998.2  137.83  5012.3  138.33  5015.3  140.54
  5025.7  142.31  5034.1  145.28  5039.3  148.99  5046.4  150.34  5079.1  150.83
  5153.6  149.53  5206.7  150.35  5367.6  153.18  5527.2  157.69  5741.1  163.43
#Mann= 6 ,-1 , 0
  3807.4     .12       0    4833     .07       0  4997.7     .05       0
  5012.3     .07       0  5206.7     .05       0  5527.2     .07       0
Bank Sta=4997.7,5012.3
XS Rating Curve= 0 ,0
Exp/Cntr=0.3,0.1

Type RM Length L Ch R = 1 ,11274   ,759,759,759
BEGIN DESCRIPTION:
Mapping XS f1ffbb94
END DESCRIPTION:
XS GIS Cut Line= 3
      2517348.11     13463515.91      2516306.44     13462335.35
      2515730.97     13461829.21
#Sta/Elev= 30
  3431.4  168.48  3660.6  161.55  3739.3  160.75  3788.7  158.19    3838  159.46
  3866.4  157.98  4015.4  156.54  4305.7   158.2  4532.4  154.89  4659.5  149.18
  4728.9   148.2  4964.9  148.75  4971.6  144.69  4985.8  142.35  4992.7  137.04
  4993.2  136.54  5007.4  137.04  5014.2  137.28    5035  145.33  5063.5  144.56
  5071.1  145.69  5077.7   144.1  5120.4  147.71  5191.6   150.7  5410.8  155.86
  5580.6   161.4  5609.1  163.47    5636  163.09  5759.3  167.76  5772.2  167.84
#Mann= 6 ,-1 , 0
  3431.4     .12       0  4728.9     .07       0  4992.7     .05       0
  5007.4     .07       0    5636    .035       0  5759.3     .07       0
Bank Sta=4992.7,5007.4
XS Rating Curve= 0 ,0
Exp/Cntr=0.3,0.1

Type RM Length L Ch R = 1 ,10515   ,623,623,623
BEGIN DESCRIPTION:
KILGORE CREEK 17.0
END DESCRIPTION:
XS GIS Cut Line= 4
      2517667.56     13463265.91      2517368.94     13462800.63
        2516925.       13461975.      2516425.01     13461625.01
#Sta/Elev= 30
  3509.7  171.13  3786.5  166.89  4040.8  161.17  4105.6  160.92  4313.4  153.94
  4614.5  146.82  4718.4  145.82  4734.6  144.52  4750.2  144.29  4820.1  147.65
  4844.2  147.67  4875.1  144.25  4897.8  146.14  4926.1  146.52  4942.4  142.43
  4978.8  136.41  4979.3  135.91  4993.5  136.41  4997.1  137.83  5007.4  137.61
  5013.5  139.85  5022.2  140.34  5028.3  142.43  5043.1  142.84  5049.2  145.09
  5085.4  149.87  5135.6  151.32    5200  150.81  5445.1  153.61  5610.3  157.97
#Mann= 5 ,-1 , 0
  3509.7     .12       0  4820.1     .07       0  4978.8     .05       0
  4993.5     .07       0    5200     .12       0
Bank Sta=4978.8,4993.5
XS Rating Curve= 0 ,0
Exp/Cntr=0.3,0.1

Type RM Length L Ch R = 1 ,9892    ,315,315,315
BEGIN DESCRIPTION:
KILGORE CREEK 16.0
END DESCRIPTION:
XS GIS Cut Line= 3
      2518091.12     13462036.73      2517475.05     13461905.02
      2516274.99       13461425.
#Sta/Elev= 30
    4370  164.37  4458.1  164.97  4545.3  163.14  4688.7  164.69  4693.8  165.73
    4733  164.73  4738.2   165.6  4782.5  162.79  4787.6  163.34    4931  153.97
  4969.4  150.13  4975.3  148.59  4980.4  144.53  4997.5  136.76    5000  136.76
  5001.6  134.77  5002.1  134.27  5017.3  134.77  5021.6  134.92  5039.1  140.97
  5053.9   141.7  5086.2  145.64  5117.2  147.26  5259.9  147.86  5344.7  145.68
  5642.6  149.28  5840.1   151.5  6051.4  157.37  6214.1  162.16  6292.5  163.87
#Mann= 6 ,-1 , 0
    4370     .07       0  5001.6     .05       0  5017.3     .07       0
  5642.6     .12       0  6051.4     .07       0  6214.1     .12       0
Bank Sta=5001.6,5017.3
XS Rating Curve= 0 ,0
Exp/Cntr=0.3,0.1

Type RM Length L Ch R = 1 ,9577    ,465,465,465
BEGIN DESCRIPTION:
KILGORE CREEK 15.0
END DESCRIPTION:
XS GIS Cut Line= 3
      2518153.65     13461807.57        2517375.       13461625.
      2516374.97     13461424.99
#Sta/Elev= 30
  4205.2  170.63  4413.6  173.18  4498.9  174.01  4546.5  173.31  4656.3  169.56
  4721.4  166.06  4857.1  156.35  4881.7  153.93  4891.2  150.95  4896.3  153.37
  4912.5  150.94  4922.8  143.92  4933.1  138.46  4938.7  136.85  4963.9  136.56
  4978.4   134.8  4978.9   134.3  4994.2   134.8  5002.4   139.8  5007.5   139.8
  5015.2  143.45    5056  146.04  5076.5  145.96  5117.1  146.62  5168.1   144.8
    5218  146.01  5375.3  145.54  5667.8  150.82  5910.9  158.53  6024.8  161.63
#Mann= 10 ,-1 , 0
  4205.2    .035       0  4413.6     .07       0  4656.3    .035       0
  4857.1     .07       0  4978.4     .05       0  4994.2     .07       0
  5076.5     .12       0    5218     .07       0  5375.3     .12       0
  5910.9     .07       0
Bank Sta=4978.4,4994.2
XS Rating Curve= 0 ,0
Exp/Cntr=0.3,0.1

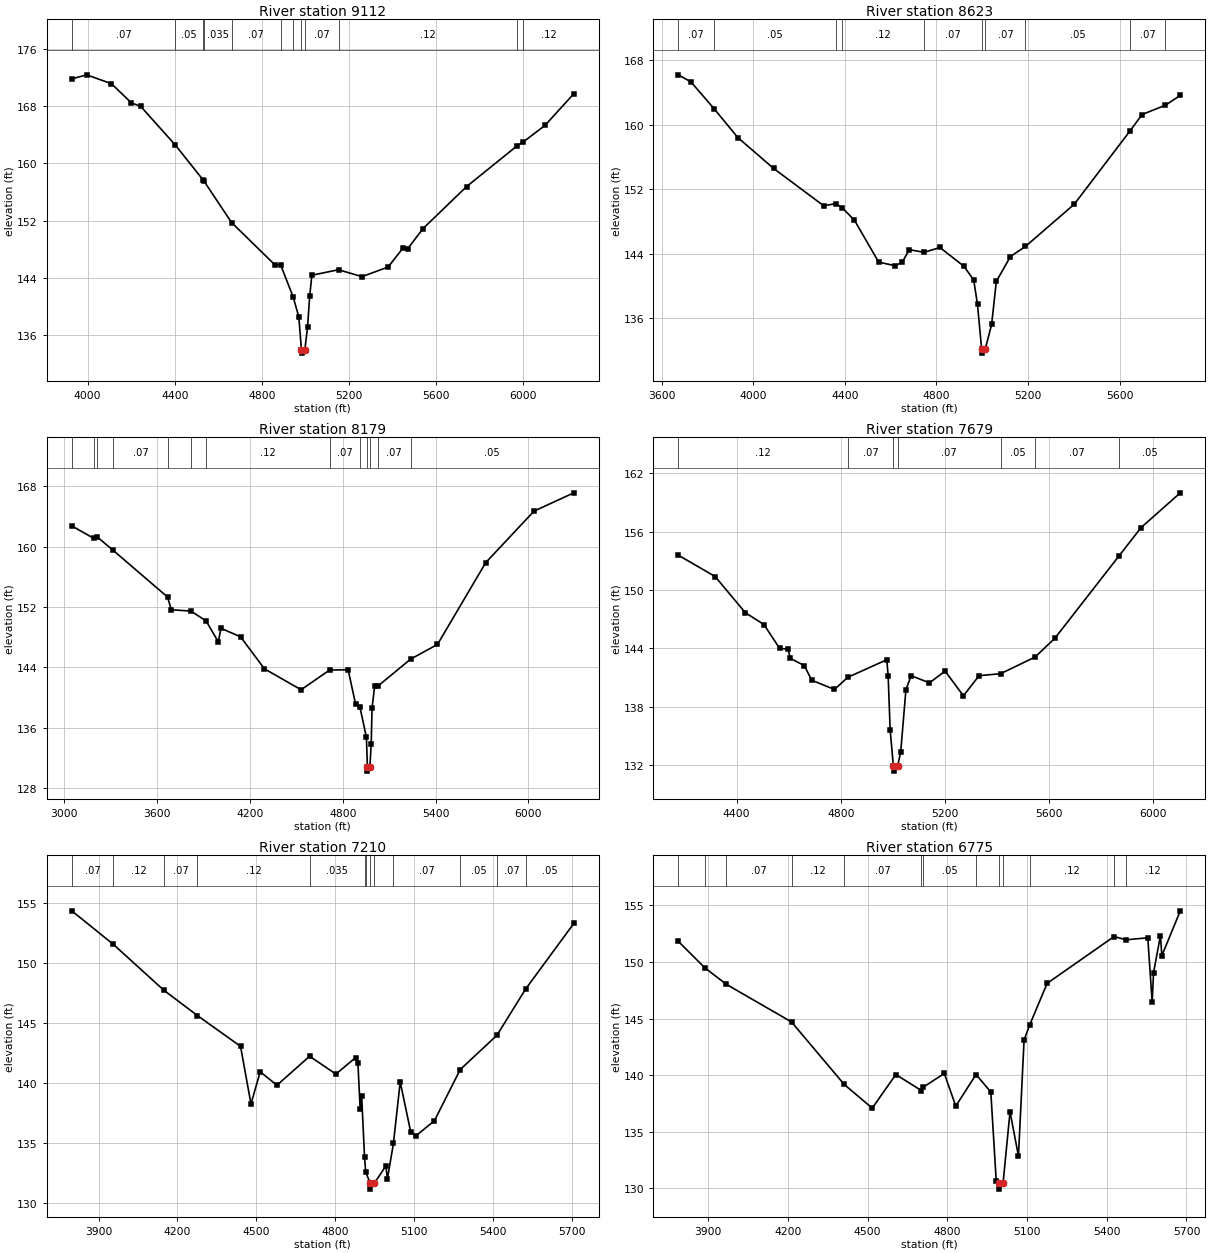
Type RM Length L Ch R = 1 ,9112    ,489,489,489
BEGIN DESCRIPTION:
Mapping XS 19625db8
END DESCRIPTION:
XS GIS Cut Line= 3
      2518153.63     13461703.38      2517605.05     13461203.41
      2516042.54     13461161.74
#Sta/Elev= 30
  3927.3  171.82  3995.8  172.39  4109.3  171.15  4201.2  168.46  4243.7  167.98
  4401.8   162.6  4531.4  157.64  4533.2  157.57  4661.1  151.72  4859.7  145.81
  4886.5  145.79  4943.3  141.35  4969.7  138.54  4981.8  133.95  4982.3  133.45
  4997.6  133.95  5009.7  137.05  5019.7  141.41  5029.7  144.35  5152.3  145.12
  5259.8  144.15  5379.8   145.5  5449.9  148.22  5469.9  148.06  5539.9  150.87
    5740  156.75    5973  162.48  6000.4     163  6100.1  165.31  6232.6  169.75
#Mann= 12 ,-1 , 0
  3927.3     .07       0  4401.8     .05       0  4531.4     .07       0
  4533.2    .035       0  4661.1     .07       0  4886.5     .12       0
  4943.3     .07       0  4981.8     .05       0  4997.6     .07       0
  5152.3     .12       0    5973     .07       0  6000.4     .12       0
Bank Sta=4981.8,4997.6
XS Rating Curve= 0 ,0
Exp/Cntr=0.3,0.1

Type RM Length L Ch R = 1 ,8623    ,444,444,444
BEGIN DESCRIPTION:
Mapping XS ebc5471b
END DESCRIPTION:
XS GIS Cut Line= 3
      2518278.64     13461439.49      2517709.22     13460835.35
      2516382.83     13460522.85
#Sta/Elev= 30
  3672.3  166.17  3727.6   165.3  3829.1  161.96  3932.7  158.39  4088.5  154.57
  4307.8  149.93  4360.2   150.2  4389.3  149.66  4442.1  148.13  4547.9  142.94
  4619.8   142.5  4650.7  142.94  4681.5  144.49  4746.6  144.16    4815  144.76
  4920.6  142.42    4963  140.71  4979.4  137.69  4997.4  132.16  4997.9  131.66
  5013.3  132.16  5041.1  135.23  5061.6  140.55  5123.3  143.64  5188.8  144.89
  5401.9  150.12  5644.9  159.19  5698.3  161.25  5800.3   162.4  5865.2  163.62
#Mann= 10 ,-1 , 0
  3672.3     .07       0  3829.1     .05       0  4360.2    .035       0
  4389.3     .12       0  4746.6     .07       0  4997.4     .05       0
  5013.3     .07       0  5188.8     .05       0  5644.9     .07       0
  5800.3     .05       0
Bank Sta=4997.4,5013.3
XS Rating Curve= 0 ,0
Exp/Cntr=0.3,0.1

Type RM Length L Ch R = 1 ,8179    ,500,500,500
BEGIN DESCRIPTION:
Mapping XS f060c9ce
END DESCRIPTION:
XS GIS Cut Line= 3
      2519243.91     13460995.06      2517396.72      13460342.3
      2516119.45     13460196.52
#Sta/Elev= 30
  3048.8  162.73  3192.3  161.07  3214.8  161.24  3315.6  159.51    3668  153.31
  3691.8  151.63  3818.1  151.46  3916.7  150.16  3995.6  147.39  4012.8  149.18
  4139.6  148.05  4294.2  143.81  4530.9  141.04  4714.8  143.65  4834.8  143.69
  4882.5  139.18  4911.4   138.7  4953.1  134.73  4959.4  130.77  4959.9  130.27
  4975.3  130.77    4984  133.92  4989.3  138.61  5006.2  141.52    5025  141.49
    5239   145.1  5412.3  147.04  5724.3  157.88  6036.3  164.69  6293.5  167.11
#Mann= 13 ,-1 , 0
  3048.8     .07       0  3192.3     .12       0  3214.8     .05       0
  3315.6     .07       0    3668     .12       0  3818.1     .07       0
  3916.7     .12       0  4714.8     .07       0  4911.4     .05       0
  4959.4     .05       0  4975.3     .05       0    5025     .07       0
    5239     .05       0
Bank Sta=4959.4,4975.3
XS Rating Curve= 0 ,0
Exp/Cntr=0.3,0.1

Type RM Length L Ch R = 1 ,7679    ,469,469,469
BEGIN DESCRIPTION:
KILGORE CREEK 12.0
END DESCRIPTION:
XS GIS Cut Line= 3
      2518474.98     13460174.99        2517675.       13459975.
      2516575.04       13459875.
#Sta/Elev= 30
  4175.5  153.59  4317.2  151.39  4433.2  147.67  4505.3  146.44  4564.6  144.01
  4598.1   143.9  4605.8  142.97  4659.9  142.23  4688.3  140.72  4775.9  139.77
  4826.9  141.02  4976.9  142.83  4982.1  141.14  4989.8  135.59  5002.2  131.87
  5002.7  131.37  5018.1  131.87  5030.2  133.31  5050.3  139.75  5070.4  141.19
  5140.7  140.45  5200.9  141.66  5271.2  139.12  5331.5  141.19  5413.9  141.39
  5546.7  143.11  5622.7  145.04  5869.1  153.51    5954  156.43  6104.6     160
#Mann= 7 ,-1 , 0
  4175.5     .12       0  4826.9     .07       0  5002.2     .05       0
  5018.1     .07       0  5413.9     .05       0  5546.7     .07       0
  5869.1     .05       0
Bank Sta=5002.2,5018.1
XS Rating Curve= 0 ,0
Exp/Cntr=0.3,0.1

Type RM Length L Ch R = 1 ,7210    ,435,435,435
BEGIN DESCRIPTION:
KILGORE CREEK 11.0
END DESCRIPTION:
XS GIS Cut Line= 3
      2518575.03     13460075.01        2517475.       13459575.
      2516775.03       13459575.
#Sta/Elev= 30
  3798.4  154.37  3956.2  151.57  4148.7  147.73    4276  145.62  4439.9  143.05
  4479.5  138.24  4514.6  140.92  4578.3   139.8  4702.4  142.22  4802.4  140.73
  4877.1  142.11  4885.9  141.65  4894.7  137.79  4900.2  138.91  4911.1  133.81
  4915.6  132.53  4932.9  131.62  4933.4  131.12  4948.8  131.62  4992.5  133.07
  4997.9  131.95    5021  134.94  5046.7  140.08  5086.7  135.89  5106.7  135.58
  5176.7  136.83  5274.8  141.11  5414.2  143.97  5524.2  147.86  5706.7  153.32
#Mann= 13 ,-1 , 0
  3798.4     .07       0  3956.2     .12       0  4148.7     .07       0
    4276     .12       0  4702.4    .035       0  4911.1     .12       0
  4915.6     .05       0  4932.9     .05       0  4948.8     .05       0
    5021     .07       0  5274.8     .05       0  5414.2     .07       0
  5524.2     .05       0
Bank Sta=4932.9,4948.8
XS Rating Curve= 0 ,0
Exp/Cntr=0.3,0.1

Type RM Length L Ch R = 1 ,6775    ,443,443,443
BEGIN DESCRIPTION:
KILGORE CREEK 10.0
END DESCRIPTION:
XS GIS Cut Line= 3
      2518674.97       13459375.        2517475.       13459175.
      2516839.31     13458955.63
#Sta/Elev= 30
  3787.9  151.82  3888.4  149.47    3969  148.02  4214.1   144.7  4412.4  139.18
  4517.8  137.09  4606.5  140.06  4702.9  138.64  4708.8  138.93    4789  140.15
  4832.1  137.27  4908.3  140.06  4963.9  138.52  4984.2   130.7  4993.8  130.44
  4994.3  129.94  5009.9  130.44  5036.2  136.77  5067.9  132.86  5089.1  143.11
  5110.6  144.46    5176  148.11  5427.7  152.24  5472.9  151.95  5554.5  152.13
    5571  146.44  5576.2  149.05  5602.2  152.33  5607.4  150.55  5676.9  154.51
#Mann= 13 ,-1 , 0
  3787.9     .07       0  3888.4     .12       0    3969     .07       0
  4214.1     .12       0  4412.4     .07       0  4702.9     .12       0
  4708.8     .05       0  4908.3     .12       0  4993.8     .05       0
  5009.9     .12       0  5110.6     .12       0  5427.7     .07       0
  5472.9     .12       0
Bank Sta=4993.8,5009.9
XS Rating Curve= 0 ,0
Exp/Cntr=0.3,0.1

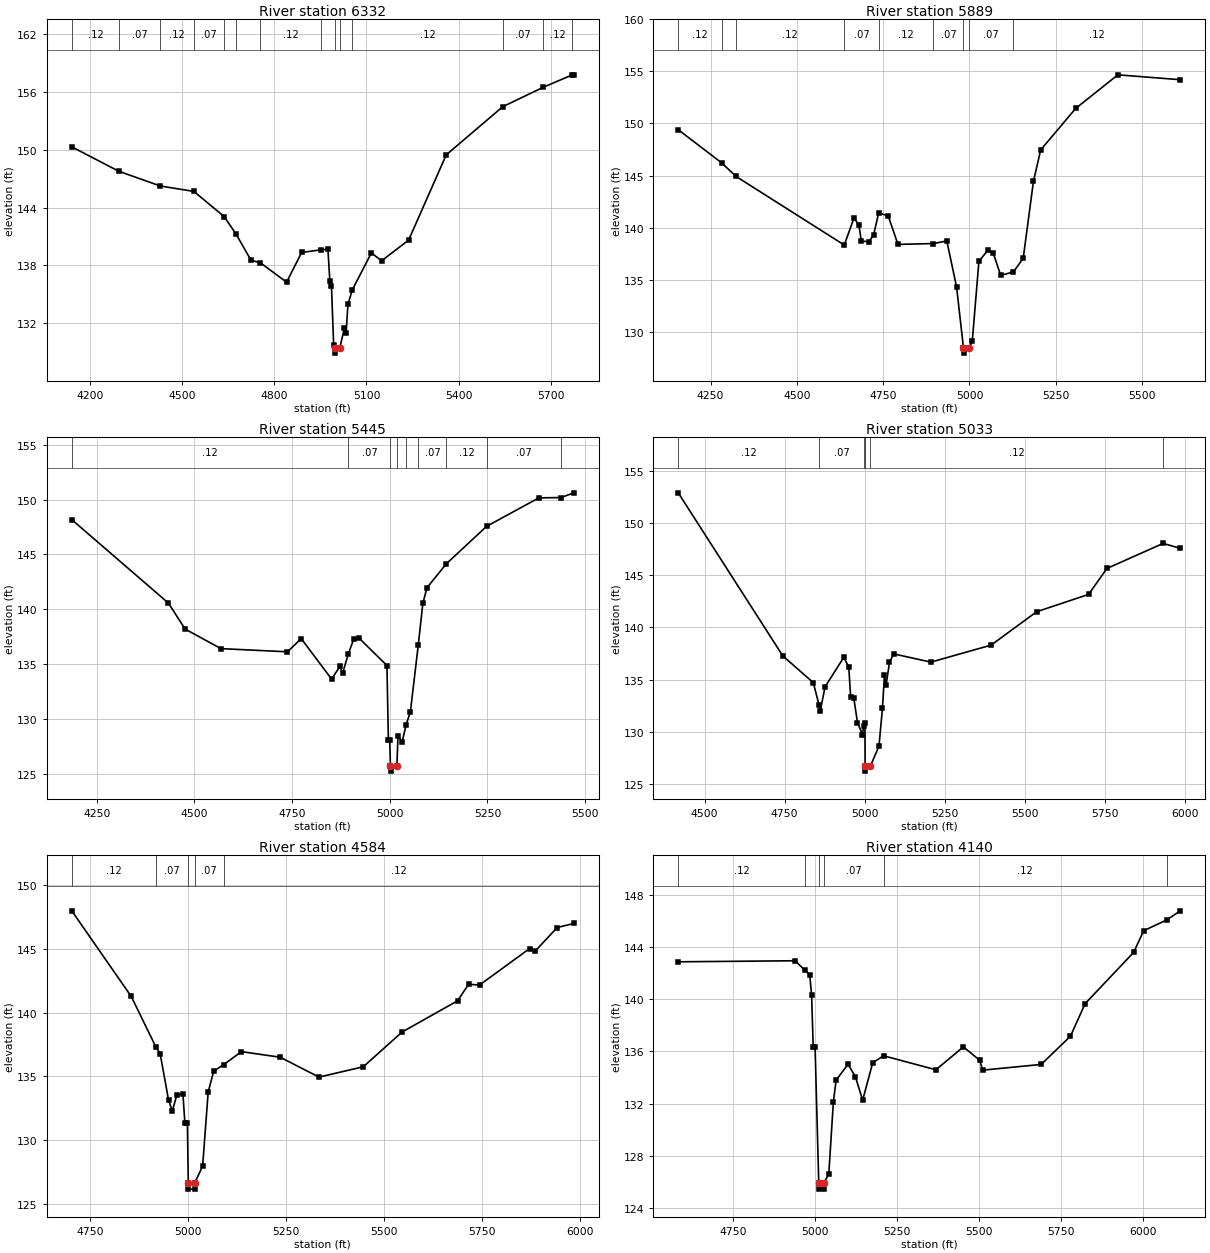
Type RM Length L Ch R = 1 ,6332    ,443,443,443
BEGIN DESCRIPTION:
KILGORE CREEK 9.0
END DESCRIPTION:
XS GIS Cut Line= 3
      2518624.99       13459325.        2517825.       13459025.
      2517112.14     13458712.36
#Sta/Elev= 30
  4141.7  150.29  4295.3  147.75  4429.9  146.23  4538.8  145.67  4637.6  143.05
  4676.2  141.23  4724.6  138.53    4755  138.27  4840.3  136.26  4889.3  139.34
  4953.5  139.62  4974.7  139.68    4981  136.38  4986.3  135.81  4993.4  129.75
    4997   129.4  4997.5   128.9  5013.1   129.4  5028.4  131.51  5033.9  130.95
  5039.8  133.96  5054.3  135.48  5116.2   139.3    5149  138.47  5237.2  140.62
  5359.5  149.46    5543  154.45  5673.8  156.45  5769.5  157.76  5774.5  157.75
#Mann= 14 ,-1 , 0
  4141.7     .12       0  4295.3     .07       0  4429.9     .12       0
  4538.8     .07       0  4637.6     .12       0  4676.2     .07       0
    4755     .12       0  4953.5     .05       0    4997     .05       0
  5013.1     .05       0  5054.3     .12       0    5543     .07       0
  5673.8     .12       0  5769.5     .07       0
Bank Sta=4997,5013.1
XS Rating Curve= 0 ,0
Exp/Cntr=0.3,0.1

Type RM Length L Ch R = 1 ,5889    ,444,444,444
BEGIN DESCRIPTION:
KILGORE CREEK 8.0
END DESCRIPTION:
XS GIS Cut Line= 3
      2518574.99     13459224.99        2517975.       13458625.
      2517477.89     13458279.15
#Sta/Elev= 30
  4156.5   149.4  4282.6  146.21  4323.7  144.92  4637.3  138.33  4665.6  140.93
  4679.7  140.24  4686.8  138.71    4708  138.65  4722.2  139.27    4737  141.42
  4764.6  141.12  4792.9  138.39  4895.6  138.47  4934.3  138.72  4962.6  134.31
  4982.6  128.45  4983.1  127.95  4999.2  128.45  5008.1  129.12  5027.3  136.76
  5054.3  137.88  5069.2  137.52  5090.3  135.42  5127.1  135.74  5155.6  137.05
  5185.3  144.45  5206.2  147.46  5307.5  151.44  5429.7  154.67  5610.6   154.2
#Mann= 9 ,-1 , 0
  4156.5     .12       0  4282.6     .07       0  4323.7     .12       0
  4637.3     .07       0    4737     .12       0  4895.6     .07       0
  4982.6     .05       0  4999.2     .07       0  5127.1     .12       0
Bank Sta=4982.6,4999.2
XS Rating Curve= 0 ,0
Exp/Cntr=0.3,0.1

Type RM Length L Ch R = 1 ,5445    ,412,412,412
BEGIN DESCRIPTION:
KILGORE CREEK 7.0
END DESCRIPTION:
XS GIS Cut Line= 3
      2518775.02     13458875.02        2518225.       13458275.
      2517780.57     13458117.75
#Sta/Elev= 30
  4185.8  148.17  4433.4  140.57  4475.9  138.21  4567.8  136.43    4738  136.14
  4773.2  137.34  4850.9  133.66  4872.4  134.81  4879.2  134.18  4893.7  135.94
  4907.6  137.29  4921.8  137.37  4992.7  134.89  4996.4   128.1  4999.8   128.1
  5001.6  125.78  5002.1  125.28  5018.2  125.78    5021   128.5  5031.6  127.93
  5041.5  129.46  5052.8   130.7    5073  136.79  5084.6  140.55  5095.2  141.97
  5144.7  144.15  5247.9  147.56  5381.6  150.15  5438.5  150.18  5471.2  150.61
#Mann= 9 ,-1 , 0
  4185.8     .12       0  4893.7     .07       0  5001.6     .05       0
  5018.2     .07       0  5041.5     .12       0    5073     .07       0
  5144.7     .12       0  5247.9     .07       0  5438.5     .12       0
Bank Sta=5001.6,5018.2
XS Rating Curve= 0 ,0
Exp/Cntr=0.3,0.1

Type RM Length L Ch R = 1 ,5033    ,449,449,449
BEGIN DESCRIPTION:
KILGORE CREEK 6.0
END DESCRIPTION:
XS GIS Cut Line= 3
      2519075.03     13458575.02        2518575.       13458275.
      2518175.01     13457375.01
#Sta/Elev= 30
  4417.8  152.91  4744.4  137.28  4839.6  134.71  4857.3   132.6    4861  131.97
  4876.5  134.32  4934.8  137.14  4950.4  136.22  4956.2  133.34  4965.9  133.28
  4977.6  130.88  4993.2  129.74    4997  130.58  5000.9   130.8  5001.5  126.73
    5002  126.23  5018.1  126.73  5044.7  128.62  5055.6  132.27  5061.8  135.44
  5067.3  134.53  5077.5  136.66  5090.5  137.47  5206.8  136.68  5394.9  138.31
  5537.1  141.51  5699.2  143.17  5756.7  145.66  5932.1  148.06  5985.8  147.59
#Mann= 6 ,-1 , 0
  4417.8     .12       0  4857.3     .07       0    4997     .12       0
  5001.5     .05       0  5018.1     .12       0  5932.1     .07       0
Bank Sta=5001.5,5018.1
XS Rating Curve= 0 ,0
Exp/Cntr=0.3,0.1

Type RM Length L Ch R = 1 ,4584    ,444,444,444
BEGIN DESCRIPTION:
KILGORE CREEK 5.0
END DESCRIPTION:
XS GIS Cut Line= 3
      2519125.03     13458375.04        2518975.       13458125.
      2518275.03     13457425.03
#Sta/Elev= 30
  4703.8  148.01  4855.5  141.29  4918.4  137.32  4929.3   136.8  4950.7  133.17
  4960.4  132.28  4972.1  133.57  4987.6   133.6  4992.5  131.34  4998.9  131.34
  5001.2  126.65  5001.7  126.15  5017.4  126.15  5017.9  126.65  5037.8  127.96
    5052  133.78  5066.1  135.42  5091.7  135.93  5136.8  136.95  5235.8  136.51
  5334.8  134.95  5447.9  135.76  5546.9  138.49  5688.4  140.94  5716.6  142.23
  5744.9  142.19  5872.2  145.04  5886.4  144.84  5942.9   146.7  5985.3  147.02
#Mann= 5 ,-1 , 0
  4703.8     .12       0  4918.4     .07       0  5001.2     .05       0
  5017.9     .07       0  5091.7     .12       0
Bank Sta=5001.2,5017.9
XS Rating Curve= 0 ,0
Exp/Cntr=0.3,0.1

Type RM Length L Ch R = 1 ,4140    ,449,449,449
BEGIN DESCRIPTION:
KILGORE CREEK 4.0
END DESCRIPTION:
XS GIS Cut Line= 3
      2519681.55     13458087.35        2519325.       13457875.
      2518325.03     13457375.01
#Sta/Elev= 30
  4581.3  142.86  4938.1  142.94  4967.4  142.23  4982.7  141.86  4988.5  140.32
  4993.4  136.38  4999.1  136.38  5010.3  125.97  5010.8  125.47  5026.5  125.47
    5027  125.97    5041  126.63    5055  132.15  5063.4  133.81  5099.7  135.02
  5122.1  134.08  5144.4  132.27  5175.2  135.15  5208.5  135.67    5368   134.6
  5451.9  136.35  5502.2  135.32  5510.6  134.57  5689.5  135.01  5778.9  137.17
  5823.6  139.66  5971.8  143.58  6002.5  145.24  6072.6  146.06  6114.3  146.76
#Mann= 6 ,-1 , 0
  4581.3     .12       0  4967.4     .07       0  5010.3     .05       0
    5027     .07       0  5208.5     .12       0  6072.6     .07       0
Bank Sta=5010.3,5027
XS Rating Curve= 0 ,0
Exp/Cntr=0.3,0.1

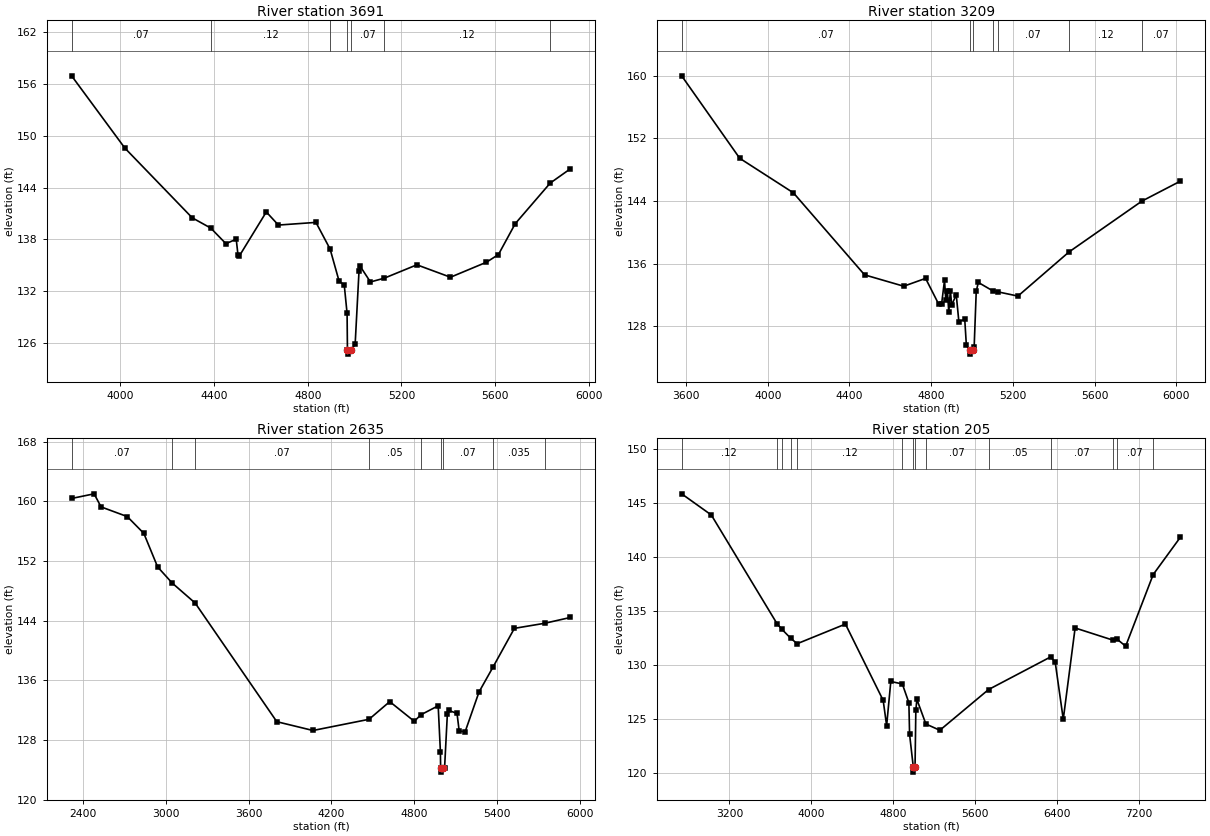
Type RM Length L Ch R = 1 ,3691    ,482,482,482
BEGIN DESCRIPTION:
KILGORE CREEK 3.0
END DESCRIPTION:
XS GIS Cut Line= 3
        2520425.       13457925.        2519325.       13457425.
      2518424.96     13457224.99
#Sta/Elev= 30
  3791.3  156.97  4018.7  148.59  4306.5   140.5  4385.6  139.31  4450.4   137.5
  4494.3  138.02    4502  136.17  4507.5  136.07  4622.8  141.18  4674.5  139.66
  4834.8  139.97  4895.2  136.88  4933.7  133.15  4955.7  132.71  4967.8  129.41
  4969.3  125.19  4969.8  124.69    4986  125.19  5002.2  125.82  5018.8  134.35
  5023.9  134.87  5067.5  133.06  5126.7   133.5  5265.9  135.05  5409.4  133.61
    5563  135.35  5614.2  136.24  5685.9  139.82  5835.3  144.53  5921.6  146.19
#Mann= 7 ,-1 , 0
  3791.3     .07       0  4385.6     .12       0  4895.2     .07       0
  4969.3     .05       0    4986     .07       0  5126.7     .12       0
  5835.3     .07       0
Bank Sta=4969.3,4986
XS Rating Curve= 0 ,0
Exp/Cntr=0.3,0.1

Type RM Length L Ch R = 1 ,3209    ,574,574,574
BEGIN DESCRIPTION:
KILGORE CREEK 2.0
END DESCRIPTION:
XS GIS Cut Line= 3
      2520524.96     13457874.97        2519425.       13456975.
      2518425.02       13457175.
#Sta/Elev= 30
  3578.7  159.99  3862.9  149.46  4125.6  145.05  4473.8  134.58  4665.4  133.13
  4772.4  134.13  4836.3  130.85  4850.6  130.84    4865  133.88  4871.4  131.36
  4879.3  132.49  4885.8  129.82  4893.7  132.58  4900.1  130.72  4922.4  132.04
  4935.3  128.59    4964  128.92  4971.9   125.6  4988.2  124.96  4988.7  124.46
  5005.2  124.96  5010.1   125.4  5020.3   132.5  5030.5  133.61  5100.4  132.55
  5124.6  132.42  5224.3  131.87    5474   137.5  5830.6  143.99  6019.7  146.55
#Mann= 7 ,-1 , 0
  3578.7     .07       0  4988.2     .05       0  5005.2     .07       0
  5100.4     .12       0  5124.6     .07       0    5474     .12       0
  5830.6     .07       0
Bank Sta=4988.2,5005.2
XS Rating Curve= 0 ,0
Exp/Cntr=0.3,0.1

Type RM Length L Ch R = 1 ,2635    ,2430,2430,2430
BEGIN DESCRIPTION:
Mapping XS 832d99c8
END DESCRIPTION:
XS GIS Cut Line= 5
      2520900.57     13458268.17      2520940.98     13457396.53
      2520211.81     13456545.83       2519456.6     13456459.03
      2518719.74     13456909.81
#Sta/Elev= 30
  2316.1  160.37  2479.4  160.99  2529.5  159.24  2719.7  157.94  2839.8  155.69
  2939.9  151.19  3045.1  149.04  3212.1  146.35    3804  130.45  4066.3  129.27
  4472.8  130.77  4622.9  133.14  4801.1   130.5  4848.1  131.37  4974.2  132.58
  4990.4  126.41  4991.9  124.19  4992.4  123.69    5009  124.19  5020.6  124.27
  5040.7  131.44  5050.8  131.96  5110.8  131.56  5126.3  129.24  5168.9  129.06
  5270.5  134.44  5373.6  137.83  5526.8  142.96  5746.4  143.64  5933.1  144.42
#Mann= 9 ,-1 , 0
  2316.1     .07       0  3045.1    .035       0  3212.1     .07       0
  4472.8     .05       0  4848.1     .07       0  4991.9     .05       0
    5009     .07       0  5373.6    .035       0  5746.4     .07       0
Bank Sta=4991.9,5009
XS Rating Curve= 0 ,0
Exp/Cntr=0.3,0.1

Type RM Length L Ch R = 1 ,205     ,0,0,0
BEGIN DESCRIPTION:
KILGORE CREEK 1.0
END DESCRIPTION:
XS GIS Cut Line= 4
      2522213.32     13457638.09      2521105.18     13455995.34
      2519507.96     13455682.84      2518779.42     13456714.94
#Sta/Elev= 30
  2732.8  145.86  3022.4   143.9  3664.8  133.82  3711.5  133.31  3796.4  132.49
  3861.1  131.97  4332.5  133.79  4701.2  126.72  4734.9  124.38  4775.7  128.47
  4888.3  128.24  4952.3   126.5  4959.1  123.57  4995.1  120.57  4995.6  120.07
  5012.5  120.57  5020.2  125.81  5030.4  126.81  5118.3  124.53  5254.6  123.95
  5730.1  127.72  6335.7  130.74  6381.2  130.28  6460.3  124.97    6576  133.43
    6946   132.3    6981  132.43  7069.7  131.74  7338.7  138.38  7605.2  141.85
#Mann= 14 ,-1 , 0
  2732.8     .12       0  3664.8     .07       0  3711.5     .12       0
  3796.4     .07       0  3861.1     .12       0  4888.3     .05       0
  4995.1     .05       0  5012.5     .05       0  5118.3     .07       0
  5730.1     .05       0  6335.7     .07       0    6946     .05       0
    6981     .07       0  7338.7    .035       0
Bank Sta=4995.1,5012.5
XS Rating Curve= 0 ,0
Exp/Cntr=0.3,0.1

Chan Stop Cuts=-1
Use User Specified Reach Order=0
Composite Channel Slope=5