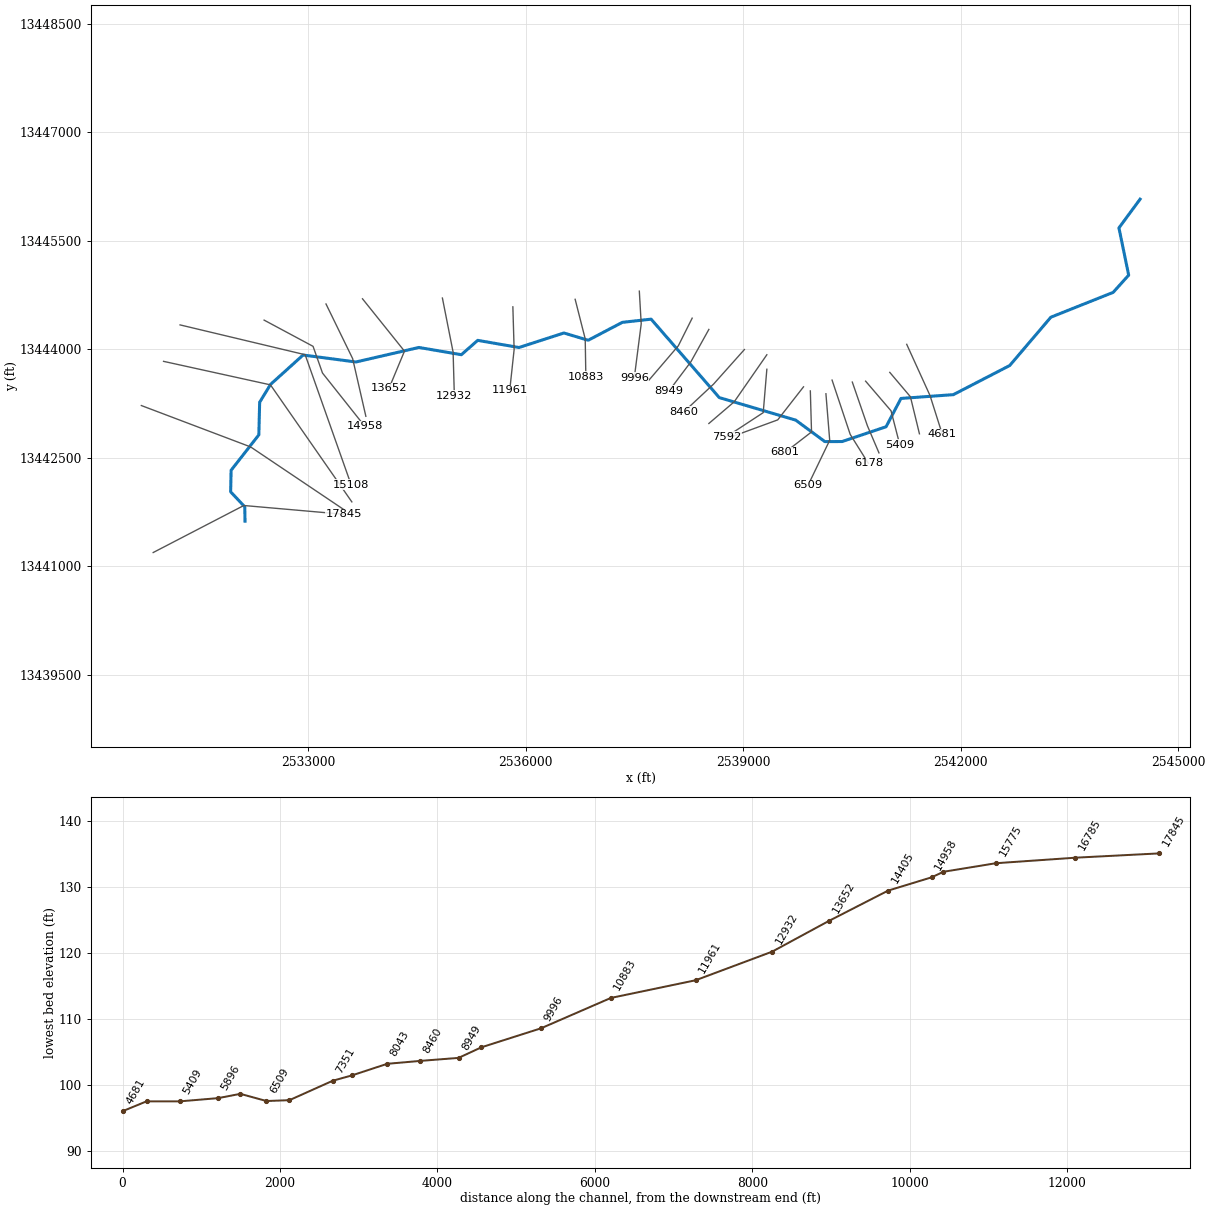
--- PAYTON BRANCH.prj (project) ---

Proj Title=PAYTON BRANCH Base Level Engineering
Current Plan=p01
Default Exp/Contr=0.3,0.1
English Units
Geom File=g01
Flow File=f01
Plan File=p01
Y Axis Title=Elevation
X Axis Title(PF)=Main Channel Distance
X Axis Title(XS)=Station
BEGIN DESCRIPTION:
PAYTON BRANCH
END DESCRIPTION:
DSS Export Rating Curves= 0
DSS Export Rating Curve Sorted= 0
DSS Export Volume Flow Curves= 0
DXF OffsetX= 0
DXF OffsetY= 0
DXF ScaleX= 1
DXF ScaleY= 10

--- PAYTON BRANCH.p01 (plan) ---

Plan Title=Multiple Run
Program Version=4.10
Short Identifier=Multiple
Geom File=g01
Flow File=f01
Subcritical Flow
K Sum by GR= 0
Std Step Tol= 0.01
Critical Tol= 0.01
Num of Std Step Trials= 20
Max Error Tol= 0.3
Flow Tol Ratio= 0.001
Split Flow NTrial= 30
Split Flow Tol= 0.02
Split Flow Ratio= 0.02
Log Output Level= 0
Friction Slope Method= 1
Unsteady Friction Slope Method= 2
Unsteady Bridges Friction Slope Method= 1
Parabolic Critical Depth
Global Vel Dist= 1 , 1 , 1
Global Log Level= 0
CheckData=True
Encroach Param=-1 ,0,0, 0
BEGIN DESCRIPTION:
Multiple Run
END DESCRIPTION:
Computation Interval=1HOUR
Output Interval=1HOUR
Run HTab= 0
Run UNet= 0
Run PostProcess= 0
Run WQNet= 0
UNET Theta= 1
UNET Theta Warmup= 1
UNET ZTol= 0.02
UNET ZSATol= 0.05
UNET MxIter= 20
UNET MaxInSteps= 0
UNET DtIC= 0
UNET DtMin= 0
UNET MaxCRTS= 20
UNET WFStab= 2
UNET SFStab= 1
UNET WFX= 1
UNET SFX= 1
UNET DSS MLevel= 4
UNET DZMax Abort= 100
UNET Convert EG Bridges= 0
UNET Use Existing IB Tables=-1
UNET Froude Reduction=False
UNET Froude Limit= 1
UNET Froude Power= 10
UNET Time Slicing=0,0, 5
UNET Junction Losses=0
Instantaneous Interval=1HOUR
Write IC File= 0
Write IC File at Sim End=0
Echo Input=False
Echo Parameters=False
Echo Output=False
Write Detailed= 0
WQ AD Non Conservative
WQ ULTIMATE=-1
WQ Max Comp Step=1HOUR
WQ Output Interval=15MIN
WQ Output Selected Increments= 0
WQ Output face flow=0
WQ Output face velocity=0
WQ Output face area=0
WQ Output face dispersion=0
WQ Output cell volume=0
WQ Output cell surface area=0
WQ Output cell continuity=0
WQ Output cumulative cell continuity=0
WQ Output face conc=0
WQ Output face dconc_dx=0
WQ Output face courant=0
WQ Output face peclet=0
WQ Output face adv mass=0
WQ Output face disp mass=0
WQ Output cell mass=0
WQ Output cell source sink temp=0
WQ Output cell source sink nsm=0
WQ Output MaxMinRange=-1
WQ Daily Max Min Mean=-1
WQ Daily Range=0
WQ Daily Time=0
WQ Create Restart=0
WQ Fixed Restart=0
WQ System Summary=0
WQ Use Fixed Temperature=0
Sorting and Armoring Iterations= 10
XS Update Threshold= 0.02
Hydraulics Update Threshold= 0.02
Energy Slope Method= 1
Volume Change Method= 0
XS Weighting Method= 0
Number of US Weighted Cross Sections= 1
Number of DS Weighted Cross Sections= 1
Upstream XS Weight=0.25
Main XS Weight=0.5
Downstream XS Weight=0.25
Number of DS XS's Weighted with US Boundary= 1
Upstream Boundary Weight= 1
Weight of XSs Associated with US Boundary= 0
Number of US XS's Weighted with DS Boundary= 1
Downstream Boundary Weight= 0.5
Weight of XSs Associated with DS Boundary= 0.5
Sediment Output Level= 4
Mass or Volume Output= 0
Output Increment Type= 1
Profile and TS Output Increment= 10
XS Output Flag= 0
XS Output Increment= 10
Disregard all LS=0
Disregard all Conn=0
Disregard all Breaches=0
Disregard all Pumps=0

--- PAYTON BRANCH.f01 (steady flow) ---

Flow Title=Multiple
Program Version=4.10
Number of Profiles= 7
Profile Names=10-year,25-year,50-year,1pct_min,100-year,1pct_plu,500-year
River Rch & RM=PAYTON BRANCH,Reach-1         ,17845
     298     443     562     345     688    1373    1020
River Rch & RM=PAYTON BRANCH,Reach-1         ,15108
     464     714     928     583    1163    2320    1807
River Rch & RM=PAYTON BRANCH,Reach-1         ,11961
     726    1149    1523     975    1945    3881    3139
River Rch & RM=PAYTON BRANCH,Reach-1         ,6509
    1193    1932    2600    1687    3366    6715    5581
River Rch & RM=PAYTON BRANCH,Reach-1         ,6178
    1630    2686    3656    2398    4785    9547    8113
Boundary for River Rch & Prof#=PAYTON BRANCH,Reach-1         , 1
Up Type= 0
Dn Type= 3
Dn Slope=0.0003
Boundary for River Rch & Prof#=PAYTON BRANCH,Reach-1         , 2
Up Type= 0
Dn Type= 3
Dn Slope=0.0003
Boundary for River Rch & Prof#=PAYTON BRANCH,Reach-1         , 3
Up Type= 0
Dn Type= 3
Dn Slope=0.0003
Boundary for River Rch & Prof#=PAYTON BRANCH,Reach-1         , 4
Up Type= 0
Dn Type= 3
Dn Slope=0.0003
Boundary for River Rch & Prof#=PAYTON BRANCH,Reach-1         , 5
Up Type= 0
Dn Type= 3
Dn Slope=0.0003
Boundary for River Rch & Prof#=PAYTON BRANCH,Reach-1         , 6
Up Type= 0
Dn Type= 3
Dn Slope=0.0003
Boundary for River Rch & Prof#=PAYTON BRANCH,Reach-1         , 7
Up Type= 0
Dn Type= 3
Dn Slope=0.0003
DSS Import GetInterval= 0
DSS Import GetPeak= 0
DSS Import FillOption= 0

--- PAYTON BRANCH.g01 (geometry) ---

Geom Title=Existing Conditions
Program Version=4.10

River Reach=PAYTON BRANCH   ,Reach-1
Reach XY= 30
        2532125.       13441625.      2532121.46     13441823.53
       2531926.6     13442030.88      2531933.01     13442328.33
      2532315.85     13442818.27      2532326.98      13443269.1
      2532478.51     13443516.52      2532926.55     13443921.25
      2533654.97     13443825.07        2534525.     13444025.82
       2535109.8      13443925.5      2535335.43     13444123.96
      2535904.97     13444025.07        2536525.     13444225.82
      2536859.75     13444125.36      2537330.93     13444372.76
       2537728.3     13444416.95      2538668.81     13443332.82
      2539723.53     13443021.45        2540125.       13442725.
      2540363.15      13442725.6      2540969.99       13442930.
        2541176.     13443321.46      2541897.64     13443373.37
      2542675.85     13443776.09      2543243.49     13444443.61
      2544103.17     13444787.06      2544317.45     13445024.99
      2544182.99     13445678.34        2544475.       13446075.

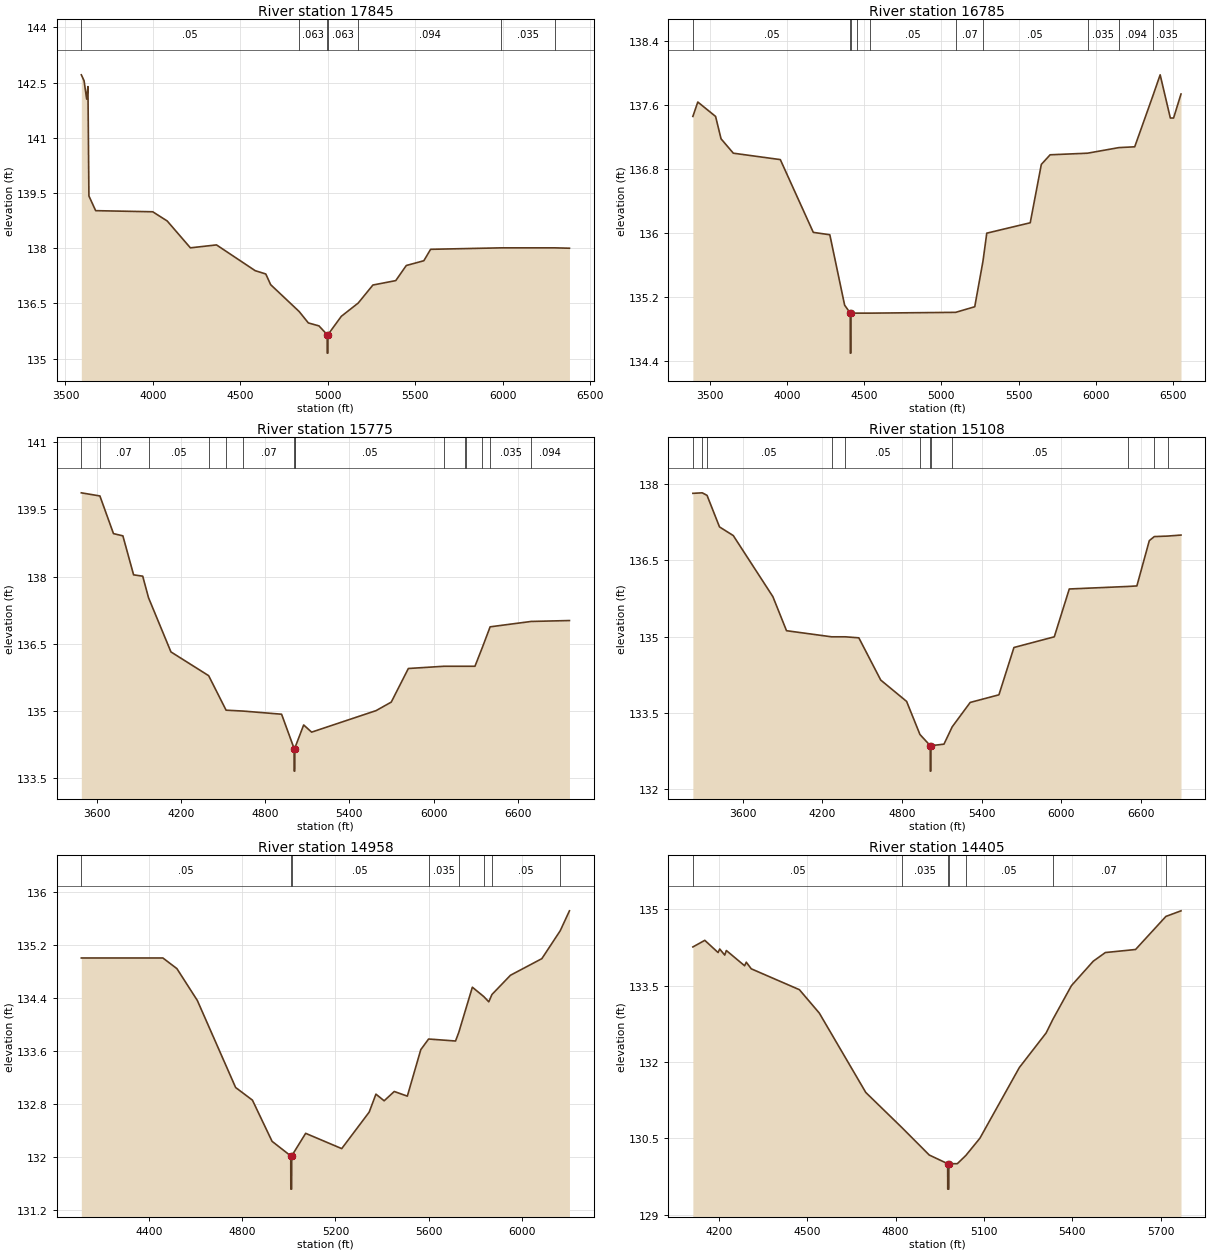
Type RM Length L Ch R = 1 ,17845   ,1060,1060,1060
BEGIN DESCRIPTION:
PAYTON BRANCH 29.0
END DESCRIPTION:
XS GIS Cut Line= 3
      2530857.95     13441191.81      2532108.54     13441841.75
      2533484.13     13441720.77
#Sta/Elev= 30
  3590.6  142.71  3606.3  142.55  3621.1  142.05  3628.4  142.39    3634  139.42
  3672.6  139.02  3998.7  138.99  4081.5  138.74  4214.1  138.01  4363.3  138.09
  4584.4  137.39  4645.1   137.3  4672.9  137.01  4835.9  136.28  4888.4  135.97
  4949.1  135.89  4996.1  135.65  4996.3  135.15  4999.8  135.15  5000.1  135.65
  5076.8  136.15  5173.3  136.51  5257.4     137    5388  137.12  5448.2  137.53
  5548.6  137.66  5587.2  137.97    5992  138.01  6296.2  138.01  6380.9     138
#Mann= 7 ,-1 , 0
  3590.6     .05       0  4835.9    .063       0  4996.1     .05       0
  5000.1    .063       0  5173.3    .094       0    5992    .035       0
  6296.2    .063       0
Bank Sta=4996.1,5000.1
XS Rating Curve= 0 ,0
Exp/Cntr=0.3,0.1

Type RM Length L Ch R = 1 ,16785   ,1010,1010,1010
BEGIN DESCRIPTION:
Mapping XS 32f9e1d8
END DESCRIPTION:
XS GIS Cut Line= 3
       2530694.7     13443223.05      2532201.99     13442651.53
      2533490.96     13441783.69
#Sta/Elev= 30
    3388  137.46  3419.9  137.64  3535.2  137.46  3570.7  137.18  3650.4     137
  3955.1  136.92    4169  136.01  4276.2  135.98  4372.2   135.1  4408.8     135
  4409.1   134.5  4412.6   134.5  4412.8     135  4450.2     135  4537.3     135
  5092.5  135.01  5216.1  135.08  5269.5  135.65  5294.1     136    5576  136.13
    5648  136.86    5705  136.98  5947.7     137  6151.1  137.07  6253.7  137.08
  6371.9  137.72  6418.7  137.98  6484.7  137.44  6505.7  137.44  6553.9  137.74
#Mann= 10 ,-1 , 0
    3388     .05       0  4408.8     .05       0  4412.8     .05       0
  4450.2     .07       0  4537.3     .05       0  5092.5     .07       0
  5269.5     .05       0  5947.7    .035       0  6151.1    .094       0
  6371.9    .035       0
Bank Sta=4408.8,4412.8
XS Rating Curve= 0 ,0
Exp/Cntr=0.3,0.1

Type RM Length L Ch R = 1 ,15775   ,667,667,667
BEGIN DESCRIPTION:
Mapping XS b30da97f
END DESCRIPTION:
XS GIS Cut Line= 3
      2531001.14     13443833.79       2532476.1     13443508.98
      2533598.79     13441891.78
#Sta/Elev= 30
  3489.7  139.87  3622.2   139.8  3718.9  138.96  3785.9  138.91  3862.3  138.04
  3927.3  138.01  3968.6  137.53  4128.5  136.32  4397.2  135.79  4521.5  135.02
  4643.3     135    4917  134.93  5006.9  134.16  5007.1  133.66  5010.6  133.66
  5010.9  134.16  5013.4  134.19  5074.4  134.69  5131.1  134.53  5590.4  135.01
  5698.7   135.2  5820.5  135.95  6073.9     136  6226.5     136  6230.2     136
  6295.2     136    6348  136.42  6403.4  136.88  6696.1     137  6968.7  137.02
#Mann= 15 ,-1 , 0
  3489.7    .035       0  3622.2     .07       0  3968.6     .05       0
  4397.2     .07       0  4521.5     .05       0  4643.3     .07       0
  5006.9     .05       0  5010.9     .07       0  5013.4     .05       0
  6073.9    .035       0  6226.5     .05       0  6230.2     .07       0
    6348     .05       0  6403.4    .035       0  6696.1    .094       0
Bank Sta=5006.9,5010.9
XS Rating Curve= 0 ,0
Exp/Cntr=0.3,0.1

Type RM Length L Ch R = 1 ,15108   ,150,150,150
BEGIN DESCRIPTION:
Mapping XS 58bd33c8
END DESCRIPTION:
XS GIS Cut Line= 3
      2531228.99     13444337.56      2532954.85     13443925.36
      2533588.34     13442131.43
#Sta/Elev= 30
  3225.6  137.82  3296.2  137.83  3332.4  137.78  3426.2  137.16  3529.9  136.99
  3828.1  135.79  3930.9  135.12    4270     135  4373.5     135  4475.8  134.98
  4640.6  134.15  4835.7  133.73    4936  133.08  5013.9  132.86  5014.1  132.36
  5017.6  132.36  5017.9  132.86    5117  132.89  5178.8  133.23  5314.5  133.71
    5531  133.86  5644.1  134.79    5948     135  6060.9  135.94    6505  135.99
    6570     136  6663.7  136.89  6701.3  136.97  6801.8  136.98  6902.5     137
#Mann= 12 ,-1 , 0
  3225.6     .05       0  3296.2    .035       0  3332.4     .05       0
    4270     .07       0  4373.5     .05       0    4936     .07       0
  5013.9     .05       0  5017.9     .07       0  5178.8     .05       0
    6505     .07       0  6701.3    .035       0  6801.8    .094       0
Bank Sta=5013.9,5017.9
XS Rating Curve= 0 ,0
Exp/Cntr=0.3,0.1

Type RM Length L Ch R = 1 ,14958   ,553,553,553
BEGIN DESCRIPTION:
Mapping XS f7f0b028
END DESCRIPTION:
XS GIS Cut Line= 4
      2532388.58     13444403.61       2533063.8      13444041.3
      2533194.01     13443672.37      2533775.16     13442939.42
#Sta/Elev= 30
  4110.4     135  4460.1     135  4520.2  134.84  4607.9  134.36    4772  133.05
    4844  132.86  4928.2  132.24  5008.4  132.02  5008.7  131.52  5012.2  131.52
  5012.4  132.02  5072.3  132.36  5226.9  132.13  5344.7  132.68  5373.6  132.95
  5408.8  132.85  5452.1  132.99  5508.2  132.92  5565.9  133.62  5599.4  133.78
  5714.9  133.75  5728.8  133.88    5787  134.56  5835.7  134.42  5857.5  134.34
  5870.9  134.45  5950.4  134.74    6085  134.99  6163.7  135.41  6203.3  135.71
#Mann= 8 ,-1 , 0
  4110.4     .05       0  5008.4     .05       0  5012.4     .05       0
  5599.4    .035       0  5728.8     .05       0  5835.7    .035       0
  5870.9     .05       0  6163.7    .035       0
Bank Sta=5008.4,5012.4
XS Rating Curve= 0 ,0
Exp/Cntr=0.3,0.1

Type RM Length L Ch R = 1 ,14405   ,753,753,753
BEGIN DESCRIPTION:
Mapping XS aea1c911
END DESCRIPTION:
XS GIS Cut Line= 3
      2533242.46     13444626.73      2533610.04     13443871.52
      2533792.34     13443074.62
#Sta/Elev= 30
    4112  134.26  4152.5  134.39  4197.6  134.15  4203.1  134.22  4220.1   134.1
  4225.7  134.19  4287.7  133.89  4293.3  133.96  4310.3  133.83  4473.7  133.42
  4541.3  132.96  4699.1   131.4  4821.7  130.71  4914.7  130.17  4977.1     130
  4977.4   129.5  4980.9   129.5  4981.1     130  5009.9     130  5038.6  130.16
  5086.5   130.5  5220.5  131.89  5311.5  132.57  5333.7  132.83  5397.4   133.5
  5471.5  133.98  5512.5  134.15  5615.1  134.21  5718.1  134.86  5769.4  134.97
#Mann= 7 ,-1 , 0
    4112     .05       0  4821.7    .035       0  4977.1    .035       0
  4981.1    .035       0  5038.6     .05       0  5333.7     .07       0
  5718.1    .035       0
Bank Sta=4977.1,4981.1
XS Rating Curve= 0 ,0
Exp/Cntr=0.3,0.1

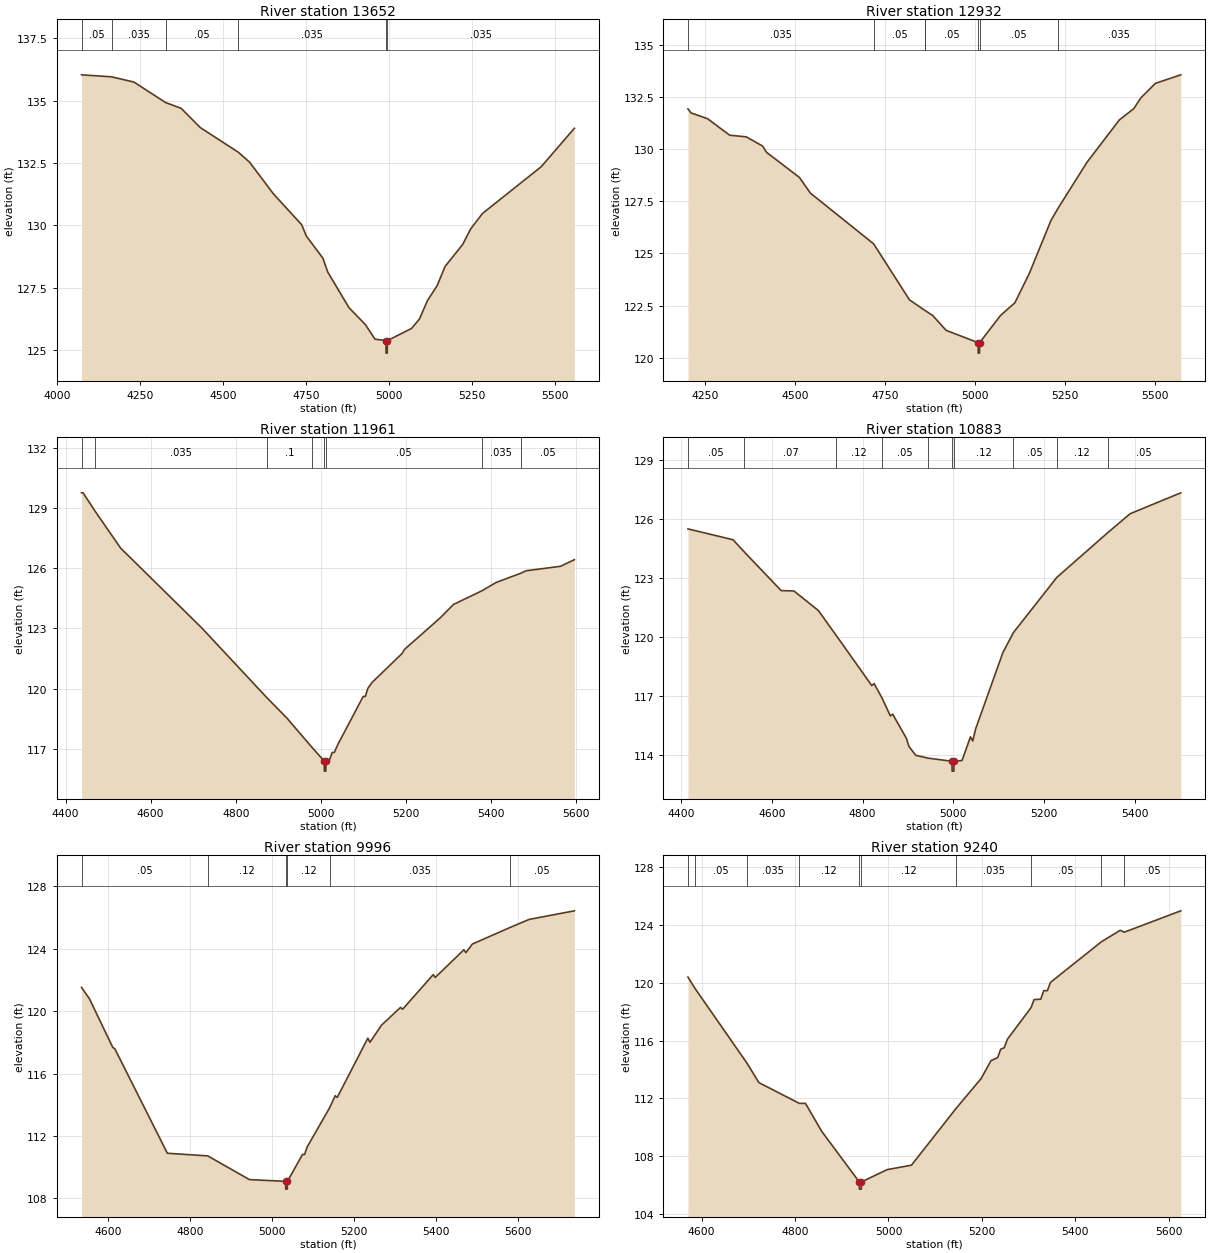
Type RM Length L Ch R = 1 ,13652   ,720,720,720
BEGIN DESCRIPTION:
Mapping XS 6aa5857f
END DESCRIPTION:
XS GIS Cut Line= 3
       2533745.9     13444698.37      2534325.03     13443974.92
      2534110.95      13443459.3
#Sta/Elev= 30
  4073.3  136.03  4163.6  135.95  4231.3  135.74  4326.6  134.92  4373.3  134.69
  4430.9  133.92  4545.8  132.93  4579.8  132.53  4651.8  131.26  4736.6  130.03
    4751  129.57  4800.6  128.69    4815  128.14  4879.1  126.71  4928.7  126.03
  4957.5  125.45  4990.7  125.39    4991  124.89  4994.5  124.89  4994.7  125.39
  5067.8  125.88  5091.7  126.26  5115.5  126.99  5144.8  127.59  5168.7  128.36
  5221.8  129.24  5245.7  129.86  5281.4  130.48  5458.3  132.35  5558.3  133.89
#Mann= 6 ,-1 , 0
  4073.3     .05       0  4163.6    .035       0  4326.6     .05       0
  4545.8    .035       0  4990.7    .035       0  4994.7    .035       0
Bank Sta=4990.7,4994.7
XS Rating Curve= 0 ,0
Exp/Cntr=0.3,0.1

Type RM Length L Ch R = 1 ,12932   ,971,971,971
BEGIN DESCRIPTION:
Mapping XS d5d419d6
END DESCRIPTION:
XS GIS Cut Line= 3
      2534848.49     13444708.59      2534996.06     13443962.05
      2535013.43     13443354.39
#Sta/Elev= 30
  4201.9  131.92  4210.2  131.73  4256.3  131.45  4317.8  130.66    4364  130.58
  4409.4  130.14  4420.3  129.84  4511.4  128.64  4541.9  127.89  4717.7  125.46
  4817.2  122.78  4860.4  122.27  4860.7  122.27  4881.7  122.03  4919.1  121.32
    5008  120.73  5008.2  120.23  5011.7  120.23    5012  120.73    5070  122.03
    5110  122.64    5150  124.04    5210  126.57  5229.8  127.16  5310.1  129.36
  5400.1  131.39  5440.1  131.93  5460.1  132.45  5500.2  133.14  5570.8  133.55
#Mann= 7 ,-1 , 0
  4201.9    .035       0  4717.7     .05       0  4860.4     .07       0
  4860.7     .05       0    5008     .05       0    5012     .05       0
  5229.8    .035       0
Bank Sta=5008,5012
XS Rating Curve= 0 ,0
Exp/Cntr=0.3,0.1

Type RM Length L Ch R = 1 ,11961   ,1078,1078,1078
BEGIN DESCRIPTION:
Mapping XS 4f58dc4a
END DESCRIPTION:
XS GIS Cut Line= 3
      2535820.72     13444587.02      2535838.08     13443996.77
      2535777.31     13443432.53
#Sta/Elev= 30
  4437.6  129.75  4441.1  129.75  4469.6  128.83  4529.7  126.99  4719.7  123.03
  4873.4  119.54  4919.8  118.54  4978.4  117.09  5007.8  116.39  5008.1  115.89
  5011.7  115.89  5011.9  116.39  5019.9  116.42  5026.5  116.82  5031.5  116.82
  5039.9  117.22  5099.4  119.61  5104.4  119.61  5110.3  120.01  5120.4  120.31
  5190.8  121.75  5196.4  121.95  5281.3  123.54  5311.5  124.19  5378.2  124.87
  5412.1  125.29  5469.1  125.74  5482.5  125.87  5562.9  126.09  5595.6  126.42
#Mann= 8 ,-1 , 0
  4437.6     .07       0  4469.6    .035       0  4873.4      .1       0
  4978.4     .05       0  5007.8     .05       0  5011.9     .05       0
  5378.2    .035       0  5469.1     .05       0
Bank Sta=5007.8,5011.9
XS Rating Curve= 0 ,0
Exp/Cntr=0.3,0.1

Type RM Length L Ch R = 1 ,10883   ,887,887,887
BEGIN DESCRIPTION:
Mapping XS f00bd06a
END DESCRIPTION:
XS GIS Cut Line= 3
      2536680.08     13444691.26      2536818.98     13444144.34
      2536827.66     13443623.49
#Sta/Elev= 30
  4415.6  125.49  4514.9  124.94  4540.1  124.31  4620.8  122.36    4649  122.34
  4702.7  121.35  4742.2  120.08  4820.4  117.54  4825.6  117.64  4843.2   116.9
  4861.3     116  4866.5  116.09  4896.7  114.86  4902.3  114.45  4917.3     114
  4944.3  113.86    4997   113.7  4997.3   113.2  5001.2   113.2  5001.5   113.7
  5019.2  113.74  5037.7  114.94  5042.7  114.73  5049.2  115.35  5109.2  119.22
  5132.3  120.23  5227.9  123.03  5339.6  125.29  5389.3  126.26  5500.8  127.32
#Mann= 10 ,-1 , 0
  4415.6     .05       0  4540.1     .07       0  4742.2     .12       0
  4843.2     .05       0  4944.3     .12       0    4997     .05       0
  5001.5     .12       0  5132.3     .05       0  5227.9     .12       0
  5339.6     .05       0
Bank Sta=4997,5001.5
XS Rating Curve= 0 ,0
Exp/Cntr=0.3,0.1

Type RM Length L Ch R = 1 ,9996    ,756,756,756
BEGIN DESCRIPTION:
Mapping XS 86ba7aed
END DESCRIPTION:
XS GIS Cut Line= 3
      2537565.51     13444804.09      2537591.55     13444352.68
      2537496.31     13443608.11
#Sta/Elev= 30
  4535.4  121.52  4554.5   120.8  4611.5  117.68  4616.5  117.59  4744.8  110.89
  4843.5  110.72  4945.2   109.2  5033.3  109.09  5033.6  108.59  5037.6  108.59
    5038  109.09  5074.8  110.82  5079.8  110.81    5086  111.29  5141.2  113.82
  5154.5  114.58  5159.5  114.47  5234.2  118.27  5239.3     118  5267.5   119.1
    5314  120.24    5319  120.12  5393.7  122.34  5398.7  122.16  5468.4  123.93
  5473.4  123.75  5489.3   124.3  5580.1  125.35  5627.9  125.88  5738.2  126.43
#Mann= 6 ,-1 , 0
  4535.4     .05       0  4843.5     .12       0  5033.3     .05       0
    5038     .12       0  5141.2    .035       0  5580.1     .05       0
Bank Sta=5033.3,5038
XS Rating Curve= 0 ,0
Exp/Cntr=0.3,0.1

Type RM Length L Ch R = 1 ,9240    ,291,291,291
BEGIN DESCRIPTION:
Mapping XS 71d81f36
END DESCRIPTION:
XS GIS Cut Line= 3
      2538294.67      13444430.8       2538103.7     13444048.86
      2537695.74     13443571.45
#Sta/Elev= 30
  4570.8   120.4  4585.5  119.63  4697.3  114.43  4722.6  113.09  4809.2  111.65
  4822.4  111.65  4856.8  109.73  4937.5  106.21  4937.8  105.71  4941.9  105.71
  4942.2  106.21  4997.2  107.06  5049.3  107.37  5144.5  111.29  5198.6  113.38
  5219.5  114.61  5233.8  114.82  5240.3   115.4    5248  115.51  5254.6  116.09
  5305.4  118.29  5311.7  118.84    5326  118.87  5332.5  119.46  5340.2  119.46
  5346.8  120.03    5456  122.85  5496.1  123.64  5504.9  123.51  5625.8  124.99
#Mann= 10 ,-1 , 0
  4570.8     .07       0  4585.5     .05       0  4697.3    .035       0
  4809.2     .12       0  4937.5     .05       0  4942.2     .12       0
  5144.5    .035       0  5305.4     .05       0    5456    .035       0
  5504.9     .05       0
Bank Sta=4937.5,4942.2
XS Rating Curve= 0 ,0
Exp/Cntr=0.3,0.1

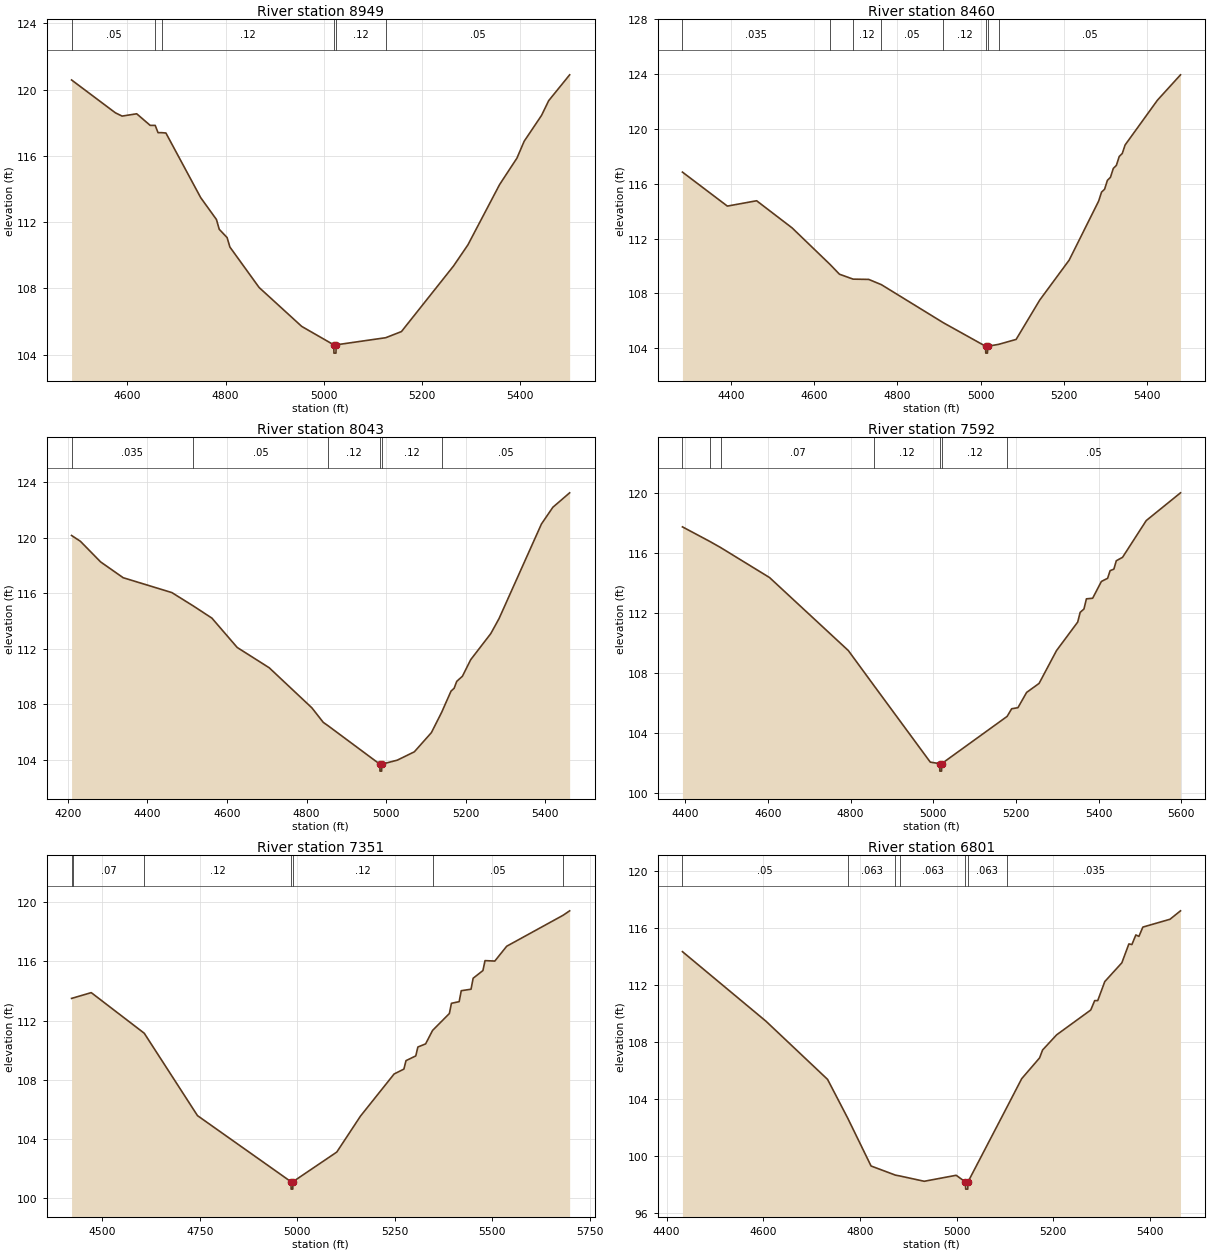
Type RM Length L Ch R = 1 ,8949    ,489,489,489
BEGIN DESCRIPTION:
PAYTON BRANCH 13.0
END DESCRIPTION:
XS GIS Cut Line= 3
      2538525.01     13444275.01        2538275.       13443825.
        2537975.       13443425.
#Sta/Elev= 30
  4486.1  120.58  4575.3   118.6  4589.1   118.4  4618.8  118.54  4646.3  117.84
  4656.5  117.84  4662.3   117.4  4669.9   117.4  4678.3  117.38  4749.2  113.48
  4781.3  112.16    4787  111.57    4803  111.07  4808.7   110.5  4868.2  108.06
  4955.1  105.71  5020.4   104.6  5020.7   104.1  5024.8   104.1  5025.2   104.6
  5126.2  105.03  5158.2   105.4  5264.4  109.36  5293.6  110.63  5358.2  114.27
  5393.6  115.87  5408.2  116.88  5443.6  118.44  5458.2  119.33  5500.9  120.89
#Mann= 6 ,-1 , 0
  4486.1     .05       0  4656.5    .035       0  4669.9     .12       0
  5020.4     .05       0  5025.2     .12       0  5126.2     .05       0
Bank Sta=5020.4,5025.2
XS Rating Curve= 0 ,0
Exp/Cntr=0.3,0.1

Type RM Length L Ch R = 1 ,8460    ,417,417,417
BEGIN DESCRIPTION:
Mapping XS 98ed0c9c
END DESCRIPTION:
XS GIS Cut Line= 3
      2539015.17     13443996.78      2538589.81     13443519.34
      2538183.22      13443138.7
#Sta/Elev= 30
  4283.5  116.85  4391.4  114.37  4461.7  114.76  4546.9  112.78  4638.5   110.1
  4660.6   109.4  4693.5  109.04  4730.9  109.02  4761.2  108.64  4910.1  105.86
  5011.8  104.14  5012.1  103.64  5016.2  103.64  5016.6  104.14  5042.9  104.28
    5085  104.64  5141.7  107.51  5212.5  110.43  5283.3  114.74  5290.2  115.39
  5297.5   115.6  5304.3  116.25  5311.6  116.47  5318.5  117.12  5325.8  117.34
  5332.7  117.99    5340  118.21  5346.8  118.83  5424.5   122.1  5479.9  123.95
#Mann= 8 ,-1 , 0
  4283.5    .035       0  4638.5     .05       0  4693.5     .12       0
  4761.2     .05       0  4910.1     .12       0  5011.8     .05       0
  5016.6     .12       0  5042.9     .05       0
Bank Sta=5011.8,5016.6
XS Rating Curve= 0 ,0
Exp/Cntr=0.3,0.1

Type RM Length L Ch R = 1 ,8043    ,451,451,451
BEGIN DESCRIPTION:
PAYTON BRANCH 12.0
END DESCRIPTION:
XS GIS Cut Line= 3
      2539324.98     13443924.97        2538875.       13443275.
      2538525.01       13442975.
#Sta/Elev= 30
  4209.5  120.16  4231.8  119.74  4282.4  118.26  4339.2  117.12  4461.5  116.05
  4515.3  115.09  4562.2  114.21  4625.7   112.1  4706.1  110.64  4813.5  107.75
  4841.9  106.71  4853.4  106.48  4984.1   103.7  4984.4   103.2  4988.6   103.2
    4989   103.7    5028  103.99  5070.8  104.59  5113.6  105.97  5139.2  107.42
    5163  108.96  5170.7  109.16  5177.3  109.66  5191.6  110.03  5212.4  111.22
  5262.9   113.1  5283.8  114.19  5390.2  120.99  5418.8  122.19    5461  123.23
#Mann= 6 ,-1 , 0
  4209.5    .035       0  4515.3     .05       0  4853.4     .12       0
  4984.1     .05       0    4989     .12       0  5139.2     .05       0
Bank Sta=4984.1,4989
XS Rating Curve= 0 ,0
Exp/Cntr=0.3,0.1

Type RM Length L Ch R = 1 ,7592    ,241,241,241
BEGIN DESCRIPTION:
PAYTON BRANCH 11.0
END DESCRIPTION:
XS GIS Cut Line= 3
        2539325.     13443724.95        2539275.       13443125.
      2538771.11     13442794.21
#Sta/Elev= 30
  4393.1  117.72  4459.2  116.75  4485.5  116.34  4603.8  114.34  4794.4  109.47
  4857.6  107.09  4992.6  102.03  5015.3  101.93  5015.7  101.43  5019.9  101.43
  5020.3  101.93  5178.5  105.08  5189.5  105.59  5204.6  105.66  5225.7  106.68
  5255.8  107.28    5298  109.47  5349.2  111.37  5355.2  112.02  5364.3  112.24
  5370.3  112.92  5385.4  112.96  5406.5  114.08  5421.6  114.29  5427.6   114.8
  5436.7   114.9  5442.6  115.46  5457.7  115.69    5515  118.14  5597.9  119.99
#Mann= 7 ,-1 , 0
  4393.1    .035       0  4459.2     .05       0  4485.5     .07       0
  4857.6     .12       0  5015.3     .05       0  5020.3     .12       0
  5178.5     .05       0
Bank Sta=5015.3,5020.3
XS Rating Curve= 0 ,0
Exp/Cntr=0.3,0.1

Type RM Length L Ch R = 1 ,7351    ,550,550,550
BEGIN DESCRIPTION:
PAYTON BRANCH 10.0
END DESCRIPTION:
XS GIS Cut Line= 3
      2539831.03     13443481.75      2539474.97     13443024.92
      2538818.95     13442784.16
#Sta/Elev= 30
  4420.8   113.5  4423.5  113.52  4471.3  113.89  4607.3  111.15  4743.9  105.59
  4983.8  101.13  4984.2  100.63  4988.4  100.63  4988.8  101.13  5101.3  103.13
  5162.2  105.56  5248.4   108.4  5273.5  108.73  5278.9   109.3    5304  109.62
  5309.4  110.22  5329.2  110.43  5347.1  111.34  5390.2  112.48  5395.5  113.17
  5415.3  113.28  5420.7  114.02  5445.8  114.12  5451.2  114.86  5476.3  115.38
  5481.7  116.05  5506.8  116.02  5537.3  117.02    5682  119.11  5698.8  119.41
#Mann= 7 ,-1 , 0
  4420.8     .05       0  4423.5     .07       0  4607.3     .12       0
  4983.8     .05       0  4988.8     .12       0  5347.1     .05       0
    5682    .035       0
Bank Sta=4983.8,4988.8
XS Rating Curve= 0 ,0
Exp/Cntr=0.3,0.1

Type RM Length L Ch R = 1 ,6801    ,292,292,292
BEGIN DESCRIPTION:
PAYTON BRANCH 9.0
END DESCRIPTION:
XS GIS Cut Line= 3
        2539925.     13443425.03      2539941.59     13442858.17
      2539575.01     13442575.01
#Sta/Elev= 30
  4432.9  114.32  4605.9  109.44  4733.1  105.37    4775  102.64  4823.1    99.3
  4873.6   98.66  4882.9    98.6  4933.1   98.23  4999.1   98.65  5018.4   98.18
  5018.8   97.68  5023.1   97.68  5023.5   98.18  5103.8   103.4  5134.7  105.42
  5171.6  106.87  5177.9  107.43  5206.9  108.49  5277.5  110.23  5285.7  110.89
    5292  110.89  5306.5  112.22  5341.9  113.54  5356.4  114.86  5362.7  114.82
  5370.8  115.49  5377.2  115.39  5385.3  116.04  5441.5  116.59  5463.2  117.18
#Mann= 7 ,-1 , 0
  4432.9     .05       0    4775    .063       0  4873.6    .035       0
  4882.9    .063       0  5018.4     .05       0  5023.5    .063       0
  5103.8    .035       0
Bank Sta=5018.4,5023.5
XS Rating Curve= 0 ,0
Exp/Cntr=0.3,0.1

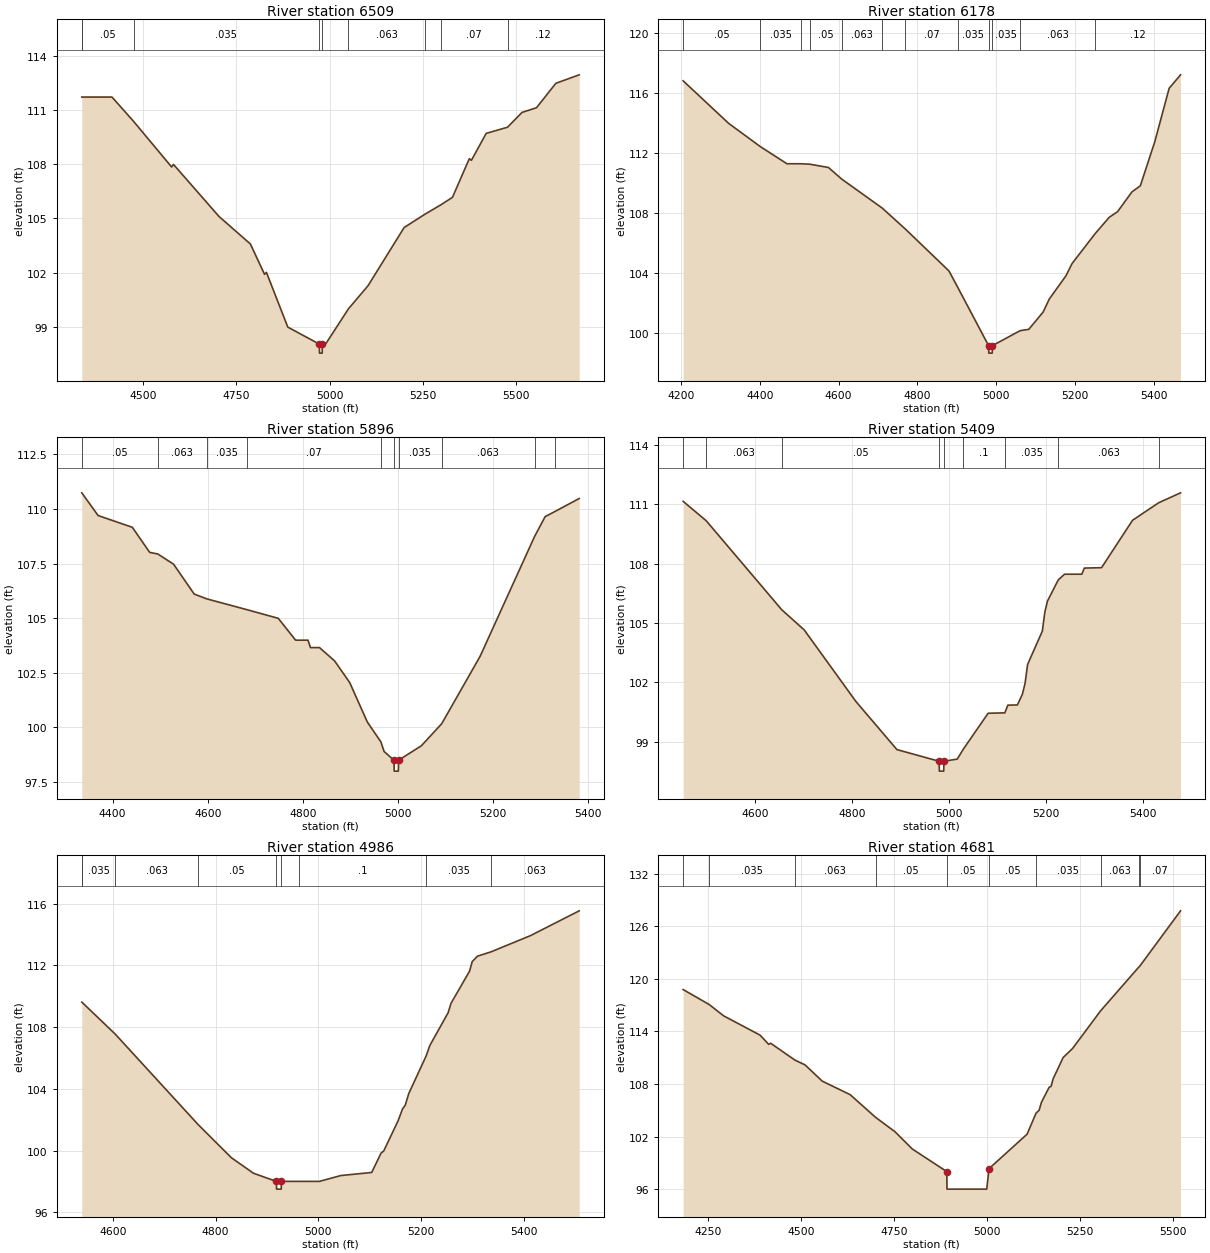
Type RM Length L Ch R = 1 ,6509    ,331,331,331
BEGIN DESCRIPTION:
Mapping XS 6149342a
END DESCRIPTION:
XS GIS Cut Line= 3
      2540140.16     13443385.69      2540192.24      13442743.3
      2539893.65     13442121.81
#Sta/Elev= 30
  4335.2  111.72  4336.2  111.72  4416.2  111.72  4473.9  110.38  4576.2  107.85
  4581.2  107.99  4703.3  105.11  4787.4  103.59  4825.3  101.91  4830.4  102.02
  4887.7   98.99  4972.2   98.05  4972.7   97.55  4979.9   97.55  4980.4   98.05
  4989.7   98.07  5050.3     100  5102.9  101.28  5199.7   104.5    5255  105.23
  5297.6  105.75  5329.3  106.17  5374.5  108.31  5380.1  108.22  5419.8  109.71
  5476.9  110.05  5515.9  110.87  5554.7  111.13  5606.5  112.48  5669.2  112.95
#Mann= 9 ,-1 , 0
  4335.2     .07       0  4336.2     .05       0  4473.9    .035       0
  4972.2    .035       0  4980.4    .035       0  5050.3    .063       0
    5255     .12       0  5297.6     .07       0  5476.9     .12       0
Bank Sta=4972.2,4980.4
XS Rating Curve= 0 ,0
Exp/Cntr=0.3,0.1

Type RM Length L Ch R = 1 ,6178    ,282,282,282
BEGIN DESCRIPTION:
PAYTON BRANCH 8.0
END DESCRIPTION:
XS GIS Cut Line= 3
        2540225.       13443575.        2540475.       13442825.
      2540725.02     13442424.97
#Sta/Elev= 30
  4205.5  116.83  4321.4  113.98  4401.7  112.43    4469  111.29  4504.7  111.29
  4526.9  111.26  4574.4  111.04  4607.7  110.27  4710.7  108.33  4769.4  106.93
  4880.1  104.13  4903.7  102.97  4980.7   99.14  4981.2   98.64  4989.9   98.64
  4990.4   99.14  5060.7  100.14  5082.7  100.23  5119.3  101.39  5134.6  102.25
  5177.1  103.81  5192.4  104.62    5251  106.62  5286.8  107.71    5308  108.09
  5344.5  109.41  5365.8  109.82  5402.3  112.75  5438.9  116.33  5467.8  117.23
#Mann= 12 ,-1 , 0
  4205.5     .05       0  4401.7    .035       0  4504.7    .063       0
  4526.9     .05       0  4607.7    .063       0  4710.7    .035       0
  4769.4     .07       0  4903.7    .035       0  4980.7    .035       0
  4990.4    .035       0  5060.7    .063       0    5251     .12       0
Bank Sta=4980.7,4990.4
XS Rating Curve= 0 ,0
Exp/Cntr=0.3,0.1

Type RM Length L Ch R = 1 ,5896    ,487,487,487
BEGIN DESCRIPTION:
Mapping XS 9fad7f56
END DESCRIPTION:
XS GIS Cut Line= 3
      2540504.29     13443547.43      2540712.61      13442943.3
      2540871.97     13442569.16
#Sta/Elev= 30
  4335.2  110.74  4369.5   109.7  4441.5  109.16    4478  108.01  4494.9  107.94
  4528.2  107.47  4571.6   106.1  4598.3  105.88  4681.9  105.39  4748.3  104.99
  4784.7  103.99  4810.7  103.99    4816  103.65  4834.9  103.65  4866.7  103.04
  4898.4  102.05  4935.5  100.24    4964   99.33  4970.7   98.89  4991.5   98.49
    4992   97.99  5000.7   97.99  5001.2   98.49    5049   99.15  5091.8  100.16
  5172.6  103.25  5287.1  108.74  5309.3  109.65  5330.4  109.89  5380.9  110.48
#Mann= 10 ,-1 , 0
  4335.2     .05       0  4494.9    .063       0  4598.3    .035       0
  4681.9     .07       0    4964    .035       0  4991.5    .035       0
  5001.2    .035       0  5091.8    .063       0  5287.1     .07       0
  5330.4     .12       0
Bank Sta=4991.5,5001.2
XS Rating Curve= 0 ,0
Exp/Cntr=0.3,0.1

Type RM Length L Ch R = 1 ,5409    ,423,423,423
BEGIN DESCRIPTION:
Mapping XS a5a294d2
END DESCRIPTION:
XS GIS Cut Line= 3
      2540687.85     13443559.97      2541038.54     13443150.25
      2541159.79     13442679.11
#Sta/Elev= 30
  4451.6  111.16  4499.1  110.18    4655  105.67  4701.3  104.65  4807.8  101.03
  4892.5   98.59  4979.5      98    4980    97.5    4989    97.5  4989.5      98
    5017   98.11  5029.4   98.61  5080.6  100.43    5115  100.45  5121.3  100.84
  5140.9  100.85  5151.2  101.39  5156.8  101.95    5162   102.9  5192.4  104.59
  5197.5  105.54  5202.8   106.1  5225.2  107.18  5238.2  107.47  5273.8  107.47
    5279  107.78  5314.5   107.8  5378.4   110.2  5432.5  111.09  5477.4  111.59
#Mann= 9 ,-1 , 0
  4451.6     .05       0  4499.1    .063       0    4655     .05       0
  4979.5     .05       0  4989.5     .05       0  5029.4      .1       0
    5115    .035       0  5225.2    .063       0  5432.5     .07       0
Bank Sta=4979.5,4989.5
XS Rating Curve= 0 ,0
Exp/Cntr=0.3,0.1

Type RM Length L Ch R = 1 ,4986    ,305,305,305
BEGIN DESCRIPTION:
Mapping XS 89e3dbbd
END DESCRIPTION:
XS GIS Cut Line= 3
      2541021.17      13443681.5       2541305.9     13443344.69
      2541430.45     13442832.65
#Sta/Elev= 30
  4539.5  109.61  4540.7  109.58  4604.7  107.54    4766  101.68  4830.8   99.53
  4873.6   98.53  4918.1      98  4918.6    97.5  4927.6    97.5  4928.1      98
  4962.6      98  5001.9      98  5043.6   98.38  5103.7   98.58    5122   99.84
  5127.1   99.97  5155.2  101.94  5163.7   102.7  5168.9  102.93  5175.8  103.69
  5209.4  106.11  5216.9  106.81  5252.3  108.92  5258.1  109.54  5294.1  111.62
  5299.3  112.24  5309.5  112.59  5335.7  112.87  5412.5  113.92  5507.5  115.53
#Mann= 9 ,-1 , 0
  4539.5     .05       0  4540.7    .035       0  4604.7    .063       0
    4766     .05       0  4918.1     .05       0  4928.1     .05       0
  4962.6      .1       0  5209.4    .035       0  5335.7    .063       0
Bank Sta=4918.1,4928.1
XS Rating Curve= 0 ,0
Exp/Cntr=0.3,0.1

Type RM Length L Ch R = 1 ,4681    ,431,431,431
BEGIN DESCRIPTION:
Mapping XS eeb2ca26
END DESCRIPTION:
XS GIS Cut Line= 3
        2541255.     13444069.01      2541576.18     13443361.54
      2541745.09     13442828.84
#Sta/Elev= 30
  4184.2  118.77  4254.2  117.06    4293  115.77  4390.8  113.57  4413.9  112.52
  4419.4  112.64  4484.1  110.73  4511.7  110.17  4557.8  108.32  4632.6  106.78
  4701.4  104.18  4753.4  102.54  4799.6  100.58  4892.3      98  4892.8      96
  4999.5      96  5005.8   98.34  5107.9  102.27    5132  104.67  5140.2     105
  5146.4   105.9  5167.2  107.62  5172.4  107.73  5177.8  108.58  5204.7  111.01
  5230.3  112.06  5305.3  116.34  5407.9  121.33  5410.2  121.42    5520  127.75
#Mann= 10 ,-1 , 0
  4184.2     .05       0  4254.2    .035       0  4484.1    .063       0
  4701.4     .05       0  4892.3     .05       0  5005.8     .05       0
    5132    .035       0  5305.3    .063       0  5407.9    .035       0
  5410.2     .07       0
Bank Sta=4892.3,5005.8
XS Rating Curve= 0 ,0
Exp/Cntr=0.3,0.1