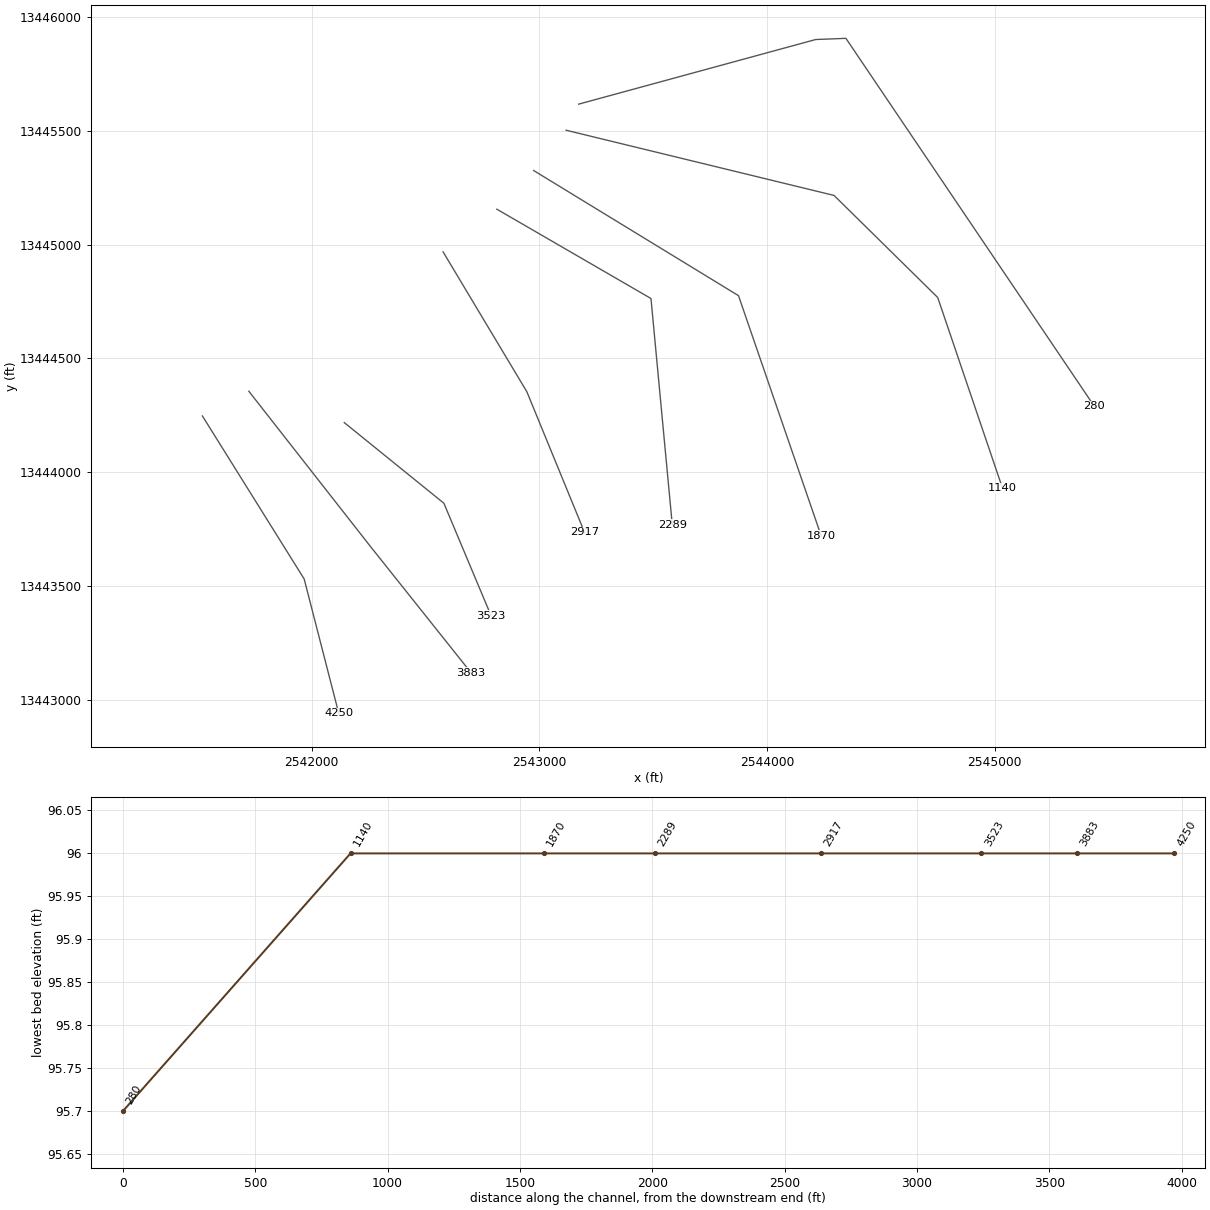
HEC-RAS study PAYTON BRANCH.prj: PAYTON BRANCH Base Level Engineering

--- PAYTON BRANCH.g01 (geometry) --- (continued)

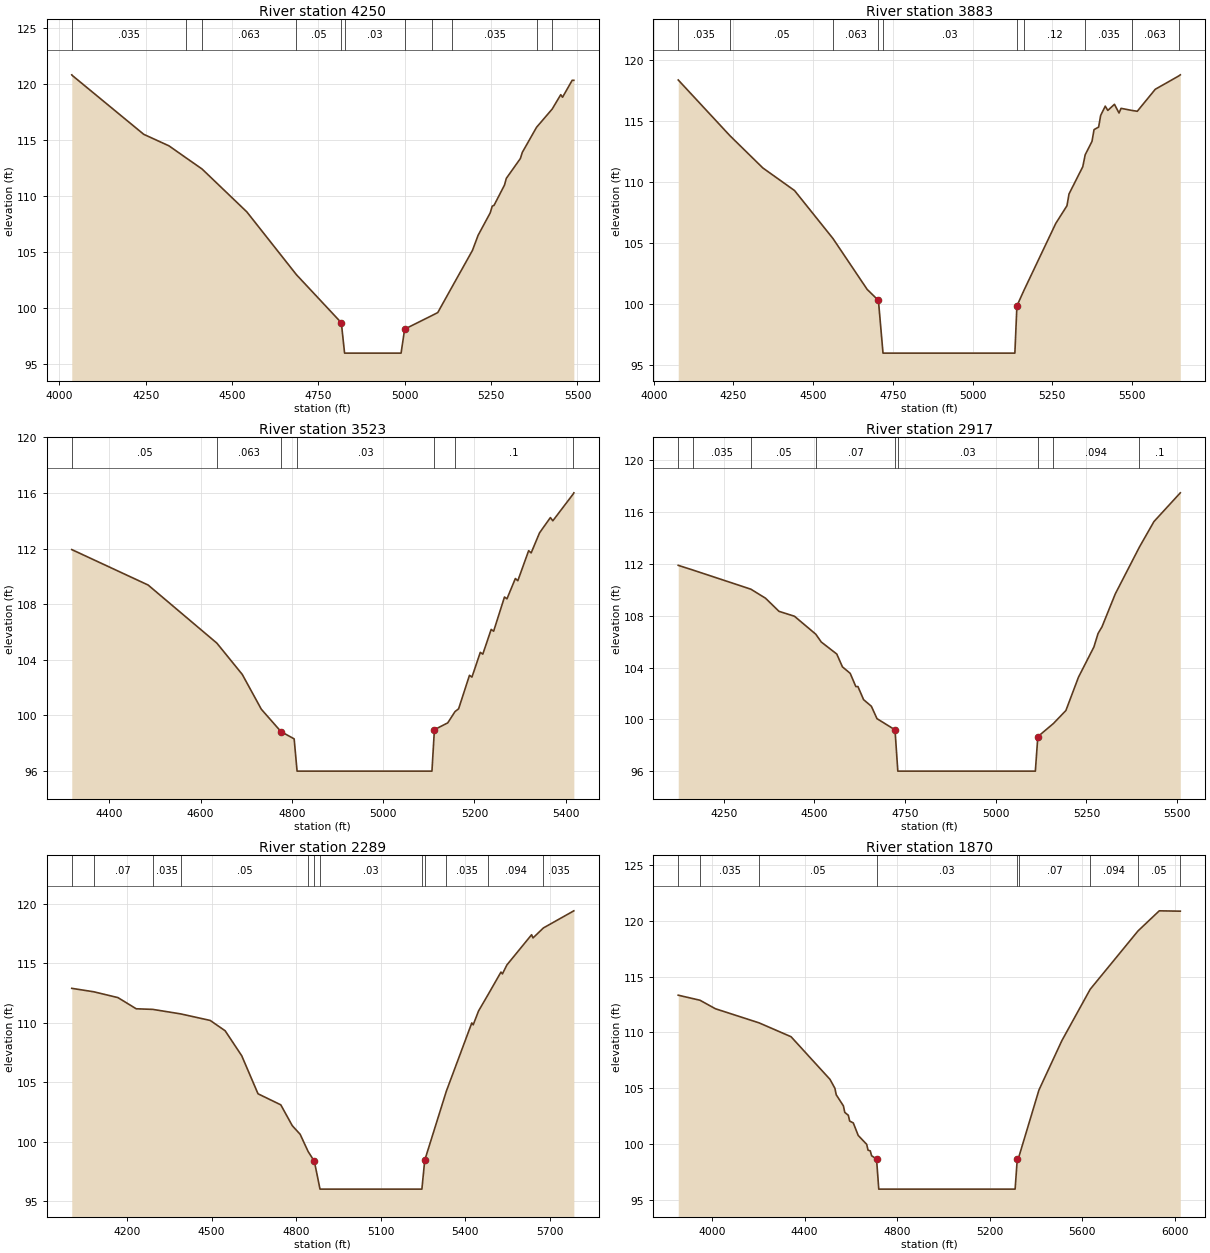
Type RM Length L Ch R = 1 ,4250    ,367,367,367
BEGIN DESCRIPTION:
Mapping XS e244c9a5
END DESCRIPTION:
XS GIS Cut Line= 3
      2541519.77     13444246.93      2541966.81     13443530.81
      2542118.72     13442940.54
#Sta/Elev= 30
  4035.9  120.84  4036.3  120.81  4244.3  115.53  4317.4   114.5  4367.3  113.42
  4413.3  112.43  4542.7  108.61  4686.4     103  4816.4   98.71  4825.8      96
  4989.4      96  4999.7   98.14  5078.4   99.35  5095.6   99.62  5138.2  101.98
  5195.9  105.16  5212.6  106.53  5247.5  108.52  5253.3  109.12  5258.5  109.19
  5288.8     111  5294.1   111.6  5334.8  113.37  5340.4  113.92  5381.7  116.16
    5427  117.79  5451.7  119.07  5456.9  118.84  5484.7  120.35  5489.6  120.35
#Mann= 12 ,-1 , 0
  4035.9     .05       0  4036.3    .035       0  4367.3     .05       0
  4413.3    .063       0  4686.4     .05       0  4816.4     .05       0
  4825.8     .03       0  4999.7     .03       0  5078.4      .1       0
  5138.2    .035       0  5381.7    .063       0    5427     .07       0
Bank Sta=4816.4,4999.7
XS Rating Curve= 0 ,0
Exp/Cntr=0.3,0.1

Type RM Length L Ch R = 1 ,3883    ,360,360,360
BEGIN DESCRIPTION:
Mapping XS b9296627
END DESCRIPTION:
XS GIS Cut Line= 3
      2541723.74     13444355.48      2542257.61     13443674.04
      2542699.54     13443119.45
#Sta/Elev= 30
    4077  118.33  4239.3  113.77  4342.3  111.14  4441.8  109.29  4562.3  105.37
  4669.6  101.21  4704.9  100.31  4719.3      96  5132.9      96  5139.3   99.86
  5161.9  101.16  5261.1   106.6  5296.3  108.05  5302.7  109.01  5345.9  111.24
  5353.4  112.21  5374.8  113.31  5381.2  114.27  5395.6  114.48    5402  115.43
  5416.4  116.19  5424.4  115.84  5445.2  116.34  5459.6  115.63    5466  116.01
  5499.7  115.84  5516.8  115.77  5573.3  117.57  5647.1  118.66  5651.8  118.75
#Mann= 10 ,-1 , 0
    4077    .035       0  4239.3     .05       0  4562.3    .063       0
  4704.9     .05       0  4719.3     .03       0  5139.3     .03       0
  5161.9     .12       0  5353.4    .035       0  5499.7    .063       0
  5647.1     .07       0
Bank Sta=4704.9,5139.3
XS Rating Curve= 0 ,0
Exp/Cntr=0.3,0.1

Type RM Length L Ch R = 1 ,3523    ,606,606,606
BEGIN DESCRIPTION:
Mapping XS cc672df0
END DESCRIPTION:
XS GIS Cut Line= 3
      2542143.03     13444217.75       2542580.5     13443863.61
      2542788.21     13443368.57
#Sta/Elev= 30
    4318  111.93  4485.3  109.38  4635.9   105.2  4691.5  102.95  4733.2  100.45
  4776.3   98.84  4805.1   98.32  4811.5      96  5106.9      96  5112.3   98.98
  5141.5   99.47  5157.4  100.28  5165.3  100.48  5189.1  102.89  5194.5  102.76
  5212.8  104.54  5218.3  104.41  5236.6  106.19    5242  106.06  5265.8  108.52
  5271.2  108.39  5289.6  109.85    5295  109.69  5318.7  111.85  5324.2  111.69
  5342.5  113.13  5366.3  114.23  5371.7     114  5416.6  115.94  5417.7  116.01
#Mann= 7 ,-1 , 0
    4318     .05       0  4635.9    .063       0  4776.3     .05       0
  4811.5     .03       0  5112.3     .03       0  5157.4      .1       0
  5416.6    .035       0
Bank Sta=4776.3,5112.3
XS Rating Curve= 0 ,0
Exp/Cntr=0.3,0.1

Type RM Length L Ch R = 1 ,2917    ,628,628,628
BEGIN DESCRIPTION:
Mapping XS 20d6ce22
END DESCRIPTION:
XS GIS Cut Line= 3
        2542577.     13444967.82      2542945.08      13444353.2
      2543198.54     13443735.16
#Sta/Elev= 30
  4124.5  111.89  4164.7  111.53  4324.7  110.05  4365.3  109.35  4402.3  108.34
    4445  107.96  4503.9  106.57  4518.9  105.97  4561.7  105.04  4577.3  104.05
  4598.7  103.55  4614.2  102.53    4620  102.53  4635.6  101.52    4657  101.01
  4672.6  100.05  4722.2   99.19    4730      96  5109.2      96    5116   98.66
  5159.1   99.68  5193.4  100.68  5228.2  103.26  5270.7  105.59  5282.1  106.63
  5292.9  107.14  5329.5  109.68  5396.1   113.3  5436.2  115.27  5508.9  117.49
#Mann= 9 ,-1 , 0
  4124.5     .05       0  4164.7    .035       0  4324.7     .05       0
  4503.9     .07       0  4722.2     .05       0    4730     .03       0
    5116     .03       0  5159.1    .094       0  5396.1      .1       0
Bank Sta=4722.2,5116
XS Rating Curve= 0 ,0
Exp/Cntr=0.3,0.1

Type RM Length L Ch R = 1 ,2289    ,419,419,419
BEGIN DESCRIPTION:
Mapping XS 4a937752
END DESCRIPTION:
XS GIS Cut Line= 3
      2542813.18     13445155.26      2543490.22     13444762.92
       2543583.8     13443768.22
#Sta/Elev= 30
  4003.9  112.89    4082   112.6  4167.8  112.11  4232.6  111.17  4291.3  111.12
  4390.4  110.74  4495.1  110.19  4548.2  109.32    4607  107.22  4664.8  104.02
  4745.7  103.09  4786.3  101.34  4814.4  100.61  4842.5   99.17  4864.7   98.34
  4884.8      96  5246.3      96  5256.4   98.43  5333.1  104.24  5423.4  109.98
  5428.4  109.82  5447.2  110.98  5479.9  112.31    5527  114.26    5532   114.1
  5547.7  114.85  5635.6   117.4  5640.6  117.13  5677.5  117.97  5785.5  119.41
#Mann= 12 ,-1 , 0
  4003.9     .05       0    4082     .07       0  4291.3    .035       0
  4390.4     .05       0  4842.5    .033       0  4864.7    .033       0
  4884.8     .03       0  5246.3    .033       0  5256.4    .033       0
  5333.1    .035       0  5479.9    .094       0  5677.5    .035       0
Bank Sta=4864.7,5256.4
XS Rating Curve= 0 ,0
Exp/Cntr=0.3,0.1

Type RM Length L Ch R = 1 ,1870    ,730,730,730
BEGIN DESCRIPTION:
PAYTON BRANCH 2.0
END DESCRIPTION:
XS GIS Cut Line= 3
      2542975.01       13445325.      2543874.67     13444775.38
      2544238.08     13443719.74
#Sta/Elev= 30
  3854.1  113.33    3948  112.88  4014.7  112.12  4203.4  110.86  4341.8  109.62
  4510.2  105.81  4531.5  105.01  4537.3  104.43  4568.2  103.44  4574.1  102.86
  4589.5   102.6  4595.4  102.08  4610.9  101.92  4632.2   100.8  4668.9     100
  4674.8   99.48  4684.4   99.42  4690.2   98.98  4711.5    98.7  4721.1      96
  5310.6      96    5320   98.72  5325.3   98.78  5413.7  104.86  5512.7  109.27
  5635.2  113.86  5841.8  119.07  5933.9  120.87  6022.7  120.84  6024.8  120.84
#Mann= 9 ,-1 , 0
  3854.1     .05       0    3948    .035       0  4203.4     .05       0
  4711.5     .03       0    5320     .03       0  5325.3     .07       0
  5635.2    .094       0  5841.8     .05       0  6022.7    .035       0
Bank Sta=4711.5,5320
XS Rating Curve= 0 ,0
Exp/Cntr=0.3,0.1

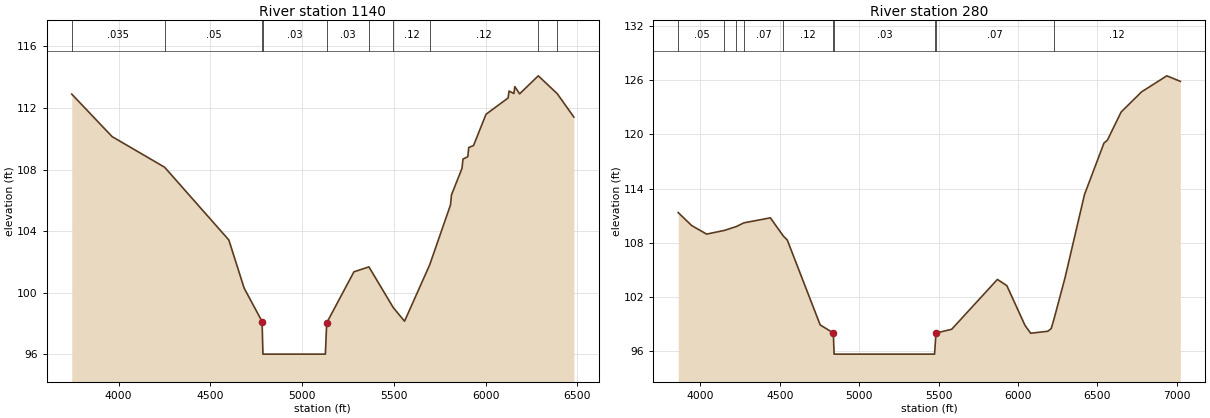
Type RM Length L Ch R = 1 ,1140    ,860,860,860
BEGIN DESCRIPTION:
Mapping XS 39fa967d
END DESCRIPTION:
XS GIS Cut Line= 4
       2543117.3     13445502.15      2544294.39      13445215.7
      2544749.71     13444767.44      2545034.67     13443928.92
#Sta/Elev= 30
    3745   112.9  3964.7  110.14  4250.9  108.15    4601  103.42  4684.4  100.29
  4782.1   98.12  4786.8      96    5127      96  5134.2   98.03  5282.6  101.35
  5364.4  101.67  5497.2   99.02  5558.5   98.14  5695.3   101.8  5808.9   105.7
  5814.2  106.35  5871.6  108.08  5876.9  108.68    5903  108.83  5908.3  109.43
  5934.4  109.56  6002.4  111.59  6122.7  112.65    6128   113.1  6154.1  112.94
  6159.4  113.39  6185.5  112.92  6287.3  114.09  6390.5  112.93    6481  111.41
#Mann= 10 ,-1 , 0
    3745    .035       0  4250.9     .05       0  4782.1     .05       0
  4786.8     .03       0  5134.2     .03       0  5364.4     .12       0
  5497.2     .12       0  5695.3     .12       0  6287.3    .094       0
  6390.5    .035       0
Bank Sta=4782.1,5134.2
XS Rating Curve= 0 ,0
Exp/Cntr=0.3,0.1

Type RM Length L Ch R = 1 ,280     ,0,0,0
BEGIN DESCRIPTION:
PAYTON BRANCH 1.0
END DESCRIPTION:
XS GIS Cut Line= 4
       2543172.5     13445616.73      2544213.66     13445900.59
      2544346.47      13445905.8      2545437.58     13444289.61
#Sta/Elev= 30
  3859.8  111.35  3944.2  109.92  4038.6  108.97  4150.6  109.38  4226.2  109.81
  4272.3  110.21  4440.1  110.77  4521.5  108.76  4546.5  108.32  4753.8   98.93
  4836.7   98.04  4841.4    95.7  5474.2    95.7  5483.1   98.03  5582.1   98.45
  5869.9  103.96  5929.5  103.27  6043.7   98.88  6079.7   98.01  6187.6   98.23
  6208.6   98.52  6226.3   99.57  6295.5  104.12  6418.4  113.34  6541.2  119.04
  6562.2  119.34  6649.2  122.47  6778.1   124.7  6936.9  126.47  7021.9  125.86
#Mann= 10 ,-1 , 0
  3859.8     .05       0  4150.6     .07       0  4226.2    .035       0
  4272.3     .07       0  4521.5     .12       0  4836.7     .05       0
  4841.4     .03       0  5474.2     .05       0  5483.1     .07       0
  6226.3     .12       0
Bank Sta=4836.7,5483.1
XS Rating Curve= 0 ,0
Exp/Cntr=0.3,0.1

Chan Stop Cuts=-1
Use User Specified Reach Order=0
Composite Channel Slope=5