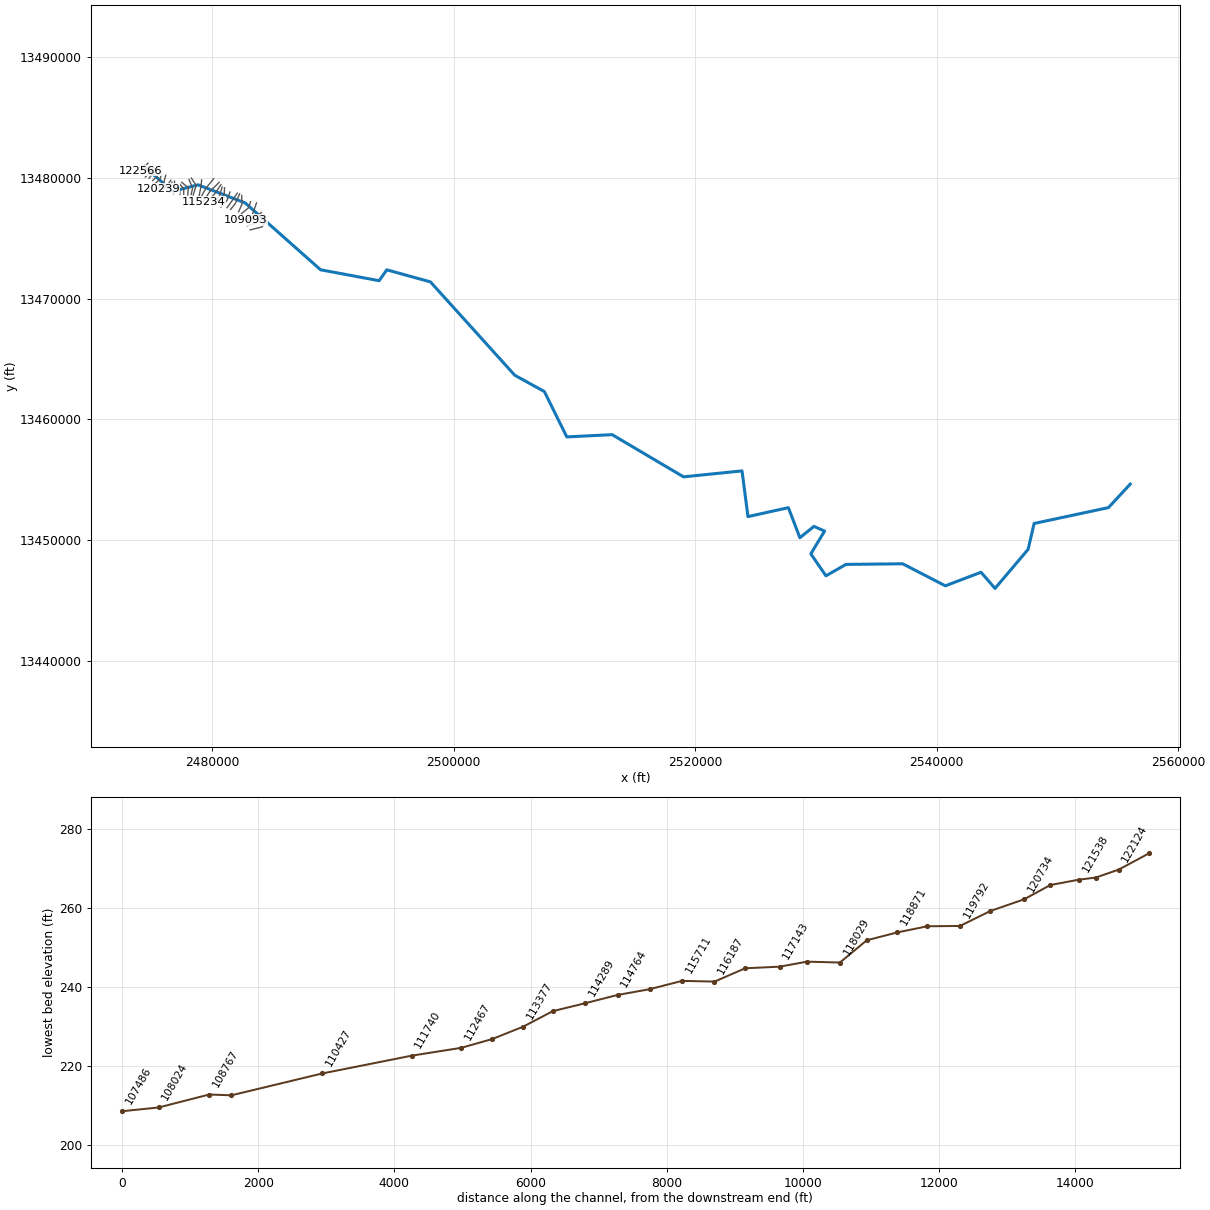
--- PERDIDO CREEK.prj (project) ---

Proj Title=PERDIDO CREEK Base Level Engineering
Current Plan=p01
Default Exp/Contr=0.3,0.1
English Units
Geom File=g01
Flow File=f01
Plan File=p01
Y Axis Title=Elevation
X Axis Title(PF)=Main Channel Distance
X Axis Title(XS)=Station
BEGIN DESCRIPTION:
PERDIDO CREEK
END DESCRIPTION:
DSS Export Rating Curves= 0
DSS Export Rating Curve Sorted= 0
DSS Export Volume Flow Curves= 0
DXF OffsetX= 0
DXF OffsetY= 0
DXF ScaleX= 1
DXF ScaleY= 10

--- PERDIDO CREEK.p01 (plan) ---

Plan Title=Multiple Run
Short Identifier=Multiple
Geom File=g01
Flow File=f01
Subcritical Flow
K Sum by GR= 0
Std Step Tol= 0.01
Critical Tol= 0.01
Num of Std Step Trials= 20
Max Error Tol= 0.3
Flow Tol Ratio= 0.001
Split Flow NTrial= 30
Split Flow Tol= 0.02
Split Flow Ratio= 0.02
Log Output Level= 0
Friction Slope Method= 1
Unsteady Friction Slope Method= 2
Unsteady Bridges Friction Slope Method= 1
Parabolic Critical Depth
Global Vel Dist=  1 , 1 , 1
Global Log Level= 0
CheckData=True
Encroach Param= -1, 0, 0, 0
BEGIN DESCRIPTION:
Multiple Run
END DESCRIPTION:

--- PERDIDO CREEK.f01 (steady flow) ---

Flow Title=Multiple
Program Version=4.10
Number of Profiles= 7
Profile Names=10-year,25-year,50-year,1pct_min,100-year,1pct_plu,500-year
River Rch & RM=PERDIDO CREEK,Reach-1         ,122566
     587     940    1256     812    1620    3233    2670
River Rch & RM=PERDIDO CREEK,Reach-1         ,117545
     871    1418    1915    1251    2495    4979    4192
River Rch & RM=PERDIDO CREEK,Reach-1         ,111740
     972    1588    2151    1407    2808    5602    4736
River Rch & RM=PERDIDO CREEK,Reach-1         ,104449
    1868    3160    4380    2926    5839   11650   10279
River Rch & RM=PERDIDO CREEK,Reach-1         ,103936
    2706    4644    6499    4379    8737   17432   15645
River Rch & RM=PERDIDO CREEK,Reach-1         ,98723
    3230    5576    7834    5297   10569   21088   19057
River Rch & RM=PERDIDO CREEK,Reach-1         ,95655
    3300    5689    7984    5392   10758   21465   19350
River Rch & RM=PERDIDO CREEK,Reach-1         ,90173
    4069    7067    9968    6762   13491   26919   24483
River Rch & RM=PERDIDO CREEK,Reach-1         ,88029
    4407    7664   10819    7343   14652   29234   26616
River Rch & RM=PERDIDO CREEK,Reach-1         ,82990
    4656    8101   11440    7765   15494   30914   28151
River Rch & RM=PERDIDO CREEK,Reach-1         ,79246
    6081   10674   15164   10350   20652   41206   37933
River Rch & RM=PERDIDO CREEK,Reach-1         ,77598
    6162   10809   15350   10471   20893   41688   38335
River Rch & RM=PERDIDO CREEK,Reach-1         ,74893
    6545   11460   16258   11080   22107   44109   40460
River Rch & RM=PERDIDO CREEK,Reach-1         ,72866
    6387   11200   15904   10847   21643   43183   39689
River Rch & RM=PERDIDO CREEK,Reach-1         ,70225
    6615   11568   16398   11164   22274   44443   40683
River Rch & RM=PERDIDO CREEK,Reach-1         ,67491
    6692   11702   16586   11291   22528   44950   41138
River Rch & RM=PERDIDO CREEK,Reach-1         ,65247
    6675   11661   16518   11236   22419   44732   40882
River Rch & RM=PERDIDO CREEK,Reach-1         ,61895
    6601   11502   16263   11043   22033   43961   40027
River Rch & RM=PERDIDO CREEK,Reach-1         ,57529
    7723   13505   19145   13028   25995   51866   47426
River Rch & RM=PERDIDO CREEK,Reach-1         ,50402
    7709   13458   19055   12951   25841   51559   47026
River Rch & RM=PERDIDO CREEK,Reach-1         ,44518
    7796   13611   19273   13098   26135   52146   47559
River Rch & RM=PERDIDO CREEK,Reach-1         ,42800
    7861   13727   19439   13214   26365   52606   47993
River Rch & RM=PERDIDO CREEK,Reach-1         ,35864
    7836   13671   19349   13143   26224   52324   47670
River Rch & RM=PERDIDO CREEK,Reach-1         ,33635
    9556   16749   23784   16205   32334   64515   59119
River Rch & RM=PERDIDO CREEK,Reach-1         ,29536
    9577   16779   23819   16223   32370   64587   59142
River Rch & RM=PERDIDO CREEK,Reach-1         ,26637
   10007   17492   24799   16868   33657   67155   61304
River Rch & RM=PERDIDO CREEK,Reach-1         ,21337
    9971   17414   24673   16772   33464   66770   60875
River Rch & RM=PERDIDO CREEK,Reach-1         ,16716
   10506   18364   26034   17706   35329   70491   64328
River Rch & RM=PERDIDO CREEK,Reach-1         ,12880
   10478   18302   25935   17630   35177   70187   63987
River Rch & RM=PERDIDO CREEK,Reach-1         ,9395
   11557   20229   28708   19542   38992   77799   71112
River Rch & RM=PERDIDO CREEK,Reach-1         ,7238
   11608   20318   28834   19627   39161   78136   71414
River Rch & RM=PERDIDO CREEK,Reach-1         ,6295
   11597   20288   28782   19584   39076   77967   71208
River Rch & RM=PERDIDO CREEK,Reach-1         ,2170
   11558   20212   28665   19498   38904   77624   70848
Boundary for River Rch & Prof#=PERDIDO CREEK,Reach-1         , 1
Up Type= 0
Dn Type= 3
Dn Slope=0.00032
Boundary for River Rch & Prof#=PERDIDO CREEK,Reach-1         , 2
Up Type= 0
Dn Type= 3
Dn Slope=0.00032
Boundary for River Rch & Prof#=PERDIDO CREEK,Reach-1         , 3
Up Type= 0
Dn Type= 3
Dn Slope=0.00032
Boundary for River Rch & Prof#=PERDIDO CREEK,Reach-1         , 4
Up Type= 0
Dn Type= 3
Dn Slope=0.00032
Boundary for River Rch & Prof#=PERDIDO CREEK,Reach-1         , 5
Up Type= 0
Dn Type= 3
Dn Slope=0.00032
Boundary for River Rch & Prof#=PERDIDO CREEK,Reach-1         , 6
Up Type= 0
Dn Type= 3
Dn Slope=0.00032
Boundary for River Rch & Prof#=PERDIDO CREEK,Reach-1         , 7
Up Type= 0
Dn Type= 3
Dn Slope=0.00032
DSS Import GetInterval= 0
DSS Import GetPeak= 0
DSS Import FillOption= 0

--- PERDIDO CREEK.g01 (geometry) ---

Geom Title=Existing Conditions
Program Version=4.10

River Reach=PERDIDO CREEK   ,Reach-1
Reach XY= 30
        2474375.       13480925.      2476726.53     13478878.74
       2478828.3     13479416.92       2482727.7     13477919.65
      2488976.46     13472378.54      2493824.99     13471474.15
      2494459.61     13472374.91        2498075.       13471375.
      2505054.91     13463644.79      2507508.51     13462292.05
      2509365.01     13458535.65      2513123.42     13458721.18
      2519035.54     13455226.09      2523877.45     13455719.54
      2524368.81     13451932.82      2527714.72     13452674.01
      2528668.52     13450182.69      2529830.85     13451122.94
      2530714.66     13450735.12      2529574.68     13448849.89
      2530826.36     13447028.29      2532485.54     13447973.91
      2537180.18     13448024.57      2540713.73     13446200.55
      2543668.97     13447323.38       2544828.3     13445983.08
      2547569.16     13449222.71      2548065.19     13451364.53
      2554223.45     13452678.75        2556025.       13454625.

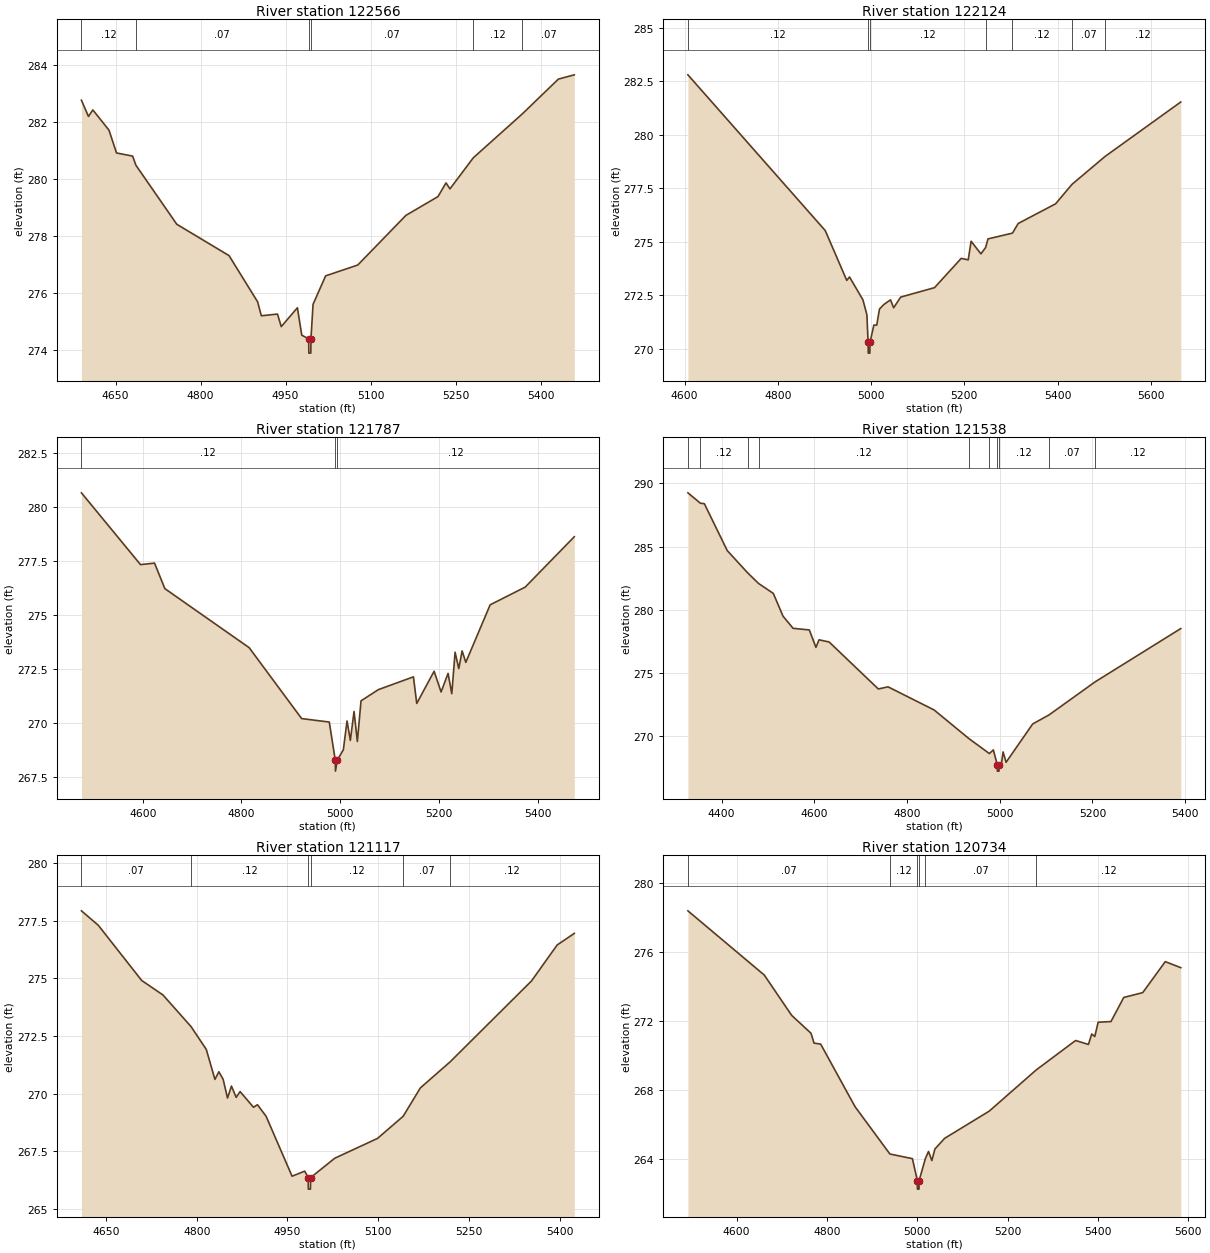
Type RM Length L Ch R = 1 ,122566  ,442,442,442
BEGIN DESCRIPTION:
PERDIDO CREEK 173.0
END DESCRIPTION:
XS GIS Cut Line= 3
      2474676.04     13481201.85      2474408.07     13480891.41
        2474075.       13480575.
#Sta/Elev= 30
  4589.9  282.76  4602.3  282.19    4610  282.42  4638.5  281.71  4651.8  280.91
  4680.2   280.8    4686  280.48  4758.1  278.41  4850.3  277.31  4900.7  275.69
  4907.3   275.2  4935.8  275.26  4942.4  274.82  4970.9  275.48  4978.6  274.52
  4990.8  274.39  4991.1  273.89  4994.6  273.89  4994.8  274.39  4998.5   275.6
  5020.7   276.6  5077.4  276.98  5162.3  278.72  5218.9  279.38  5233.1  279.86
    5240  279.65  5281.2  280.74  5367.7  282.28  5431.3   283.5  5459.4  283.65
#Mann= 6 ,-1 , 0
  4589.9     .12       0    4686     .07       0  4990.8     .05       0
  4994.8     .07       0  5281.2     .12       0  5367.7     .07       0
Bank Sta=4990.8,4994.8
XS Rating Curve= 0 ,0
Exp/Cntr=0.3,0.1

Type RM Length L Ch R = 1 ,122124  ,337,337,337
BEGIN DESCRIPTION:
Mapping XS cc316351
END DESCRIPTION:
XS GIS Cut Line= 3
      2475109.78     13480874.31      2474771.99       13480678.
      2474212.13     13480315.61
#Sta/Elev= 30
  4606.9   282.8  4901.6  275.52  4947.8  273.19  4953.7  273.35  4982.5  272.28
    4991  271.58  4993.6  270.29  4993.9  269.79  4997.4  269.79  4997.6  270.29
  5005.9   271.1  5012.1   271.1    5018  271.85  5027.2  272.06  5041.6  272.28
  5048.4  271.91  5063.5  272.41  5136.1  272.85  5193.4  274.22  5208.4  274.15
  5214.6  275.02  5235.7  274.43  5245.8  274.73  5250.8  275.13  5303.4   275.4
  5315.6  275.85  5395.9  276.77  5431.1  277.68  5501.8  278.98  5664.5  281.53
#Mann= 7 ,-1 , 0
  4606.9     .12       0  4993.6     .05       0  4997.6     .12       0
  5245.8     .07       0  5303.4     .12       0  5431.1     .07       0
  5501.8     .12       0
Bank Sta=4993.6,4997.6
XS Rating Curve= 0 ,0
Exp/Cntr=0.3,0.1

Type RM Length L Ch R = 1 ,121787  ,249,249,249
BEGIN DESCRIPTION:
Mapping XS 08e0f0f5
END DESCRIPTION:
XS GIS Cut Line= 3
      2475210.46     13480728.46      2474814.67     13480381.27
        2474464.     13480065.32
#Sta/Elev= 30
  4475.9  280.64  4595.6  277.32    4624  277.39  4644.9  276.21  4815.7  273.48
    4922   270.2    4978  270.04  4990.2  268.27  4990.5  267.77  4994.2  268.27
  5006.5  268.76    5014  270.09  5020.7  269.19  5028.2  270.53  5034.9  269.14
  5042.3  271.02  5077.5  271.54  5148.5  272.13  5155.2   270.9  5190.4  272.39
  5204.5  271.43  5218.7  272.29  5226.2  271.35  5232.9  273.27  5240.4  272.51
  5247.1  273.33  5254.6   272.8  5303.9  275.46  5374.9  276.28  5474.4  278.61
#Mann= 3 ,-1 , 0
  4475.9     .12       0  4990.2     .05       0  4994.2     .12       0
Bank Sta=4990.2,4994.2
XS Rating Curve= 0 ,0
Exp/Cntr=0.3,0.1

Type RM Length L Ch R = 1 ,121538  ,421,421,421
BEGIN DESCRIPTION:
PERDIDO CREEK 171.0
END DESCRIPTION:
XS GIS Cut Line= 3
      2475475.03     13480775.03        2475025.       13480275.
      2474775.02     13479975.03
#Sta/Elev= 30
  4327.3  289.25  4354.2  288.43  4362.8  288.39  4412.2  284.68  4455.9  282.93
  4479.7  282.08  4511.6  281.29  4532.5  279.49  4554.2  278.53  4589.3   278.4
  4603.5  277.02  4610.2  277.62  4631.9  277.45  4738.1  273.73    4759   273.9
  4858.4  272.07  4933.3  269.81  4977.6  268.62  4986.2  268.91  4994.7  267.73
  4994.9  267.23  4998.4  267.23  4998.7  267.73  5003.3  267.73  5007.2  268.75
  5013.7  267.93    5071  270.96  5106.4  271.68  5205.6  274.29  5390.5  278.51
#Mann= 10 ,-1 , 0
  4327.3     .07       0  4354.2     .12       0  4455.9     .07       0
  4479.7     .12       0  4933.3     .07       0  4977.6     .12       0
  4994.7     .05       0  4998.7     .12       0  5106.4     .07       0
  5205.6     .12       0
Bank Sta=4994.7,4998.7
XS Rating Curve= 0 ,0
Exp/Cntr=0.3,0.1

Type RM Length L Ch R = 1 ,121117  ,383,383,383
BEGIN DESCRIPTION:
PERDIDO CREEK 170.0
END DESCRIPTION:
XS GIS Cut Line= 3
      2475625.03     13480375.03        2475375.       13480075.
      2475075.01     13479775.01
#Sta/Elev= 30
  4609.4  277.93  4637.4   277.3    4709  274.91  4744.2  274.28  4790.6  272.91
  4815.8  271.92  4830.1  270.62  4836.6  270.95  4843.7  270.62  4850.9  269.81
  4857.4  270.33  4865.2  269.84  4871.7  270.09  4893.9  269.41  4900.4  269.52
  4914.7  269.02  4957.6  266.42  4978.5  266.64  4984.3  266.36  4984.5  265.86
    4988  265.86  4988.3  266.36  5028.2   267.2  5098.9  268.06  5141.3  269.02
  5169.7  270.25  5218.9  271.38  5353.5  274.89  5395.9  276.45  5424.2  276.95
#Mann= 6 ,-1 , 0
  4609.4     .07       0  4790.6     .12       0  4984.3     .05       0
  4988.3     .12       0  5141.3     .07       0  5218.9     .12       0
Bank Sta=4984.3,4988.3
XS Rating Curve= 0 ,0
Exp/Cntr=0.3,0.1

Type RM Length L Ch R = 1 ,120734  ,495,495,495
BEGIN DESCRIPTION:
Mapping XS 22661970
END DESCRIPTION:
XS GIS Cut Line= 3
      2475838.96     13480349.99      2475658.42     13479870.85
      2475232.13     13479479.22
#Sta/Elev= 30
  4492.3  278.41  4661.4  274.68    4722  272.34  4764.8   271.3  4771.5  270.73
  4786.2  270.67  4862.2  267.04  4939.4  264.29  4989.2  264.02  5000.1  262.75
  5000.3  262.25  5003.8  262.25  5004.1  262.75    5018  264.03  5024.9  264.44
  5032.2  263.91    5039  264.58  5060.6   265.2  5159.3  266.78  5263.2  269.17
  5350.4  270.88  5378.8  270.65  5386.1  271.26  5392.9  271.11  5400.3  271.94
  5428.7  271.98    5457  273.38    5499  273.66  5548.9  275.46  5583.2  275.11
#Mann= 6 ,-1 , 0
  4492.3     .07       0  4939.4     .12       0  5000.1     .05       0
  5004.1     .12       0    5018     .07       0  5263.2     .12       0
Bank Sta=5000.1,5004.1
XS Rating Curve= 0 ,0
Exp/Cntr=0.3,0.1

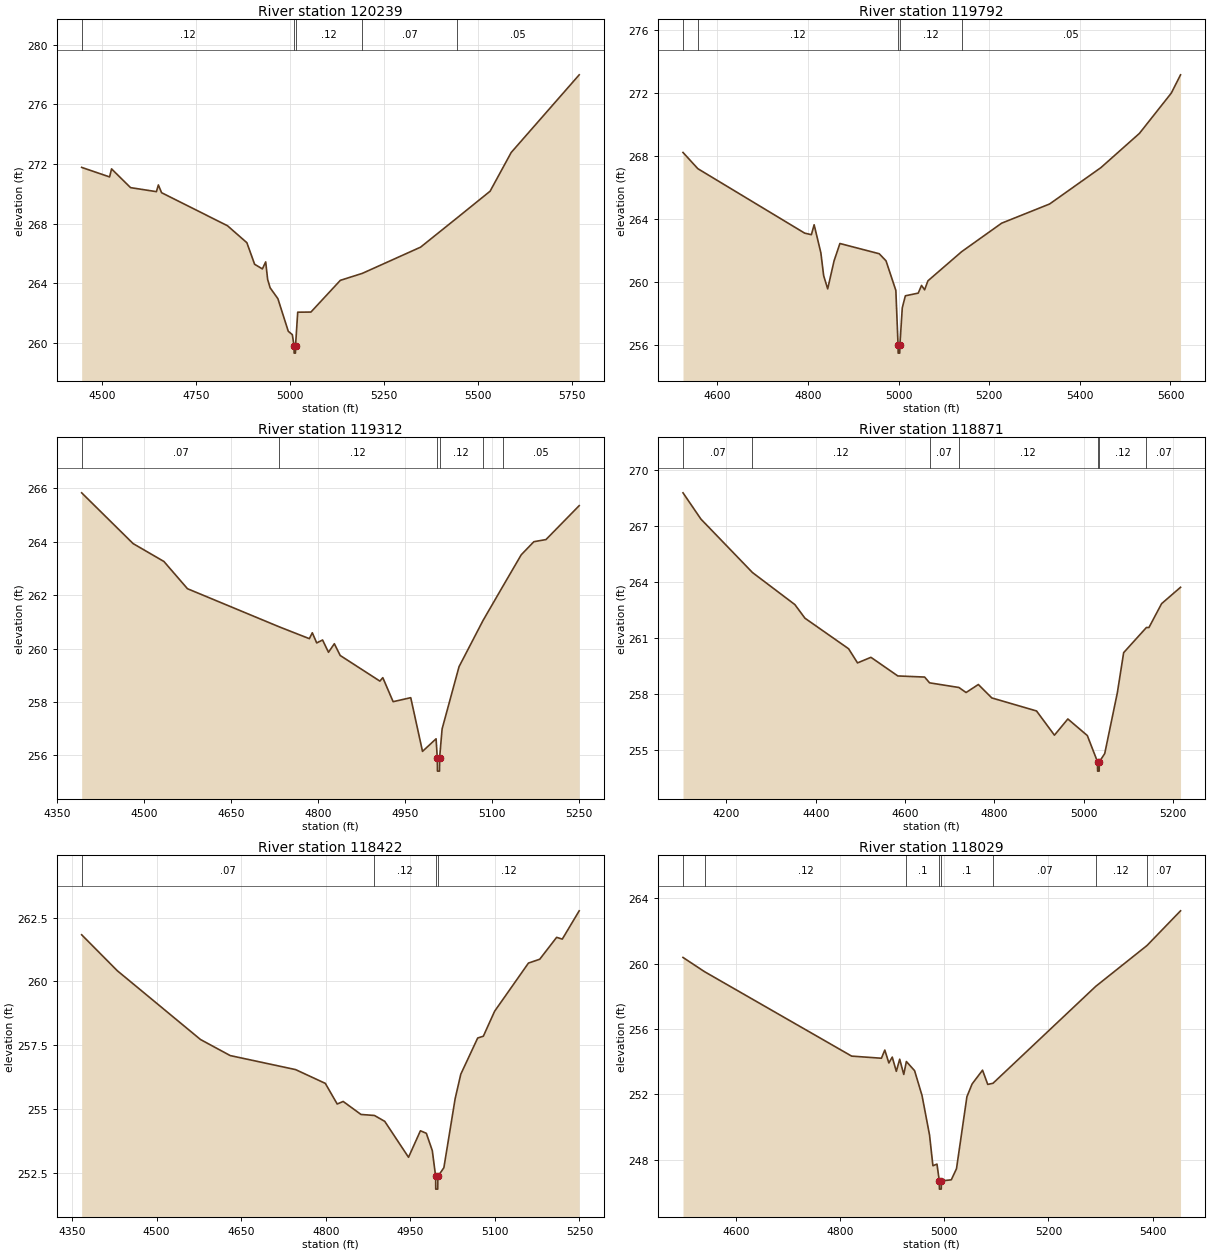
Type RM Length L Ch R = 1 ,120239  ,447,447,447
BEGIN DESCRIPTION:
Mapping XS 268d23f2
END DESCRIPTION:
XS GIS Cut Line= 3
      2476148.01     13480211.16      2476016.06     13479676.41
      2475519.74     13479086.38
#Sta/Elev= 30
  4446.2  271.77  4520.4  271.13  4525.6  271.67  4576.1  270.41  4644.8  270.14
    4650  270.59  4658.5  270.07  4833.6  267.85  4885.1  266.71  4905.7  265.26
  4926.3  264.95  4935.1  265.42  4940.3  264.24  4946.9  263.68  4967.5  262.95
  4995.1  260.76  5005.9  260.53  5010.4  259.79  5010.7  259.29  5014.2  259.29
  5014.4  259.79  5020.2  262.04  5055.3  262.05  5133.4  264.18  5191.9  264.65
  5346.6  266.41  5443.2  268.37  5531.3  270.17  5587.3  272.77    5768  277.99
#Mann= 5 ,-1 , 0
  4446.2     .12       0  5010.4     .05       0  5014.4     .12       0
  5191.9     .07       0  5443.2     .05       0
Bank Sta=5010.4,5014.4
XS Rating Curve= 0 ,0
Exp/Cntr=0.3,0.1

Type RM Length L Ch R = 1 ,119792  ,480,480,480
BEGIN DESCRIPTION:
Mapping XS 2b294043
END DESCRIPTION:
XS GIS Cut Line= 3
      2476571.59     13479790.96      2476307.72      13479402.1
      2475849.66      13478971.8
#Sta/Elev= 30
  4523.9  268.23  4556.7   267.2  4792.4  263.11  4807.3  263.01  4813.4  263.64
  4828.3  261.85  4834.4  260.41  4843.3  259.57  4857.4  261.35  4870.3  262.45
  4957.1   261.8  4972.1  261.35  4993.8  259.47  4998.7  255.99  4998.9  255.49
  5002.4  255.49  5002.7  255.99    5008  258.37  5014.8  259.13  5043.2   259.3
  5050.5  259.79  5057.3  259.51  5064.6  260.08    5139  261.93  5227.3  263.74
  5333.3  264.96  5446.6  267.27  5531.5  269.44  5601.9     272  5622.3  273.16
#Mann= 5 ,-1 , 0
  4523.9     .07       0  4556.7     .12       0  4998.7     .05       0
  5002.7     .12       0    5139     .05       0
Bank Sta=4998.7,5002.7
XS Rating Curve= 0 ,0
Exp/Cntr=0.3,0.1

Type RM Length L Ch R = 1 ,119312  ,441,441,441
BEGIN DESCRIPTION:
PERDIDO CREEK 166.0
END DESCRIPTION:
XS GIS Cut Line= 3
        2476675.     13479624.98        2476575.       13479025.
      2476424.97     13478824.96
#Sta/Elev= 30
    4392  265.83  4480.7  263.93  4533.9  263.26  4574.5  262.24  4733.1  260.81
  4784.8  260.37  4789.9  260.59  4797.5  260.21  4807.6  260.32  4817.8  259.86
  4827.9  260.18    4838  259.74  4906.5  258.78  4911.5  258.91  4929.3  258.01
  4959.7  258.16    4980  256.15  5003.4  256.62  5005.5  255.91  5005.8  255.41
  5009.3  255.41  5009.5  255.91  5013.8  256.99    5043  259.32  5084.4  261.05
  5118.6  262.33  5150.3  263.51  5172.1     264    5193  264.08  5250.3  265.35
#Mann= 6 ,-1 , 0
    4392     .07       0  4733.1     .12       0  5005.5     .05       0
  5009.5     .12       0  5084.4     .07       0  5118.6     .05       0
Bank Sta=5005.5,5009.5
XS Rating Curve= 0 ,0
Exp/Cntr=0.3,0.1

Type RM Length L Ch R = 1 ,118871  ,449,449,449
BEGIN DESCRIPTION:
PERDIDO CREEK 165.0
END DESCRIPTION:
XS GIS Cut Line= 3
        2476875.       13479725.        2476925.       13478825.
      2476775.02     13478675.02
#Sta/Elev= 30
    4103  268.79  4143.1  267.38  4258.5  264.51  4353.4  262.79  4375.9  262.06
  4473.6  260.42  4493.6  259.66  4523.6  259.96  4583.7  258.96  4643.8   258.9
  4654.8  258.59  4720.5  258.34  4736.5  258.07    4764   258.5  4794.1  257.78
  4894.2  257.08  4934.3  255.78  4964.3  256.65  5007.9  255.76  5030.7  254.35
  5030.9  253.85  5034.4  253.85  5034.7  254.35  5046.8  254.79  5075.1  258.06
  5089.2  260.21  5140.1  261.56  5145.8  261.56  5174.1  262.84  5216.5  263.72
#Mann= 7 ,-1 , 0
    4103     .07       0  4258.5     .12       0  4654.8     .07       0
  4720.5     .12       0  5030.7     .05       0  5034.7     .12       0
  5140.1     .07       0
Bank Sta=5030.7,5034.7
XS Rating Curve= 0 ,0
Exp/Cntr=0.3,0.1

Type RM Length L Ch R = 1 ,118422  ,393,393,393
BEGIN DESCRIPTION:
PERDIDO CREEK 164.0
END DESCRIPTION:
XS GIS Cut Line= 3
      2477125.01     13479474.96        2477325.       13478875.
        2477325.     13478625.01
#Sta/Elev= 30
  4367.1  261.83  4430.3  260.42  4577.9  257.72  4630.6  257.09  4746.5  256.54
  4799.2     256  4820.3  255.19  4830.9  255.29  4862.5  254.78  4886.4  254.74
  4904.6  254.51  4946.8   253.1  4967.9  254.14  4978.4  254.04    4989  253.36
  4994.9  252.35  4995.1  251.85  4998.6  251.85  4998.9  252.35  5009.5  252.69
  5029.5   255.4  5039.5  256.36  5069.5  257.78  5079.5  257.85  5099.5  258.83
  5159.5  260.72  5179.5  260.87  5209.5  261.73  5219.5  261.66  5249.5  262.77
#Mann= 4 ,-1 , 0
  4367.1     .07       0  4886.4     .12       0  4994.9     .05       0
  4998.9     .12       0
Bank Sta=4994.9,4998.9
XS Rating Curve= 0 ,0
Exp/Cntr=0.3,0.1

Type RM Length L Ch R = 1 ,118029  ,484,484,484
BEGIN DESCRIPTION:
Mapping XS 96e4ef9b
END DESCRIPTION:
XS GIS Cut Line= 3
      2477314.68     13479471.53      2477641.06     13479082.66
      2477641.06     13478634.74
#Sta/Elev= 30
  4498.2  260.37  4539.6   259.5  4822.1  254.34  4879.3  254.21  4885.8  254.71
  4893.6  253.92  4900.1  254.28  4907.9  253.41  4914.4  254.15  4922.2  253.22
  4927.2  254.01    4943  253.45  4957.3  251.93  4971.7  249.52  4978.2  247.64
    4986  247.74  4990.5  246.71  4990.7  246.21  4994.2  246.21  4994.5  246.71
  5013.5  246.78  5023.5  247.46  5043.5  251.86  5053.5  252.64  5073.5  253.48
  5083.5  252.61  5093.6  252.68  5290.8   258.6  5389.4   261.1  5453.8  263.22
#Mann= 8 ,-1 , 0
  4498.2     .07       0  4539.6     .12       0  4927.2      .1       0
  4990.5     .05       0  4994.5      .1       0  5093.6     .07       0
  5290.8     .12       0  5389.4     .07       0
Bank Sta=4990.5,4994.5
XS Rating Curve= 0 ,0
Exp/Cntr=0.3,0.1

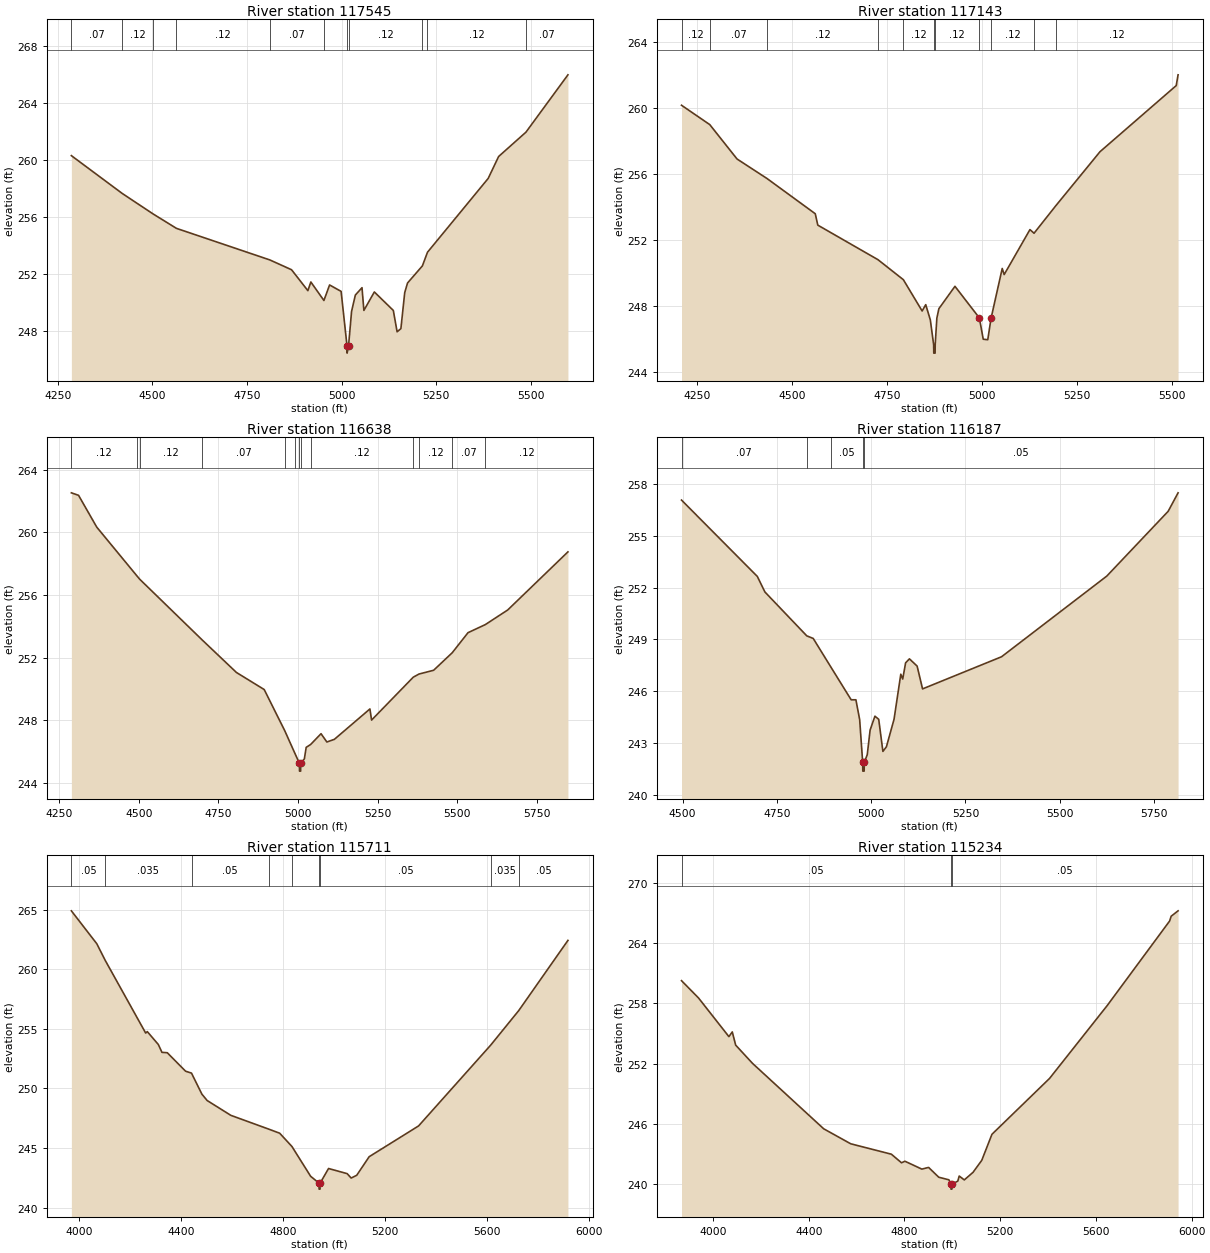
Type RM Length L Ch R = 1 ,117545  ,402,402,402
BEGIN DESCRIPTION:
PERDIDO CREEK 162.0
END DESCRIPTION:
XS GIS Cut Line= 3
      2477475.03     13479624.97        2478025.       13479175.
        2477975.     13478574.97
#Sta/Elev= 30
  4285.6  260.32  4420.2  257.66  4501.8  256.22  4563.3  255.21  4810.3  252.99
  4867.7   252.3  4910.8  250.83  4918.7  251.44  4953.2  250.14  4968.2  251.23
  4998.7  250.78  5014.3  246.94  5014.5  246.44  5018.3  246.94  5026.3  249.37
  5036.3  250.52  5053.9  251.04  5058.9  249.44  5086.5  250.74  5136.7  249.44
  5146.7  247.94  5156.7  248.16  5166.8  250.69  5174.3  251.37  5213.5  252.57
    5227  253.53  5387.5  258.72  5415.1  260.26  5487.3  261.97  5598.3     266
#Mann= 11 ,-1 , 0
  4285.6     .07       0  4420.2     .12       0  4501.8     .07       0
  4563.3     .12       0  4810.3     .07       0  4953.2     .12       0
  5014.3     .05       0  5018.3     .12       0  5213.5     .07       0
    5227     .12       0  5487.3     .07       0
Bank Sta=5014.3,5018.3
XS Rating Curve= 0 ,0
Exp/Cntr=0.3,0.1

Type RM Length L Ch R = 1 ,117143  ,505,505,505
BEGIN DESCRIPTION:
Mapping XS fc8a6621
END DESCRIPTION:
XS GIS Cut Line= 3
      2478082.03     13479860.42      2478377.17     13479148.63
      2478259.11     13478624.31
#Sta/Elev= 30
  4209.3  260.15  4283.7  258.98  4355.6   256.9  4434.5  255.72  4561.6  253.59
  4568.3   252.9  4726.9  250.81  4793.7   249.6  4843.1  247.71  4852.6  248.09
  4864.7  247.17  4873.5  245.66  4873.8  245.16  4877.3  245.16  4877.5  245.66
  4881.9  247.28  4887.3  247.85  4929.6   249.2  4993.8  247.29  5004.1     246
    5016  245.97  5024.6  247.26  5054.1  250.28  5059.2  249.91  5127.1  252.63
  5137.9  252.41  5195.1  254.07  5311.6  257.34  5512.4  261.34  5517.3  261.99
#Mann= 11 ,-1 , 0
  4209.3     .12       0  4283.7     .07       0  4434.5     .12       0
  4726.9     .07       0  4793.7     .12       0  4873.5     .07       0
  4877.5     .12       0  4993.8     .05       0  5024.6     .12       0
  5137.9     .07       0  5195.1     .12       0
Bank Sta=4993.8,5024.6
XS Rating Curve= 0 ,0
Exp/Cntr=0.3,0.1

Type RM Length L Ch R = 1 ,116638  ,451,451,451
BEGIN DESCRIPTION:
PERDIDO CREEK 160.0
END DESCRIPTION:
XS GIS Cut Line= 3
      2478274.98     13479975.03        2478675.       13479375.
        2478425.       13478575.
#Sta/Elev= 30
  4288.2  262.53  4310.8  262.37  4367.9  260.34  4494.3  257.22  4502.5  257.02
  4699.8  253.12  4806.5  251.06  4893.7  249.97  4957.6  247.37  4990.9  245.86
  5004.3  245.26  5004.6  244.76  5008.1  244.76  5008.3  245.26  5019.8  245.54
  5025.6  246.28  5039.5  246.46  5072.2  247.15  5090.5  246.62  5114.1  246.79
  5225.7  248.73  5230.9  248.02  5361.9  250.76  5379.9  250.96  5425.8   251.2
  5484.2  252.32  5533.7   253.6  5588.4  254.12  5658.4  255.05  5847.5  258.76
#Mann= 13 ,-1 , 0
  4288.2     .12       0  4494.3     .07       0  4502.5     .12       0
  4699.8     .07       0  4957.6     .12       0  4990.9    .035       0
  5004.3    .035       0  5008.3    .035       0  5039.5     .12       0
  5361.9     .07       0  5379.9     .12       0  5484.2     .07       0
  5588.4     .12       0
Bank Sta=5004.3,5008.3
XS Rating Curve= 0 ,0
Exp/Cntr=0.3,0.1

Type RM Length L Ch R = 1 ,116187  ,476,476,476
BEGIN DESCRIPTION:
PERDIDO CREEK 159.0
END DESCRIPTION:
XS GIS Cut Line= 3
        2479125.     13479824.99        2479075.       13479325.
        2478925.     13478525.02
#Sta/Elev= 30
  4497.2  257.07  4698.2  252.65  4718.3  251.75  4829.3  249.21  4846.4  249.06
  4893.6  247.39  4946.9  245.51  4959.5  245.51  4969.5  244.36  4977.5  241.88
  4977.8  241.38  4981.4  241.38  4981.6  241.88  4989.6  242.33  4997.2  243.76
  5009.9  244.56    5020  244.38  5031.1  242.52  5040.4  242.79  5060.7  244.39
  5078.5  246.99  5083.6  246.71  5091.3  247.65  5101.4  247.88  5121.8  247.46
  5136.2  246.14  5345.6     248  5624.6  252.67  5787.3  256.42  5813.6  257.49
#Mann= 5 ,-1 , 0
  4497.2     .07       0  4829.3    .035       0  4893.6     .05       0
  4977.5     .05       0  4981.6     .05       0
Bank Sta=4977.5,4981.6
XS Rating Curve= 0 ,0
Exp/Cntr=0.3,0.1

Type RM Length L Ch R = 1 ,115711  ,477,477,477
BEGIN DESCRIPTION:
PERDIDO CREEK 158.0
END DESCRIPTION:
XS GIS Cut Line= 3
      2480124.98     13479924.97        2479475.       13479125.
      2479025.01     13478325.02
#Sta/Elev= 30
  3969.3   264.9  4069.1  262.14  4102.5  260.73  4260.9  254.65  4267.3  254.77
  4310.5  253.69  4324.8  253.03  4345.6     253  4417.5  251.45  4440.7  251.29
  4481.4  249.53  4502.2  248.99  4594.9  247.75    4744  246.59  4786.7  246.25
  4834.7  245.14  4908.1  242.64  4941.2  242.06  4941.5  241.56  4945.1  241.56
  4945.4  242.06  4978.5  243.29  5051.4  242.86  5067.3  242.49    5089  242.72
    5138  244.28  5331.8  246.86  5614.5  253.63  5724.7  256.53  5917.9  262.42
#Mann= 9 ,-1 , 0
  3969.3     .05       0  4102.5    .035       0  4440.7     .05       0
    4744     .07       0  4834.7     .05       0  4941.2     .05       0
  4945.4     .05       0  5614.5    .035       0  5724.7     .05       0
Bank Sta=4941.2,4945.4
XS Rating Curve= 0 ,0
Exp/Cntr=0.3,0.1

Type RM Length L Ch R = 1 ,115234  ,470,470,470
BEGIN DESCRIPTION:
PERDIDO CREEK 157.0
END DESCRIPTION:
XS GIS Cut Line= 3
      2480575.03     13479625.03        2479775.       13478825.
      2479275.01     13478025.01
#Sta/Elev= 30
  3868.6  260.28  3939.4  258.56  4066.6  254.69  4080.8  255.16  4094.9  253.84
  4165.6  252.01  4462.6  245.48  4575.7  243.98  4745.5  242.94  4787.9  242.08
    4802  242.24  4872.7  241.45    4901  241.62  4943.4  240.64  4985.9  240.38
  4994.3  239.95  4994.6  239.45  4998.3  239.45  4998.6  239.95    5023  240.25
  5028.9  240.76  5050.1  240.37  5086.7  241.13  5123.2  242.33  5165.7  244.93
  5406.3  250.51  5646.8  257.78    5908  266.24  5914.5  266.72  5943.4  267.26
#Mann= 3 ,-1 , 0
  3868.6     .05       0  4994.3     .05       0  4998.6     .05       0
Bank Sta=4994.3,4998.6
XS Rating Curve= 0 ,0
Exp/Cntr=0.3,0.1

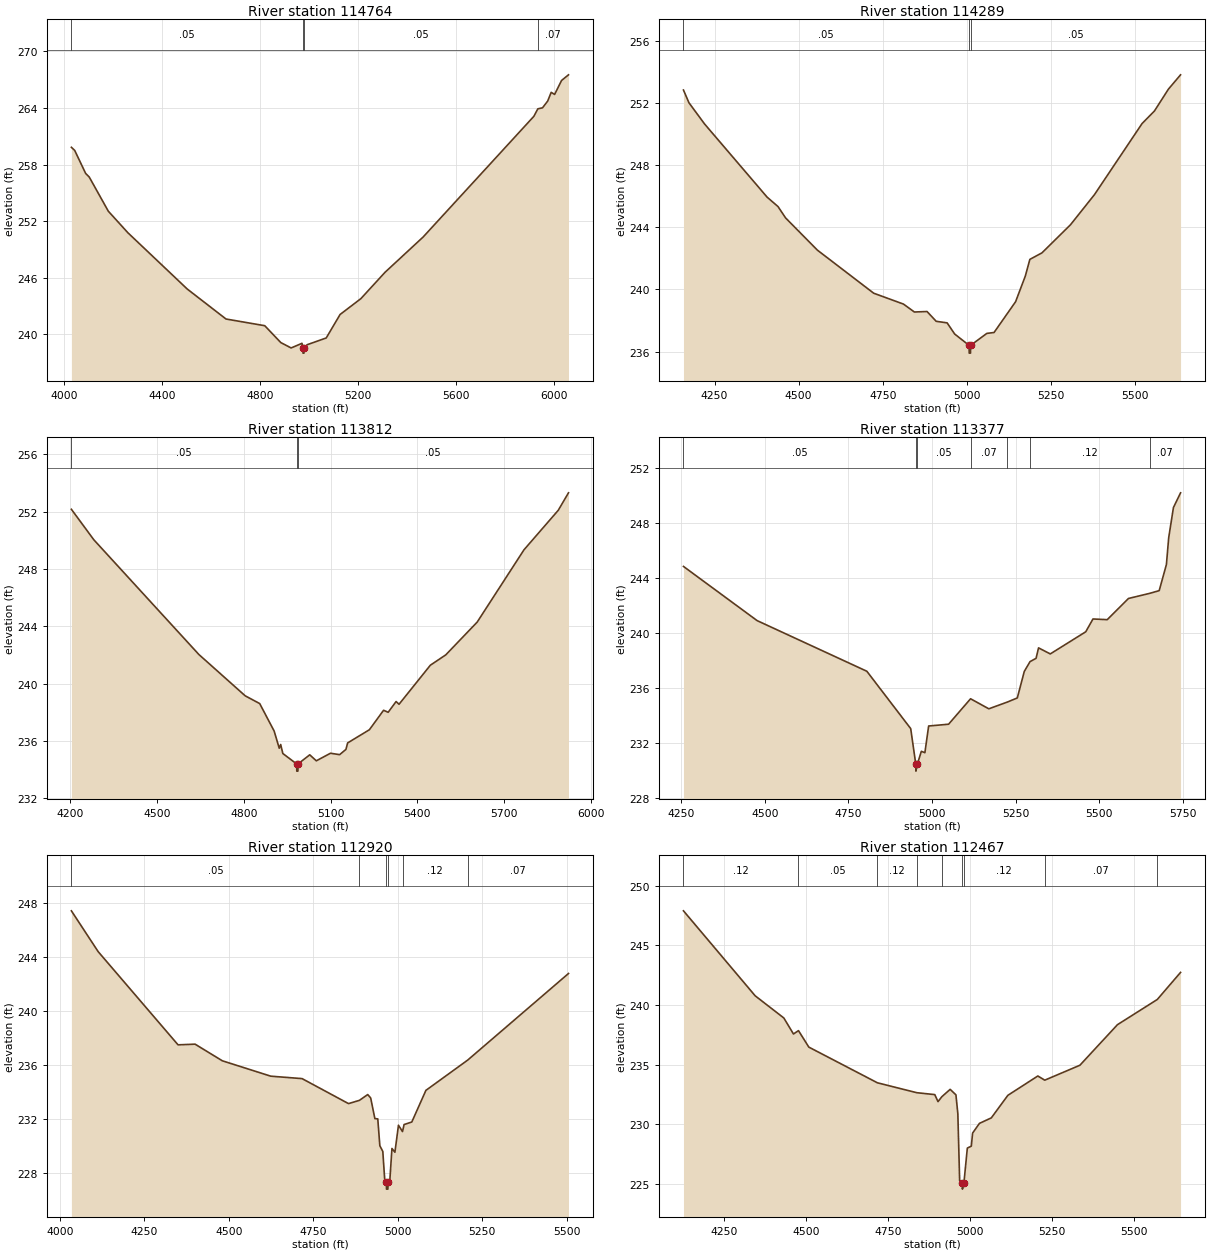
Type RM Length L Ch R = 1 ,114764  ,475,475,475
BEGIN DESCRIPTION:
PERDIDO CREEK 156.0
END DESCRIPTION:
XS GIS Cut Line= 3
        2480725.       13479425.        2480175.       13478625.
      2479424.99     13477874.99
#Sta/Elev= 30
  4029.4  259.83  4042.9   259.5  4087.6  257.06  4102.2  256.68  4180.3  253.05
    4260  250.77  4502.9  244.79  4661.3  241.61  4819.6   240.9  4885.2  239.11
  4927.4  238.54  4971.8  239.03  4975.7  238.49    4976  237.99  4979.8  237.99
  4980.1  238.49  4992.8  238.88  5070.9   239.6  5127.5  242.09  5212.4  243.77
  5311.3  246.57  5466.9  250.31  5919.5  263.12  5935.6  263.91  5954.8  264.02
    5976  264.74  5990.2  265.66  6004.3  265.44  6032.6  266.92  6060.9  267.52
#Mann= 4 ,-1 , 0
  4029.4     .05       0  4975.7     .05       0  4980.1     .05       0
  5935.6     .07       0
Bank Sta=4975.7,4980.1
XS Rating Curve= 0 ,0
Exp/Cntr=0.3,0.1

Type RM Length L Ch R = 1 ,114289  ,477,477,477
BEGIN DESCRIPTION:
PERDIDO CREEK 155.0
END DESCRIPTION:
XS GIS Cut Line= 3
        2480825.     13479225.02        2480575.       13478425.
      2480074.99     13478024.99
#Sta/Elev= 30
  4157.4  252.85  4173.7  252.03  4220.3  250.66  4406.2  245.95  4438.7  245.34
  4461.2  244.61  4555.5  242.54  4723.2  239.76  4811.7  239.06  4844.2  238.55
  4881.9  238.58  4909.1  237.95  4941.6  237.85  4964.1  237.13    5007   236.4
  5007.3   235.9  5011.1   235.9  5011.4   236.4  5059.6  237.17  5081.2  237.23
  5145.2  239.21  5174.1  240.86  5187.7  241.94  5223.7  242.36  5308.5  244.17
  5379.8  246.11  5521.4  250.69  5558.2   251.5  5599.9  252.91  5635.9  253.83
#Mann= 3 ,-1 , 0
  4157.4     .05       0    5007     .05       0  5011.4     .05       0
Bank Sta=5007,5011.4
XS Rating Curve= 0 ,0
Exp/Cntr=0.3,0.1

Type RM Length L Ch R = 1 ,113812  ,435,435,435
BEGIN DESCRIPTION:
PERDIDO CREEK 154.0
END DESCRIPTION:
XS GIS Cut Line= 3
        2481025.     13479174.98        2480975.       13478375.
      2480175.02     13477925.01
#Sta/Elev= 30
  4203.4  252.17    4281  250.04  4644.2  242.03  4804.6  239.14  4854.7   238.6
  4904.7  236.68  4922.3  235.48  4927.3  235.74  4934.8  235.11  4982.7  234.38
    4983  233.88  4986.9  233.88  4987.2  234.38  5027.9  235.02  5050.5   234.6
  5099.6  235.13  5131.2  235.03  5153.1   235.4  5158.9  235.85  5234.1  236.77
  5283.2  238.13  5299.1  237.99  5326.5  238.74  5336.7  238.55  5445.1  241.28
  5498.3     242    5607  244.29  5768.9  249.34  5887.4   252.1  5922.8  253.32
#Mann= 3 ,-1 , 0
  4203.4     .05       0  4982.7     .05       0  4987.2     .05       0
Bank Sta=4982.7,4987.2
XS Rating Curve= 0 ,0
Exp/Cntr=0.3,0.1

Type RM Length L Ch R = 1 ,113377  ,457,457,457
BEGIN DESCRIPTION:
PERDIDO CREEK 153.0
END DESCRIPTION:
XS GIS Cut Line= 3
      2481474.99     13478824.98        2481225.       13478125.
      2480724.99     13477574.99
#Sta/Elev= 30
  4256.7  244.82    4477  240.88  4805.1   237.2  4936.3  233.03  4951.5  230.44
  4951.8  229.94  4956.1  230.44  4968.1  231.38  4978.7  231.28  4989.9  233.22
  5049.6  233.35  5115.3   235.2  5169.9  234.47  5225.2  234.96  5255.1  235.26
    5276  237.19  5293.2   237.9  5311.2  238.14  5318.6   238.9  5353.7  238.46
  5459.8  240.07  5481.4     241    5524  240.95  5587.5  242.49  5650.5  242.86
  5679.4  243.06    5701  244.96  5707.8   246.9    5722   249.1  5743.3  250.17
#Mann= 7 ,-1 , 0
  4256.7     .05       0  4951.5     .05       0  4956.1     .05       0
  5115.3     .07       0  5225.2     .05       0  5293.2     .12       0
  5650.5     .07       0
Bank Sta=4951.5,4956.1
XS Rating Curve= 0 ,0
Exp/Cntr=0.3,0.1

Type RM Length L Ch R = 1 ,112920  ,453,453,453
BEGIN DESCRIPTION:
PERDIDO CREEK 152.0
END DESCRIPTION:
XS GIS Cut Line= 3
      2482075.02     13478725.03        2481525.       13477925.
      2481224.98     13477524.97
#Sta/Elev= 30
  4034.4  247.39  4113.6  244.37    4350  237.47  4400.4  237.52    4481  236.29
  4624.4  235.15    4717  234.97  4854.4  233.12  4886.6  233.36  4911.2  233.79
    4920  233.54  4932.4  232.01    4941  231.99  4947.1     230  4955.9  229.58
    4962  227.32  4966.5  227.29  4966.8  226.79  4970.9  226.79  4971.3  227.29
  4976.9  227.52  4982.9   229.8  4991.7  229.52  5002.2  231.52  5014.2  231.05
  5018.8  231.57  5041.7  231.76  5083.4   234.1    5207  236.34  5505.3  242.75
#Mann= 6 ,-1 , 0
  4034.4     .05       0  4886.6      .1       0  4966.5     .05       0
  4971.3      .1       0  5014.2     .12       0    5207     .07       0
Bank Sta=4966.5,4971.3
XS Rating Curve= 0 ,0
Exp/Cntr=0.3,0.1

Type RM Length L Ch R = 1 ,112467  ,727,727,727
BEGIN DESCRIPTION:
PERDIDO CREEK 151.0
END DESCRIPTION:
XS GIS Cut Line= 3
      2482275.01     13478675.01        2481925.       13477875.
      2481525.02     13477375.03
#Sta/Elev= 30
  4127.7   247.9    4346  240.78  4433.3  238.92  4462.6  237.58  4477.9  237.86
  4509.4  236.48  4718.2  233.49    4838  232.66  4892.9   232.5  4902.7  231.91
  4914.6  232.33  4939.7  232.94  4957.3  232.48  4963.1   230.9  4968.6  225.29
  4976.7  225.08    4977  224.58  4981.5  225.08    4992  228.02  5004.1  228.18
  5008.1  229.28  5028.9  230.09    5065  230.55  5115.4  232.44  5206.6  234.06
  5227.7  233.71  5334.7  234.96  5449.1  238.36  5570.3  240.47  5641.2  242.74
#Mann= 9 ,-1 , 0
  4127.7     .12       0  4477.9     .05       0  4718.2     .12       0
    4838      .1       0  4914.6     .12       0  4976.7     .05       0
  4981.5     .12       0  5227.7     .07       0  5570.3     .12       0
Bank Sta=4976.7,4981.5
XS Rating Curve= 0 ,0
Exp/Cntr=0.3,0.1

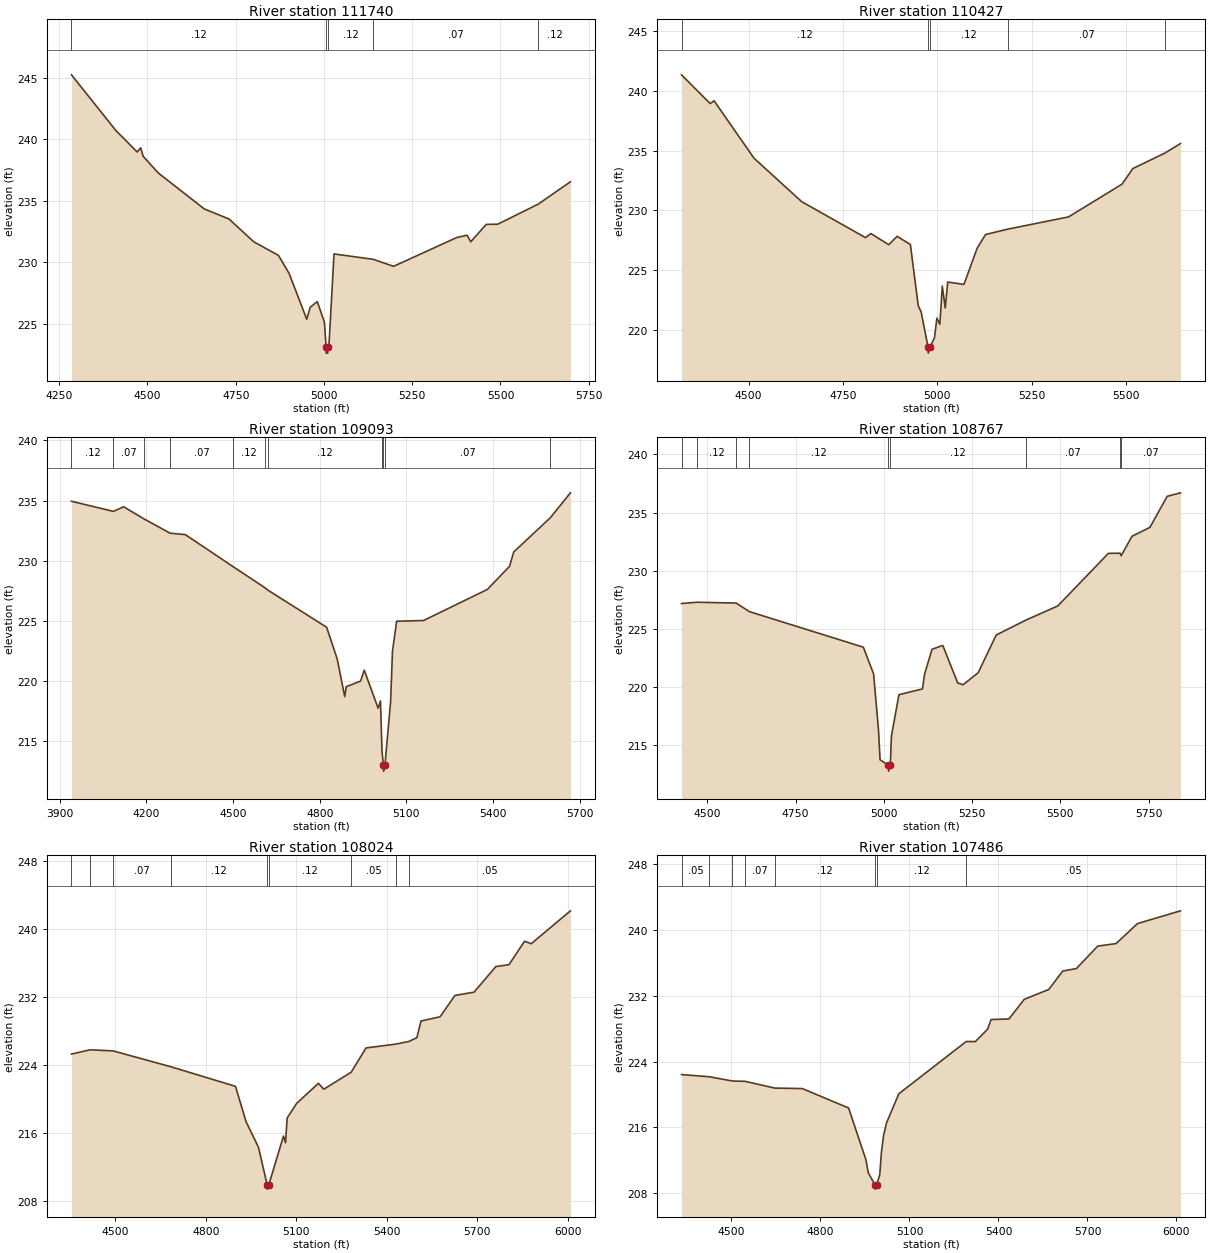
Type RM Length L Ch R = 1 ,111740  ,1313,1313,1313
BEGIN DESCRIPTION:
Mapping XS c661fdb4
END DESCRIPTION:
XS GIS Cut Line= 3
      2482443.14     13478540.95      2482467.44      13477815.3
      2482189.66     13477186.81
#Sta/Elev= 30
  4284.9  245.23  4410.9  240.69    4471  238.95    4481  239.29  4487.9   238.6
    4531  237.24  4661.1  234.32  4731.1   233.5  4801.1  231.65  4871.2  230.54
  4901.2  229.08  4951.2  225.35  4961.2  226.33  4981.2  226.78  5001.3  225.09
  5006.1  223.09  5006.5  222.59  5010.7  222.59  5011.1  223.09  5013.9  223.09
  5028.5  230.66  5139.7  230.22  5197.1  229.65  5376.6     232  5405.4  232.18
  5415.8  231.65  5459.6  233.06  5492.4  233.08  5607.4  234.72  5698.1  236.53
#Mann= 5 ,-1 , 0
  4284.9     .12       0  5006.1     .05       0  5011.1     .12       0
  5139.7     .07       0  5607.4     .12       0
Bank Sta=5006.1,5011.1
XS Rating Curve= 0 ,0
Exp/Cntr=0.3,0.1

Type RM Length L Ch R = 1 ,110427  ,1334,1334,1334
BEGIN DESCRIPTION:
Mapping XS ad5de7ed
END DESCRIPTION:
XS GIS Cut Line= 3
      2483179.23     13478026.85       2483005.6     13477510.31
      2482410.97     13477011.16
#Sta/Elev= 30
  4322.5  241.33  4398.3  238.93  4408.8  239.16  4514.3  234.37  4640.9  230.73
  4809.7  227.73  4823.9  228.07  4871.3  227.14  4893.4  227.84  4928.6  227.15
  4949.4  222.03  4957.2  221.51  4975.4  218.58  4975.8  218.08  4980.5  218.58
  4992.3  219.35  4998.8     221  5006.6  220.49  5013.1  223.68  5020.9  221.85
  5027.4  224.02  5070.4  223.82  5105.5  226.85  5127.6  227.99  5186.8  228.44
  5347.4  229.46  5489.2   232.2  5517.8   233.5  5602.9   234.8  5643.8  235.59
#Mann= 5 ,-1 , 0
  4322.5     .12       0  4975.4     .05       0  4980.5     .12       0
  5186.8     .07       0  5602.9     .12       0
Bank Sta=4975.4,4980.5
XS Rating Curve= 0 ,0
Exp/Cntr=0.3,0.1

Type RM Length L Ch R = 1 ,109093  ,326,326,326
BEGIN DESCRIPTION:
Mapping XS b16d57c8
END DESCRIPTION:
XS GIS Cut Line= 3
      2483668.62     13477921.58      2483324.87      13476921.6
      2482799.45     13476505.41
#Sta/Elev= 30
  3940.4  234.94  4085.2   234.1  4121.3  234.48  4190.5  233.49  4281.8  232.29
  4334.7  232.17  4498.2  229.54  4609.2  227.78  4619.4  227.58    4824  224.48
  4860.5  221.85  4886.5  218.73  4891.8  219.55  4941.3  220.01  4954.2  220.92
  5002.2  217.76  5010.3  218.37  5015.7  214.14  5020.6  213.04    5021  212.54
  5025.8  213.04  5045.5  218.33  5051.9  222.48  5066.3  224.98  5159.3  225.04
  5380.4  227.62  5457.3  229.54  5471.7  230.73  5598.4  233.57  5668.1  235.64
#Mann= 11 ,-1 , 0
  3940.4     .12       0  4085.2     .07       0  4190.5     .12       0
  4281.8     .07       0  4498.2     .12       0  4609.2     .07       0
  4619.4     .12       0  5015.7     .07       0  5020.6     .05       0
  5025.8     .07       0  5598.4     .12       0
Bank Sta=5020.6,5025.8
XS Rating Curve= 0 ,0
Exp/Cntr=0.3,0.1

Type RM Length L Ch R = 1 ,108767  ,743,743,743
BEGIN DESCRIPTION:
Mapping XS 786b987e
END DESCRIPTION:
XS GIS Cut Line= 3
      2484075.24     13477109.48      2483588.28     13476825.64
      2482872.13      13476367.3
#Sta/Elev= 30
  4426.6  227.17  4469.5  227.28  4581.4  227.21  4619.2  226.47  4941.9  223.41
  4970.9  221.11  4984.9  216.24  4989.2  213.72    5013  213.24  5013.4  212.74
  5018.2  213.24  5021.5  215.77  5042.7  219.32  5109.5  219.82  5115.4   221.1
  5136.6  223.23    5167  223.56  5209.3  220.33  5224.5  220.18  5267.2  221.21
  5318.4  224.46  5403.1  225.75  5492.8  226.96  5636.3  231.49  5669.3   231.5
  5672.5  231.28  5703.1  232.96    5754  233.73  5802.9   236.4  5840.5   236.7
#Mann= 9 ,-1 , 0
  4426.6    .035       0  4469.5     .12       0  4581.4     .07       0
  4619.2     .12       0    5013     .05       0  5018.2     .12       0
  5403.1     .07       0  5669.3     .05       0  5672.5     .07       0
Bank Sta=5013,5018.2
XS Rating Curve= 0 ,0
Exp/Cntr=0.3,0.1

Type RM Length L Ch R = 1 ,108024  ,538,538,538
BEGIN DESCRIPTION:
Mapping XS bbea2362
END DESCRIPTION:
XS GIS Cut Line= 3
      2484283.34     13476822.19      2483887.51     13476349.97
      2482901.39     13476023.58
#Sta/Elev= 30
  4354.1  225.32  4415.9  225.82  4492.4  225.69  4684.7  223.82    4898  221.53
  4933.2  217.37  4974.2  214.38  5003.2  209.95  5003.6  209.45  5008.5  209.95
  5057.2  215.69  5064.1   214.9  5069.3   217.8    5101  219.53  5173.1  221.88
  5190.9  221.19  5281.9  223.19  5331.1  226.04    5430  226.49    5473   226.8
  5499.6  227.24  5513.3   229.2  5576.7   229.7    5626  232.21  5689.2  232.59
  5761.7   235.6  5805.1  235.82  5856.9  238.58  5878.8  238.28    6009  242.15
#Mann= 9 ,-1 , 0
  4354.1    .035       0  4415.9     .05       0  4492.4     .07       0
  4684.7     .12       0  5003.2     .05       0  5008.5     .12       0
  5281.9     .05       0    5430     .12       0    5473     .05       0
Bank Sta=5003.2,5008.5
XS Rating Curve= 0 ,0
Exp/Cntr=0.3,0.1

Type RM Length L Ch R = 1 ,107486  ,272,272,272
BEGIN DESCRIPTION:
Mapping XS 06f443d6
END DESCRIPTION:
XS GIS Cut Line= 3
      2484443.83     13476515.29      2484137.51      13475933.3
      2483144.47     13475683.31
#Sta/Elev= 30
  4331.7  222.42    4425  222.16  4503.1  221.64  4545.6   221.6  4645.6  220.78
  4738.9  220.72  4894.8  218.36  4953.6  212.03  4960.9  210.51    4984     209
  4984.5   208.5  4989.4     209    5000   210.3  5005.2  212.88  5012.6  215.01
  5022.9  216.57  5064.2  220.09  5291.3  226.44    5322  226.43  5363.2  227.93
  5375.1  229.11  5435.4  229.18  5486.9  231.57  5569.4  232.76  5616.6     235
  5662.9  235.31  5734.4  238.03  5796.3  238.34  5868.5  240.77  6013.4  242.32
#Mann= 8 ,-1 , 0
  4331.7     .05       0    4425     .07       0  4503.1     .05       0
  4545.6     .07       0  4645.6     .12       0    4984     .05       0
  4989.4     .12       0  5291.3     .05       0
Bank Sta=4984,4989.4
XS Rating Curve= 0 ,0
Exp/Cntr=0.3,0.1