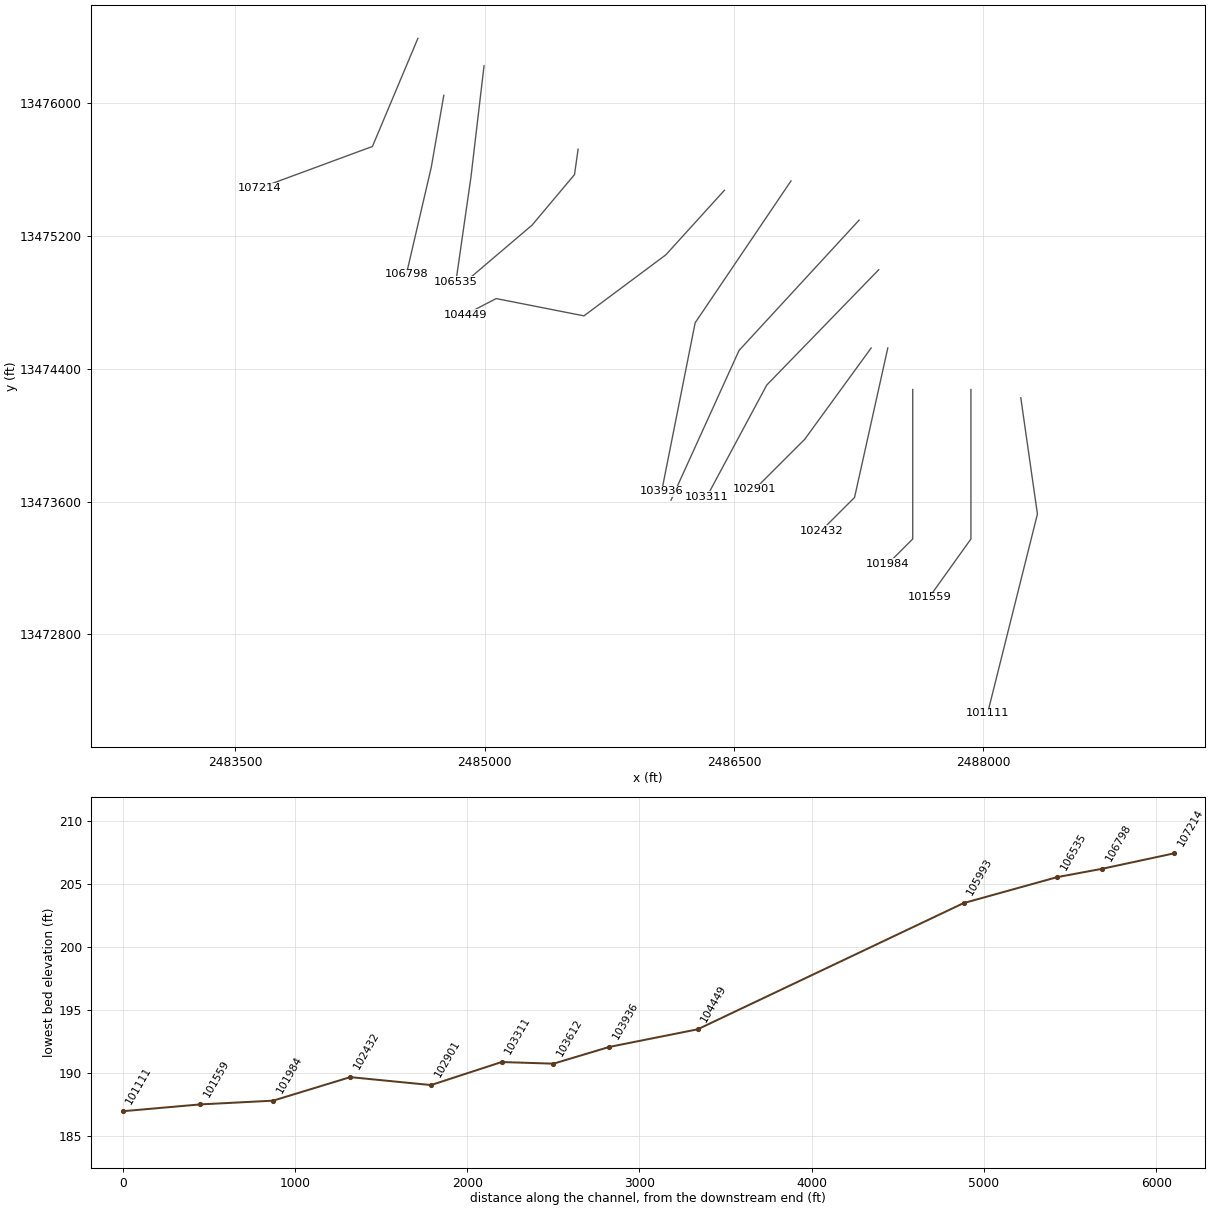
HEC-RAS study PERDIDO CREEK.prj: PERDIDO CREEK Base Level Engineering

--- PERDIDO CREEK.g01 (geometry) --- (continued)

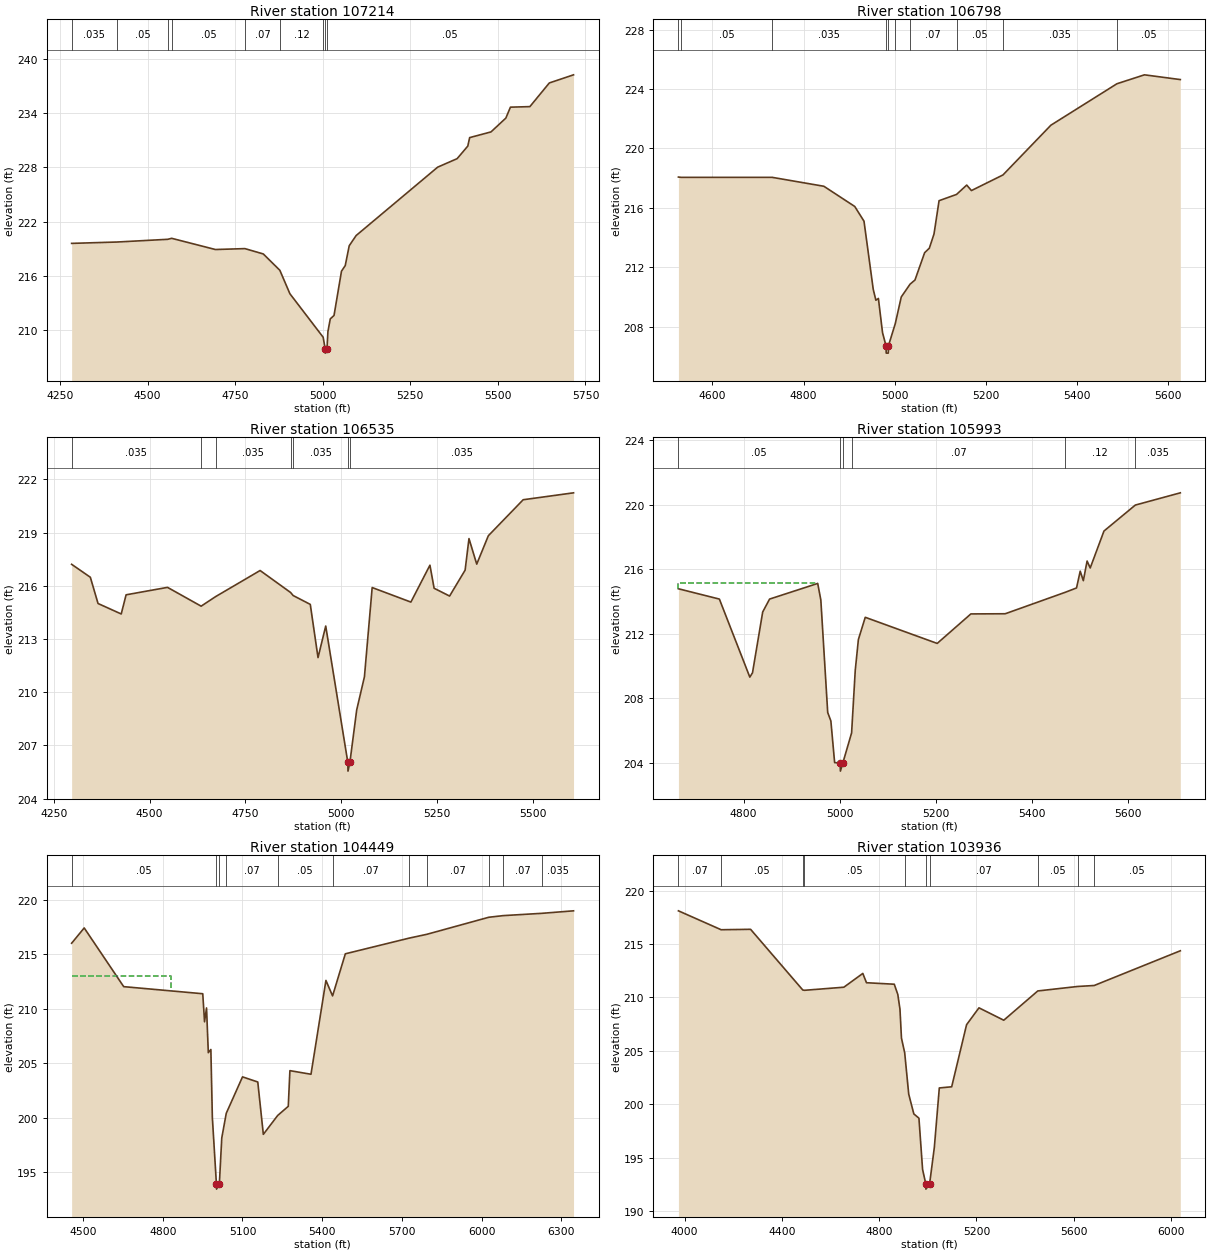
Type RM Length L Ch R = 1 ,107214  ,416,416,416
BEGIN DESCRIPTION:
Mapping XS c154a216
END DESCRIPTION:
XS GIS Cut Line= 3
      2484598.55     13476389.32      2484325.13     13475738.31
      2483643.74     13475486.59
#Sta/Elev= 30
  4283.4  219.59  4413.2  219.74  4557.6  220.04    4569  220.15  4693.8  218.91
    4778  219.01  4830.4  218.42  4877.7  216.61  4906.3  214.02  5001.3   209.2
  5006.9  207.94  5007.3  207.44  5012.3  207.94  5014.9  209.83  5021.6  211.23
  5032.3  211.61  5053.6  216.51  5064.3  217.13  5075.7  219.33  5095.5  220.46
  5328.2  228.03  5383.7  228.97  5414.1  230.36  5419.4   231.3  5480.3  231.93
  5522.7  233.46  5535.8  234.67  5591.3  234.73  5646.8  237.35  5715.9  238.25
#Mann= 9 ,-1 , 0
  4283.4    .035       0  4413.2     .05       0  4557.6     .07       0
    4569     .05       0    4778     .07       0  4877.7     .12       0
  5001.3     .05       0  5006.9     .05       0  5012.3     .05       0
Bank Sta=5006.9,5012.3
XS Rating Curve= 0 ,0
Exp/Cntr=0.3,0.1

Type RM Length L Ch R = 1 ,106798  ,263,263,263
BEGIN DESCRIPTION:
Mapping XS 55a94ca7
END DESCRIPTION:
XS GIS Cut Line= 3
      2484754.41     13476046.41      2484679.17     13475613.86
      2484529.12     13474968.32
#Sta/Elev= 30
  4525.2  218.07  4531.2  218.05  4731.1  218.05  4844.5  217.45  4912.3  216.09
  4932.6   215.1  4952.9  210.51  4958.7  209.78  4964.2   209.9  4973.3  207.59
  4980.9  206.72  4981.4  206.22  4985.9  206.22  4986.3  206.72  5001.3  208.21
  5014.4     210  5033.7  210.86  5044.5  211.14  5065.7  212.98    5076  213.28
  5086.3  214.24  5097.4  216.48  5135.7   216.9  5158.1  217.53  5168.4  217.16
  5237.6  218.21  5342.9  221.56  5487.9  224.35  5548.3  224.95    5627  224.63
#Mann= 10 ,-1 , 0
  4525.2     .07       0  4531.2     .05       0  4731.1    .035       0
  4980.9    .035       0  4986.3    .035       0  5001.3     .05       0
  5033.7     .07       0  5135.7     .05       0  5237.6    .035       0
  5487.9     .05       0
Bank Sta=4980.9,4986.3
XS Rating Curve= 0 ,0
Exp/Cntr=0.3,0.1

Type RM Length L Ch R = 1 ,106535  ,542,542,542
BEGIN DESCRIPTION:
Mapping XS 2627a75b
END DESCRIPTION:
XS GIS Cut Line= 3
       2484996.3     13476223.48       2484917.6     13475553.37
      2484827.33     13474924.93
#Sta/Elev= 30
  4296.6  217.21  4345.4  216.48  4365.5     215    4426  214.41  4438.7  215.49
  4546.8  215.91  4634.5  214.85  4672.4  215.39  4788.4  216.86    4868  215.62
  4874.6  215.45  4919.3  214.95  4939.5  211.95  4959.6  213.73  5017.2  206.05
  5017.7  205.55  5022.7  206.05  5040.4     209  5060.6  210.87  5080.8   215.9
  5181.8  215.08  5231.5  217.16  5242.4  215.86  5282.8  215.42  5323.3  216.88
  5333.4  218.66  5353.6  217.22  5383.9  218.82  5474.8  220.85  5606.2  221.24
#Mann= 7 ,-1 , 0
  4296.6    .035       0  4634.5    .063       0  4672.4    .035       0
    4868     .05       0  4874.6    .035       0  5017.2    .035       0
  5022.7    .035       0
#XS Ineff= 2 , 0
       0  4788.4  216.86               0
Permanent Ineff=
       F       F
Bank Sta=5017.2,5022.7
XS Rating Curve= 0 ,0
Exp/Cntr=0.3,0.1

Type RM Length L Ch R = 1 ,105993  ,1544,1544,1544
BEGIN DESCRIPTION:
Mapping XS 1710ab42
END DESCRIPTION:
XS GIS Cut Line= 4
      2485562.19     13475722.09      2485540.64     13475569.03
      2485285.37     13475264.74      2484910.63     13474945.71
#Sta/Elev= 30
  4664.5   214.8  4749.7  214.16    4813  209.32  4818.6  209.59  4839.8  213.36
  4854.1  214.16  4954.2  215.13  4960.7  214.11    4975  207.13  4981.6   206.6
  4989.4  204.02  5000.9  203.99  5001.4  203.49  5006.4  203.99  5024.7  205.86
  5032.3  209.74  5038.8  211.65  5053.1  213.03  5202.7  211.41  5272.8  213.24
  5344.2  213.25    5469  214.58  5492.5  214.85  5500.2  215.89  5506.7   215.3
  5514.5  216.52    5521  216.09  5549.6  218.38  5614.8  219.99  5708.4  220.75
#Mann= 6 ,-1 , 0
  4664.5     .05       0  5000.9     .05       0  5006.4     .05       0
  5024.7     .07       0    5469     .12       0  5614.8    .035       0
#XS Ineff= 2 , 0
       0  4954.2  215.13               0
Permanent Ineff=
       F       F
Bank Sta=5000.9,5006.4
XS Rating Curve= 0 ,0
Exp/Cntr=0.3,0.1

Type RM Length L Ch R = 1 ,104449  ,513,513,513
BEGIN DESCRIPTION:
Mapping XS 7cefcad2
END DESCRIPTION:
XS GIS Cut Line= 5
      2486442.27     13475474.42       2486090.5     13475086.38
      2485597.44     13474718.33      2485069.67     13474822.49
      2484882.16     13474725.27
#Sta/Elev= 30
  4457.4     216  4504.7   217.4  4653.3  212.02  4950.7  211.37  4957.4   208.8
  4964.9  210.07  4971.6  205.97  4981.2  206.26  4986.8  200.03    5002  193.96
  5002.5  193.46  5013.2  193.96  5022.2  198.15  5039.1  200.41  5100.3  203.75
  5157.7  203.28  5178.6  198.48  5232.5  200.21  5272.4  201.05  5278.6  204.32
  5357.9  203.99  5414.1  212.59  5439.1  211.17  5487.1  215.03  5725.8  216.46
  5794.2  216.82  6026.8  218.38    6081  218.53  6226.1  218.74  6345.6  218.97
#Mann= 11 ,-1 , 0
  4457.4     .05       0    5002     .05       0  5013.2     .05       0
  5039.1     .07       0  5232.5     .05       0  5439.1     .07       0
  5725.8     .05       0  5794.2     .07       0  6026.8     .12       0
    6081     .07       0  6226.1    .035       0
#XS Ineff= 2 , 0
       0  4830.4  212.99               0
Permanent Ineff=
       F       F
Bank Sta=5002,5013.2
XS Rating Curve= 0 ,0
Exp/Cntr=0.3,0.1

Type RM Length L Ch R = 1 ,103936  ,324,324,324
BEGIN DESCRIPTION:
Mapping XS 80d6316c
END DESCRIPTION:
XS GIS Cut Line= 3
      2486842.71     13475530.87      2486266.31     13474676.69
      2486064.91     13473662.77
#Sta/Elev= 30
  3974.4  218.11  4150.1  216.34  4271.2  216.38  4485.8   210.7  4492.4  210.67
  4654.8  210.96  4732.8  212.25  4747.8  211.38  4862.1  211.24  4876.7  210.28
  4885.6   208.9  4891.7   206.2    4905  204.83  4921.6  200.95  4942.6   199.1
  4963.6   198.7  4978.6   193.9  4991.7  192.56  4992.2  192.06  5007.5  192.56
    5027  195.98  5047.4  201.53  5098.3  201.64  5159.5  207.45  5210.5  209.03
  5312.5  207.87  5452.4  210.61  5616.7  211.03  5684.4  211.12  6038.6  214.37
#Mann= 10 ,-1 , 0
  3974.4     .07       0  4150.1     .05       0  4485.8    .035       0
  4492.4     .05       0    4905     .07       0  4991.7     .05       0
  5007.5     .07       0  5452.4     .05       0  5616.7     .07       0
  5684.4     .05       0
Bank Sta=4991.7,5007.5
XS Rating Curve= 0 ,0
Exp/Cntr=0.3,0.1

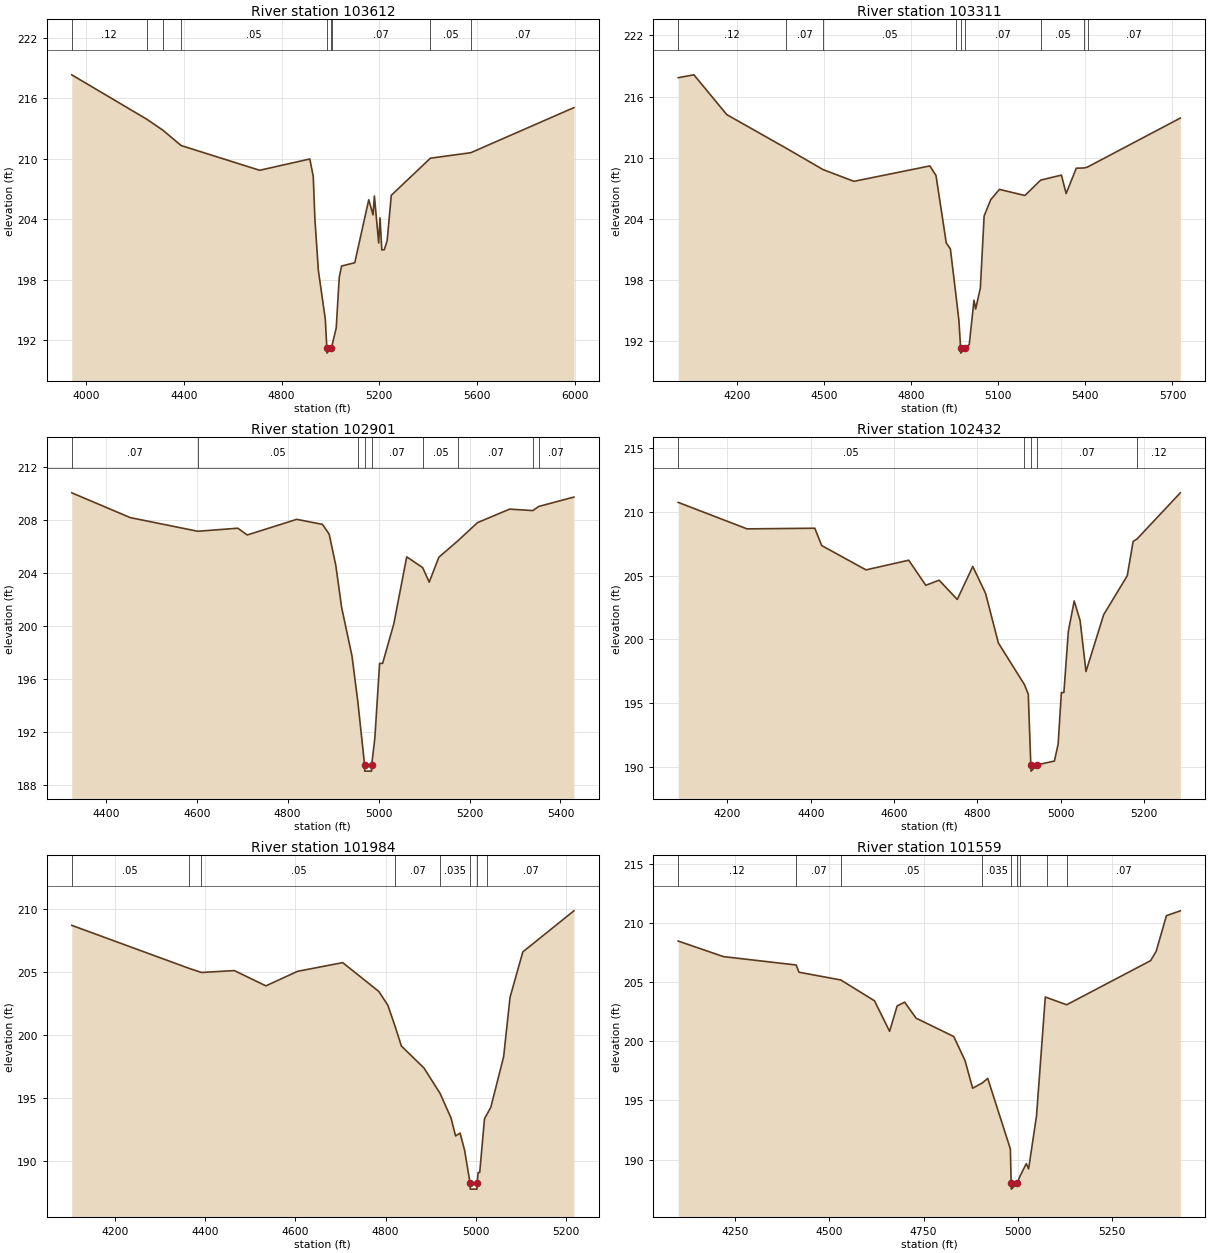
Type RM Length L Ch R = 1 ,103612  ,301,301,301
BEGIN DESCRIPTION:
Mapping XS 22bc5743
END DESCRIPTION:
XS GIS Cut Line= 3
      2487252.41     13475294.74       2486530.2     13474510.02
      2486121.09     13473608.59
#Sta/Elev= 30
  3940.6  218.31  4247.9  213.91  4312.7  212.84  4388.7   211.3  4710.1  208.85
  4915.4  209.97  4929.5  208.26  4936.3  204.01  4950.5  198.93  4978.9  194.09
  4985.2  191.23  4985.7  190.73    5001  191.23  5004.9  191.35  5023.6  193.22
  5035.9  198.21  5045.5  199.36  5099.6  199.69  5156.8  205.93  5174.4  204.43
  5179.9   206.3  5197.5  201.64    5203  204.14  5210.3  200.96  5220.5  200.98
  5232.2  201.88  5249.1  206.37  5409.4  210.05  5574.5  210.59    5997  215.06
#Mann= 9 ,-1 , 0
  3940.6     .12       0  4247.9    .035       0  4312.7     .12       0
  4388.7     .05       0  4985.2     .05       0    5001     .05       0
  5004.9     .07       0  5409.4     .05       0  5574.5     .07       0
Bank Sta=4985.2,5001
XS Rating Curve= 0 ,0
Exp/Cntr=0.3,0.1

Type RM Length L Ch R = 1 ,103311  ,410,410,410
BEGIN DESCRIPTION:
Mapping XS 9372efb0
END DESCRIPTION:
XS GIS Cut Line= 3
      2487370.51     13474996.17      2486696.86     13474301.69
      2486336.28     13473629.06
#Sta/Elev= 30
  3996.4  217.86  4050.7  218.14  4163.9  214.24  4369.7  210.93  4495.8  208.85
  4602.2   207.7  4863.8  209.21  4885.1  208.27  4920.4  201.66  4934.6  201.08
  4954.6  196.36  4963.9  194.09  4969.9  191.36  4970.4  190.86  4985.7  191.36
  4999.7  191.71    5016  196.05  5021.7  195.18  5037.9  197.24  5050.9   204.3
  5073.6   205.9  5103.7  206.91  5191.4  206.31  5245.8  207.82  5317.3  208.31
  5333.6   206.5  5368.6  208.99    5395  209.01  5407.3   209.1  5727.1   213.9
#Mann= 9 ,-1 , 0
  3996.4     .12       0  4369.7     .07       0  4495.8     .05       0
  4954.6     .07       0  4969.9     .05       0  4985.7     .07       0
  5245.8     .05       0    5395     .12       0  5407.3     .07       0
Bank Sta=4969.9,4985.7
XS Rating Curve= 0 ,0
Exp/Cntr=0.3,0.1

Type RM Length L Ch R = 1 ,102901  ,469,469,469
BEGIN DESCRIPTION:
PERDIDO CREEK 135.0
END DESCRIPTION:
XS GIS Cut Line= 3
      2487324.99     13474524.98        2486925.       13473975.
      2486625.01     13473675.01
#Sta/Elev= 30
  4325.2  210.03  4453.8  208.16  4602.2  207.13  4690.3  207.36  4711.2  206.85
  4819.8  208.03  4876.6  207.65  4891.3  206.91  4905.9  204.55  4918.7  201.38
  4941.5  197.71  4954.2   194.3  4969.1  189.53  4969.6  189.03  4984.4  189.03
  4984.9  189.53  4991.7  191.51  5002.2  197.16  5008.8  197.16  5033.5  200.15
  5061.8   205.2  5096.9  204.39  5111.3  203.29  5132.5  205.17    5175  206.43
  5217.4  207.78  5288.1   208.8  5339.2  208.69    5352     209  5429.5  209.71
#Mann= 9 ,-1 , 0
  4325.2     .07       0  4602.2     .05       0  4954.2     .07       0
  4969.1     .05       0  4984.9     .07       0  5096.9     .05       0
    5175     .07       0  5339.2     .12       0    5352     .07       0
Bank Sta=4969.1,4984.9
XS Rating Curve= 0 ,0
Exp/Cntr=0.3,0.1

Type RM Length L Ch R = 1 ,102432  ,448,448,448
BEGIN DESCRIPTION:
PERDIDO CREEK 134.0
END DESCRIPTION:
XS GIS Cut Line= 3
        2487425.     13474524.98        2487225.       13473625.
      2487024.98     13473424.98
#Sta/Elev= 30
  4081.9  210.76  4247.1  208.68  4409.7  208.73  4426.3  207.37  4532.6  205.46
  4635.1  206.22    4676  204.25    4708  204.65  4751.6  203.14  4788.7  205.73
  4819.4  203.62  4850.2  199.72  4912.6  196.46  4921.9  195.71    4928  190.16
  4928.5  189.66  4943.9  190.16  4984.6  190.45  4993.6  191.78  5001.3  195.83
  5007.4  195.83    5018  200.62  5032.1  203.02  5046.3  201.48  5060.4  197.48
  5102.8  201.94  5159.4     205  5173.5  207.69  5183.2   207.9  5286.7  211.51
#Mann= 5 ,-1 , 0
  4081.9     .05       0  4912.6     .07       0    4928     .05       0
  4943.9     .07       0  5183.2     .12       0
Bank Sta=4928,4943.9
XS Rating Curve= 0 ,0
Exp/Cntr=0.3,0.1

Type RM Length L Ch R = 1 ,101984  ,425,425,425
BEGIN DESCRIPTION:
PERDIDO CREEK 133.0
END DESCRIPTION:
XS GIS Cut Line= 3
        2487575.     13474274.96        2487575.       13473375.
        2487425.       13473225.
#Sta/Elev= 30
  4104.8  208.67  4363.5  205.28  4392.1  204.94  4464.8  205.09  4534.8  203.88
  4604.8  205.03  4704.8  205.72  4784.8  203.44  4804.8  202.35  4821.7  200.59
  4834.8  199.12  4884.8  197.38  4920.3  195.38  4944.8  193.42  4954.8     192
  4964.8  192.23  4974.8  190.87  4986.8  188.29  4987.3  187.79  5002.2  187.79
  5002.7  188.29  5004.8  189.11  5008.3  189.11  5018.9  193.36  5025.4  193.78
    5033  194.28  5061.3  198.28  5075.5  202.98  5103.8  206.57  5216.9  209.82
#Mann= 8 ,-1 , 0
  4104.8     .05       0  4363.5     .07       0  4392.1     .05       0
  4821.7     .07       0  4920.3    .035       0  4986.8    .035       0
  5002.7    .035       0  5025.4     .07       0
Bank Sta=4986.8,5002.7
XS Rating Curve= 0 ,0
Exp/Cntr=0.3,0.1

Type RM Length L Ch R = 1 ,101559  ,448,448,448
BEGIN DESCRIPTION:
PERDIDO CREEK 132.0
END DESCRIPTION:
XS GIS Cut Line= 3
        2487925.     13474275.02        2487925.       13473375.
      2487675.02     13473025.03
#Sta/Elev= 30
    4100  208.51    4220  207.19  4412.6  206.48    4420  205.87  4530.8  205.21
    4620  203.45    4660  200.86    4680  203.01    4700  203.33    4730  201.98
    4830  200.42    4860  198.37    4880  196.04  4905.7  196.49    4920  196.87
    4980  190.89    4982  187.99  4982.5  187.49    4998  187.99  5005.3  188.58
  5022.1  189.65  5028.3  189.21  5049.2  193.69  5072.5  203.77  5076.7  203.72
  5129.1  203.11  5351.5  206.85  5366.2  207.64  5393.3  210.66  5430.1  211.07
#Mann= 9 ,-1 , 0
    4100     .12       0  4412.6     .07       0  4530.8     .05       0
  4905.7    .035       0    4982    .035       0    4998    .035       0
  5005.3     .07       0  5076.7    .035       0  5129.1     .07       0
Bank Sta=4982,4998
XS Rating Curve= 0 ,0
Exp/Cntr=0.3,0.1

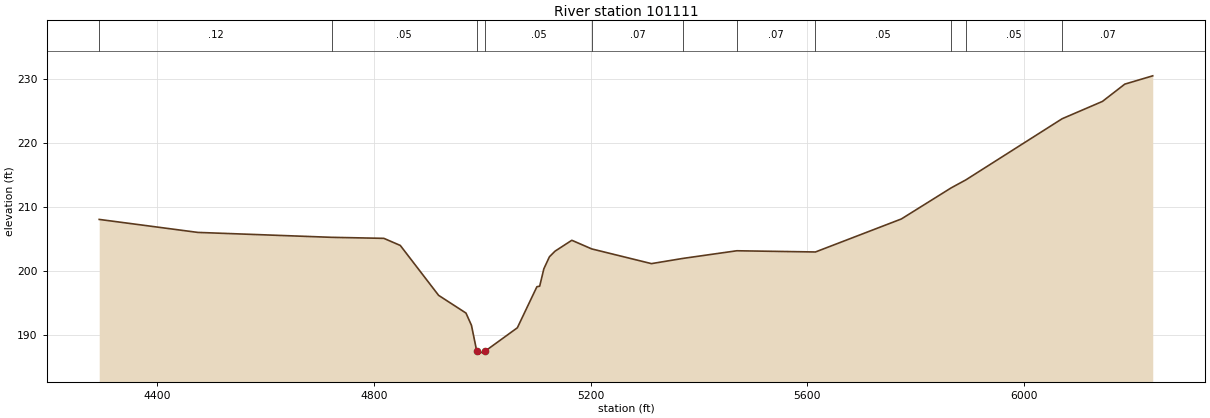
Type RM Length L Ch R = 1 ,101111  ,1210,1210,1210
BEGIN DESCRIPTION:
PERDIDO CREEK 131.0
END DESCRIPTION:
XS GIS Cut Line= 3
      2488224.99     13474225.04        2488325.       13473525.
        2488025.     13472324.98
#Sta/Elev= 30
  4293.3  208.01  4475.2  205.98  4722.4  205.21  4818.6  205.05  4848.9  203.94
  4919.6  196.14  4970.1  193.37  4980.2  191.46  4989.9  187.45  4990.4  186.95
    5006  187.45  5064.9  191.07    5101  197.49  5106.1  197.57  5113.8  200.29
  5124.1  202.17  5134.5  203.05  5165.4  204.75  5202.1   203.4  5312.3   201.1
  5370.9  201.92  5469.9  203.11    5615  202.92  5773.5  208.08  5865.4  212.94
  5892.7   214.2  6070.2  223.75  6144.6  226.46  6185.8  229.16  6237.4  230.46
#Mann= 11 ,-1 , 0
  4293.3     .12       0  4722.4     .05       0  4989.9     .05       0
    5006     .05       0  5202.1     .07       0  5370.9     .05       0
  5469.9     .07       0    5615     .05       0  5865.4     .12       0
  5892.7     .05       0  6070.2     .07       0
Bank Sta=4989.9,5006
XS Rating Curve= 0 ,0
Exp/Cntr=0.3,0.1