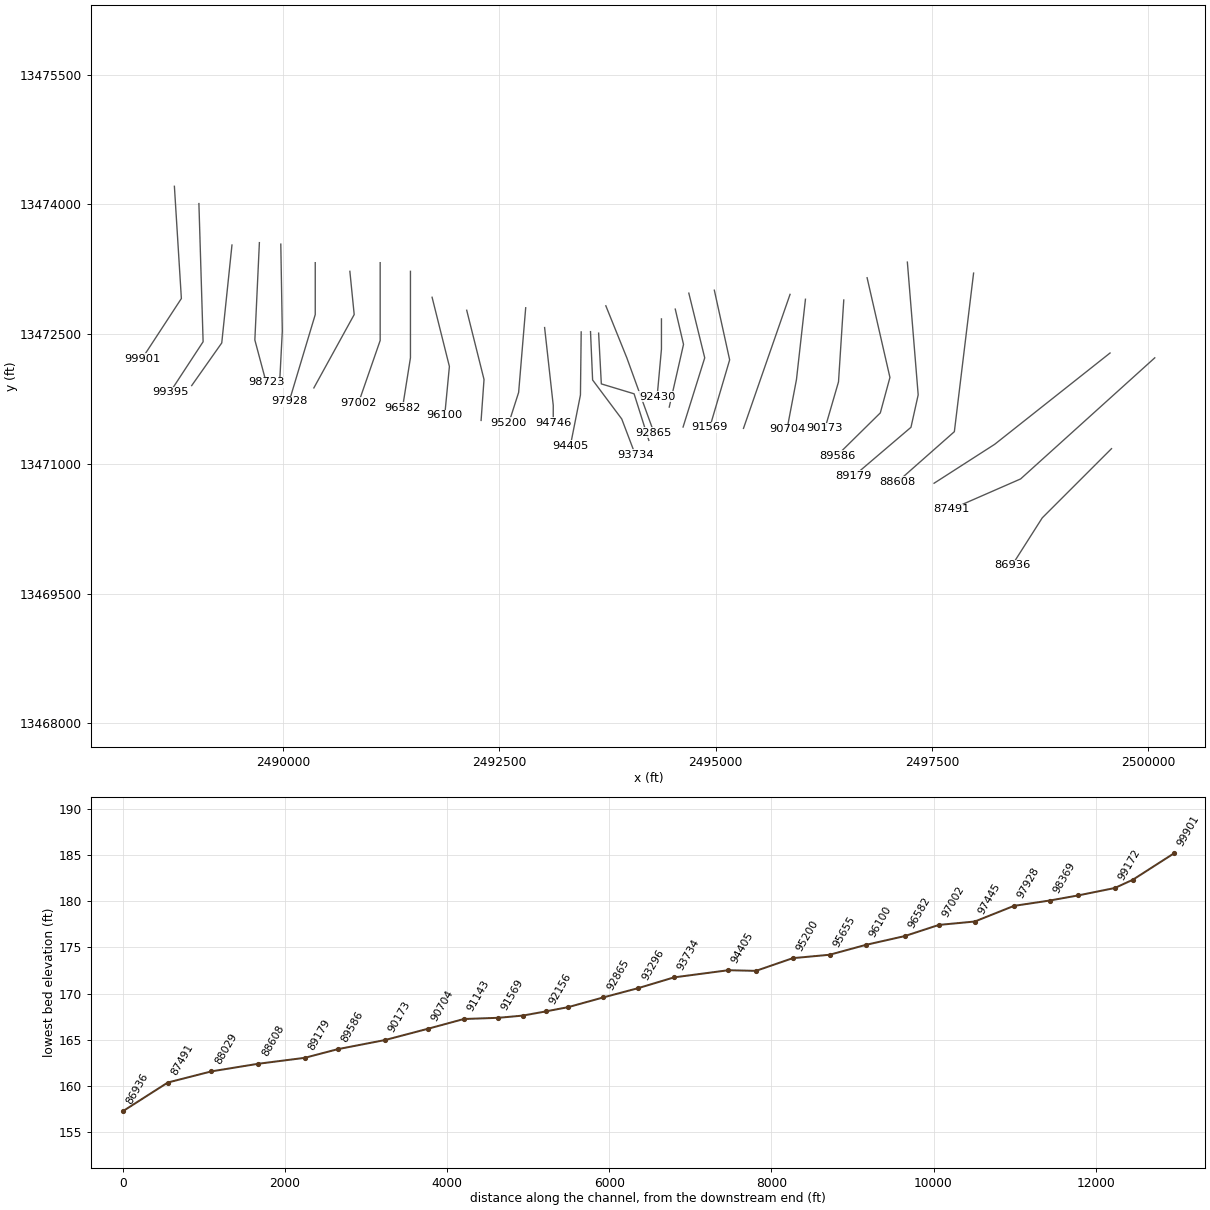
HEC-RAS study PERDIDO CREEK.prj: PERDIDO CREEK Base Level Engineering

--- PERDIDO CREEK.g01 (geometry) --- (continued)

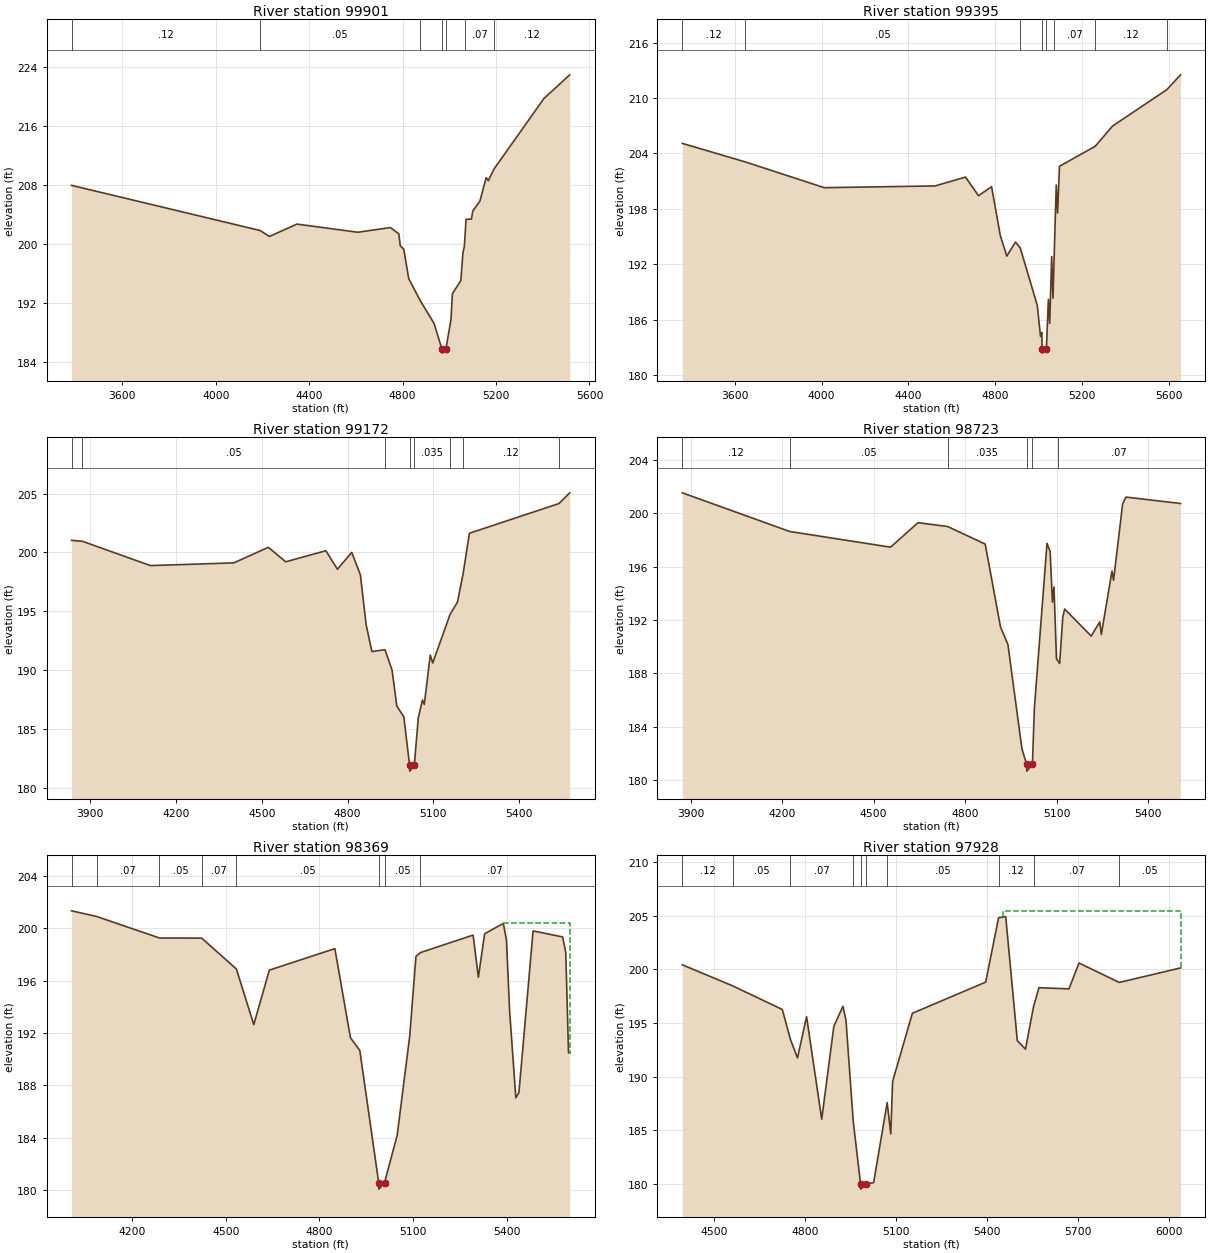
Type RM Length L Ch R = 1 ,99901   ,506,506,506
BEGIN DESCRIPTION:
Mapping XS 75a1fac7
END DESCRIPTION:
XS GIS Cut Line= 3
      2488747.54      13474208.1      2488828.26     13472910.75
      2488372.52     13472213.31
#Sta/Elev= 30
  3382.5  207.97  4189.5  201.85  4229.7  201.04  4347.5  202.72    4608  201.61
  4747.6  202.25  4783.8  201.39  4789.8   199.8  4804.9   199.3    4826  195.33
  4875.7  192.32  4934.6  189.25  4968.6  185.72  4969.1  185.22    4985  185.72
    5007  189.79    5013  193.27  5049.2  195.06  5058.3  198.85  5064.3   199.7
  5068.6  201.89  5071.5  203.36  5094.5   203.4  5100.5   204.5  5130.7  205.82
  5157.8  209.02  5166.9   208.6  5191.1  210.18  5405.2  219.76  5515.5  222.96
#Mann= 7 ,-1 , 0
  3382.5     .12       0  4189.5     .05       0  4875.7    .035       0
  4968.6    .035       0    4985    .035       0  5068.6     .07       0
  5191.1     .12       0
Bank Sta=4968.6,4985
XS Rating Curve= 0 ,0
Exp/Cntr=0.3,0.1

Type RM Length L Ch R = 1 ,99395   ,223,223,223
BEGIN DESCRIPTION:
Mapping XS 1b5a4fcb
END DESCRIPTION:
XS GIS Cut Line= 3
      2489030.81     13474008.23      2489079.42     13472410.97
      2488698.27     13471828.85
#Sta/Elev= 30
  3358.8  205.09  3647.6  203.09  4012.3  200.29  4522.6  200.48  4662.6  201.44
  4722.7  199.42  4782.7   200.4  4822.7  195.13  4852.7  192.87  4892.7   194.4
  4914.8  193.75    4993  187.55  5008.1  184.17  5014.1   184.6    5015  182.86
  5015.5  182.36  5031.4  182.86  5035.7  183.14  5044.3  188.18  5050.3  185.58
  5059.4  192.83  5065.4  188.32  5069.1  191.43  5080.5  200.58  5086.5  197.54
  5095.4  202.61  5259.6  204.77  5339.8  206.97  5589.5  210.91  5652.6  212.52
#Mann= 8 ,-1 , 0
  3358.8     .12       0  3647.6     .05       0  4914.8    .035       0
    5015    .035       0  5031.4    .035       0  5069.1     .07       0
  5259.6     .12       0  5589.5     .07       0
Bank Sta=5015,5031.4
XS Rating Curve= 0 ,0
Exp/Cntr=0.3,0.1

Type RM Length L Ch R = 1 ,99172   ,449,449,449
BEGIN DESCRIPTION:
Mapping XS 9c918dc0
END DESCRIPTION:
XS GIS Cut Line= 3
      2489412.76     13473529.04       2489294.7     13472397.08
      2488947.51     13471904.07
#Sta/Elev= 30
  3835.4  201.03  3873.5  200.95  4110.9  198.89  4402.5  199.12  4523.2  200.44
  4583.5  199.21  4724.2  200.15  4764.5  198.58  4814.7  200.01  4844.9  198.09
    4865  193.86  4885.1   191.6  4930.8  191.76  4955.5  190.03    4972  186.98
  4996.7  186.06  5016.7  181.96  5017.2  181.46  5033.2  181.96  5047.2  185.99
  5061.7  187.49  5068.1  187.12  5089.1   191.3  5097.7  190.63    5158  194.74
    5184  195.79  5203.7  198.18  5225.8  201.63  5538.7  204.15  5576.5  205.06
#Mann= 8 ,-1 , 0
  3835.4     .12       0  3873.5     .05       0  4930.8    .035       0
  5016.7    .035       0  5033.2    .035       0    5158     .07       0
  5203.7     .12       0  5538.7     .07       0
Bank Sta=5016.7,5033.2
XS Rating Curve= 0 ,0
Exp/Cntr=0.3,0.1

Type RM Length L Ch R = 1 ,98723   ,354,354,354
BEGIN DESCRIPTION:
PERDIDO CREEK 128.0
END DESCRIPTION:
XS GIS Cut Line= 3
      2489729.59     13473556.76       2489677.2     13472431.08
      2489807.73     13471942.21
#Sta/Elev= 30
  3873.1  201.55  4224.8  198.65  4555.6  197.47  4645.7  199.31  4742.8  199.02
  4865.9   197.7    4916  191.48  4940.3  190.17  4986.1  182.35  5001.8  181.16
  5002.3  180.66  5020.6  181.16    5027  185.37  5068.4  197.76  5078.7  197.14
  5086.2  193.35  5091.3  194.48  5099.4  189.09  5104.6  188.92  5109.8  188.74
  5120.1  192.21  5126.2  192.83  5213.3   190.8  5241.3  191.86  5246.5  190.92
  5281.4  195.67  5286.6  194.99  5316.3  200.71  5327.2  201.23    5506  200.75
#Mann= 6 ,-1 , 0
  3873.1     .12       0  4224.8     .05       0  4742.8    .035       0
  5001.8    .035       0  5020.6    .035       0  5104.6     .07       0
Bank Sta=5001.8,5020.6
XS Rating Curve= 0 ,0
Exp/Cntr=0.3,0.1

Type RM Length L Ch R = 1 ,98369   ,441,441,441
BEGIN DESCRIPTION:
Mapping XS adaabe16
END DESCRIPTION:
XS GIS Cut Line= 3
      2489976.99     13473539.42      2489994.35      13472532.5
      2489963.97     13471942.26
#Sta/Elev= 30
  4004.8  201.31    4085  200.88  4286.7  199.24  4422.2  199.23  4533.4  196.88
  4589.3  192.64  4639.3  196.79  4849.4  198.43  4899.4  191.64  4929.4  190.67
    4990   180.6  4990.5   180.1  5008.8   180.6  5049.4  184.21  5089.5  191.76
  5109.5  197.83  5124.1  198.13  5292.9  199.46  5309.8  196.25  5329.8  199.56
  5389.9  200.35  5399.9  199.08  5409.9  193.72  5429.9  187.06  5439.9  187.46
  5485.3  199.78  5580.1  199.32  5590.1  198.14    5599  190.49  5602.9  190.49
#Mann= 8 ,-1 , 0
  4004.8     .12       0    4085     .07       0  4286.7     .05       0
  4422.2     .07       0  4533.4     .05       0    4990     .05       0
  5008.8     .05       0  5124.1     .07       0
#XS Ineff= 2 , 0
       0                  5389.9       0  200.35
Permanent Ineff=
       F       F
Bank Sta=4990,5008.8
XS Rating Curve= 0 ,0
Exp/Cntr=0.3,0.1

Type RM Length L Ch R = 1 ,97928   ,483,483,483
BEGIN DESCRIPTION:
PERDIDO CREEK 127.0
END DESCRIPTION:
XS GIS Cut Line= 3
        2490375.     13473324.98        2490375.       13472725.
        2490075.     13471725.01
#Sta/Elev= 30
  4393.9  200.41  4561.1  198.44  4723.9  196.25  4750.6  193.47  4773.9  191.74
  4803.9  195.58  4853.9  186.03  4893.9  194.68  4923.9  196.55  4933.9  195.25
    4958   185.8    4982  180.02  4982.5  179.52  5000.8  180.02  5025.2  180.12
  5069.9  187.58  5081.8  184.67  5087.8  189.54  5153.1   195.9    5395   198.8
  5437.5  204.79  5461.1   204.9  5499.4  193.34  5526.3  192.56    5553  196.53
  5570.7  198.28  5669.9  198.17  5702.9  200.58  5835.8  198.77  6037.9  200.12
#Mann= 10 ,-1 , 0
  4393.9     .12       0  4561.1     .05       0  4750.6     .07       0
    4958    .035       0    4982    .035       0  5000.8    .035       0
  5069.9     .05       0  5437.5     .12       0    5553     .07       0
  5835.8     .05       0
#XS Ineff= 2 , 0
       0                  5453.3       0  205.44
Permanent Ineff=
       F       F
Bank Sta=4982,5000.8
XS Rating Curve= 0 ,0
Exp/Cntr=0.3,0.1

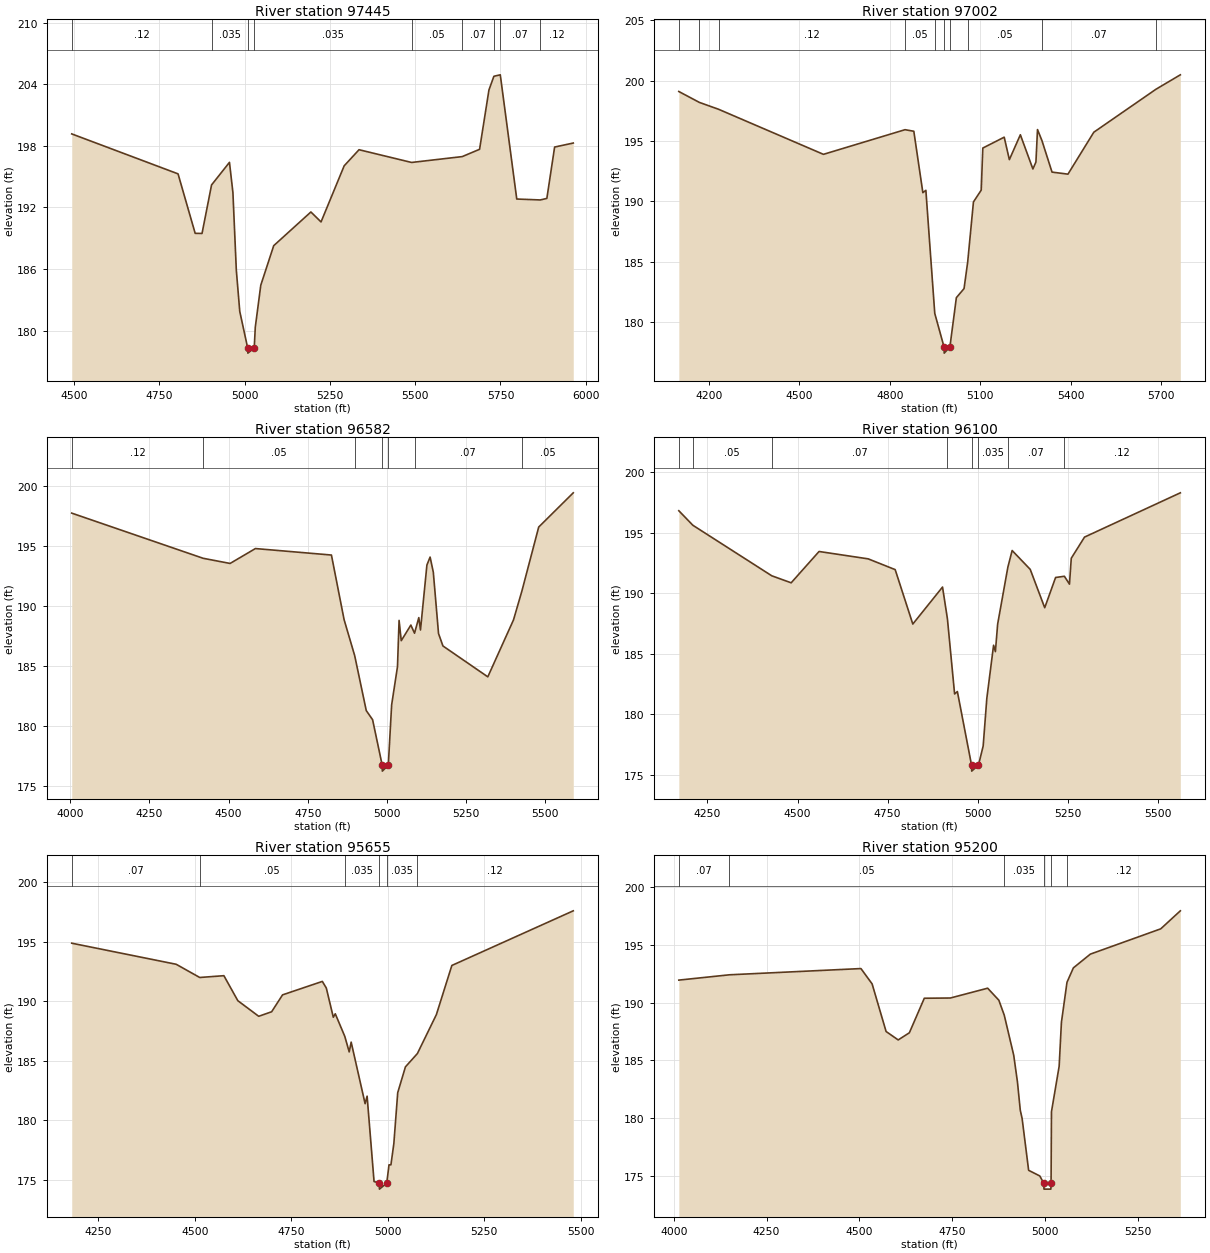
Type RM Length L Ch R = 1 ,97445   ,443,443,443
BEGIN DESCRIPTION:
PERDIDO CREEK 126.0
END DESCRIPTION:
XS GIS Cut Line= 3
        2490775.     13473225.01        2490825.       13472725.
      2490358.95     13471877.15
#Sta/Elev= 30
  4493.3  199.16  4804.9  195.27  4855.1  189.48  4875.2  189.47  4903.1  194.19
  4955.6  196.39  4965.7  193.46  4975.7   185.9  4985.8  181.88    5009  178.32
  5009.5  177.82  5028.2  178.32  5031.3  180.34  5047.4  184.43  5085.3  188.28
  5194.3  191.56    5224  190.59  5291.8  196.05  5335.4  197.62  5489.4  196.38
  5637.9  196.95  5688.7  197.66  5716.2  203.44  5730.7  204.77  5749.4  204.91
  5797.7  192.82  5866.5  192.73  5885.9  192.88  5908.7  197.88  5963.3  198.27
#Mann= 9 ,-1 , 0
  4493.3     .12       0  4903.1    .035       0    5009    .035       0
  5028.2    .035       0  5489.4     .05       0  5637.9     .07       0
  5730.7     .12       0  5749.4     .07       0  5866.5     .12       0
#XS Ineff= 2 , 0
       0                  5335.4       0  197.62
Permanent Ineff=
       F       F
Bank Sta=5009,5028.2
XS Rating Curve= 0 ,0
Exp/Cntr=0.3,0.1

Type RM Length L Ch R = 1 ,97002   ,420,420,420
BEGIN DESCRIPTION:
PERDIDO CREEK 125.0
END DESCRIPTION:
XS GIS Cut Line= 3
        2491125.     13473325.02        2491125.       13472425.
      2490874.52     13471702.61
#Sta/Elev= 30
  4099.7   199.1  4167.7   198.2  4231.6  197.63  4579.7   193.9  4850.6  195.94
  4879.7  195.81  4909.7  190.73  4919.7  190.92  4949.2  180.74  4980.1  177.95
  4980.6  177.45  4999.4  177.95  5020.9  182.04  5046.4  182.79  5058.5  184.99
  5077.6  189.96  5103.4  190.94  5108.7  194.42  5179.7  195.32  5196.8  193.46
  5233.3  195.52  5274.9  192.69    5285  193.26  5290.2  195.95  5304.8  195.05
  5338.4  192.43  5391.3  192.26  5477.1  195.73  5683.6  199.29  5764.3  200.48
#Mann= 10 ,-1 , 0
  4099.7     .12       0  4167.7     .07       0  4231.6     .12       0
  4850.6     .05       0  4949.2    .035       0  4980.1    .035       0
  4999.4    .035       0  5058.5     .05       0  5304.8     .07       0
  5683.6     .12       0
Bank Sta=4980.1,4999.4
XS Rating Curve= 0 ,0
Exp/Cntr=0.3,0.1

Type RM Length L Ch R = 1 ,96582   ,482,482,482
BEGIN DESCRIPTION:
PERDIDO CREEK 124.0
END DESCRIPTION:
XS GIS Cut Line= 3
        2491475.     13473224.97        2491475.       13472225.
      2491383.48     13471648.59
#Sta/Elev= 30
  4004.6  197.72  4419.5  193.96  4504.6  193.53  4584.6  194.77  4824.6  194.23
  4864.6  188.85    4898  185.86  4934.6  181.28  4954.6  180.52  4984.9  176.74
  4985.4  176.24  5004.2  176.74  5014.7  181.75  5033.2  184.94  5038.2  188.79
  5045.1   187.1  5075.4   188.4    5087  187.72  5100.5  189.02  5105.8  187.99
  5126.1   193.4  5136.2  194.06  5146.3   192.8  5162.8  187.69  5176.7  186.66
  5318.4  184.09  5399.5  188.83  5426.1  191.24  5479.1  196.56  5588.2  199.41
#Mann= 7 ,-1 , 0
  4004.6     .12       0  4419.5     .05       0    4898    .035       0
  4984.9    .035       0  5004.2    .035       0    5087     .07       0
  5426.1     .05       0
Bank Sta=4984.9,5004.2
XS Rating Curve= 0 ,0
Exp/Cntr=0.3,0.1

Type RM Length L Ch R = 1 ,96100   ,445,445,445
BEGIN DESCRIPTION:
PERDIDO CREEK 123.0
END DESCRIPTION:
XS GIS Cut Line= 3
      2491724.99     13472925.04        2491925.       13472125.
      2491871.07     13471560.33
#Sta/Elev= 30
  4170.5  196.81  4209.4  195.61  4428.5  191.43  4482.3  190.85  4559.7  193.44
  4696.2  192.83    4771  191.94  4819.9  187.44  4902.4   190.5    4916  187.87
  4935.9  181.66  4943.6  181.86  4982.9  175.78  4983.4  175.28  5002.2  175.78
  5015.2  177.36  5025.3  181.29  5044.1  185.69  5049.1  185.16  5055.4  187.44
  5083.7  192.14  5095.6  193.52  5145.8  191.96    5186  188.79  5216.2  191.29
  5240.6  191.39  5254.7  190.74  5259.7  192.88  5296.5  194.63  5562.4  198.29
#Mann= 8 ,-1 , 0
  4170.5     .07       0  4209.4     .05       0  4428.5     .07       0
    4916    .035       0  4982.9    .035       0  5002.2    .035       0
  5083.7     .07       0  5240.6     .12       0
Bank Sta=4982.9,5002.2
XS Rating Curve= 0 ,0
Exp/Cntr=0.3,0.1

Type RM Length L Ch R = 1 ,95655   ,455,455,455
BEGIN DESCRIPTION:
PERDIDO CREEK 122.0
END DESCRIPTION:
XS GIS Cut Line= 3
        2492125.     13472775.01        2492325.       13471975.
       2492291.2     13471501.24
#Sta/Elev= 30
  4180.8  194.87  4451.4   193.1  4512.5  191.99  4575.1  192.14  4611.2  190.04
  4665.3  188.73  4698.8  189.11  4727.1  190.53  4830.2  191.66  4840.5   191.1
  4858.6  188.65  4863.7  188.94  4888.3  187.05  4899.8  185.74  4904.9  186.56
    4941  181.39  4946.2  182.02  4964.2  174.85  4977.7  174.71  4978.2  174.21
  4997.1  174.71  5002.9  176.25  5007.9  176.25  5015.5  178.04  5025.5  182.31
  5045.5  184.48  5076.5   185.6  5125.7  188.87  5165.8     193  5480.4  197.59
#Mann= 6 ,-1 , 0
  4180.8     .07       0  4512.5     .05       0  4888.3    .035       0
  4977.7    .035       0  4997.1    .035       0  5076.5     .12       0
Bank Sta=4977.7,4997.1
XS Rating Curve= 0 ,0
Exp/Cntr=0.3,0.1

Type RM Length L Ch R = 1 ,95200   ,454,454,454
BEGIN DESCRIPTION:
PERDIDO CREEK 121.0
END DESCRIPTION:
XS GIS Cut Line= 3
      2492806.56     13472803.69        2492725.       13471825.
       2492612.4     13471474.32
#Sta/Elev= 30
  4013.6  191.94    4150   192.4    4504  192.94  4534.1  191.61  4571.7  187.49
  4604.3  186.76  4634.4  187.38  4674.6  190.37  4744.8  190.39  4845.2  191.24
  4875.3   190.2  4889.9   188.9  4915.4  185.43  4925.4  183.12    4933  180.68
    4938  179.95  4955.5  175.47  4985.6  174.98  4996.4  174.34  4996.9  173.84
  5015.4  173.84  5015.9  174.34    5017  180.54  5037.7  184.48  5043.8  188.28
  5058.8  191.75    5076     193  5121.7  194.19  5311.2  196.38    5364  197.94
#Mann= 6 ,-1 , 0
  4013.6     .07       0    4150     .05       0  4889.9    .035       0
  4996.4    .035       0  5015.9    .035       0  5058.8     .12       0
Bank Sta=4996.4,5015.9
XS Rating Curve= 0 ,0
Exp/Cntr=0.3,0.1

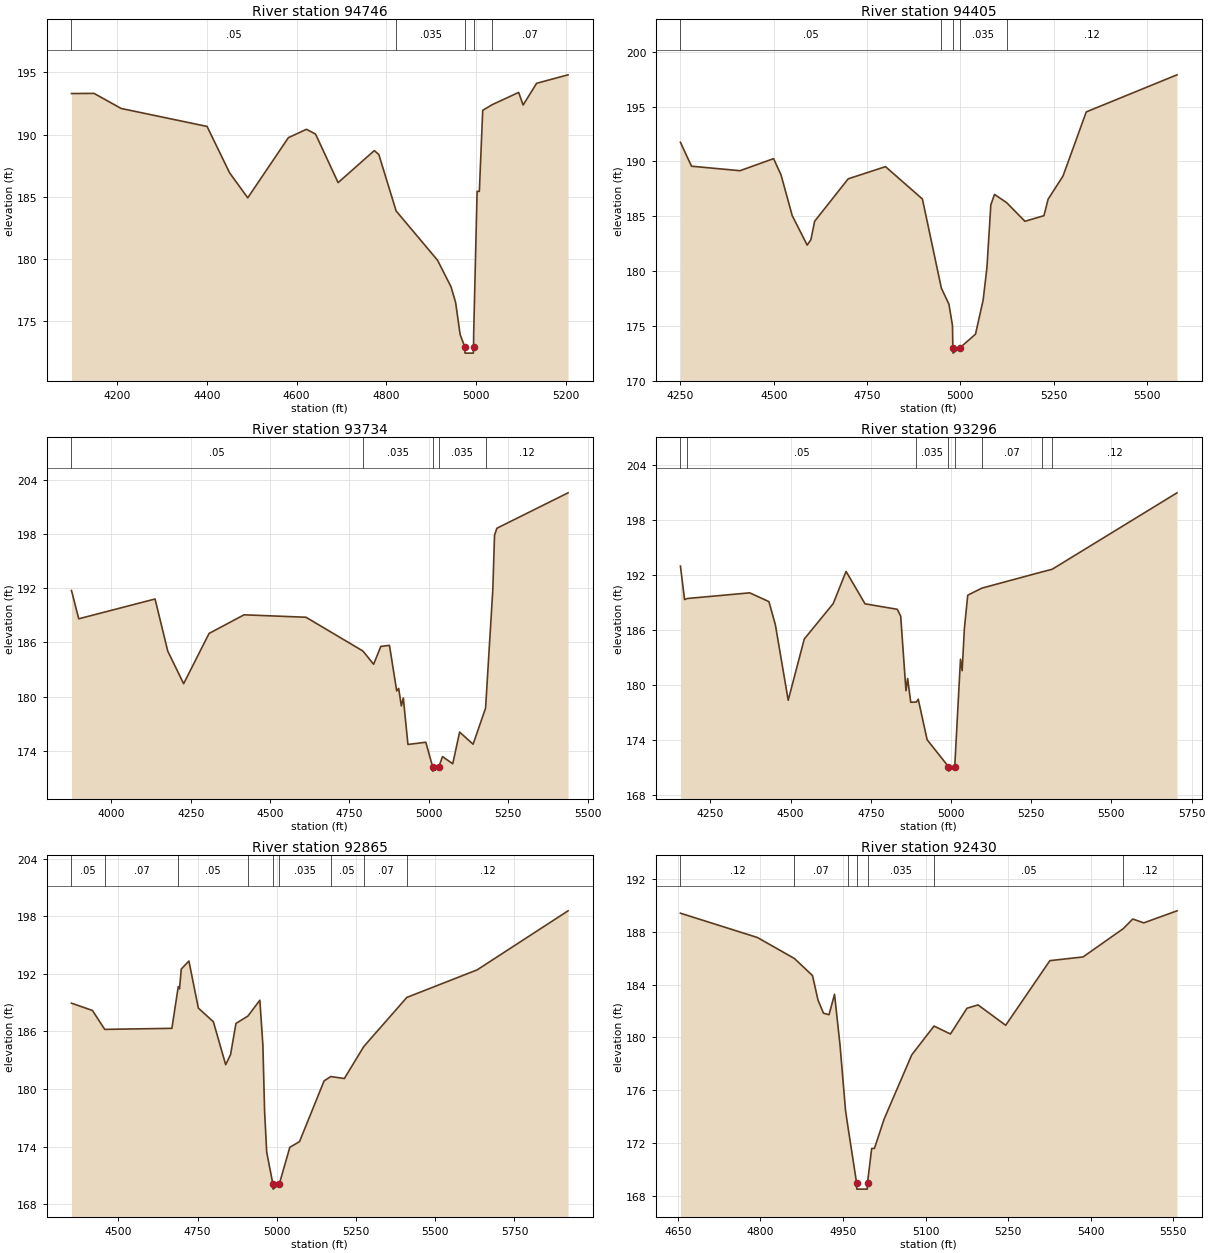
Type RM Length L Ch R = 1 ,94746   ,341,341,341
BEGIN DESCRIPTION:
PERDIDO CREEK 120.0
END DESCRIPTION:
XS GIS Cut Line= 3
        2493025.     13472574.97        2493125.       13471675.
        2493125.     13471475.01
#Sta/Elev= 30
  4098.8  193.29  4149.1   193.3  4209.4  192.09  4400.6  190.65  4450.9  186.92
  4491.2  184.92  4581.7  189.75    4622  190.42  4642.1  190.04  4692.4  186.14
  4772.9  188.71    4783   188.4  4821.5  183.87  4913.8  179.91  4943.9  177.77
    4954  176.52  4964.1  173.94  4974.4  172.96  4974.9  172.46  4993.4  172.46
  4993.9  172.96  4994.2  174.05  5001.8  185.44  5006.8  185.44  5014.3  191.94
  5034.6  192.38  5094.3  193.38  5104.3  192.37  5134.3  194.11  5204.3  194.79
#Mann= 5 ,-1 , 0
  4098.8     .05       0  4821.5    .035       0  4974.4    .035       0
  4993.9    .035       0  5034.6     .07       0
Bank Sta=4974.4,4993.9
XS Rating Curve= 0 ,0
Exp/Cntr=0.3,0.1

Type RM Length L Ch R = 1 ,94405   ,671,671,671
BEGIN DESCRIPTION:
Mapping XS d21b47a1
END DESCRIPTION:
XS GIS Cut Line= 3
      2493447.77     13472524.67      2493439.09     13471795.52
       2493321.9     13471205.24
#Sta/Elev= 30
  4249.9  191.75  4279.6  189.57  4409.6  189.16  4499.6  190.26  4519.6  188.77
  4549.6  185.06  4589.6  182.38  4599.6  182.87  4609.6  184.55  4699.6  188.42
  4799.6  189.53  4898.5  186.58  4949.3  178.45  4969.6  176.99  4979.1  175.05
  4980.1  173.03  4980.6  172.53  4999.6  173.03  5040.8  174.26  5061.2  177.35
  5071.4  180.31  5081.9  186.05  5091.8     187  5124.5  186.24  5173.3  184.55
  5224.3  185.06  5235.4  186.56  5275.3  188.67  5337.7  194.52  5580.9   197.9
#Mann= 5 ,-1 , 0
  4249.9     .05       0  4949.3    .035       0  4980.1    .035       0
  4999.6    .035       0  5124.5     .12       0
Bank Sta=4980.1,4999.6
XS Rating Curve= 0 ,0
Exp/Cntr=0.3,0.1

Type RM Length L Ch R = 1 ,93734   ,438,438,438
BEGIN DESCRIPTION:
Mapping XS e31fba59
END DESCRIPTION:
XS GIS Cut Line= 4
      2493555.44     13472527.81      2493579.74     13471968.75
      2493916.52     13471517.74      2494072.77     13471105.42
#Sta/Elev= 30
  3874.9  191.74  3897.7  188.61    4138   190.8    4178  185.03    4228  181.43
  4308.1  186.99  4418.2  189.05  4613.2  188.78  4792.5  185.04  4826.1  183.58
  4848.8  185.55    4876  185.67  4898.8  180.63    4905   180.9  4913.4  178.97
  4919.6  179.85  4934.2   174.7  4990.5  174.95  5011.8  172.25  5012.3  171.75
  5031.5  172.25  5043.1  173.36  5075.2  172.56  5096.9  176.07  5139.3  174.73
  5178.6  178.72  5201.4  191.84  5206.8  197.85  5214.2  198.63  5438.3  202.55
#Mann= 5 ,-1 , 0
  3874.9     .05       0  4792.5    .035       0  5011.8    .035       0
  5031.5    .035       0  5178.6     .12       0
Bank Sta=5011.8,5031.5
XS Rating Curve= 0 ,0
Exp/Cntr=0.3,0.1

Type RM Length L Ch R = 1 ,93296   ,431,431,431
BEGIN DESCRIPTION:
Mapping XS 390751e5
END DESCRIPTION:
XS GIS Cut Line= 4
      2493649.19     13472510.46      2493680.44     13471923.61
      2494058.91     13471809.03      2494229.06      13471270.8
#Sta/Elev= 30
  4156.8  192.98  4169.7  189.33  4178.2  189.44  4372.6  190.06  4432.6   189.1
  4452.7  186.57  4492.7  178.33  4542.8  185.02  4632.9  188.88    4673   192.4
  4732.2  188.86  4832.8  188.26  4843.3   187.5  4859.7  179.37  4864.9  180.71
  4874.6  178.11  4892.3  178.13  4897.9  178.45  4925.6  174.02    4992  171.09
  4992.5  170.59  5011.7  171.09  5029.6  182.81  5034.8  181.56  5041.8  186.18
  5052.2   189.8    5096  190.57  5283.1  192.34  5315.2  192.63  5704.4  200.98
#Mann= 8 ,-1 , 0
  4156.8     .07       0  4178.2     .05       0  4892.3    .035       0
    4992    .035       0  5011.7    .035       0    5096     .07       0
  5283.1    .035       0  5315.2     .12       0
Bank Sta=4992,5011.7
XS Rating Curve= 0 ,0
Exp/Cntr=0.3,0.1

Type RM Length L Ch R = 1 ,92865   ,435,435,435
BEGIN DESCRIPTION:
PERDIDO CREEK 117.0
END DESCRIPTION:
XS GIS Cut Line= 3
      2493732.52      13472826.4        2493975.       13472225.
      2494288.07     13471361.12
#Sta/Elev= 30
  4351.8  188.95    4418  188.19  4456.7  186.22  4668.7  186.33  4688.8  190.68
  4692.8  190.44  4698.3  192.51  4722.4  193.34  4752.2  188.44  4799.7  187.01
  4838.5  182.54  4853.9   183.6  4870.9  186.84  4908.7  187.61  4946.3  189.26
  4955.9  184.59  4961.3  177.69  4967.9  173.44  4987.6  170.08  4988.1  169.58
  5007.4  170.08  5040.9  173.94  5071.5  174.53  5149.2  180.86  5170.4  181.31
    5213   181.1  5274.3  184.43  5410.3  189.55  5632.2  192.42  5919.1  198.57
#Mann= 9 ,-1 , 0
  4351.8     .05       0  4456.7     .07       0  4688.8     .05       0
  4908.7    .035       0  4987.6    .035       0  5007.4    .035       0
  5170.4     .05       0  5274.3     .07       0  5410.3     .12       0
Bank Sta=4987.6,5007.4
XS Rating Curve= 0 ,0
Exp/Cntr=0.3,0.1

Type RM Length L Ch R = 1 ,92430   ,274,274,274
BEGIN DESCRIPTION:
PERDIDO CREEK 116.0
END DESCRIPTION:
XS GIS Cut Line= 3
        2494375.       13472675.        2494375.       13472325.
        2494325.     13471774.97
#Sta/Elev= 30
  4654.6   189.4  4794.6  187.56  4861.8  185.97  4894.6  184.68  4904.6  182.82
  4914.6  181.83  4924.6  181.72  4934.6  183.26  4944.6  179.42  4954.6  174.47
    4959  173.23  4974.6  169.02  4975.1  168.52  4994.1  168.52  4994.6  169.02
  5002.1   171.6  5007.1   171.6  5024.7  173.82  5074.9  178.68  5115.4  180.86
  5145.2  180.26  5175.3  182.21  5195.4  182.46  5245.6  180.92  5325.9  185.81
  5386.2  186.09  5459.2  188.23  5476.5  188.96  5496.6  188.67  5556.9  189.58
#Mann= 7 ,-1 , 0
  4654.6     .12       0  4861.8     .07       0    4959    .035       0
  4974.6    .035       0  4994.6    .035       0  5115.4     .05       0
  5459.2     .12       0
Bank Sta=4974.6,4994.6
XS Rating Curve= 0 ,0
Exp/Cntr=0.3,0.1

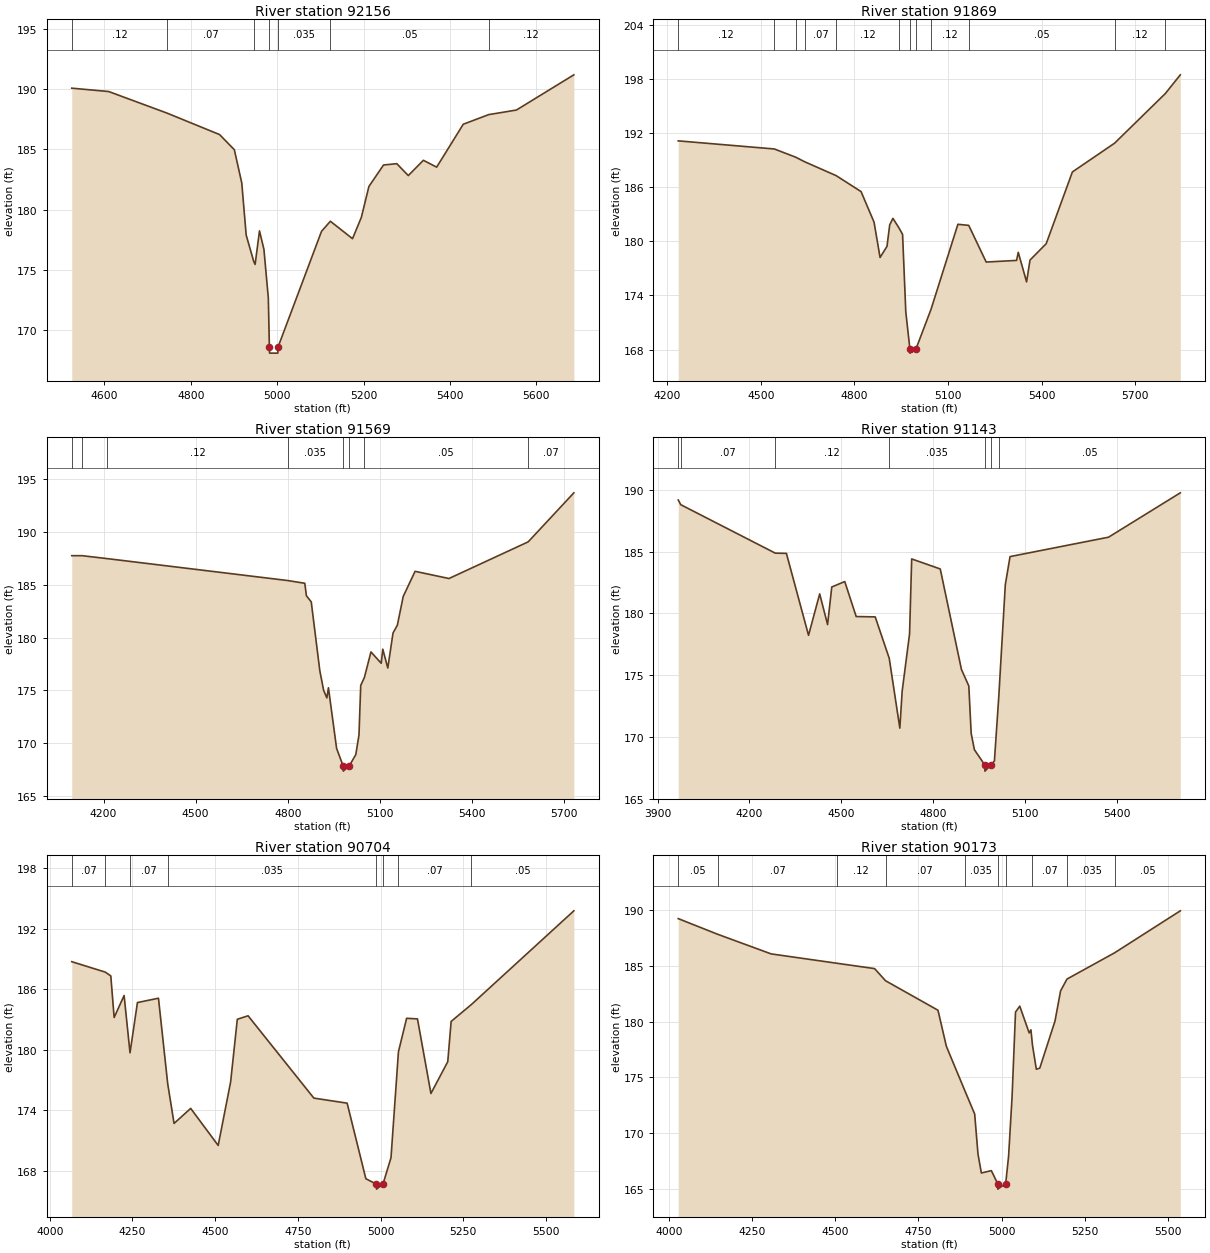
Type RM Length L Ch R = 1 ,92156   ,287,287,287
BEGIN DESCRIPTION:
Mapping XS b12013c4
END DESCRIPTION:
XS GIS Cut Line= 3
       2494534.6      13472788.2      2494630.09     13472380.21
      2494465.15     13471655.36
#Sta/Elev= 30
  4524.3   190.1  4609.8  189.82  4745.3  188.02  4866.5  186.24  4900.7  184.98
  4917.9  182.21  4928.1  177.88  4945.8  175.66  4948.8  175.44  4958.9  178.23
  4969.2  176.69  4979.4  172.64  4981.8  168.56  4982.3  168.06  5001.3  168.06
  5001.8  168.56  5102.5  178.19    5123  179.03  5174.3  177.58  5194.8  179.36
  5212.2  181.92  5246.1  183.71  5276.8  183.82  5303.4  182.83  5338.4   184.1
  5369.1  183.53  5430.7   187.1  5489.6   187.9  5553.7  188.28  5686.7  191.21
#Mann= 7 ,-1 , 0
  4524.3     .12       0  4745.3     .07       0  4945.8    .035       0
  4981.8    .035       0  5001.8    .035       0    5123     .05       0
  5489.6     .12       0
Bank Sta=4981.8,5001.8
XS Rating Curve= 0 ,0
Exp/Cntr=0.3,0.1

Type RM Length L Ch R = 1 ,91869   ,300,300,300
BEGIN DESCRIPTION:
PERDIDO CREEK 115.0
END DESCRIPTION:
XS GIS Cut Line= 3
      2494691.34     13472972.83        2494875.       13472225.
        2494625.     13471425.01
#Sta/Elev= 30
  4235.8  191.16  4543.6  190.26  4611.9  189.35  4640.8  188.84  4741.7   187.3
  4821.4  185.53    4863  182.14  4882.3  178.22  4904.5  179.45  4913.2  181.84
  4923.5  182.56  4943.3  181.47  4954.4  180.78  4964.7  172.19  4977.7   168.1
  4978.2   167.6  4997.7   168.1  5045.5  172.46  5131.6   181.9  5166.3  181.78
  5222.2  177.71  5319.6  177.89  5324.9  178.79  5351.6  175.51  5362.6  177.93
  5414.5  179.75  5498.3  187.71  5633.4   190.9  5795.7   196.4    5844  198.49
#Mann= 12 ,-1 , 0
  4235.8     .12       0  4543.6     .07       0  4611.9     .12       0
  4640.8     .07       0  4741.7     .12       0  4943.3    .035       0
  4977.7    .035       0  4997.7    .035       0  5045.5     .12       0
  5166.3     .05       0  5633.4     .12       0  5795.7     .05       0
Bank Sta=4977.7,4997.7
XS Rating Curve= 0 ,0
Exp/Cntr=0.3,0.1

Type RM Length L Ch R = 1 ,91569   ,426,426,426
BEGIN DESCRIPTION:
Mapping XS c6ba461d
END DESCRIPTION:
XS GIS Cut Line= 3
      2494985.99     13473006.97      2495163.08     13472201.39
       2494933.9     13471423.57
#Sta/Elev= 30
  4096.5  187.75  4130.3  187.75  4212.8  187.47  4799.5   185.4  4855.7  185.14
  4860.9  183.96  4876.7  183.38  4904.6  176.87  4916.9  175.02  4927.5  174.29
  4932.7  175.25  4959.3  169.51  4980.5  167.86    4981  167.36  5000.6  167.86
  5021.8  168.92  5032.2  170.78  5037.9  175.47  5049.8  176.22  5071.2  178.64
  5104.6  177.57  5109.8   178.9  5126.1  177.12  5143.1  180.43  5157.3  181.18
  5176.4   183.9    5215  186.27  5325.4  185.59  5583.5  189.06  5732.2   193.7
#Mann= 8 ,-1 , 0
  4096.5     .12       0  4130.3     .07       0  4212.8     .12       0
  4799.5    .035       0  4980.5    .035       0  5000.6    .035       0
  5049.8     .05       0  5583.5     .07       0
Bank Sta=4980.5,5000.6
XS Rating Curve= 0 ,0
Exp/Cntr=0.3,0.1

Type RM Length L Ch R = 1 ,91143   ,439,439,439
BEGIN DESCRIPTION:
PERDIDO CREEK 113.0
END DESCRIPTION:
XS GIS Cut Line= 3
      2495860.95     13472958.69      2495521.78     13471983.28
      2495322.89     13471409.58
#Sta/Elev= 30
  3967.3  189.17  3975.6  188.79  4284.2  184.87  4320.6  184.85  4392.9  178.22
  4429.3  181.57  4455.1  179.09  4468.8  182.13  4511.2  182.57  4548.5  179.74
  4610.7  179.71  4656.5  176.36  4691.1  170.71  4698.7   173.7  4722.9  178.34
  4729.8   184.4  4823.1  183.59  4892.3  175.46  4916.4  174.12  4924.1  170.29
  4934.7  168.96  4968.6  167.73  4969.1  167.23  4988.7  167.73    5000  168.05
  5014.4   173.3  5035.6  182.31  5051.1  184.59  5372.8  186.16  5607.2  189.75
#Mann= 7 ,-1 , 0
  3967.3     .12       0  3975.6     .07       0  4284.2     .12       0
  4656.5    .035       0  4968.6     .05       0  4988.7    .035       0
  5014.4     .05       0
Bank Sta=4968.6,4988.7
XS Rating Curve= 0 ,0
Exp/Cntr=0.3,0.1

Type RM Length L Ch R = 1 ,90704   ,531,531,531
BEGIN DESCRIPTION:
PERDIDO CREEK 112.0
END DESCRIPTION:
XS GIS Cut Line= 3
      2496038.91     13472902.27      2495935.19     13471974.55
      2495826.25      13471400.6
#Sta/Elev= 30
  4066.5  188.72  4167.5  187.69  4184.5  187.31  4194.6  183.19  4224.7  185.37
  4242.6  179.69    4265  184.67  4328.6   185.1  4356.5  176.63  4375.7  172.69
    4426  174.18  4509.1  170.51  4546.7   176.8  4566.9  183.01  4599.4  183.36
  4798.3   175.2  4898.9   174.7  4955.5  167.21  4987.2  166.68  4987.7  166.18
  5007.3  166.68  5031.5   169.3    5054  179.79  5078.7  183.11  5111.5  183.05
  5152.2  175.66  5203.1  178.81  5213.3   182.8    5274  184.46  5584.2  193.76
#Mann= 8 ,-1 , 0
  4066.5     .07       0  4167.5    .035       0  4242.6     .07       0
  4356.5    .035       0  4987.2    .035       0  5007.3    .035       0
    5054     .07       0    5274     .05       0
Bank Sta=4987.2,5007.3
XS Rating Curve= 0 ,0
Exp/Cntr=0.3,0.1

Type RM Length L Ch R = 1 ,90173   ,587,587,587
BEGIN DESCRIPTION:
Mapping XS 68c22d92
END DESCRIPTION:
XS GIS Cut Line= 3
      2496481.62     13472893.59      2496420.86     13471947.43
      2496264.73     13471409.65
#Sta/Elev= 30
  4028.4  189.25  4147.2  187.84  4307.6  186.08    4505  185.24  4618.2  184.76
  4651.1  183.67  4808.6  181.02  4833.8  177.78  4889.5  173.78  4918.8   171.7
  4928.8   168.1  4938.9   166.4  4968.9  166.61  4987.8  165.45  4988.3  164.95
    5012  165.45  5020.7  167.91  5031.1  173.21  5041.5  180.85  5054.2  181.39
  5082.6  178.98  5087.8  179.26  5092.5  177.88    5104  175.72  5114.4  175.82
  5160.1  180.05  5176.9  182.76  5196.1  183.82  5339.2  186.18  5536.5  189.95
#Mann= 10 ,-1 , 0
  4028.4     .05       0  4147.2     .07       0    4505     .12       0
  4651.1     .07       0  4889.5    .035       0  4987.8     .05       0
    5012    .035       0  5092.5     .07       0  5196.1    .035       0
  5339.2     .05       0
Bank Sta=4987.8,5012
XS Rating Curve= 0 ,0
Exp/Cntr=0.3,0.1

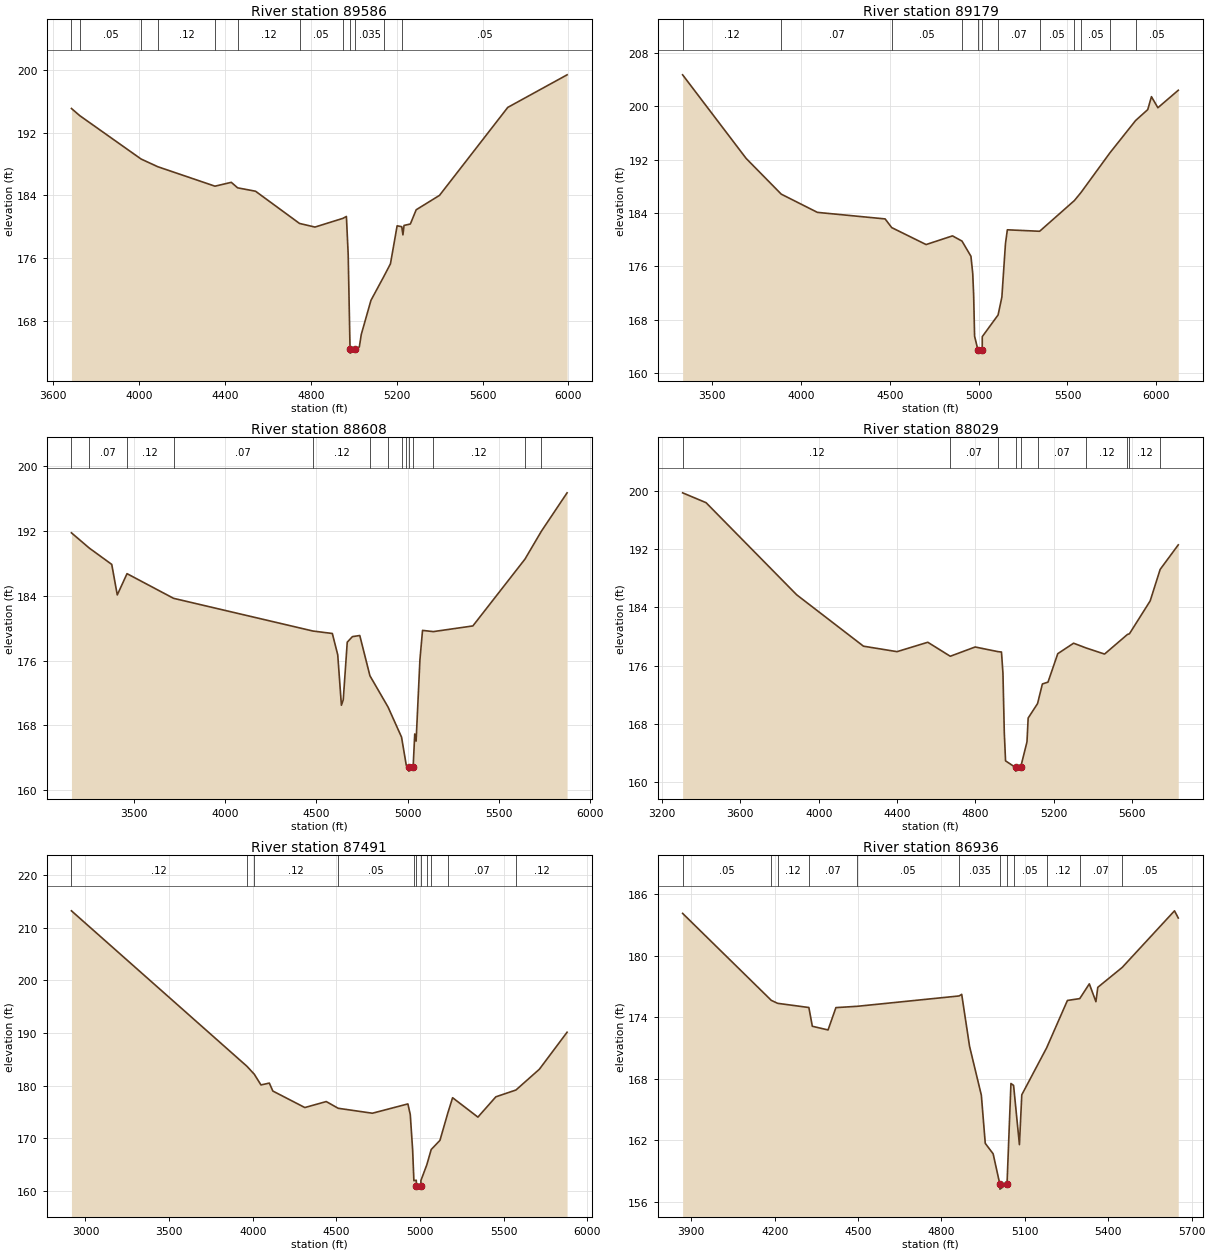
Type RM Length L Ch R = 1 ,89586   ,407,407,407
BEGIN DESCRIPTION:
Mapping XS 952a7a6b
END DESCRIPTION:
XS GIS Cut Line= 4
       2496751.1     13473150.97        2497015.     13471998.15
      2496903.89     13471588.43      2496403.87     13471095.35
#Sta/Elev= 30
  3684.3  195.06  3723.5  194.14  4008.9  188.63    4087  187.65  4353.1  185.18
    4429  185.67  4458.5  184.97  4541.9  184.54  4747.1  180.44  4818.9  179.98
  4949.3  181.09  4965.5  181.33  4973.8  176.46  4982.4  164.45  4982.9  163.95
  5006.7  164.45  5025.6  164.73  5034.8  166.33  5079.8  170.66  5139.9   173.7
  5170.7  175.31  5201.8  180.14  5223.3  180.03  5228.8  178.99    5234  180.19
  5263.4  180.37  5290.6  182.18  5399.2  184.01  5717.4   195.2  5993.7  199.34
#Mann= 12 ,-1 , 0
  3684.3     .07       0  3723.5     .05       0  4008.9     .07       0
    4087     .12       0  4353.1     .07       0  4458.5     .12       0
  4747.1     .05       0  4949.3    .035       0  4982.4    .035       0
  5006.7    .035       0  5139.9     .12       0  5223.3     .05       0
Bank Sta=4982.4,5006.7
XS Rating Curve= 0 ,0
Exp/Cntr=0.3,0.1

Type RM Length L Ch R = 1 ,89179   ,571,571,571
BEGIN DESCRIPTION:
Mapping XS 08e218da
END DESCRIPTION:
XS GIS Cut Line= 4
      2497216.39     13473331.52      2497341.39     13471796.76
      2497258.06     13471421.76       2496598.3     13470859.24
#Sta/Elev= 30
    3333  204.69  3690.7  192.17  3888.4  186.82    4092  184.09  4473.3  183.11
  4510.4  181.81    4704  179.27  4852.6  180.57  4906.2  179.79  4956.6  177.51
  4966.6  174.95  4971.7   171.8  4977.1  165.54  4995.7  163.51  4996.2  163.01
    5020  163.51  5020.4  165.48  5109.5  168.73  5130.7  171.41    5151  179.42
  5161.5  181.48  5343.4  181.26  5539.1  185.86  5576.4  187.07  5739.5  193.02
  5883.9  197.85  5952.1  199.48    5973  201.42  6009.2  199.76    6124  202.38
#Mann= 12 ,-1 , 0
    3333     .12       0  3888.4     .07       0  4510.4     .05       0
  4906.2     .12       0  4995.7     .05       0    5020     .12       0
  5109.5     .07       0  5343.4     .05       0  5539.1    .035       0
  5576.4     .05       0  5739.5    .035       0  5883.9     .05       0
Bank Sta=4995.7,5020
XS Rating Curve= 0 ,0
Exp/Cntr=0.3,0.1

Type RM Length L Ch R = 1 ,88608   ,579,579,579
BEGIN DESCRIPTION:
Mapping XS 4e829f4a
END DESCRIPTION:
XS GIS Cut Line= 3
      2497981.58     13473204.44      2497759.36     13471371.13
      2497106.56     13470794.72
#Sta/Elev= 30
  3157.3  191.73  3254.7  189.86  3378.3  187.84  3408.6  184.08    3462   186.7
  3717.4  183.66  4481.8  179.63  4587.7  179.33  4617.4   176.7  4637.5  170.49
  4647.6  171.16  4669.5  178.26  4697.9  178.94  4738.2  179.08  4793.9  174.12
  4893.6  170.25  4967.2  166.56  4993.3  163.08  5006.5  162.87    5007  162.37
  5030.8  162.87  5039.6  166.95  5047.1  166.07    5068  176.08  5082.3  179.71
  5141.3  179.56  5358.3  180.26  5643.9  188.49    5734  191.93  5874.9  196.66
#Mann= 14 ,-1 , 0
  3157.3     .12       0  3254.7     .07       0    3462     .12       0
  3717.4     .07       0  4481.8     .12       0  4793.9     .05       0
  4893.6      .1       0  4967.2    .035       0  4993.3     .07       0
  5006.5     .05       0  5030.8     .07       0  5141.3     .12       0
  5643.9     .07       0    5734     .12       0
Bank Sta=5006.5,5030.8
XS Rating Curve= 0 ,0
Exp/Cntr=0.3,0.1

Type RM Length L Ch R = 1 ,88029   ,538,538,538
BEGIN DESCRIPTION:
PERDIDO CREEK 108.0
END DESCRIPTION:
XS GIS Cut Line= 3
      2499558.29     13472280.76        2498225.       13471225.
      2497525.03     13470775.02
#Sta/Elev= 30
  3304.7  199.72  3424.4  198.37  3887.6  185.73  4228.9  178.68  4400.4  177.93
  4557.5  179.22  4672.4   177.3  4799.5  178.57  4916.6  177.93  4934.1  177.88
  4941.6  174.99  4948.5   166.8  4954.9  162.95    5006  162.04  5006.5  161.54
  5031.8  162.04  5064.5  165.57  5070.4  168.82  5118.5  170.81  5143.1   173.5
  5171.8  173.75  5221.7  177.65  5302.6  179.09  5366.2  178.44  5460.8   177.6
  5577.8  180.29  5587.9  180.38  5693.9  184.89  5744.9  189.21  5837.5  192.58
#Mann= 10 ,-1 , 0
  3304.7     .12       0  4672.4     .07       0  4916.6    .035       0
    5006    .035       0  5031.8    .035       0  5118.5     .07       0
  5366.2     .12       0  5577.8     .07       0  5587.9     .12       0
  5744.9     .07       0
Bank Sta=5006,5031.8
XS Rating Curve= 0 ,0
Exp/Cntr=0.3,0.1

Type RM Length L Ch R = 1 ,87491   ,555,555,555
BEGIN DESCRIPTION:
PERDIDO CREEK 107.0
END DESCRIPTION:
XS GIS Cut Line= 3
      2500075.01     13472225.01        2498525.       13470825.
      2497724.99       13470475.
#Sta/Elev= 30
  2916.2  213.24  3965.1  183.68  4009.2  182.16  4048.7  180.14  4098.8  180.49
  4119.7  178.98    4311  175.84  4438.8  176.98  4510.2   175.7  4714.6  174.76
  4926.8  176.53    4941  174.49  4955.2  167.75  4961.2  163.04  4962.6  161.94
  4976.8  162.02  4978.1  160.83  4978.6  160.33  5003.9  160.83  5004.9     162
  5040.1  164.98    5066  167.86  5118.3   169.6  5165.6  174.82  5193.9  177.71
  5345.2  174.02  5452.4  177.88  5572.3  179.17  5712.4  183.12  5878.1  190.16
#Mann= 11 ,-1 , 0
  2916.2     .12       0  3965.1     .07       0  4009.2     .12       0
  4510.2     .05       0  4961.2    .035       0  4978.1    .035       0
  5003.9    .035       0  5040.1     .07       0    5066    .035       0
  5165.6     .07       0  5572.3     .12       0
Bank Sta=4978.1,5003.9
XS Rating Curve= 0 ,0
Exp/Cntr=0.3,0.1

Type RM Length L Ch R = 1 ,86936   ,590,590,590
BEGIN DESCRIPTION:
PERDIDO CREEK 106.0
END DESCRIPTION:
XS GIS Cut Line= 3
        2499575.       13471175.        2498775.       13470375.
        2498425.       13469825.
#Sta/Elev= 30
  3868.6  184.13  4187.6  175.64  4210.4  175.35  4322.8  174.94  4335.3  173.11
  4391.9  172.75  4420.1  174.93  4497.4  175.06  4863.5  176.07  4872.7  176.23
    4901  171.15  4943.4  166.38  4957.5  161.68  4985.8  160.66  5009.8  157.71
  5010.3  157.21  5035.8  157.71  5049.9  167.52  5059.4  167.34  5080.4  161.55
  5088.9  166.42  5178.4  171.01  5253.1  175.63  5297.4  175.81  5331.9  177.25
  5355.6  175.51  5362.3  176.91  5450.1  178.85  5638.3  184.38  5651.9  183.68
#Mann= 12 ,-1 , 0
  3868.6     .05       0  4187.6     .07       0  4210.4     .12       0
  4322.8     .07       0  4497.4     .05       0  4863.5    .035       0
  5009.8    .035       0  5035.8    .035       0  5059.4     .05       0
  5178.4     .12       0  5297.4     .07       0  5450.1     .05       0
Bank Sta=5009.8,5035.8
XS Rating Curve= 0 ,0
Exp/Cntr=0.3,0.1