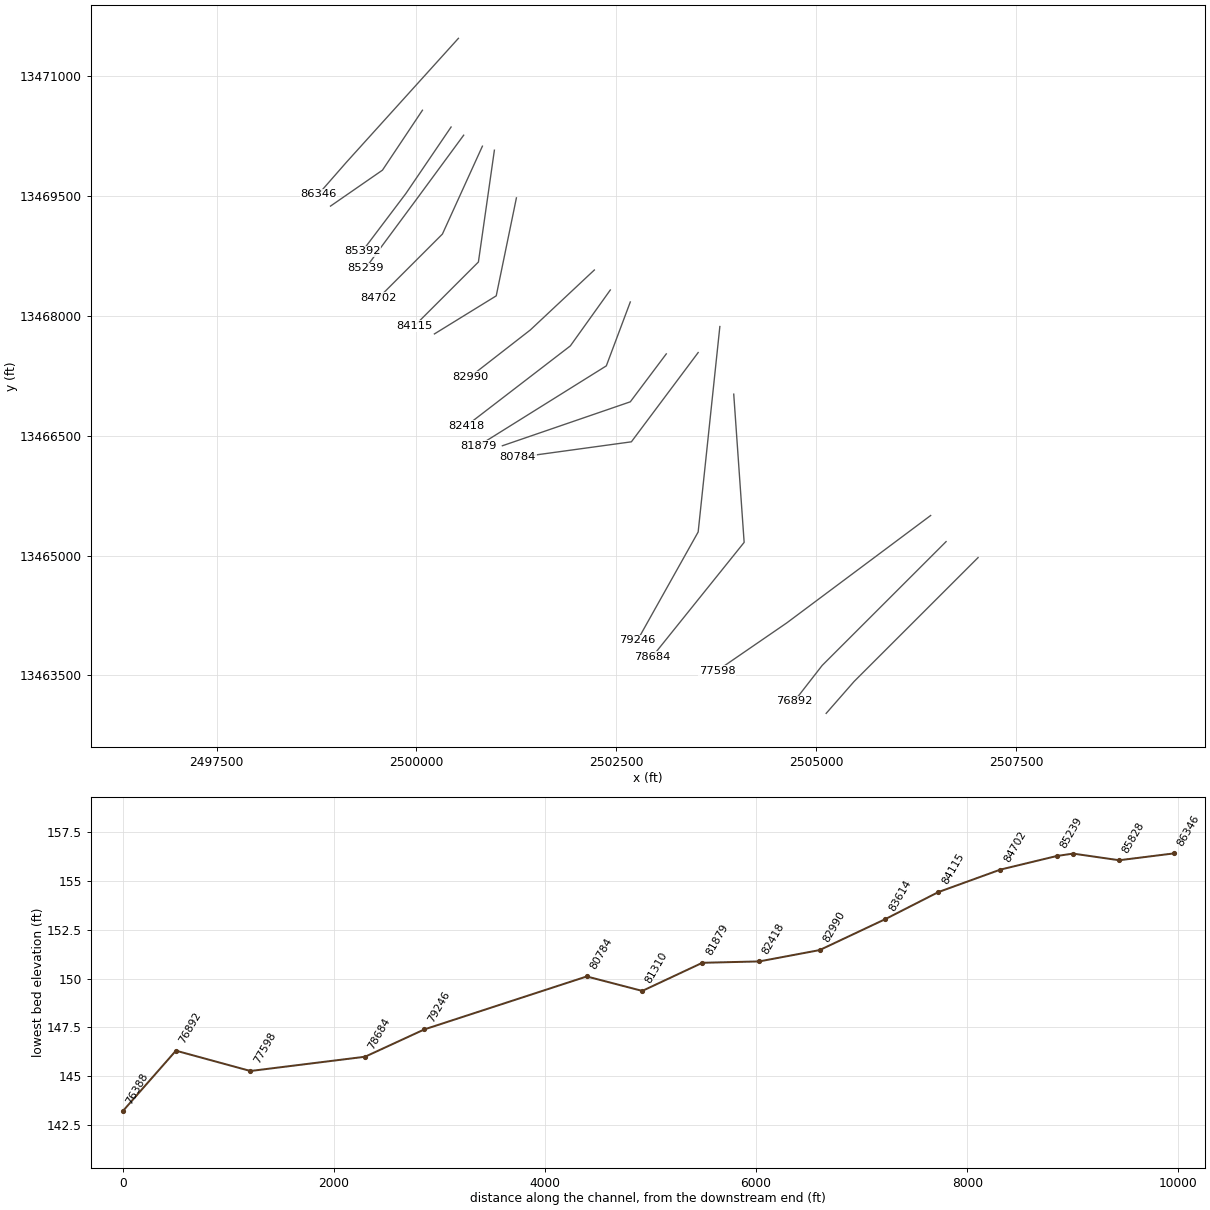
HEC-RAS study PERDIDO CREEK.prj: PERDIDO CREEK Base Level Engineering

--- PERDIDO CREEK.g01 (geometry) --- (continued)

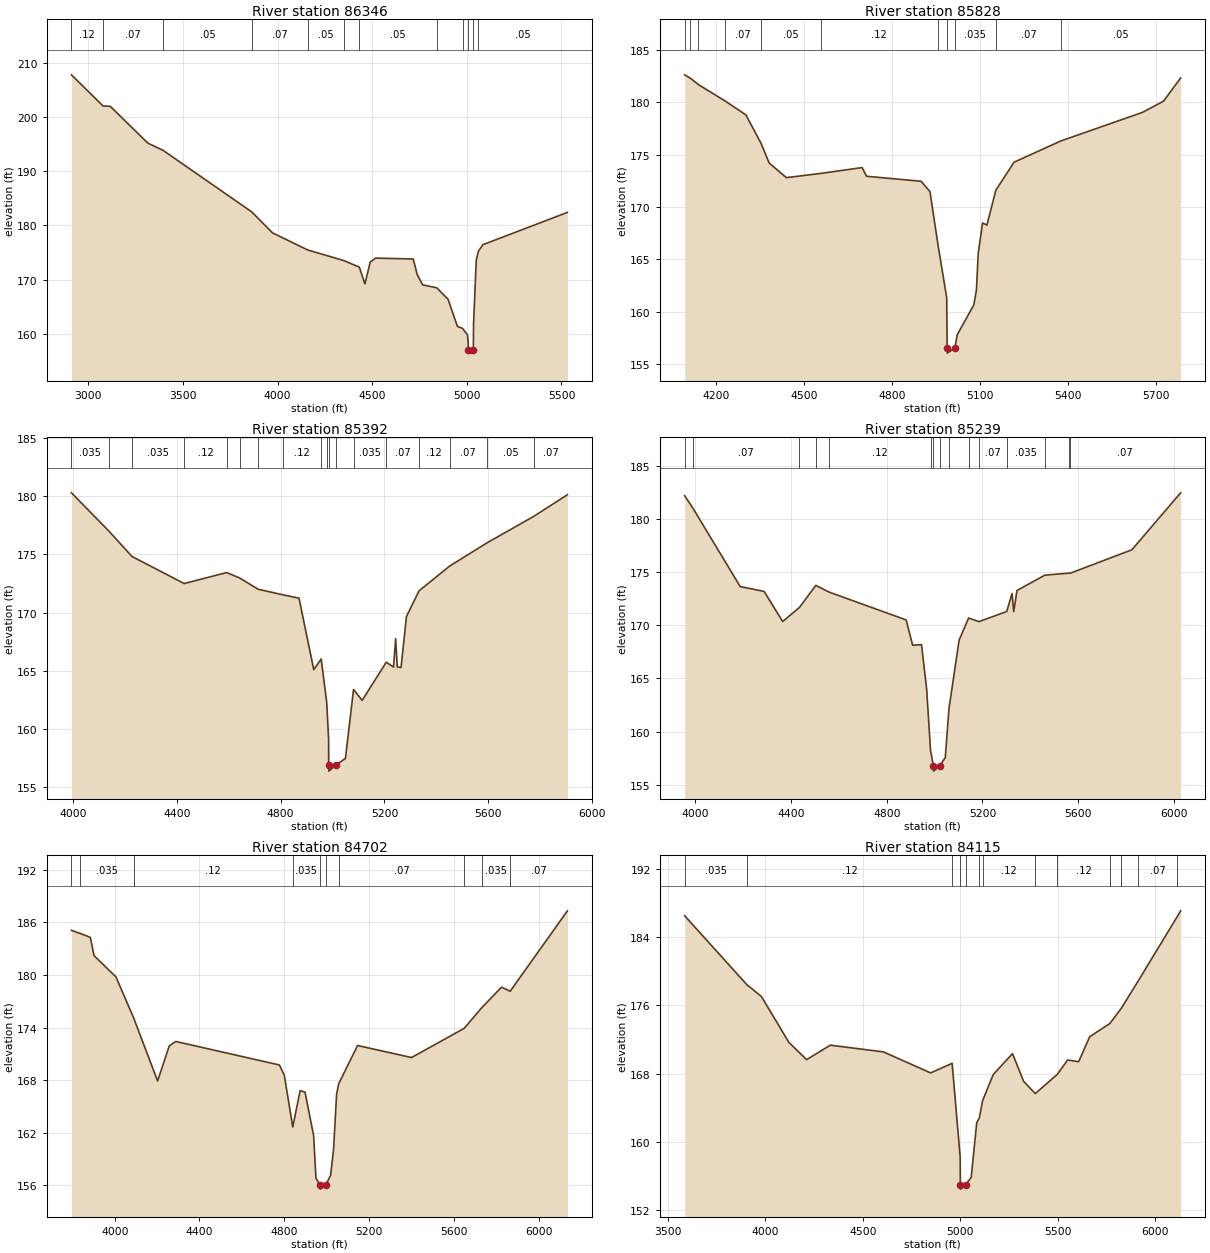
Type RM Length L Ch R = 1 ,86346   ,518,518,518
BEGIN DESCRIPTION:
PERDIDO CREEK 105.0
END DESCRIPTION:
XS GIS Cut Line= 3
      2500525.02     13471475.02        2499125.       13469925.
      2498774.99     13469524.99
#Sta/Elev= 30
  2911.3  207.79  3077.6  202.06  3116.5  201.97  3315.2  195.17  3395.3  193.85
    3864  182.48  3973.6  178.61  4159.2  175.46    4349  173.51    4432  172.29
  4461.6  169.19    4490  173.24  4518.4  173.95    4717  173.79  4738.1   170.9
  4766.5  169.02  4841.1  168.47    4901  166.35  4950.3  161.35  4977.5  160.98
  5003.3  159.79  5007.1   158.6  5008.2  156.91  5008.7  156.41  5034.4  156.91
  5035.6  161.79  5049.8  173.51    5061  175.21  5084.9  176.43  5531.5  182.39
#Mann= 12 ,-1 , 0
  2911.3     .12       0  3077.6     .07       0  3395.3     .05       0
    3864     .07       0  4159.2     .05       0    4349     .07       0
    4432     .05       0  4841.1    .035       0  4977.5     .07       0
  5008.2     .05       0  5034.4     .07       0    5061     .05       0
Bank Sta=5008.2,5034.4
XS Rating Curve= 0 ,0
Exp/Cntr=0.3,0.1

Type RM Length L Ch R = 1 ,85828   ,436,436,436
BEGIN DESCRIPTION:
PERDIDO CREEK 104.0
END DESCRIPTION:
XS GIS Cut Line= 3
      2500074.99     13470574.99        2499575.       13469825.
      2498925.04     13469375.03
#Sta/Elev= 30
  4093.3  182.62  4111.8  182.32  4139.8   181.7  4232.6   180.1  4302.1   178.8
  4353.4  176.11  4381.7   174.2  4440.3  172.81  4557.4  173.21  4698.7  173.77
  4713.7  172.94    4900  172.46  4930.1  171.48  4957.4  166.42  4987.2  161.35
  4988.9  156.56  4989.4  156.06  5015.3  156.56  5023.1  157.81  5079.8  160.67
  5088.6  162.07  5094.7  165.56  5109.5  168.48  5124.4  168.28  5154.9  171.61
    5217  174.28  5376.6  176.31  5655.5  179.04  5727.1  180.11  5785.2  182.32
#Mann= 11 ,-1 , 0
  4093.3     .05       0  4111.8     .07       0  4139.8     .05       0
  4232.6     .07       0  4353.4     .05       0  4557.4     .12       0
  4957.4    .035       0  4988.9    .035       0  5015.3    .035       0
  5154.9     .07       0  5376.6     .05       0
Bank Sta=4988.9,5015.3
XS Rating Curve= 0 ,0
Exp/Cntr=0.3,0.1

Type RM Length L Ch R = 1 ,85392   ,153,153,153
BEGIN DESCRIPTION:
Mapping XS f1448754
END DESCRIPTION:
XS GIS Cut Line= 3
      2500433.29     13470364.95      2499867.33     13469531.63
      2499322.43     13468809.73
#Sta/Elev= 30
  3993.7  180.27  4137.9  176.99  4227.1  174.81  4428.2  172.49  4591.8  173.43
  4641.8  172.97  4713.3     172  4809.8  171.52  4870.9  171.23  4927.8   165.1
  4956.4  166.02  4977.7  162.29  4984.9  159.16  4985.4   156.9  4985.9   156.4
  5011.9   156.9  5049.8  157.49    5081   163.4  5114.3  162.47  5207.2  165.74
  5235.1  165.33  5243.4  167.76  5249.6  165.34  5264.2  165.29    5285  169.66
  5333.5  171.86    5451  173.98  5594.1  175.96  5777.1  178.27  5905.5  180.11
#Mann= 18 ,-1 , 0
  3993.7    .035       0  4137.9     .07       0  4227.1    .035       0
  4428.2     .12       0  4591.8    .035       0  4641.8     .12       0
  4713.3    .035       0  4809.8     .12       0  4956.4    .035       0
  4977.7     .07       0  4985.4     .05       0  5011.9     .07       0
    5081    .035       0  5207.2     .07       0  5333.5     .12       0
    5451     .07       0  5594.1     .05       0  5777.1     .07       0
Bank Sta=4985.4,5011.9
XS Rating Curve= 0 ,0
Exp/Cntr=0.3,0.1

Type RM Length L Ch R = 1 ,85239   ,537,537,537
BEGIN DESCRIPTION:
PERDIDO CREEK 103.0
END DESCRIPTION:
XS GIS Cut Line= 3
      2500590.73     13470262.69        2499975.       13469425.
       2499360.4     13468594.15
#Sta/Elev= 30
  3955.1   182.2  3989.2  181.04  4187.3  173.65  4287.3  173.19  4364.8  170.36
  4434.8  171.68  4503.4  173.76  4559.8  173.12  4880.9  170.51    4908  168.13
  4945.1  168.18  4966.6  164.01  4982.9   158.2    4995  156.78  4995.5  156.28
  5021.5  156.78  5044.5  157.56    5060  162.17  5102.3  168.61  5142.1  170.69
  5185.3  170.35  5301.3   171.3  5323.5     173  5330.6   171.3  5344.3  173.28
  5460.5  174.72  5559.6  174.91    5565  174.89  5824.5  177.11  6028.2  182.47
#Mann= 15 ,-1 , 0
  3955.1     .12       0  3989.2     .07       0  4434.8     .12       0
  4503.4     .07       0  4559.8     .12       0  4982.9    .035       0
    4995    .035       0  5021.5    .035       0    5060      .1       0
  5142.1    .035       0  5185.3     .07       0  5301.3    .035       0
  5460.5     .07       0  5559.6     .05       0    5565     .07       0
Bank Sta=4995,5021.5
XS Rating Curve= 0 ,0
Exp/Cntr=0.3,0.1

Type RM Length L Ch R = 1 ,84702   ,587,587,587
BEGIN DESCRIPTION:
PERDIDO CREEK 102.0
END DESCRIPTION:
XS GIS Cut Line= 3
      2500825.01     13470125.01        2500325.       13469025.
      2499524.99     13468224.99
#Sta/Elev= 30
    3796   185.1  3837.1  184.74    3885  184.29  3902.6  182.21  4005.8  179.79
    4089  175.13  4202.4  167.91  4257.4  171.92  4288.1  172.42  4776.9  169.74
    4800  168.58    4840  162.66  4874.7  166.81  4897.8  166.65  4938.4  161.69
  4949.4  156.81    4969  156.08  4969.5  155.58  4995.6  156.08  5018.5  157.14
  5032.6  160.15  5046.7  166.38  5056.6  167.59  5145.7  171.96  5400.3  170.59
  5648.4  173.91  5730.5  176.24  5824.6  178.61  5865.7  178.15  6135.7  187.32
#Mann= 10 ,-1 , 0
    3796     .07       0  3837.1    .035       0    4089     .12       0
    4840    .035       0    4969    .035       0  4995.6    .035       0
  5056.6     .07       0  5648.4     .12       0  5730.5    .035       0
  5865.7     .07       0
Bank Sta=4969,4995.6
XS Rating Curve= 0 ,0
Exp/Cntr=0.3,0.1

Type RM Length L Ch R = 1 ,84115   ,501,501,501
BEGIN DESCRIPTION:
PERDIDO CREEK 101.0
END DESCRIPTION:
XS GIS Cut Line= 3
        2500975.     13470074.97        2500775.       13468675.
      2499974.97     13467874.97
#Sta/Elev= 30
  3586.1  186.54  3905.5  178.44    3980  177.06  4121.5  171.65  4212.4  169.64
  4333.6  171.34  4606.3  170.55  4848.8  168.08  4958.9  169.21  5000.3  158.19
  5001.1  154.93  5001.6  154.43  5027.8  154.93  5056.9  155.82  5085.1  162.21
  5098.7  162.81  5115.1  164.81    5170  167.89    5269  170.35  5325.6   167.1
  5385.8  165.65  5499.1  167.92  5551.8   169.6  5608.4   169.4    5665  172.33
  5768.3  173.88  5827.2  175.67  5912.1  178.81  6114.4  186.44  6131.7  187.12
#Mann= 13 ,-1 , 0
  3586.1    .035       0  3905.5     .12       0  4958.9    .035       0
  5001.1    .035       0  5027.8    .035       0  5098.7     .12       0
  5115.1     .12       0  5385.8     .07       0  5499.1     .12       0
  5768.3     .07       0  5827.2     .12       0  5912.1     .07       0
  6114.4     .05       0
Bank Sta=5001.1,5027.8
XS Rating Curve= 0 ,0
Exp/Cntr=0.3,0.1

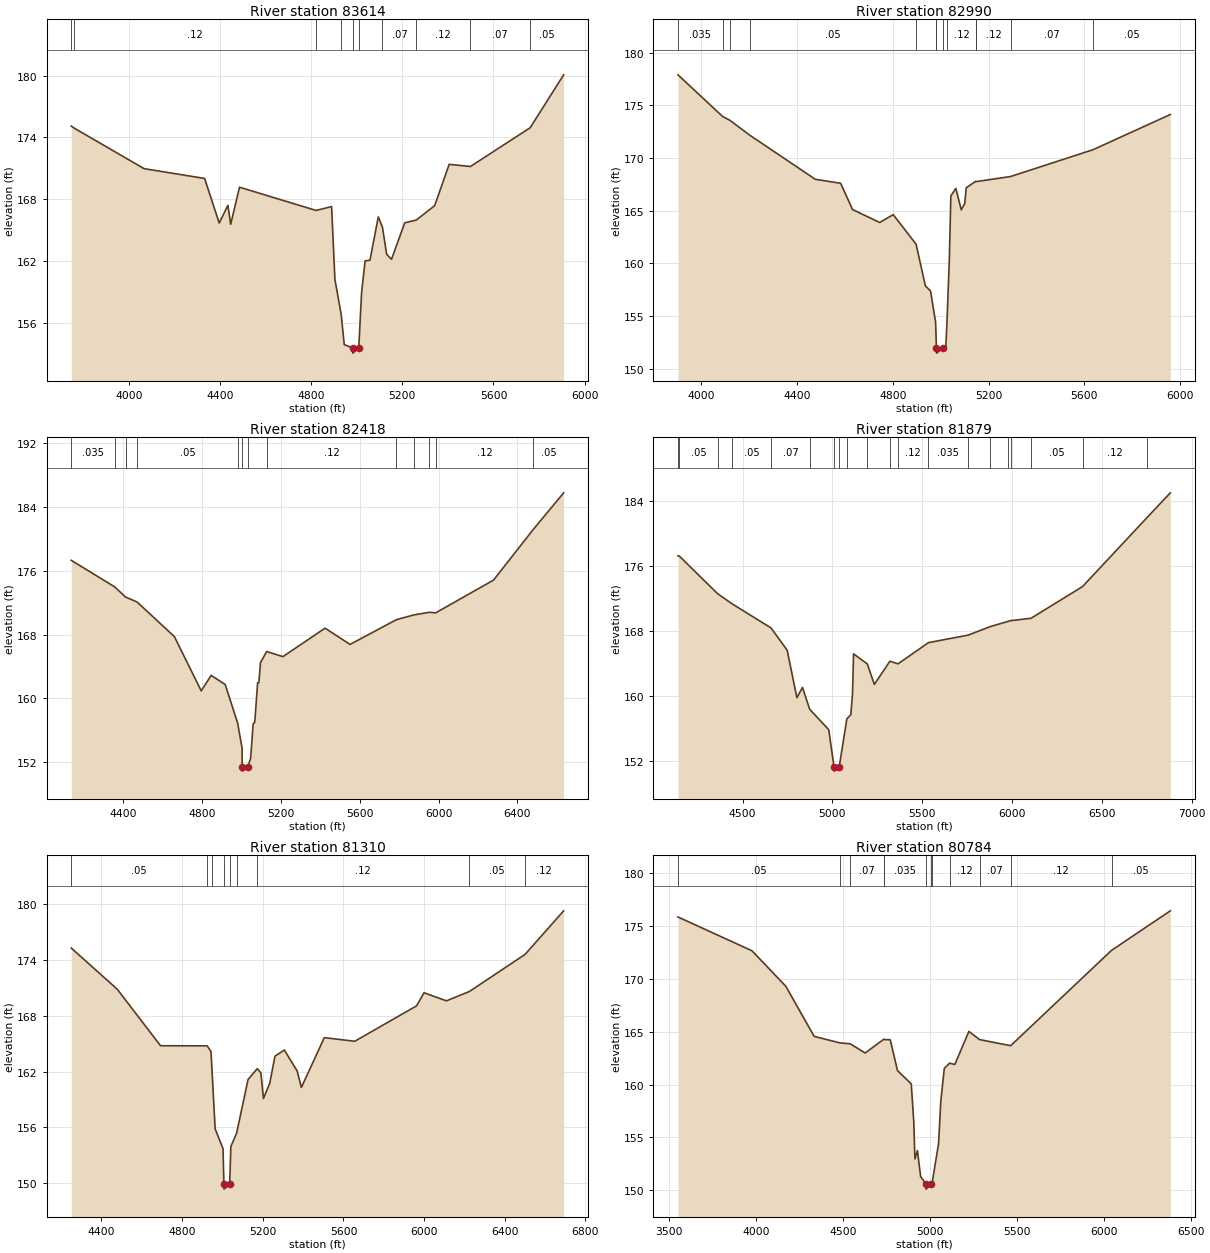
Type RM Length L Ch R = 1 ,83614   ,624,624,624
BEGIN DESCRIPTION:
PERDIDO CREEK 100.0
END DESCRIPTION:
XS GIS Cut Line= 3
      2501250.44     13469477.97      2500997.93      13468251.5
        2500225.       13467775.
#Sta/Elev= 30
  3747.8  175.09  3761.1  174.89  4067.3  170.96  4332.8  170.01  4396.9  165.68
  4434.9   167.4  4447.2  165.56  4485.9  169.16  4822.2   166.9  4889.9  167.28
  4904.5   160.2  4931.9  156.82  4945.4  153.88  4982.3  153.55  4982.8  153.05
  5009.1  153.55  5021.5  158.92  5036.9  162.01  5058.2  162.07  5094.8  166.28
    5113  165.28  5131.5  162.65  5152.8  162.16  5210.7   165.7  5261.5  165.97
  5342.1  167.37  5405.9  171.38  5499.1  171.17    5761  174.93    5908  180.07
#Mann= 10 ,-1 , 0
  3747.8     .07       0  3761.1     .12       0  4822.2     .05       0
  4931.9    .035       0  4982.3     .05       0  5009.1    .035       0
    5113     .07       0  5261.5     .12       0  5499.1     .07       0
    5761     .05       0
Bank Sta=4982.3,5009.1
XS Rating Curve= 0 ,0
Exp/Cntr=0.3,0.1

Type RM Length L Ch R = 1 ,82990   ,572,572,572
BEGIN DESCRIPTION:
PERDIDO CREEK 99.0
END DESCRIPTION:
XS GIS Cut Line= 3
      2502225.03     13468575.03        2501425.       13467825.
      2500668.59     13467236.03
#Sta/Elev= 30
  3903.6  177.89  4090.3  173.93  4120.5  173.57  4202.6  172.17  4476.8  167.97
  4582.8  167.59  4632.2   165.1  4745.5  163.87  4802.2  164.61  4897.6  161.81
  4936.5  157.84    4958  157.36    4979  154.42  4982.4   152.1  4982.6  151.96
  4983.1  151.46    5011  151.96  5021.9  152.08  5026.8  154.51  5036.4  160.33
  5042.8  166.39  5063.6  167.11  5086.2  165.07  5100.7  165.66    5107  167.17
  5146.8  167.78  5148.7  167.75    5292  168.23  5636.3  170.78  5958.9  174.12
#Mann= 13 ,-1 , 0
  3903.6    .035       0  4090.3     .05       0  4120.5    .035       0
  4202.6     .05       0  4897.6    .035       0  4982.4     .12       0
  4982.6     .05       0    5011     .12       0  5026.8     .12       0
  5146.8     .07       0  5148.7     .12       0    5292     .07       0
  5636.3     .05       0
Bank Sta=4982.6,5011
XS Rating Curve= 0 ,0
Exp/Cntr=0.3,0.1

Type RM Length L Ch R = 1 ,82418   ,539,539,539
BEGIN DESCRIPTION:
PERDIDO CREEK 98.0
END DESCRIPTION:
XS GIS Cut Line= 3
      2502424.98     13468324.98        2501925.       13467625.
      2500625.02     13466625.02
#Sta/Elev= 30
  4134.9   177.3  4355.4  173.97  4410.5   172.7  4469.3  172.07  4658.4  167.74
  4794.8  160.94  4845.2  162.88  4916.5  161.74  4980.1  156.87  5002.4  153.72
  5002.6  151.38  5003.1  150.88  5031.1  151.38  5045.6  152.49  5058.5  156.81
  5066.7     157  5081.2  161.95  5087.5  161.96  5095.7  164.48    5127  165.87
  5209.6  165.23  5423.7   168.8  5550.5  166.76  5785.8  169.86  5874.7  170.46
  5953.8  170.79  5984.9  170.71  6279.1  174.82  6481.6  181.19  6635.2  185.76
#Mann= 13 ,-1 , 0
  4134.9    .035       0  4355.4     .05       0  4410.5    .035       0
  4469.3     .05       0  4980.1     .12       0  5002.6     .05       0
  5031.1     .12       0    5127     .12       0  5785.8     .07       0
  5874.7     .12       0  5953.8     .07       0  5984.9     .12       0
  6481.6     .05       0
Bank Sta=5002.6,5031.1
XS Rating Curve= 0 ,0
Exp/Cntr=0.3,0.1

Type RM Length L Ch R = 1 ,81879   ,569,569,569
BEGIN DESCRIPTION:
PERDIDO CREEK 97.0
END DESCRIPTION:
XS GIS Cut Line= 3
        2502675.     13468175.01        2502375.       13467375.
      2500775.01       13466375.
#Sta/Elev= 30
    4140  177.25  4147.4  177.22  4360.4  172.61  4440.6  171.37    4658   168.4
  4747.9  165.67  4802.2  159.83  4833.3  161.09  4873.3  158.41  4979.3   155.9
  5009.1  151.31  5009.6  150.81  5037.6  151.31  5080.3  157.23  5102.3  157.74
  5111.7  160.26  5117.6  165.21  5194.2  163.98  5233.2  161.46    5320  164.31
  5365.3  163.99  5534.7  166.59  5756.6  167.52  5877.6  168.55  5977.6   169.2
  5991.5  169.29  6105.4  169.58  6392.7  173.48  6749.8  181.91  6881.2  184.99
#Mann= 20 ,-1 , 0
    4140     .12       0  4147.4     .05       0  4360.4     .07       0
  4440.6     .05       0    4658     .07       0  4873.3     .05       0
  5009.1     .05       0  5037.6    .035       0  5080.3     .12       0
  5194.2     .12       0    5320     .12       0  5365.3     .12       0
  5534.7    .035       0  5756.6     .12       0  5877.6     .07       0
  5977.6     .12       0  5991.5     .07       0  6105.4     .05       0
  6392.7     .12       0  6749.8     .07       0
Bank Sta=5009.1,5037.6
XS Rating Curve= 0 ,0
Exp/Cntr=0.3,0.1

Type RM Length L Ch R = 1 ,81310   ,526,526,526
BEGIN DESCRIPTION:
PERDIDO CREEK 96.0
END DESCRIPTION:
XS GIS Cut Line= 3
      2503124.97     13467524.96        2502675.       13466925.
      2501075.04     13466375.02
#Sta/Elev= 30
  4250.3  175.26  4478.4  170.84    4693  164.77  4924.1  164.76    4943  164.15
  4949.2  161.75  4963.8  155.84  5002.9  153.71  5007.1  149.87  5007.6  149.37
  5035.7  149.87  5041.8  153.96  5069.9  155.35  5127.1  161.15  5172.8  162.31
  5190.6  161.86  5203.3   159.1  5234.6  160.74  5260.5  163.65  5306.9  164.31
  5370.4  162.06  5391.5  160.29  5505.2  165.64  5655.9  165.25  5962.5  169.05
  5999.8  170.46  6110.6  169.59  6224.2  170.59  6500.8  174.58  6692.1  179.26
#Mann= 9 ,-1 , 0
  4250.3     .05       0  4924.1     .07       0  4949.2    .035       0
  5007.1    .035       0  5035.7    .035       0  5069.9     .12       0
  5172.8     .12       0  6224.2     .05       0  6500.8     .12       0
Bank Sta=5007.1,5035.7
XS Rating Curve= 0 ,0
Exp/Cntr=0.3,0.1

Type RM Length L Ch R = 1 ,80784   ,1538,1538,1538
BEGIN DESCRIPTION:
Mapping XS 5a944a48
END DESCRIPTION:
XS GIS Cut Line= 3
      2503523.91     13467541.86       2502688.4     13466424.23
      2501268.45     13466229.12
#Sta/Elev= 30
  3550.4  175.86  3975.8  172.66  4169.7  169.31  4333.1  164.56    4482  163.94
  4540.4  163.86  4626.1  162.99  4733.6   164.3  4735.3  164.26    4770  164.24
  4811.6  161.33  4890.8  160.06  4905.4  156.44  4911.7  152.98  4926.3  153.75
  4944.5   151.3  4975.3  150.61  4975.8  150.11    5004  150.61  5011.9  150.82
  5047.7  154.42  5060.3  158.39  5080.5  161.52  5110.8  162.03    5141   161.9
  5221.8  165.03  5282.9  164.26  5461.8  163.68  6041.5   172.7  6379.1  176.44
#Mann= 12 ,-1 , 0
  3550.4     .05       0    4482     .12       0  4540.4     .07       0
  4733.6     .12       0  4735.3    .035       0  4975.3    .035       0
    5004    .035       0  5011.9     .12       0  5110.8     .12       0
  5282.9     .07       0  5461.8     .12       0  6041.5     .05       0
Bank Sta=4975.3,5004
XS Rating Curve= 0 ,0
Exp/Cntr=0.3,0.1

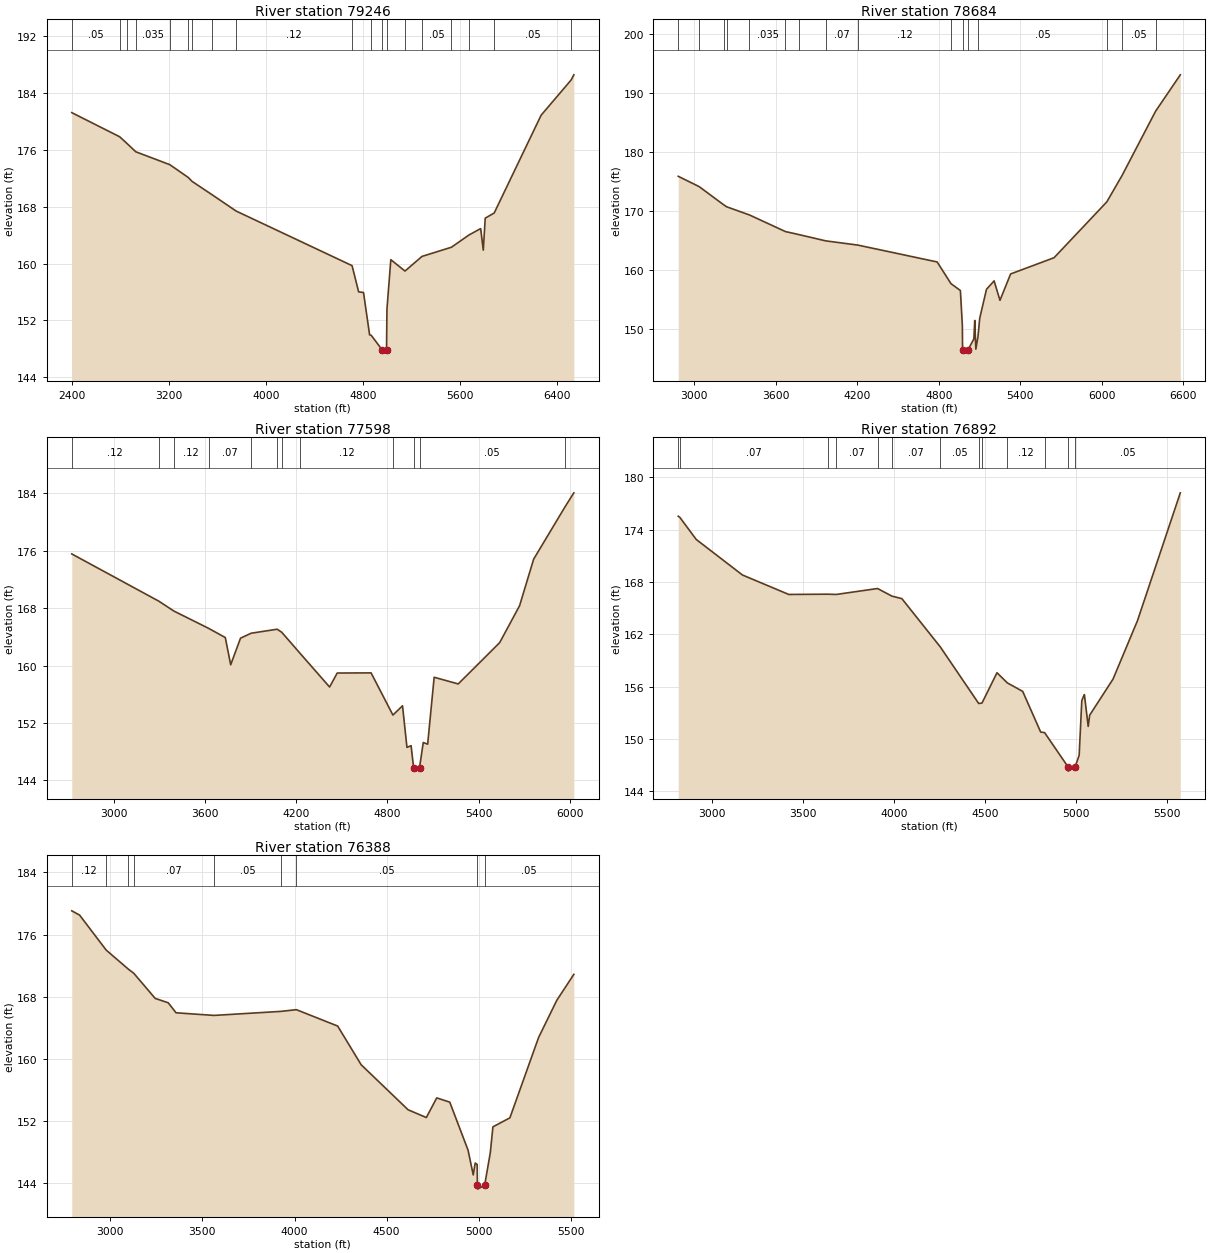
Type RM Length L Ch R = 1 ,79246   ,562,562,562
BEGIN DESCRIPTION:
Mapping XS d684f9fd
END DESCRIPTION:
XS GIS Cut Line= 3
      2503795.18      13467867.4       2503523.9     13465295.76
      2502764.52     13463939.72
#Sta/Elev= 30
  2400.6  181.24    2795  177.85  2853.4  176.94  2928.8  175.73  3208.9  173.92
  3358.4  172.15    3394  171.55  3557.3  169.69  3756.2  167.39  4711.9  159.71
  4766.1  156.02  4806.3  155.93  4856.6  149.97  4870.5   149.9  4958.2   147.9
  4959.2   147.4  4996.2   147.9  4999.5  153.56  5031.5  160.55  5148.4  158.95
  5288.7  161.01  5531.4   162.3  5676.5  164.03  5772.4  164.92    5794  161.89
    5810  166.39    5884  167.12    6271  180.88  6518.1  185.83  6540.7  186.56
#Mann= 19 ,-1 , 0
  2400.6     .05       0    2795    .035       0  2853.4     .05       0
  2928.8    .035       0  3208.9     .05       0  3358.4    .035       0
    3394     .05       0  3557.3     .07       0  3756.2     .12       0
  4711.9    .035       0  4870.5     .12       0  4958.2     .05       0
  4996.2     .12       0  5148.4     .07       0  5288.7     .05       0
  5531.4    .035       0  5676.5     .12       0    5884     .05       0
  6518.1     .12       0
Bank Sta=4958.2,4996.2
XS Rating Curve= 0 ,0
Exp/Cntr=0.3,0.1

Type RM Length L Ch R = 1 ,78684   ,1086,1086,1086
BEGIN DESCRIPTION:
Mapping XS a2ca71d8
END DESCRIPTION:
XS GIS Cut Line= 3
      2503968.78     13467021.06      2504098.99     13465165.55
      2502949.39     13463733.97
#Sta/Elev= 30
  2881.2  175.91  3035.4  174.16  3215.1   171.1  3237.8  170.75  3405.6  169.37
  3670.3  166.56    3769  166.05  3966.3  164.99  4203.9  164.27  4787.2  161.42
  4889.5  157.74  4958.4  156.59  4972.8  150.69  4974.5   146.5  4975.5     146
  5012.8   146.5  5057.6  148.41  5064.1  151.53    5072  146.67  5087.9  148.82
  5100.8  151.91  5150.4  156.79  5206.5  158.22  5249.7  154.93  5328.1  159.39
  5648.1  162.14  6036.2  171.58  6148.2  176.03  6395.7  186.93  6577.3  193.07
#Mann= 16 ,-1 , 0
  2881.2     .12       0  3035.4     .05       0  3215.1    .035       0
  3237.8     .05       0  3405.6    .035       0  3670.3     .12       0
    3769    .035       0  3966.3     .07       0  4203.9     .12       0
  4889.5    .035       0  4974.5     .05       0  5012.8    .035       0
  5087.9     .05       0  6036.2    .035       0  6148.2     .05       0
  6395.7     .12       0
Bank Sta=4974.5,5012.8
XS Rating Curve= 0 ,0
Exp/Cntr=0.3,0.1

Type RM Length L Ch R = 1 ,77598   ,706,706,706
BEGIN DESCRIPTION:
Mapping XS 2d0e2bb7
END DESCRIPTION:
XS GIS Cut Line= 3
      2506431.85     13465501.89      2504630.68     13464156.43
      2503762.89     13463559.83
#Sta/Elev= 30
  2725.1  175.56  3297.7  168.97  3396.9  167.59    3625  165.18  3734.6   163.9
  3770.1   160.1  3834.7  163.81  3904.6   164.5  4075.9  165.06  4105.6  164.64
  4225.8  161.71  4420.4     157  4470.5  158.95  4693.3  158.97  4836.7  153.09
  4899.9  154.38  4929.1  148.58  4956.2  148.82  4972.7  145.77  4973.7  145.27
  5011.9  145.77  5036.2  149.26  5065.2  149.03  5107.9  158.36  5266.2  157.43
  5538.4  163.18  5669.5  168.33  5762.1  174.83  5967.7   182.1  6026.4  184.08
#Mann= 12 ,-1 , 0
  2725.1     .12       0  3297.7     .07       0  3396.9     .12       0
    3625     .07       0  3904.6    .035       0  4075.9     .05       0
  4105.6    .035       0  4225.8     .12       0  4836.7     .05       0
  4972.7     .05       0  5011.9     .05       0  5967.7    .035       0
Bank Sta=4972.7,5011.9
XS Rating Curve= 0 ,0
Exp/Cntr=0.3,0.1

Type RM Length L Ch R = 1 ,76892   ,504,504,504
BEGIN DESCRIPTION:
PERDIDO CREEK 88.0
END DESCRIPTION:
XS GIS Cut Line= 3
      2506624.98     13465174.98        2505075.       13463625.
        2504725.       13463175.
#Sta/Elev= 30
  2812.8  175.56  2821.9  175.42  2911.8  172.89  3166.3  168.81  3420.9  166.58
  3635.2  166.61  3681.9  166.58  3909.4  167.26  3988.4  166.39  4043.1   166.1
  4254.2  160.57  4465.8  154.07  4483.9  154.12  4566.4   157.6  4622.9  156.44
  4707.8  155.46  4806.8  150.79  4828.2  150.73  4956.9  146.81  4957.9  146.31
  4996.2  146.81  5018.4  148.12  5032.9  154.38    5041  154.83  5047.3  155.09
  5068.2  151.44  5076.3  152.73  5204.8  156.87  5339.6  163.59  5574.9  178.24
#Mann= 13 ,-1 , 0
  2812.8     .12       0  2821.9     .07       0  3635.2     .05       0
  3681.9     .07       0  3909.4     .05       0  3988.4     .07       0
  4254.2     .05       0  4465.8     .12       0  4483.9     .05       0
  4622.9     .12       0  4828.2     .05       0  4956.9     .05       0
  4996.2     .05       0
Bank Sta=4956.9,4996.2
XS Rating Curve= 0 ,0
Exp/Cntr=0.3,0.1

Type RM Length L Ch R = 1 ,76388   ,598,598,598
BEGIN DESCRIPTION:
PERDIDO CREEK 87.0
END DESCRIPTION:
XS GIS Cut Line= 3
      2507025.02     13464975.02        2505475.       13463425.
      2505124.98     13463024.98
#Sta/Elev= 30
  2791.7  179.05  2834.2   178.5  2978.6  173.99  3099.2  171.53  3128.1  171.01
  3244.3  167.77    3315  167.21  3357.4  165.92    3563  165.58  3926.4   166.1
  4010.3  166.32  4234.2  164.21  4361.5  159.23  4616.1  153.43  4715.1  152.43
  4771.6  154.96  4842.3  154.41  4941.3  148.24  4969.6  145.04  4980.2  146.57
  4990.9  146.39  4992.1  143.71  4993.1  143.21  5031.4  143.71  5062.1  147.89
  5076.3  151.23  5168.4  152.39    5324  162.73  5422.7  167.52  5515.3  170.87
#Mann= 9 ,-1 , 0
  2791.7     .12       0  2978.6     .07       0  3099.2     .12       0
  3128.1     .07       0    3563     .05       0  3926.4     .07       0
  4010.3     .05       0  4992.1     .05       0  5031.4     .05       0
Bank Sta=4992.1,5031.4
XS Rating Curve= 0 ,0
Exp/Cntr=0.3,0.1