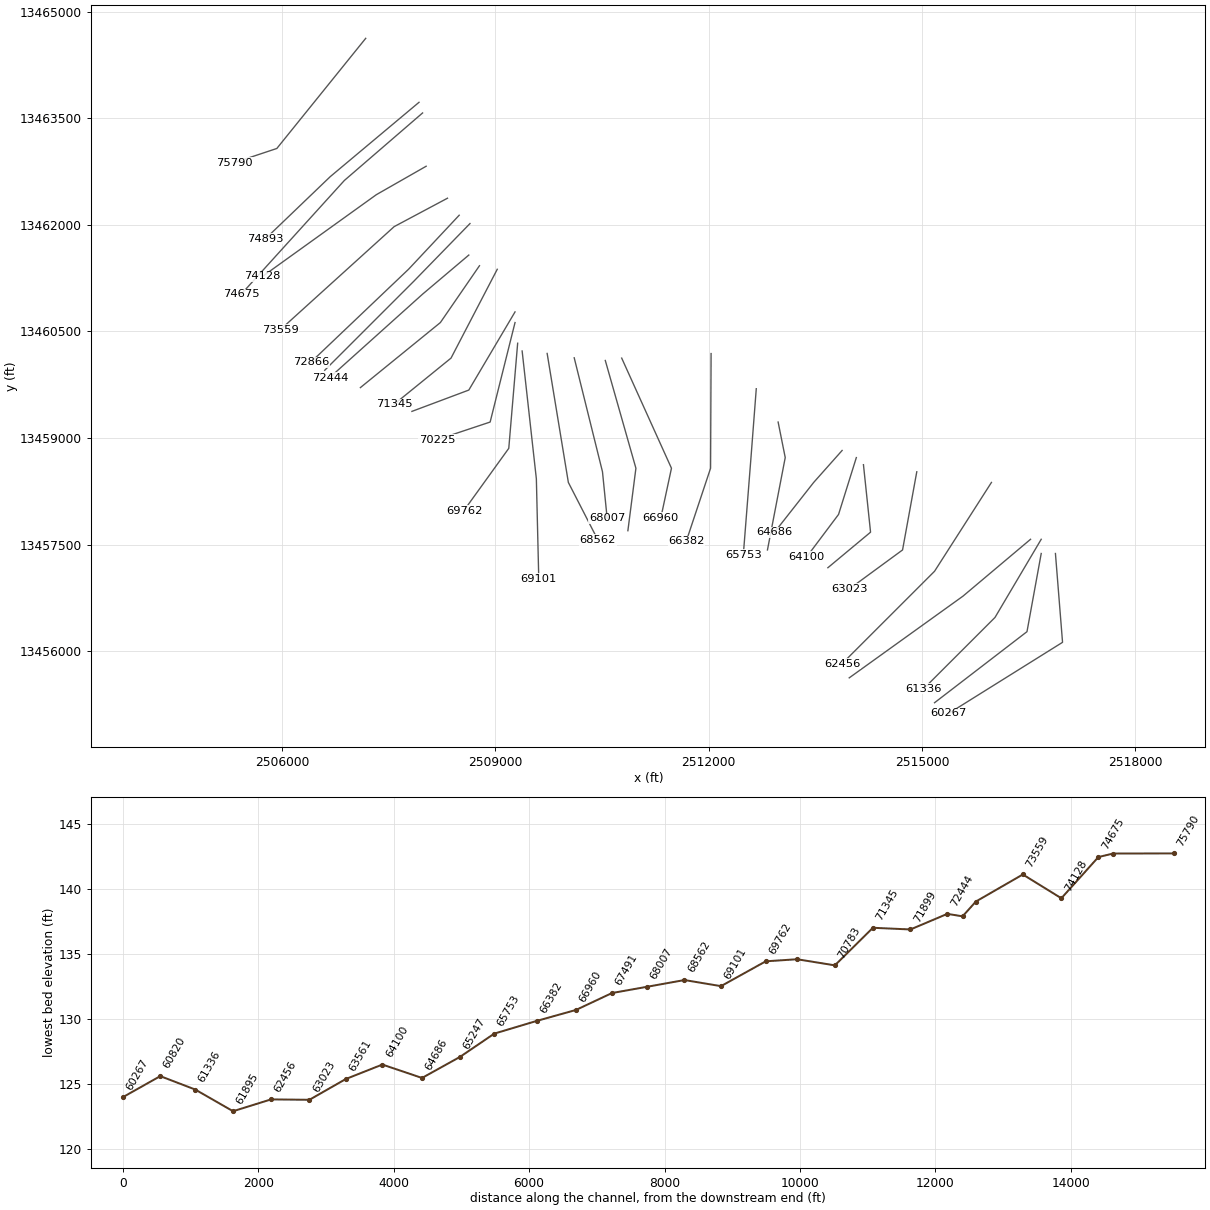
HEC-RAS study PERDIDO CREEK.prj: PERDIDO CREEK Base Level Engineering

--- PERDIDO CREEK.g01 (geometry) --- (continued)

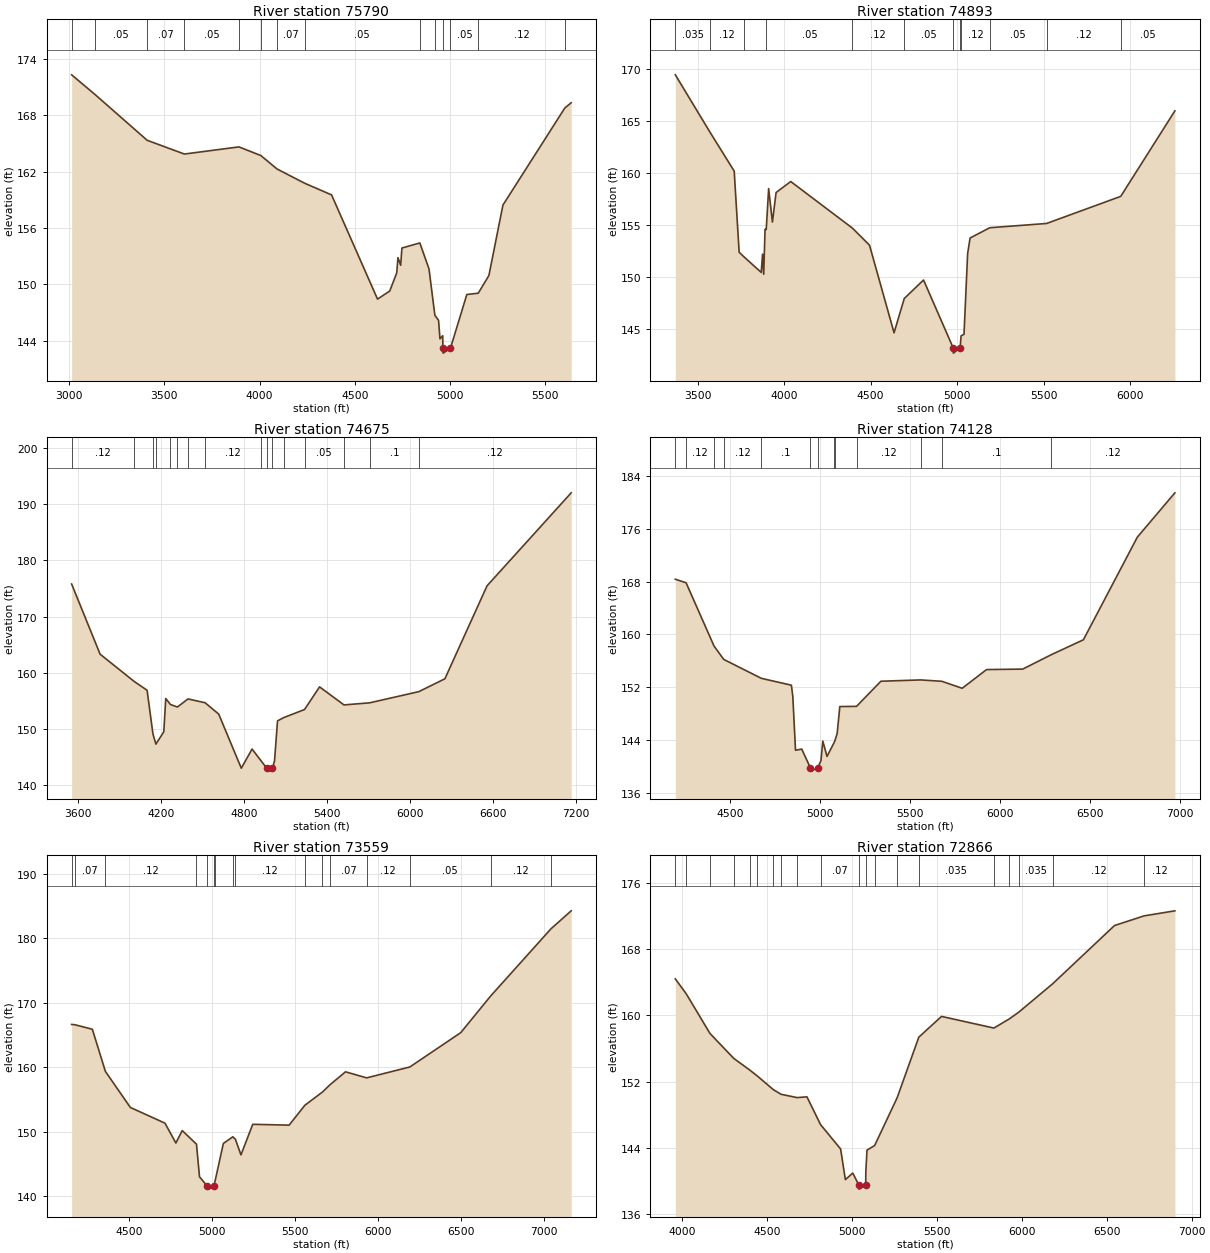
Type RM Length L Ch R = 1 ,75790   ,897,897,897
BEGIN DESCRIPTION:
PERDIDO CREEK 86.0
END DESCRIPTION:
XS GIS Cut Line= 3
      2507175.02     13464625.03        2505925.       13463075.
      2505325.02     13462875.01
#Sta/Elev= 30
  3012.9  172.28  3133.8  170.22  3409.7  165.32  3605.1  163.86  3891.5  164.62
  4006.8   163.7  4091.8  162.27  4236.5  160.76    4378  159.52  4619.5  148.44
  4683.5   149.3  4720.3  151.22  4726.7  152.85  4741.1  152.04  4747.5  153.87
  4841.6  154.41  4889.8  151.65  4920.7  146.71  4939.9  146.19  4947.4  144.22
  4961.8  144.55  4962.9   143.2  4963.9   142.7  5002.2   143.2  5088.5  148.93
  5148.6  149.07  5204.4  150.95  5278.2  158.44    5603  168.75  5636.6  169.31
#Mann= 14 ,-1 , 0
  3012.9     .12       0  3133.8     .05       0  3409.7     .07       0
  3605.1     .05       0  3891.5     .07       0  4006.8     .05       0
  4091.8     .07       0  4236.5     .05       0  4841.6     .12       0
  4920.7     .05       0  4962.9     .05       0  5002.2     .05       0
  5148.6     .12       0    5603     .05       0
Bank Sta=4962.9,5002.2
XS Rating Curve= 0 ,0
Exp/Cntr=0.3,0.1

Type RM Length L Ch R = 1 ,74893   ,218,218,218
BEGIN DESCRIPTION:
PERDIDO CREEK 85.0
END DESCRIPTION:
XS GIS Cut Line= 3
      2507924.96     13463724.97      2506676.57     13462678.79
      2505769.07     13461807.87
#Sta/Elev= 30
  3371.2  169.48  3571.4  163.96  3711.4  160.21    3740   152.4  3768.4  151.95
  3867.5  150.46  3875.3  152.22  3881.8  150.28  3889.6  154.61  3896.5  154.59
  3910.4  158.53  3932.2  155.31  3953.4  158.15    4038  159.21  4394.7  154.72
  4493.2  153.08  4635.1  144.65  4694.1  147.95  4805.5  149.73  4976.8  143.19
  4977.8  142.69  5016.9  143.19  5022.4  144.36  5039.2   144.5  5060.3  152.29
  5074.4  153.77  5187.9  154.76  5516.3  155.17  5944.9  157.78  6257.8  166.01
#Mann= 12 ,-1 , 0
  3371.2    .035       0  3571.4     .12       0  3768.4     .07       0
  3896.5     .05       0  4394.7     .12       0  4694.1     .05       0
  4976.8     .05       0  5016.9     .05       0  5022.4     .12       0
  5187.9     .05       0  5516.3     .12       0  5944.9     .05       0
Bank Sta=4976.8,5016.9
XS Rating Curve= 0 ,0
Exp/Cntr=0.3,0.1

Type RM Length L Ch R = 1 ,74675   ,547,547,547
BEGIN DESCRIPTION:
PERDIDO CREEK 84.0
END DESCRIPTION:
XS GIS Cut Line= 3
        2507975.       13463575.        2506875.       13462625.
      2505425.02     13461025.02
#Sta/Elev= 30
  3551.8   175.8  3757.5  163.29    4005   158.4  4097.5  156.85  4139.7  149.07
    4161  147.24  4218.2  149.43  4232.5  155.38  4266.5   154.3    4317  153.86
  4393.2   155.3  4516.8  154.62  4615.3   152.6  4778.7  142.94  4856.6  146.36
  4918.5  144.36  4963.8  142.92  4964.8  142.42  5003.9  142.92  5019.1  144.24
  5040.7  151.38  5085.6  151.97    5236  153.41  5344.8  157.45  5521.5  154.23
  5707.9  154.61  6062.6   156.6  6251.1  158.89    6556  175.48  7164.5  192.07
#Mann= 16 ,-1 , 0
  3551.8     .12       0    4005     .07       0  4139.7     .12       0
    4161     .07       0  4266.5     .12       0    4317     .07       0
  4393.2     .05       0  4516.8     .12       0  4918.5     .05       0
  4963.8     .05       0  5003.9     .05       0  5085.6     .12       0
    5236     .05       0  5521.5     .12       0  5707.9      .1       0
  6062.6     .12       0
Bank Sta=4963.8,5003.9
XS Rating Curve= 0 ,0
Exp/Cntr=0.3,0.1

Type RM Length L Ch R = 1 ,74128   ,569,569,569
BEGIN DESCRIPTION:
PERDIDO CREEK 83.0
END DESCRIPTION:
XS GIS Cut Line= 3
      2508025.02     13462825.01        2507325.       13462425.
      2505724.97     13461274.98
#Sta/Elev= 30
  4194.1  168.35  4253.9  167.81  4409.2  158.22  4463.1  156.19  4672.2  153.32
  4839.1  152.28    4847  150.61  4862.1  142.42  4896.7  142.59  4944.9  139.75
  4945.9  139.25  4985.3  139.75  5003.4  140.83  5013.9   143.8  5037.2  141.48
  5076.2  143.55  5082.6  143.98  5093.7  144.98  5108.4  149.04  5201.3  149.07
  5336.7  152.88  5557.2  153.08  5675.8  152.87  5788.5  151.81    5924  154.65
  6124.9  154.72  6281.3  156.87  6462.5  159.17  6762.1  174.73  6970.8  181.45
#Mann= 13 ,-1 , 0
  4194.1     .07       0  4253.9     .12       0  4409.2     .07       0
  4463.1     .12       0  4672.2      .1       0  4944.9     .05       0
  4985.3      .1       0  5076.2    .035       0  5082.6     .07       0
  5201.3     .12       0  5557.2     .05       0  5675.8      .1       0
  6281.3     .12       0
Bank Sta=4944.9,4985.3
XS Rating Curve= 0 ,0
Exp/Cntr=0.3,0.1

Type RM Length L Ch R = 1 ,73559   ,693,693,693
BEGIN DESCRIPTION:
PERDIDO CREEK 82.0
END DESCRIPTION:
XS GIS Cut Line= 3
      2508325.01       13462375.        2507575.       13461975.
      2505974.99     13460524.99
#Sta/Elev= 30
  4154.3  166.61  4173.5  166.57    4279  165.87  4357.7  159.33  4508.1  153.74
  4716.4  151.31  4782.2  148.23  4820.5  150.16  4906.4  148.05  4924.6  142.99
  4970.3  141.58  4971.3  141.08  5010.7  141.58  5018.3  142.33  5068.2  148.16
  5125.1  149.19  5140.9  148.81  5174.3  146.39  5245.3  151.13  5464.2     151
  5559.6  154.09    5665  156.13  5710.6  157.26  5804.2  159.27  5931.4  158.33
  6191.7  160.02  6498.2  165.34  6678.7  171.03  7042.1  181.45  7163.6  184.23
#Mann= 16 ,-1 , 0
  4154.3     .12       0  4173.5     .07       0  4357.7     .12       0
  4906.4    .035       0  4970.3    .035       0  5010.7    .035       0
  5018.3     .12       0  5125.1     .07       0  5140.9     .12       0
  5559.6     .07       0    5665     .12       0  5710.6     .07       0
  5931.4     .12       0  6191.7     .05       0  6678.7     .12       0
  7042.1    .035       0
Bank Sta=4970.3,5010.7
XS Rating Curve= 0 ,0
Exp/Cntr=0.3,0.1

Type RM Length L Ch R = 1 ,72866   ,197,197,197
BEGIN DESCRIPTION:
PERDIDO CREEK 81.0
END DESCRIPTION:
XS GIS Cut Line= 3
      2508489.72     13462135.62      2507778.79     13461376.57
      2506402.02     13460065.29
#Sta/Elev= 30
    3960  164.43  4024.3  162.62  4163.9  157.83  4303.5  154.82    4399  153.39
    4443  152.68  4537.8  151.02  4582.6  150.47  4676.6  150.07  4734.9  150.16
  4814.9  146.81  4933.3  143.85  4961.1  140.15  5004.8  140.94  5040.2   139.5
  5041.2     139  5080.8   139.5  5081.6  141.08  5088.5  143.72  5133.5  144.27
  5265.6  150.03  5393.6  157.38  5527.3  159.89  5835.7  158.48  5926.6  159.59
  5983.1  160.42  6181.8  163.84  6545.8  170.88  6720.1  172.05  6901.3  172.66
#Mann= 20 ,-1 , 0
    3960    .035       0  4024.3     .07       0  4163.9     .12       0
  4303.5     .12       0    4399    .063       0    4443     .12       0
  4537.8    .035       0  4582.6     .12       0  4676.6    .035       0
  4814.9     .07       0  5040.2     .05       0  5080.8     .07       0
  5133.5     .12       0  5265.6     .12       0  5393.6    .035       0
  5835.7    .035       0  5926.6     .12       0  5983.1    .035       0
  6181.8     .12       0  6720.1     .12       0
Bank Sta=5040.2,5080.8
XS Rating Curve= 0 ,0
Exp/Cntr=0.3,0.1

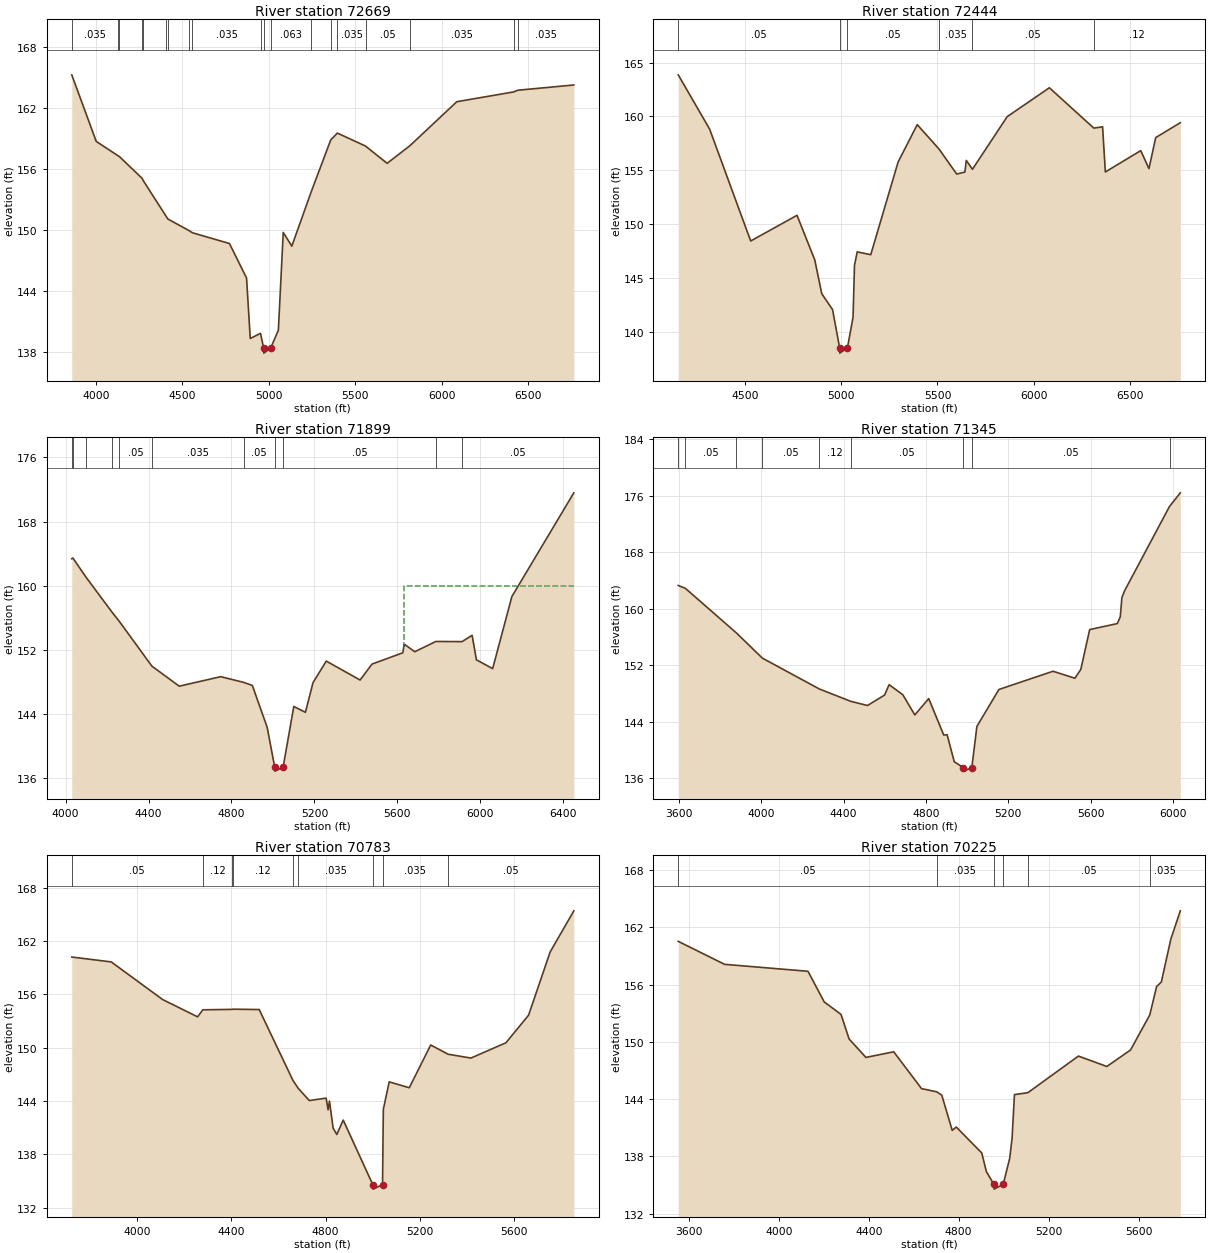
Type RM Length L Ch R = 1 ,72669   ,225,225,225
BEGIN DESCRIPTION:
Mapping XS 275e2e87
END DESCRIPTION:
XS GIS Cut Line= 3
      2508641.64     13462018.44       2507851.7     13461206.81
       2506598.7      13459953.8
#Sta/Elev= 30
    3861  165.28  4002.5  158.72  4131.2  157.28  4134.3  157.26  4268.1  155.08
  4275.8  154.82  4405.1  151.39  4417.3  151.07    4542  149.91  4558.8  149.72
  4773.2  148.66  4872.2  145.26  4893.6   139.3  4952.9  139.81    4971  138.36
    4972  137.86  5011.7  138.36  5056.2  140.12  5084.5  149.75    5134   148.4
  5246.2  153.75    5359  158.86  5397.8  159.54  5560.4  158.26  5685.5  156.56
  5817.4   158.3  6088.5  162.63  6418.7   163.6  6440.4  163.76  6765.6  164.28
#Mann= 19 ,-1 , 0
    3861    .035       0  4131.2    .063       0  4134.3    .035       0
  4268.1    .063       0  4275.8    .035       0  4405.1    .063       0
  4417.3    .035       0    4542    .063       0  4558.8    .035       0
  4952.9    .063       0    4971     .05       0  5011.7    .063       0
  5246.2     .05       0    5359    .063       0  5397.8    .035       0
  5560.4     .05       0  5817.4    .035       0  6418.7     .05       0
  6440.4    .035       0
Bank Sta=4971,5011.7
XS Rating Curve= 0 ,0
Exp/Cntr=0.3,0.1

Type RM Length L Ch R = 1 ,72444   ,545,545,545
BEGIN DESCRIPTION:
PERDIDO CREEK 80.0
END DESCRIPTION:
XS GIS Cut Line= 3
      2508625.01     13461575.01        2507975.       13461025.
      2506668.85     13459851.15
#Sta/Elev= 30
  4153.6  163.86  4316.8  158.82  4529.9  148.45  4770.5  150.83  4862.8  146.69
  4899.1  143.56  4955.1  142.09  4991.8  138.55  4992.8  138.05  5032.5  138.55
  5061.5  141.38    5069  146.19  5083.2  147.44  5153.5  147.18  5295.5  155.77
  5394.9  159.24  5508.4  156.97  5599.7  154.66  5642.3  154.84  5649.8  155.92
  5681.6   155.1  5862.1  159.98  6081.1  162.66  6311.9  158.92  6357.6  159.04
  6371.9  154.85  6555.7  156.83  6598.3  155.16  6633.5  158.04  6761.2  159.42
#Mann= 6 ,-1 , 0
  4153.6     .05       0  4991.8     .05       0  5032.5     .05       0
  5508.4    .035       0  5681.6     .05       0  6311.9     .12       0
#XS Ineff= 2 , 0
       0                  5394.9       0  159.24
Permanent Ineff=
       F       F
Bank Sta=4991.8,5032.5
XS Rating Curve= 0 ,0
Exp/Cntr=0.3,0.1

Type RM Length L Ch R = 1 ,71899   ,554,554,554
BEGIN DESCRIPTION:
PERDIDO CREEK 79.0
END DESCRIPTION:
XS GIS Cut Line= 3
      2508774.98     13461424.97        2508225.       13460625.
      2507100.33     13459709.76
#Sta/Elev= 30
    4030  163.35  4035.3  163.45  4097.4   161.1  4223.2  156.72  4258.9  155.55
  4416.4  149.95  4548.2  147.45  4748.4  148.64  4859.2  147.92  4900.7  147.54
  4972.4   142.3  5008.4  137.35  5009.4  136.85  5049.1  137.35  5100.6  144.92
  5156.6  144.19  5193.3   147.9  5257.2  150.58  5420.2  148.22  5477.7  150.21
  5626.3  151.62  5632.8   152.7  5683.8  151.75  5785.4  153.03  5911.5  153.01
  5960.3   153.8  5981.1  150.74  6059.4  149.64  6152.1  158.64  6450.8  171.58
#Mann= 11 ,-1 , 0
    4030     .05       0  4035.3     .12       0  4097.4     .05       0
  4223.2     .12       0  4258.9     .05       0  4416.4    .035       0
  4859.2     .05       0  5008.4     .05       0  5049.1     .05       0
  5785.4    .035       0  5911.5     .05       0
#XS Ineff= 2 , 0
       0                    5630       0     160
Permanent Ineff=
       F       F
Bank Sta=5008.4,5049.1
XS Rating Curve= 0 ,0
Exp/Cntr=0.3,0.1

Type RM Length L Ch R = 1 ,71345   ,562,562,562
BEGIN DESCRIPTION:
PERDIDO CREEK 78.0
END DESCRIPTION:
XS GIS Cut Line= 3
      2509024.99     13461374.98        2508375.       13460125.
      2507574.97     13459474.97
#Sta/Elev= 30
  3596.7  163.26    3631  162.87  3878.4  156.57  4005.5  152.98  4282.3  148.61
  4435.4  146.86  4516.6  146.27  4599.4  147.75  4621.5  149.22  4687.8   147.8
  4746.3  144.94    4814  147.25  4886.8  142.09  4903.3  142.13    4938  138.31
  4982.2  137.48  4983.2  136.98  5023.3  137.48    5048  143.31    5155  148.54
  5417.9  151.12  5524.2  150.13  5552.9  151.38    5596  157.02  5730.3  157.87
  5744.7  158.83  5752.6  161.56  5765.8  162.52  5983.9  174.45  6036.4  176.38
#Mann= 9 ,-1 , 0
  3596.7    .035       0    3631     .05       0  3878.4     .07       0
  4005.5     .05       0  4282.3     .12       0  4435.4     .05       0
  4982.2     .05       0  5023.3     .05       0  5983.9    .035       0
Bank Sta=4982.2,5023.3
XS Rating Curve= 0 ,0
Exp/Cntr=0.3,0.1

Type RM Length L Ch R = 1 ,70783   ,558,558,558
BEGIN DESCRIPTION:
PERDIDO CREEK 77.0
END DESCRIPTION:
XS GIS Cut Line= 3
      2509274.99     13460774.98        2508625.       13459675.
      2507824.97     13459374.99
#Sta/Elev= 30
  3722.3  160.21    3890  159.66  4108.5  155.42  4256.6  153.48  4278.8  154.27
  4403.6  154.32  4406.6  154.34  4518.2   154.3  4661.3  146.34  4683.6  145.45
  4730.8  144.06  4802.5  144.33  4810.8  143.02  4816.6     144  4832.2  140.95
  4847.9  140.24  4875.1  141.86  5000.7  134.59  5001.7  134.09    5042  134.59
  5045.4  143.07  5070.3  146.16  5155.7   145.5  5246.5  150.31  5320.7  149.27
  5417.4  148.84    5566  150.56  5662.1  153.66  5753.8  160.78  5854.4  165.41
#Mann= 9 ,-1 , 0
  3722.3     .05       0  4278.8     .12       0  4403.6     .05       0
  4406.6     .12       0  4661.3     .05       0  4683.6    .035       0
  5000.7    .035       0    5042    .035       0  5320.7     .05       0
Bank Sta=5000.7,5042
XS Rating Curve= 0 ,0
Exp/Cntr=0.3,0.1

Type RM Length L Ch R = 1 ,70225   ,463,463,463
BEGIN DESCRIPTION:
PERDIDO CREEK 76.0
END DESCRIPTION:
XS GIS Cut Line= 3
      2509275.01     13460625.04        2508925.       13459225.
        2508175.       13458975.
#Sta/Elev= 30
  3552.3  160.54  3758.5  158.13  4129.6   157.4  4201.7  154.19  4276.5  152.88
  4312.5   150.3  4387.3  148.37    4511  148.96  4634.7   145.1  4702.7  144.76
  4724.9  144.41  4771.2  140.72  4789.3  141.07  4902.7  138.35  4923.3  136.39
  4956.7  135.06  4957.7  134.56    4998  135.06  5027.1   137.8  5037.6   139.9
  5048.1  144.47  5107.7  144.67  5332.7  148.51  5459.2  147.42  5564.6  149.15
  5650.1  152.82  5680.6   155.8  5701.7  156.28  5743.8  160.77    5786  163.74
#Mann= 6 ,-1 , 0
  3552.3     .05       0  4702.7    .035       0  4956.7    .035       0
    4998    .035       0  5107.7     .05       0  5650.1    .035       0
Bank Sta=4956.7,4998
XS Rating Curve= 0 ,0
Exp/Cntr=0.3,0.1

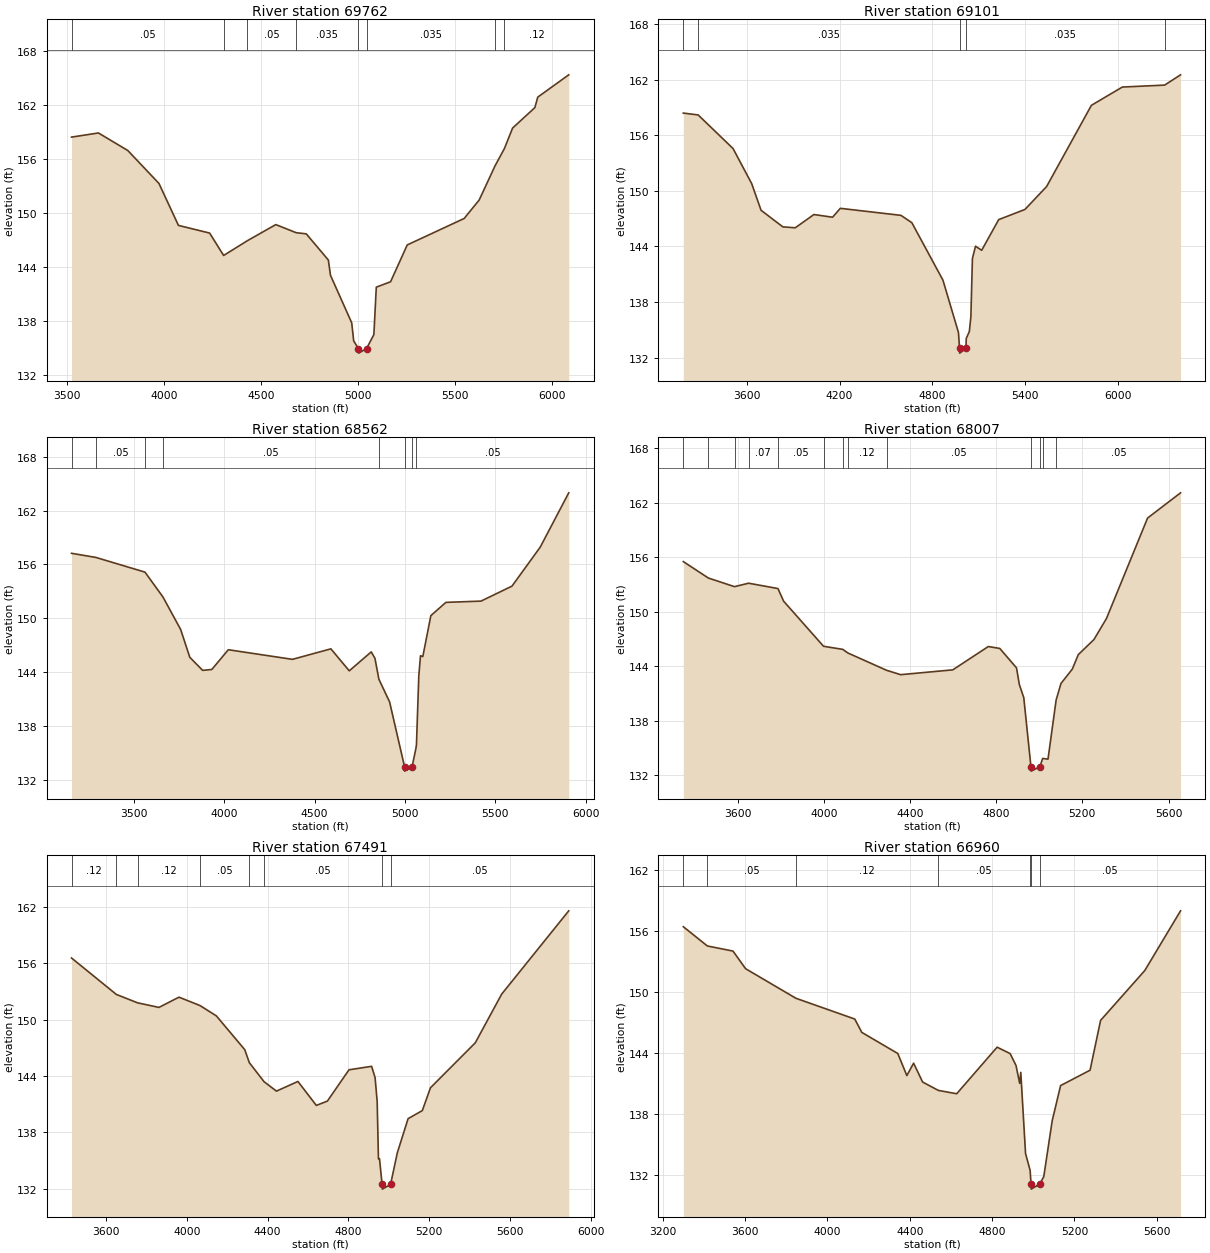
Type RM Length L Ch R = 1 ,69762   ,661,661,661
BEGIN DESCRIPTION:
Mapping XS ed129db4
END DESCRIPTION:
XS GIS Cut Line= 3
      2509312.02     13460334.12      2509187.02     13458854.99
      2508556.83     13457980.02
#Sta/Elev= 30
  3523.5   158.4  3662.2  158.86  3813.7  156.91  3974.2  153.25  4074.6  148.59
  4235.2  147.74  4307.5  145.25  4429.8  146.89  4576.4  148.68  4681.4  147.78
  4733.5  147.65  4847.3  144.74  4858.1  143.05  4967.6  137.77  4977.8  135.76
  5002.3   134.9  5003.3   134.4    5044   134.9  5081.8  136.46  5094.3  141.73
  5167.9  142.33  5253.8  146.42  5547.2  149.36  5624.5  151.41  5706.4  155.21
  5754.6  157.13  5796.6   159.4  5911.7  161.68  5926.4  162.84  6086.2  165.32
#Mann= 8 ,-1 , 0
  3523.5     .05       0  4307.5    .035       0  4429.8     .05       0
  4681.4    .035       0  5002.3    .035       0    5044    .035       0
  5706.4    .035       0  5754.6     .12       0
Bank Sta=5002.3,5044
XS Rating Curve= 0 ,0
Exp/Cntr=0.3,0.1

Type RM Length L Ch R = 1 ,69101   ,539,539,539
BEGIN DESCRIPTION:
PERDIDO CREEK 75.0
END DESCRIPTION:
XS GIS Cut Line= 3
        2509375.     13460224.99        2509575.       13458425.
      2509608.86     13457018.27
#Sta/Elev= 30
  3188.9   158.4  3284.9   158.2  3510.9  154.57  3631.6  150.78    3692  147.91
  3832.8  146.12  3913.3  146.02  4034.1  147.45  4154.8  147.16  4205.1  148.12
  4597.5  147.36  4667.9  146.57  4869.2  140.37  4969.8  134.71  4976.6  132.99
  4977.6  132.49  5018.3  132.99    5020  134.07    5040  134.82    5050  136.41
    5060  142.71    5080  144.03    5120  143.59    5230   146.9  5400.1     148
  5540.1  150.47  5830.2  159.24  6030.3  161.21  6304.1  161.42  6407.1  162.53
#Mann= 5 ,-1 , 0
  3188.9     .05       0  3284.9    .035       0  4976.6    .035       0
  5018.3    .035       0  6304.1     .07       0
Bank Sta=4976.6,5018.3
XS Rating Curve= 0 ,0
Exp/Cntr=0.3,0.1

Type RM Length L Ch R = 1 ,68562   ,555,555,555
BEGIN DESCRIPTION:
PERDIDO CREEK 74.0
END DESCRIPTION:
XS GIS Cut Line= 3
      2509726.73     13460190.39        2510025.       13458375.
      2510440.12     13457565.69
#Sta/Elev= 30
  3156.3  157.24  3290.8  156.78  3562.6  155.14  3662.1  152.36  3759.7  148.75
  3810.3  145.65  3881.3  144.19    3932  144.29  4023.2  146.49  4377.9  145.42
  4590.4  146.59    4692  144.14  4813.6  146.25  4833.9  145.54  4855.9   143.2
    4915  140.68  4997.6  133.46  4998.6  132.96  5039.5  133.46  5060.7  135.51
  5063.5   135.9  5076.5  143.58  5085.9  145.82  5098.7  145.73  5143.1  150.29
  5226.3  151.77  5420.4  151.91  5591.7  153.58  5747.7  157.92  5905.6  163.98
#Mann= 8 ,-1 , 0
  3156.3     .12       0  3290.8     .05       0  3562.6    .035       0
  3662.1     .05       0  4855.9    .035       0  4997.6    .035       0
  5039.5    .035       0  5060.7     .05       0
Bank Sta=4997.6,5039.5
XS Rating Curve= 0 ,0
Exp/Cntr=0.3,0.1

Type RM Length L Ch R = 1 ,68007   ,516,516,516
BEGIN DESCRIPTION:
PERDIDO CREEK 73.0
END DESCRIPTION:
XS GIS Cut Line= 3
      2510107.28      13460129.2       2510504.9     13458525.25
      2510570.49     13457872.64
#Sta/Elev= 30
  3347.5  155.53  3463.7  153.72  3585.1  152.77  3650.5  153.15  3786.9  152.56
  3813.1  151.17  3998.4   146.2  4087.6  145.86  4111.4  145.46  4291.4  143.55
  4356.3  143.07  4598.5   143.6  4763.3  146.17  4816.7  145.96  4894.3  143.82
  4907.5  141.98  4928.1  140.53  4961.3  132.94  4962.3  132.44  5003.2  132.94
  5015.7  133.84  5040.5  133.76  5078.3  140.28  5100.8   142.1  5153.5  143.69
  5181.2  145.28  5253.8  146.94  5311.8  149.25  5502.8  160.33  5655.9  163.11
#Mann= 13 ,-1 , 0
  3347.5     .05       0  3463.7     .07       0  3585.1     .05       0
  3650.5     .07       0  3786.9     .05       0  3998.4     .12       0
  4087.6     .05       0  4111.4     .12       0  4291.4     .05       0
  4961.3     .05       0  5003.2     .05       0  5015.7     .07       0
  5078.3     .05       0
Bank Sta=4961.3,5003.2
XS Rating Curve= 0 ,0
Exp/Cntr=0.3,0.1

Type RM Length L Ch R = 1 ,67491   ,531,531,531
BEGIN DESCRIPTION:
PERDIDO CREEK 72.0
END DESCRIPTION:
XS GIS Cut Line= 3
      2510544.43     13460091.48        2510975.       13458575.
      2510862.15     13457695.63
#Sta/Elev= 30
  3429.1  156.56  3651.2  152.68  3756.1  151.79    3862   151.3  3961.4  152.39
  4065.3   151.5  4146.5   150.4  4287.3   146.8  4309.9  145.42    4383  143.39
  4444.2  142.39  4550.6  143.42  4641.7  140.87  4696.6  141.33  4803.5  144.66
  4915.6  145.03  4932.8  143.83  4943.1   141.3  4949.5  135.18  4954.7   135.2
  4967.6  132.46  4968.6  131.96  5009.5  132.46  5042.8  135.82  5096.3  139.46
  5166.8  140.32  5207.2  142.75    5429  147.53    5560  152.72  5892.1  161.58
#Mann= 8 ,-1 , 0
  3429.1     .12       0  3651.2     .05       0  3756.1     .12       0
  4065.3     .05       0  4309.9     .12       0    4383     .05       0
  4967.6     .05       0  5009.5     .05       0
Bank Sta=4967.6,5009.5
XS Rating Curve= 0 ,0
Exp/Cntr=0.3,0.1

Type RM Length L Ch R = 1 ,66960   ,578,578,578
BEGIN DESCRIPTION:
PERDIDO CREEK 71.0
END DESCRIPTION:
XS GIS Cut Line= 3
      2510775.02     13460124.96        2511475.       13458575.
        2511325.     13457874.99
#Sta/Elev= 30
  3299.4  156.41  3416.2  154.52  3540.8  154.02  3602.1  152.29  3846.5  149.39
  4132.7  147.35  4166.8  146.04  4341.7  143.97  4385.8   141.8  4418.6  143.02
  4462.4  141.17  4538.5  140.35    4628  140.02  4824.5  144.59  4887.8  143.96
  4916.4  142.79  4934.1  141.04  4939.5  142.12  4962.7  134.15  4984.9   132.5
  4989.4  131.16  4990.4  130.66  5031.3  131.16  5051.2  131.88  5092.1  137.36
    5133  140.82  5276.2  142.33  5327.4  147.22  5542.1  152.11    5716  157.97
#Mann= 7 ,-1 , 0
  3299.4     .12       0  3416.2     .05       0  3846.5     .12       0
  4538.5     .05       0  4984.9    .035       0  4989.4    .035       0
  5031.3     .05       0
Bank Sta=4989.4,5031.3
XS Rating Curve= 0 ,0
Exp/Cntr=0.3,0.1

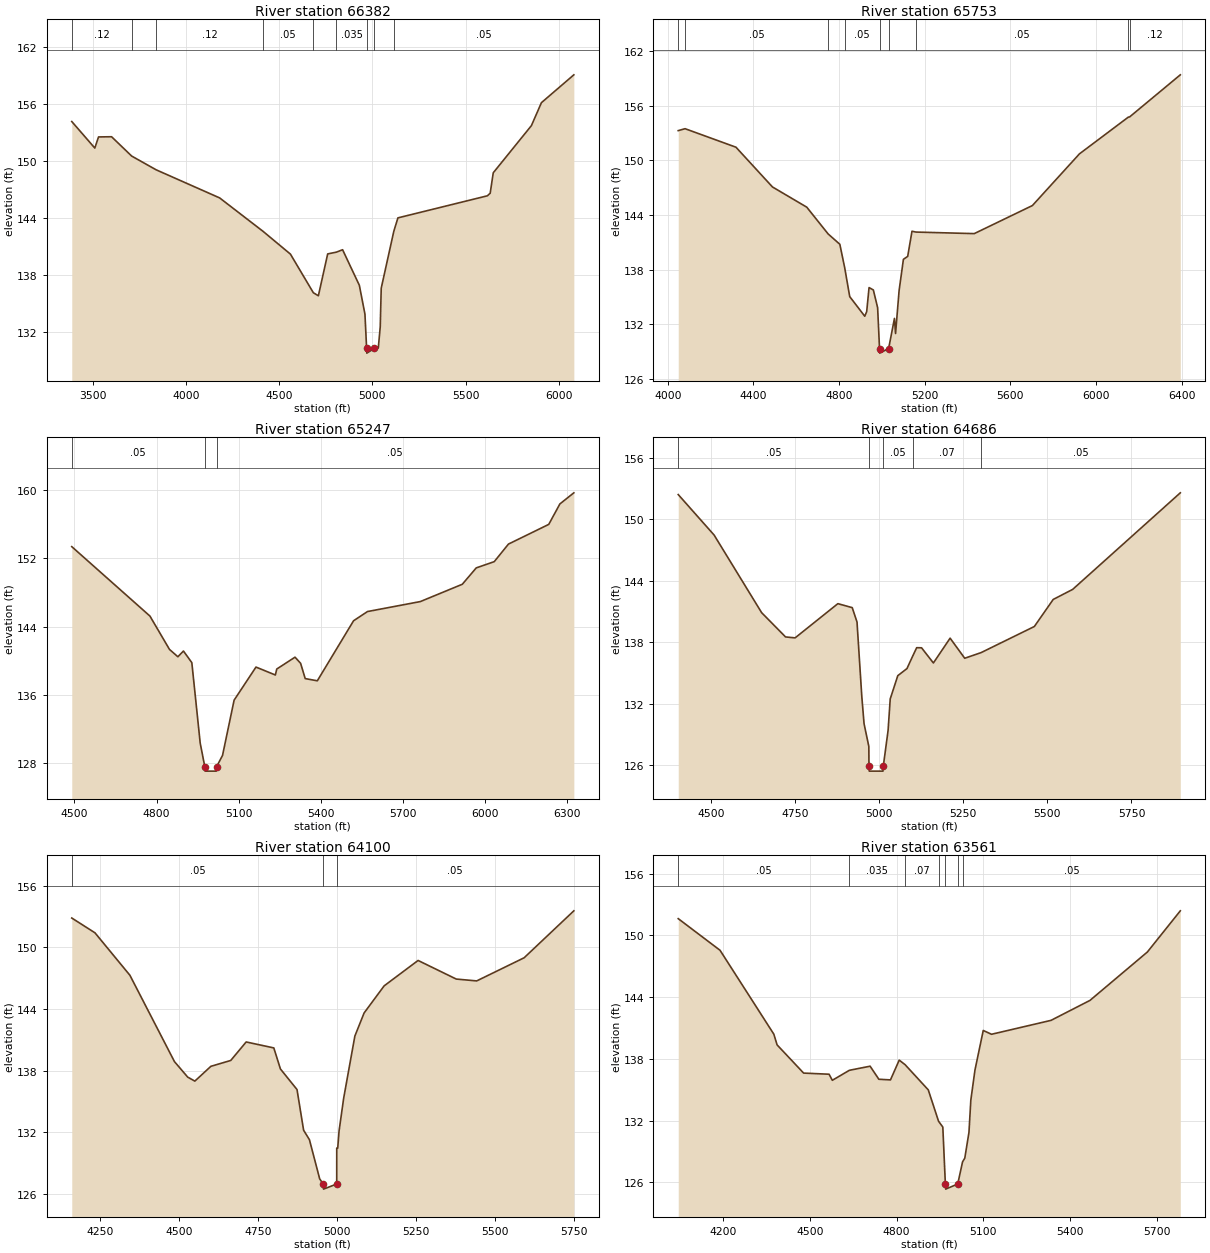
Type RM Length L Ch R = 1 ,66382   ,629,629,629
BEGIN DESCRIPTION:
PERDIDO CREEK 70.0
END DESCRIPTION:
XS GIS Cut Line= 3
      2512032.29     13460188.66        2512025.       13458575.
      2511683.64     13457548.97
#Sta/Elev= 30
  3386.3  154.17    3510  151.38    3530  152.55    3600  152.57  3707.8  150.54
  3839.6  149.09    4180  146.14  4412.7  142.63    4560  140.23    4683  136.17
    4710  135.85    4760  140.25  4807.2  140.44    4840  140.69    4930  136.95
    4960  133.92    4969  130.32    4970  129.82  5010.9  130.32  5031.6  130.35
  5042.1  132.59  5047.4  136.65  5114.8  142.62    5137  144.04  5617.1  146.36
  5632.3  146.63  5648.7  148.78  5853.6  153.74  5907.2  156.15  6081.3  159.08
#Mann= 9 ,-1 , 0
  3386.3     .12       0  3707.8     .07       0  3839.6     .12       0
  4412.7     .05       0    4683     .07       0  4807.2    .035       0
    4969    .035       0  5010.9    .035       0  5114.8     .05       0
Bank Sta=4969,5010.9
XS Rating Curve= 0 ,0
Exp/Cntr=0.3,0.1

Type RM Length L Ch R = 1 ,65753   ,506,506,506
BEGIN DESCRIPTION:
PERDIDO CREEK 69.0
END DESCRIPTION:
XS GIS Cut Line= 3
      2512667.71     13459693.88      2512594.89     13458745.28
      2512485.41     13457355.28
#Sta/Elev= 30
  4048.6  153.25  4080.6  153.46  4318.3  151.43  4488.8  147.07  4649.2  144.85
  4748.7  141.92  4803.6  140.78  4826.3  138.21  4849.8  135.04    4920  132.89
  4929.1  133.39  4940.1  136.03  4960.2  135.77  4980.2  133.82    4989  129.34
    4990  128.84  5031.6  129.34  5058.8  132.65  5063.9  130.99  5080.5   135.7
  5100.6  139.13  5120.6  139.45  5140.7  142.21  5159.6  142.12  5431.6  141.95
  5703.3  145.03  5923.1   150.7  6151.5  154.73  6157.4  154.75  6394.3  159.37
#Mann= 9 ,-1 , 0
  4048.6     .12       0  4080.6     .05       0  4748.7     .07       0
  4826.3     .05       0    4989     .05       0  5031.6     .05       0
  5159.6     .05       0  6151.5     .07       0  6157.4     .12       0
Bank Sta=4989,5031.6
XS Rating Curve= 0 ,0
Exp/Cntr=0.3,0.1

Type RM Length L Ch R = 1 ,65247   ,561,561,561
BEGIN DESCRIPTION:
PERDIDO CREEK 68.0
END DESCRIPTION:
XS GIS Cut Line= 3
        2512975.     13459224.99        2513075.       13458725.
        2512825.     13457425.01
#Sta/Elev= 30
  4490.1  153.37  4775.6  145.23    4847  141.32  4877.6  140.46    4898  141.13
  4928.6  139.77  4959.2  130.33  4976.1  127.55  4977.1  127.05  5017.7  127.05
  5018.7  127.55  5040.7  128.89    5083  135.37  5162.9  139.25  5233.7  138.32
  5238.8  139.02  5305.5  140.41  5325.9  139.69  5342.7   137.9  5386.9  137.64
  5519.3  144.68  5570.2  145.76  5763.2  146.93  5916.5  148.96  5967.4  150.88
  6033.1  151.61    6085  153.67  6232.2  155.98  6272.9  158.38  6323.8  159.68
#Mann= 3 ,-1 , 0
  4490.1     .05       0  4976.1     .05       0  5018.7     .05       0
Bank Sta=4976.1,5018.7
XS Rating Curve= 0 ,0
Exp/Cntr=0.3,0.1

Type RM Length L Ch R = 1 ,64686   ,586,586,586
BEGIN DESCRIPTION:
PERDIDO CREEK 67.0
END DESCRIPTION:
XS GIS Cut Line= 3
      2513874.99     13458824.99        2513475.       13458375.
      2512924.99     13457674.99
#Sta/Elev= 30
  4402.9  152.43  4509.5  148.48  4650.8   140.9  4721.9  138.53  4750.3  138.44
  4877.4  141.78  4920.1  141.39  4934.3  139.98  4948.5  132.72  4955.2  130.06
  4969.4  127.84  4969.8  125.93  4970.8  125.43  5011.5  125.43  5012.5  125.93
  5026.6  129.39    5033  132.48  5055.5  134.75  5082.7  135.44  5099.4  136.63
  5111.6  137.48  5126.1  137.47  5161.3  135.99    5211  138.41  5254.4  136.45
  5303.1     137  5461.4  139.55  5517.4  142.19  5575.2  143.17  5895.2   152.6
#Mann= 5 ,-1 , 0
  4402.9     .05       0  4969.8     .05       0  5012.5     .05       0
  5099.4     .07       0  5303.1     .05       0
Bank Sta=4969.8,5012.5
XS Rating Curve= 0 ,0
Exp/Cntr=0.3,0.1

Type RM Length L Ch R = 1 ,64100   ,539,539,539
BEGIN DESCRIPTION:
PERDIDO CREEK 66.0
END DESCRIPTION:
XS GIS Cut Line= 3
      2514075.01     13458725.04        2513825.       13457925.
        2513375.       13457325.
#Sta/Elev= 30
  4161.3  152.84  4234.7   151.4  4345.2  147.27  4486.1  138.87    4528  137.36
  4550.6  136.97  4601.4  138.41  4664.2  138.98    4713  140.78  4800.4   140.2
  4821.4  138.15  4873.8  136.15  4894.7  132.19  4913.1  131.27  4945.5  127.46
  4956.7  126.96  4957.7  126.46  4999.4  126.96  4999.5  130.45  5002.6  130.45
  5006.8  132.11  5021.4  135.31  5056.8  141.35    5086   143.6  5149.5  146.24
  5256.8  148.71  5377.6   146.9  5442.2  146.72  5592.2  148.97  5749.5  153.54
#Mann= 3 ,-1 , 0
  4161.3     .05       0  4956.7     .05       0  4999.4     .05       0
Bank Sta=4956.7,4999.4
XS Rating Curve= 0 ,0
Exp/Cntr=0.3,0.1

Type RM Length L Ch R = 1 ,63561   ,538,538,538
BEGIN DESCRIPTION:
PERDIDO CREEK 65.0
END DESCRIPTION:
XS GIS Cut Line= 3
        2514175.     13458624.99        2514275.       13457675.
      2513674.97     13457174.98
#Sta/Elev= 30
  4045.1  151.62  4189.6  148.55  4375.7   140.4    4387  139.36  4478.7  136.62
  4566.7  136.51    4578  135.92  4636.9  136.89  4708.7  137.29  4738.9  136.02
  4779.1  135.96  4809.3  137.88  4829.9  137.43  4909.8  134.99  4945.4  131.94
  4960.1  131.38  4968.9  125.85  4969.9  125.35  5011.7  125.85  5028.4     128
  5036.1  128.36  5050.5  130.86    5057     134  5071.3  136.92  5099.9  140.76
  5128.6  140.39  5334.2  141.74    5469  143.68  5667.5  148.38  5781.4  152.38
#Mann= 7 ,-1 , 0
  4045.1     .05       0  4636.9    .035       0  4829.9     .07       0
  4945.4     .05       0  4968.9     .05       0  5011.7     .05       0
  5028.4     .05       0
Bank Sta=4968.9,5011.7
XS Rating Curve= 0 ,0
Exp/Cntr=0.3,0.1

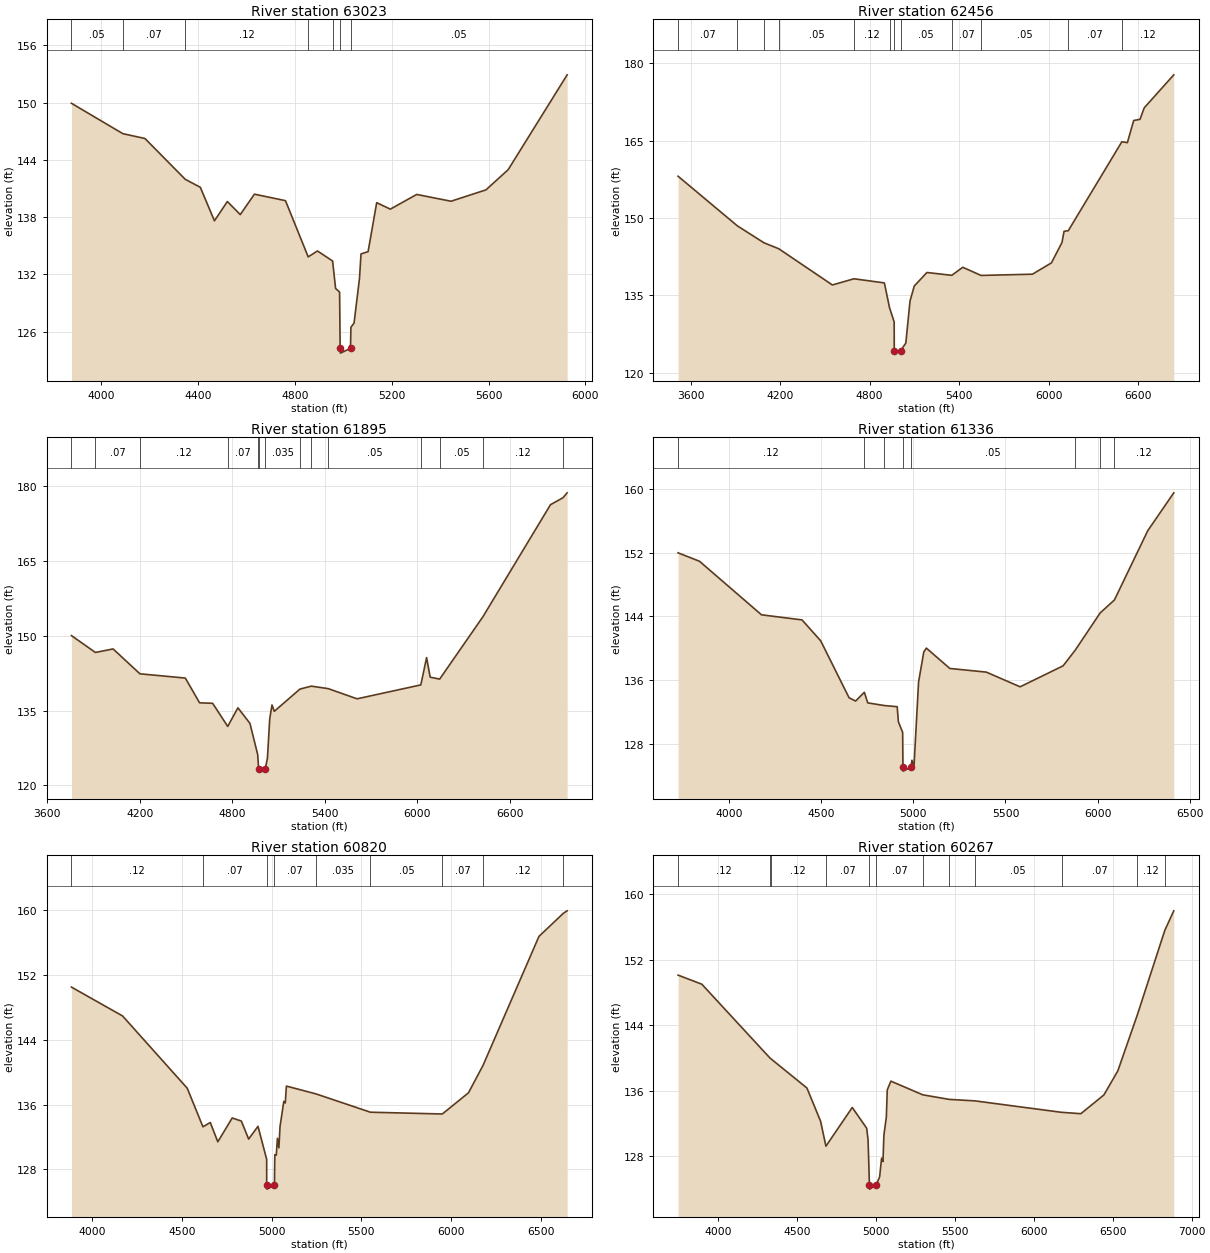
Type RM Length L Ch R = 1 ,63023   ,567,567,567
BEGIN DESCRIPTION:
PERDIDO CREEK 64.0
END DESCRIPTION:
XS GIS Cut Line= 3
        2514925.     13458525.02        2514725.       13457425.
      2513975.01     13456875.01
#Sta/Elev= 30
  3876.7  149.92  4088.8  146.74  4180.4  146.23  4346.7  141.96  4409.1  141.12
  4467.5  137.61  4520.9  139.63  4574.2  138.26  4632.7   140.4    4761  139.72
  4854.9  133.83  4893.1  134.45  4955.7   133.4  4968.1  130.53  4984.6  130.14
  4986.9  124.25  4987.9  123.75  5029.7  124.25  5031.4  126.46  5044.4   126.9
  5066.9   131.6  5073.1  134.14  5102.4  134.38  5137.9  139.51  5194.3  138.83
  5303.1  140.37  5445.1  139.66  5589.4  140.85  5681.3  142.97  5924.8   152.9
#Mann= 7 ,-1 , 0
  3876.7     .05       0  4088.8     .07       0  4346.7     .12       0
  4854.9     .07       0  4955.7     .05       0  4986.9     .05       0
  5029.7     .05       0
Bank Sta=4986.9,5029.7
XS Rating Curve= 0 ,0
Exp/Cntr=0.3,0.1

Type RM Length L Ch R = 1 ,62456   ,561,561,561
BEGIN DESCRIPTION:
PERDIDO CREEK 63.0
END DESCRIPTION:
XS GIS Cut Line= 3
      2515974.98     13458374.97        2515175.       13457125.
      2513875.01     13455825.01
#Sta/Elev= 30
    3516  158.09  3913.1  148.47  4091.9  145.18  4191.1  144.02  4550.2     137
  4694.9   138.2  4898.6   137.4  4933.4  132.59  4964.4  129.82    4965  124.28
    4966  123.78    5008  124.28  5042.5  125.73  5070.8  133.92    5099  136.79
  5183.9  139.42  5350.5  138.87  5424.3  140.43  5546.5  138.85    5891  139.09
  6018.3  141.28    6089  145.23  6103.1  147.41  6131.3  147.52  6490.3  164.77
  6527.4  164.61  6569.8   168.9  6612.2  169.13  6640.5  171.36  6838.5  177.76
#Mann= 12 ,-1 , 0
    3516     .07       0  3913.1     .05       0  4091.9     .07       0
  4191.1     .05       0  4694.9     .12       0  4933.4     .05       0
    4965     .05       0    5008     .05       0  5350.5     .07       0
  5546.5     .05       0  6131.3     .07       0  6490.3     .12       0
Bank Sta=4965,5008
XS Rating Curve= 0 ,0
Exp/Cntr=0.3,0.1

Type RM Length L Ch R = 1 ,61895   ,559,559,559
BEGIN DESCRIPTION:
PERDIDO CREEK 62.0
END DESCRIPTION:
XS GIS Cut Line= 3
        2516525.       13457575.        2515575.       13456775.
      2513974.99     13455624.99
#Sta/Elev= 30
  3757.8  150.03  3913.1  146.65  4027.6  147.36  4201.7  142.37  4495.8  141.52
  4588.2  136.56  4672.9  136.46  4770.5  131.83  4836.6  135.56  4914.6  132.44
  4964.6  126.21  4971.1  123.37  4972.1  122.87  5014.1  123.37    5028  125.48
  5042.7  133.32  5057.5  136.13  5072.2  134.85  5238.5  139.31  5312.6   139.9
  5421.9   139.4  5608.7  137.36    6022  140.15  6059.3  145.62  6082.6   141.7
    6144  141.31  6424.8  153.83  6862.2  176.26  6942.8  177.65  6970.2  178.64
#Mann= 14 ,-1 , 0
  3757.8     .12       0  3913.1     .07       0  4201.7     .12       0
  4770.5     .07       0  4964.6    .035       0  4971.1    .035       0
  5014.1    .035       0  5238.5     .05       0  5312.6    .035       0
  5421.9     .05       0    6022     .07       0    6144     .05       0
  6424.8     .12       0  6942.8     .07       0
Bank Sta=4971.1,5014.1
XS Rating Curve= 0 ,0
Exp/Cntr=0.3,0.1

Type RM Length L Ch R = 1 ,61336   ,516,516,516
BEGIN DESCRIPTION:
PERDIDO CREEK 61.0
END DESCRIPTION:
XS GIS Cut Line= 3
      2516675.01     13457575.02        2516025.       13456475.
      2515025.02     13455475.02
#Sta/Elev= 30
  3722.3  152.01  3838.5  150.95  4175.3  144.21  4395.3  143.57  4496.8  140.94
  4650.9  133.77  4686.4  133.36  4733.8  134.46  4752.3  133.13    4843  132.79
  4912.2  132.65  4918.7  130.75  4941.9  129.41  4943.4  125.04  4944.4  124.54
  4986.5  125.04  4992.2  125.91  5003.5  125.17  5028.3  135.76  5056.6  139.54
  5070.7  140.02    5198  137.46    5396     137  5579.8  135.15  5813.2  137.79
  5879.3  139.77  6014.5  144.45    6092  146.08  6272.8  154.79  6414.2  159.56
#Mann= 8 ,-1 , 0
  3722.3     .12       0  4733.8     .07       0    4843     .05       0
  4943.4     .05       0  4986.5     .05       0  5879.3     .12       0
  6014.5     .07       0    6092     .12       0
Bank Sta=4943.4,4986.5
XS Rating Curve= 0 ,0
Exp/Cntr=0.3,0.1

Type RM Length L Ch R = 1 ,60820   ,553,553,553
BEGIN DESCRIPTION:
PERDIDO CREEK 60.0
END DESCRIPTION:
XS GIS Cut Line= 3
      2516675.01     13457375.03        2516475.       13456275.
      2515174.99     13455274.99
#Sta/Elev= 30
  3886.6  150.47  4171.2  146.91  4530.8  138.01  4618.3  133.25  4659.1  133.78
    4701   131.4  4781.1  134.34  4831.9  133.96  4872.5  131.74  4924.6  133.31
  4972.9  129.24    4973  126.07    4974  125.57  5016.1  126.07  5018.2  129.82
  5026.4  129.76  5032.7  131.83  5040.9  130.66  5047.2  133.28  5068.1  136.38
  5076.3  136.19  5082.6  138.27  5248.3   137.3  5550.1  135.05  5950.2  134.83
  6095.7  137.44  6176.8  140.82    6488  156.72  6623.9  159.57  6644.8  159.87
#Mann= 9 ,-1 , 0
  3886.6     .12       0  4618.3     .07       0    4973     .05       0
  5016.1     .07       0  5248.3    .035       0  5550.1     .05       0
  5950.2     .07       0  6176.8     .12       0  6623.9    .035       0
Bank Sta=4973,5016.1
XS Rating Curve= 0 ,0
Exp/Cntr=0.3,0.1

Type RM Length L Ch R = 1 ,60267   ,311,311,311
BEGIN DESCRIPTION:
PERDIDO CREEK 59.0
END DESCRIPTION:
XS GIS Cut Line= 3
        2516875.     13457375.02        2516975.       13456125.
      2515375.01     13455125.01
#Sta/Elev= 30
    3746  150.11  3896.5     149  4328.6  139.97  4332.5  139.91  4562.4  136.31
  4648.9  132.25  4682.8   129.2  4849.5  133.93  4941.1  131.39  4949.9  129.94
  4958.4  124.45  4959.4  123.95  5001.5  124.45    5023  125.45  5035.4  127.73
  5044.2  127.32  5050.1  130.55  5065.5  132.74  5071.4  136.08  5094.4  137.15
  5296.1  135.48  5463.6  134.92  5626.1  134.74  6175.5  133.34  6297.8  133.17
    6444  135.46  6532.4  138.41    6655   145.2  6830.3   155.6  6886.8  157.97
#Mann= 12 ,-1 , 0
    3746     .12       0  4328.6     .07       0  4332.5     .12       0
  4682.8     .07       0  4958.4     .05       0  5001.5     .07       0
  5296.1     .05       0  5463.6    .035       0  5626.1     .05       0
  6175.5     .07       0    6655     .12       0  6830.3     .07       0
Bank Sta=4958.4,5001.5
XS Rating Curve= 0 ,0
Exp/Cntr=0.3,0.1