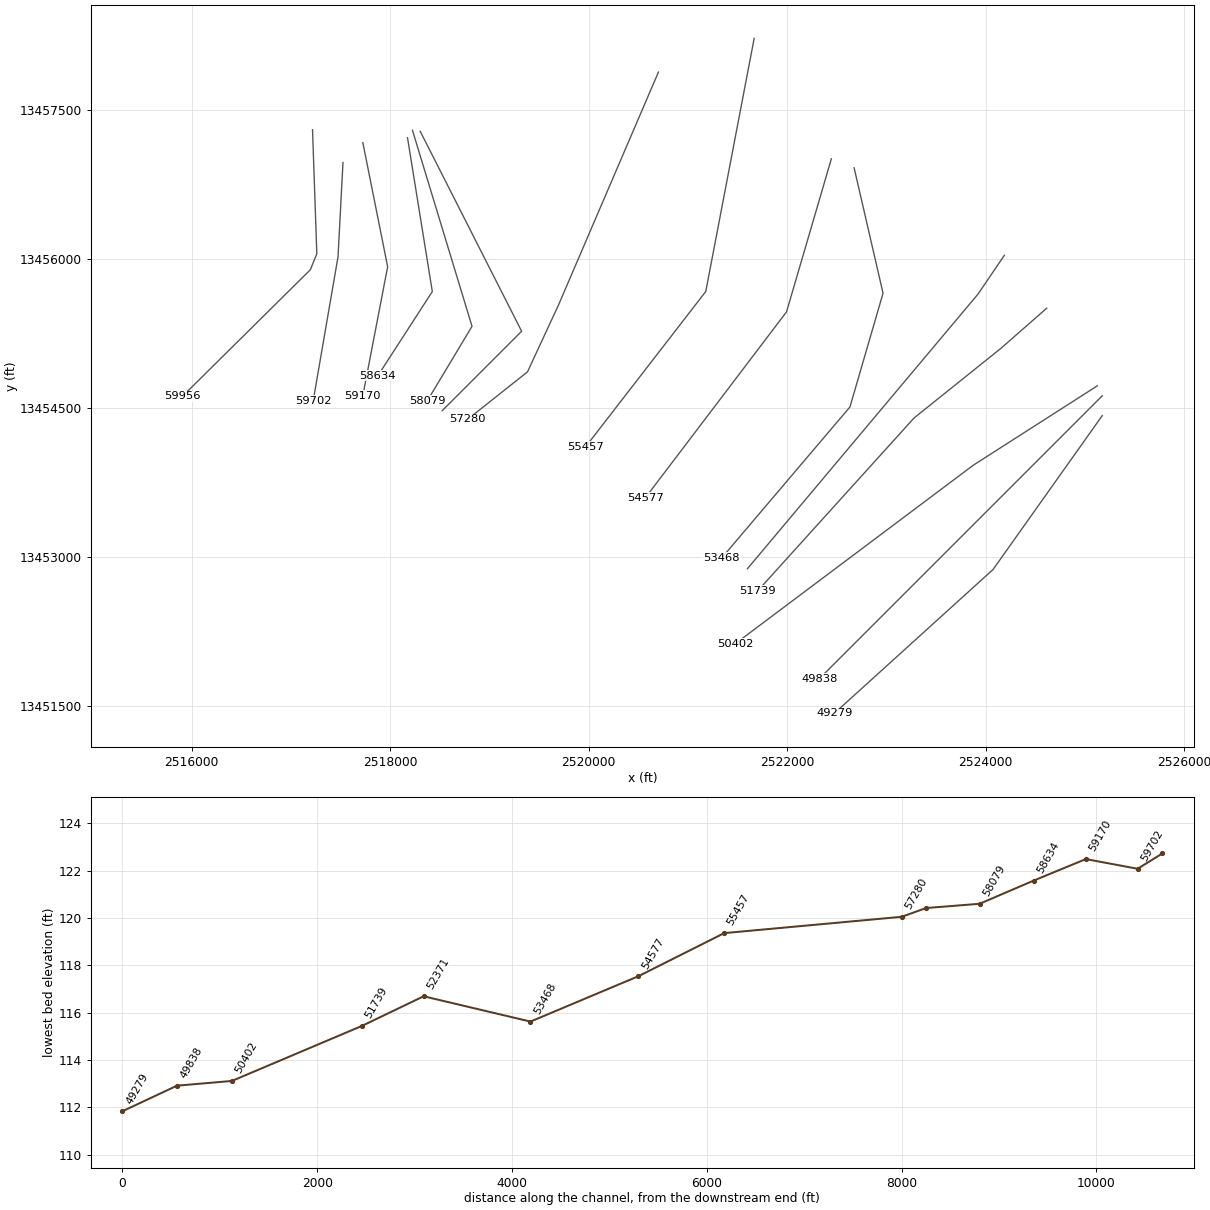
HEC-RAS study PERDIDO CREEK.prj: PERDIDO CREEK Base Level Engineering

--- PERDIDO CREEK.g01 (geometry) --- (continued)

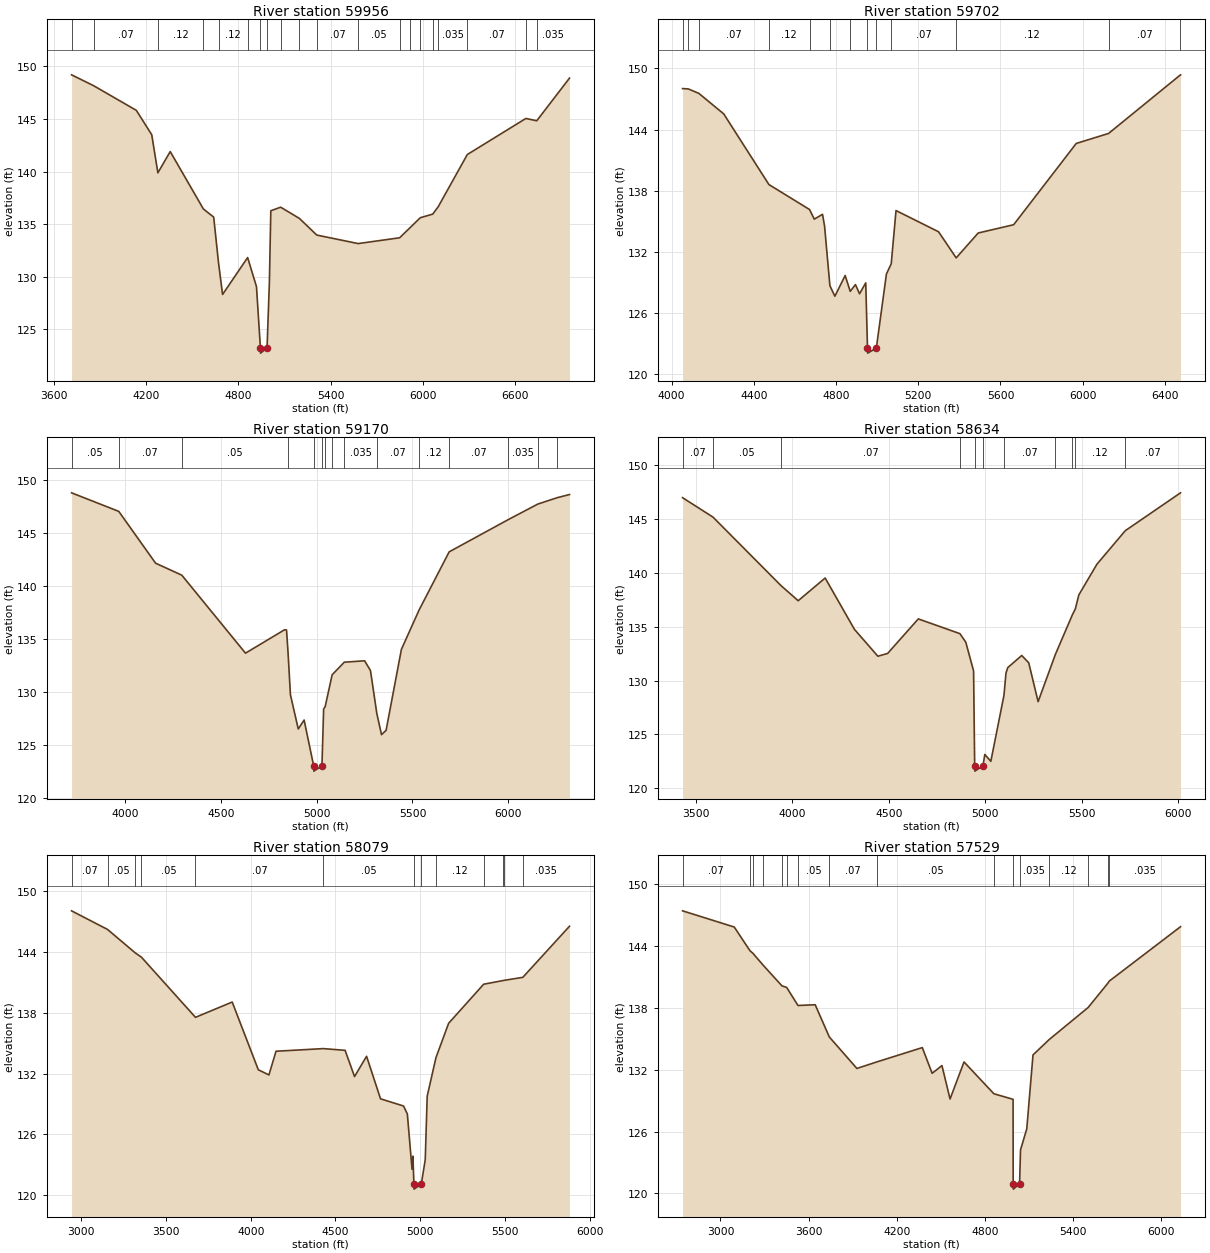
Type RM Length L Ch R = 1 ,59956   ,254,254,254
BEGIN DESCRIPTION:
Mapping XS 72b854d5
END DESCRIPTION:
XS GIS Cut Line= 4
      2517218.06     13457305.64      2517261.46     13456055.62
      2517196.36     13455895.03      2515909.13     13454620.81
#Sta/Elev= 30
  3715.9   149.2  3858.7  148.17  4136.8  145.82  4236.9   143.5  4276.7  139.88
  4356.9   141.9  4572.4  136.44  4639.3  135.67    4671  131.29  4697.1  128.31
  4859.8  131.82  4917.3  129.06  4942.9  123.23  4943.9  122.73    4986  123.23
  5001.1   129.4  5010.5  136.27  5074.5  136.61  5196.5  135.54    5309  133.96
  5578.1  133.15  5847.2   133.7    5918   134.7  5981.7  135.61  6062.4  135.95
  6099.2  136.68  6287.2  141.62  6667.6  145.05  6738.3  144.83  6951.2  148.89
#Mann= 20 ,-1 , 0
  3715.9     .12       0  3858.7     .07       0  4276.7     .12       0
  4572.4     .07       0    4671     .12       0  4859.8     .07       0
  4942.9     .05       0    4986     .07       0  5074.5     .12       0
  5196.5     .12       0    5309     .07       0  5578.1     .05       0
  5847.2    .035       0    5918     .07       0  5981.7     .05       0
  6062.4     .07       0  6099.2    .035       0  6287.2     .07       0
  6667.6     .12       0  6738.3    .035       0
Bank Sta=4942.9,4986
XS Rating Curve= 0 ,0
Exp/Cntr=0.3,0.1

Type RM Length L Ch R = 1 ,59702   ,532,532,532
BEGIN DESCRIPTION:
PERDIDO CREEK 58.0
END DESCRIPTION:
XS GIS Cut Line= 3
        2517525.     13456975.04        2517475.       13456025.
      2517224.99     13454574.95
#Sta/Elev= 30
  4053.3  148.02    4081  147.99  4132.6  147.55  4253.6  145.54  4473.5  138.61
  4671.3  136.16  4694.2  135.22  4734.3  135.69  4744.3  134.53  4770.2  128.69
  4794.4  127.66  4844.4  129.69  4869.1  128.14  4894.5   128.8  4914.5   127.9
  4944.6  128.97  4953.1  122.58  4954.1  122.08  4996.2  122.58  5045.2  129.84
  5068.6  130.84  5091.9  136.06  5298.9  133.98  5384.6  131.42  5491.7  133.86
  5664.2  134.67  5968.7  142.64  6125.9  143.62    6476  149.37  6476.1  149.37
#Mann= 13 ,-1 , 0
  4053.3     .07       0    4081     .05       0  4132.6     .07       0
  4473.5     .12       0  4671.3     .07       0  4770.2     .12       0
  4869.1      .1       0  4953.1     .05       0  4996.2      .1       0
  5068.6     .07       0  5384.6     .12       0  6125.9     .07       0
    6476     .05       0
Bank Sta=4953.1,4996.2
XS Rating Curve= 0 ,0
Exp/Cntr=0.3,0.1

Type RM Length L Ch R = 1 ,59170   ,536,536,536
BEGIN DESCRIPTION:
PERDIDO CREEK 57.0
END DESCRIPTION:
XS GIS Cut Line= 3
      2517724.99     13457175.04        2517975.       13455925.
        2517725.     13454625.01
#Sta/Elev= 30
    3721  148.75  3967.3     147  4159.6  142.11  4296.3  140.98  4628.7  133.62
  4832.6  135.83  4842.8  135.81  4850.9  133.63  4863.2  129.69    4904  126.47
  4934.6  127.31  4984.4  122.99  4985.4  122.49  5027.6  122.99  5036.5  128.36
  5044.5  128.57  5080.8  131.58  5144.5  132.77  5250.4   132.9  5280.9  131.98
    5314  127.93  5338.5  125.93  5362.4  126.34  5442.3  133.98  5534.8   137.7
  5691.5  143.18  6000.7  146.23  6154.3  147.69  6255.3  148.29  6319.6  148.59
#Mann= 15 ,-1 , 0
    3721     .05       0  3967.3     .07       0  4296.3     .05       0
  4850.9     .07       0  4984.4     .05       0  5027.6     .07       0
  5044.5    .035       0  5080.8     .12       0  5144.5    .035       0
    5314     .07       0  5534.8     .12       0  5691.5     .07       0
  6000.7    .035       0  6154.3     .07       0  6255.3     .05       0
Bank Sta=4984.4,5027.6
XS Rating Curve= 0 ,0
Exp/Cntr=0.3,0.1

Type RM Length L Ch R = 1 ,58634   ,555,555,555
BEGIN DESCRIPTION:
PERDIDO CREEK 56.0
END DESCRIPTION:
XS GIS Cut Line= 3
      2518174.99     13457225.04        2518425.       13455675.
        2517875.     13454824.99
#Sta/Elev= 30
  3430.7     147  3588.7  145.19  3941.6  138.82  4030.4  137.42  4170.2  139.53
  4322.1  134.76  4443.7  132.26  4494.3  132.52  4653.3  135.73  4869.1  134.36
  4899.5  133.57    4940   130.9  4945.7  122.08  4946.7  121.58  4988.9  122.08
  4998.2  123.13  5029.5  122.49  5097.6  128.63    5108  130.68  5117.2   131.2
  5189.7  132.33    5226  131.65  5274.7  128.04  5364.7  132.45  5452.4  136.11
  5467.9  136.67  5485.9  137.96  5579.5  140.81  5726.7  143.93  6013.2  147.45
#Mann= 11 ,-1 , 0
  3430.7     .07       0  3588.7     .05       0  3941.6     .07       0
  4869.1     .05       0  4945.7    .035       0  4988.9     .05       0
  5097.6     .07       0  5364.7     .12       0  5452.4     .07       0
  5467.9     .12       0  5726.7     .07       0
Bank Sta=4945.7,4988.9
XS Rating Curve= 0 ,0
Exp/Cntr=0.3,0.1

Type RM Length L Ch R = 1 ,58079   ,550,550,550
BEGIN DESCRIPTION:
PERDIDO CREEK 55.0
END DESCRIPTION:
XS GIS Cut Line= 3
       2518225.2     13457299.24        2518825.       13455325.
      2518374.99     13454574.99
#Sta/Elev= 30
  2942.8  148.09  3155.1  146.25  3318.2  143.94  3355.2  143.51  3673.9  137.57
  3890.6  139.08  4044.6  132.39  4107.3  131.88  4149.1  134.22  4428.4  134.48
  4556.7  134.31  4612.4  131.72  4683.4  133.72  4765.8  129.52  4901.6  128.81
    4924  128.02  4951.6  122.57  4956.8  123.86  4962.7   121.1  4963.7   120.6
  5006.3   121.1  5029.5   123.5  5041.1  129.78  5092.8  133.59  5167.5  136.98
  5374.2  140.84  5491.2  141.21  5493.8  141.22  5605.3  141.52  5880.8  146.57
#Mann= 13 ,-1 , 0
  2942.8     .07       0  3155.1     .05       0  3318.2    .035       0
  3355.2     .05       0  3673.9     .07       0  4428.4     .05       0
  4962.7     .05       0  5006.3     .05       0  5092.8     .12       0
  5374.2     .07       0  5491.2    .035       0  5493.8     .12       0
  5605.3    .035       0
Bank Sta=4962.7,5006.3
XS Rating Curve= 0 ,0
Exp/Cntr=0.3,0.1

Type RM Length L Ch R = 1 ,57529   ,249,249,249
BEGIN DESCRIPTION:
PERDIDO CREEK 54.0
END DESCRIPTION:
XS GIS Cut Line= 3
      2518303.34     13457288.79        2519325.       13455275.
        2518525.       13454475.
#Sta/Elev= 30
  2741.9  147.38  3093.8  145.81  3200.5  143.52  3220.6  143.27  3292.6  142.08
  3418.6  140.11  3450.6  139.96  3527.6  138.21  3644.8  138.28  3740.9  135.16
  3928.6  132.11  4065.7  132.75  4373.9  134.13  4440.7  131.64  4507.5  132.39
  4562.7  129.15  4657.7  132.74  4860.9  129.66  4991.7  129.12  4992.4  120.92
  4993.4  120.42    5036  120.92  5042.4  124.22  5084.9  126.26  5127.3  133.42
  5237.4  134.91    5503  138.02  5640.4  140.43  5645.3  140.56  6131.4  145.84
#Mann= 16 ,-1 , 0
  2741.9     .07       0  3200.5    .035       0  3220.6     .07       0
  3292.6    .035       0  3418.6     .05       0  3450.6     .07       0
  3527.6     .05       0  3740.9     .07       0  4065.7     .05       0
  4860.9    .035       0  4992.4    .035       0    5036    .035       0
  5237.4     .12       0    5503    .035       0  5640.4     .07       0
  5645.3    .035       0
Bank Sta=4992.4,5036
XS Rating Curve= 0 ,0
Exp/Cntr=0.3,0.1

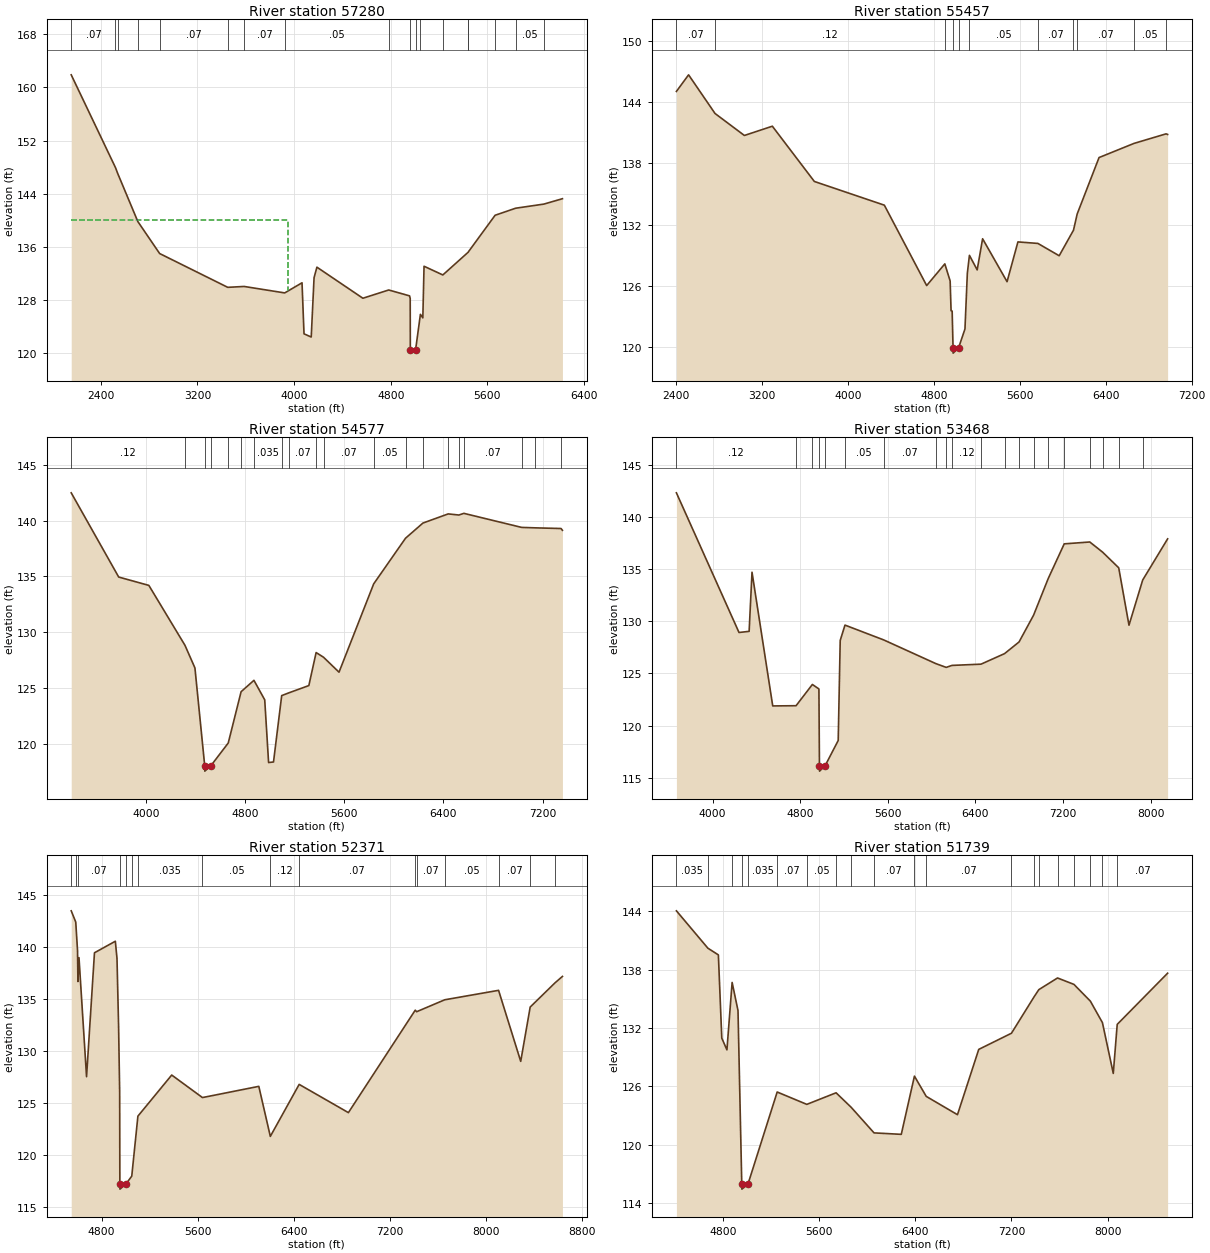
Type RM Length L Ch R = 1 ,57280   ,1823,1823,1823
BEGIN DESCRIPTION:
Mapping XS 45100a20
END DESCRIPTION:
XS GIS Cut Line= 4
      2520703.45     13457886.54      2519696.53     13455539.35
      2519384.03     13454865.74      2518779.96     13454386.66
#Sta/Elev= 30
  2154.5  161.88  2521.1  147.93  2539.3  147.06  2705.7  139.84  2886.6  135.02
  3450.5  129.94  3586.7  130.07  3922.3   129.1  4065.7  130.62  4082.2  122.95
  4141.9  122.47  4165.4  131.39    4189  132.97  4569.7   128.3  4783.5  129.54
  4955.9  128.66  4961.5  128.27  4962.6  120.55  4963.6  120.05  5006.2  120.55
    5046  125.88  5066.1  125.35  5076.1  133.11  5231.8   131.8  5442.5  135.23
  5443.6  135.28  5664.5  140.77  5834.5  141.83  6068.4  142.45  6222.1  143.26
#Mann= 18 ,-1 , 0
  2154.5     .07       0  2521.1    .035       0  2539.3     .07       0
  2705.7     .12       0  2886.6     .07       0  3450.5     .05       0
  3586.7     .07       0  3922.3     .05       0  4783.5    .033       0
  4962.6    .033       0  5006.2    .033       0    5046     .07       0
  5231.8     .12       0  5442.5    .035       0  5443.6     .12       0
  5664.5    .035       0  5834.5     .05       0  6068.4    .035       0
#XS Ineff= 2 , 0
       0    3950     140               0
Permanent Ineff=
       F       F
Bank Sta=4962.6,5006.2
XS Rating Curve= 0 ,0
Exp/Cntr=0.3,0.1

Type RM Length L Ch R = 1 ,55457   ,880,880,880
BEGIN DESCRIPTION:
PERDIDO CREEK 53.0
END DESCRIPTION:
XS GIS Cut Line= 3
      2521667.92     13458226.26      2521180.16     13455675.38
      2519971.24     13454112.85
#Sta/Elev= 30
  2402.9  145.08  2516.2  146.71  2762.5  142.91  3035.6  140.75    3296  141.66
    3687  136.23  4338.6   133.9  4732.6     126  4901.5  128.13  4951.1  126.45
  4959.7  123.53  4969.8  123.49  4978.2  119.86  4979.2  119.36  5028.9  119.86
    5089  121.73  5111.3  127.22  5130.6  128.97  5202.8  127.54  5253.3   130.6
  5480.9  126.38  5582.1  130.29    5768  130.14  5966.1  128.93  6099.3  131.44
  6133.6  133.03  6337.3  138.58  6662.5  139.97  6961.2  140.91  6975.6  140.85
#Mann= 11 ,-1 , 0
  2402.9     .07       0  2762.5     .12       0  4901.5    .033       0
  4978.2    .033       0  5028.9    .033       0  5130.6     .05       0
    5768     .07       0  6099.3     .12       0  6133.6     .07       0
  6662.5     .05       0  6961.2    .035       0
Bank Sta=4978.2,5028.9
XS Rating Curve= 0 ,0
Exp/Cntr=0.3,0.1

Type RM Length L Ch R = 1 ,54577   ,1109,1109,1109
BEGIN DESCRIPTION:
Mapping XS ec5efec4
END DESCRIPTION:
XS GIS Cut Line= 3
      2522445.44     13457012.33      2521994.06     13455470.69
      2520570.43     13453595.66
#Sta/Elev= 30
  3398.5  142.49  3781.2  134.94  4024.5  134.19  4315.6  128.82    4396  126.79
  4474.7  118.04  4475.7  117.54  4525.7  118.04  4664.5  120.06  4768.2  124.66
  4871.8  125.68  4958.7  123.93  4989.9  118.31  5029.5  118.36  5095.5  124.31
  5153.7  124.56  5314.4  125.21  5373.1  128.17  5432.8  127.75  5557.7  126.41
  5837.4  134.33    6094  138.42  6234.4  139.78    6438   140.6  6524.3   140.5
  6564.5  140.65  7030.2  139.39  7140.2  139.35  7347.8  139.29  7359.1  139.13
#Mann= 20 ,-1 , 0
  3398.5     .12       0  4315.6      .1       0  4474.7    .035       0
  4525.7      .1       0  4664.5     .12       0  4768.2    .033       0
  4871.8    .035       0  5095.5    .033       0  5153.7     .07       0
  5373.1     .12       0  5432.8     .07       0  5837.4     .05       0
    6094    .035       0  6234.4     .05       0    6438     .07       0
  6524.3    .035       0  6564.5     .07       0  7030.2    .035       0
  7140.2     .07       0  7347.8     .12       0
Bank Sta=4474.7,4525.7
XS Rating Curve= 0 ,0
Exp/Cntr=0.3,0.1

Type RM Length L Ch R = 1 ,53468   ,1097,1097,1097
BEGIN DESCRIPTION:
Mapping XS 47790635
END DESCRIPTION:
XS GIS Cut Line= 4
      2522674.62      13456922.1      2522966.29     13455658.19
      2522632.95     13454512.36      2521341.28     13452991.52
#Sta/Elev= 30
    3669  142.34  4240.7  128.93  4333.1  129.04  4359.4  134.72  4548.6  121.88
  4761.6   121.9  4910.6  123.94  4970.4  123.51  4975.2  116.12  4976.2  115.62
  5026.2  116.12  5146.5  118.56  5164.9  128.17  5208.4  129.64  5561.4  128.22
  6036.6  125.95  6132.9  125.58  6185.3  125.77  6450.8  125.89  6665.5   126.9
    6798  128.02  6930.6  130.59  7065.7  134.14  7210.7  137.44  7444.1  137.62
  7561.5  136.64  7708.3  135.14    7802  129.63  7927.3  133.97  8154.8  137.92
#Mann= 20 ,-1 , 0
    3669     .12       0  4761.6    .035       0  4910.6    .033       0
  4975.2    .033       0  5026.2    .033       0  5208.4     .05       0
  5561.4     .07       0  6036.6     .12       0  6132.9     .07       0
  6185.3     .12       0  6450.8     .07       0  6665.5    .035       0
    6798     .05       0  6930.6    .035       0  7065.7    .035       0
  7210.7     .05       0  7444.1    .035       0  7561.5     .05       0
  7708.3     .07       0  7927.3     .05       0
Bank Sta=4975.2,5026.2
XS Rating Curve= 0 ,0
Exp/Cntr=0.3,0.1

Type RM Length L Ch R = 1 ,52371   ,632,632,632
BEGIN DESCRIPTION:
Mapping XS 1846d39d
END DESCRIPTION:
XS GIS Cut Line= 3
       2524188.5     13456040.13      2523924.62     13455651.25
      2521599.14      13452881.5
#Sta/Elev= 30
  4547.6   143.5  4585.2  142.42  4600.1  139.66  4603.3  136.69  4612.2  138.99
  4675.1  127.52    4741  139.46  4914.6  140.57  4928.4  138.91  4941.6  132.42
  4950.6  126.05  4952.1  117.19  4953.1  116.69  5003.1  117.19  5051.2  117.94
  5102.3  123.72  5383.6  127.68  5639.4  125.51  6108.2  126.59    6204  121.77
  6443.9  126.78  6853.5  124.06  7409.6  133.93  7421.1  133.78    7655  134.93
  8102.8  135.84  8287.1     129  8365.9  134.23  8573.1  136.57  8634.1  137.18
#Mann= 16 ,-1 , 0
  4547.6     .07       0  4585.2    .033       0  4600.1     .07       0
  4952.1    .035       0  5003.1     .07       0  5051.2    .033       0
  5102.3    .035       0  5639.4     .05       0    6204     .12       0
  6443.9     .07       0  7409.6    .035       0  7421.1     .07       0
    7655     .05       0  8102.8     .07       0  8365.9     .05       0
  8573.1     .07       0
Bank Sta=4952.1,5003.1
XS Rating Curve= 0 ,0
Exp/Cntr=0.3,0.1

Type RM Length L Ch R = 1 ,51739   ,1337,1337,1337
BEGIN DESCRIPTION:
Mapping XS d54e4d6c
END DESCRIPTION:
XS GIS Cut Line= 4
      2524615.33     13455507.35      2524153.79     13455102.64
      2523278.79     13454401.25      2521703.22      13452659.1
#Sta/Elev= 30
  4414.4  144.04  4676.1   140.2  4763.3  139.51  4791.7  130.96  4834.4  129.75
  4877.6  136.68  4926.5  133.79  4957.9  115.94  4958.9  115.44    5009  115.94
  5252.3  125.42  5498.7  124.15  5741.9  125.34  5868.2  123.84  6057.5  121.22
  6284.1  121.07  6393.4  127.05  6491.6  124.97  6751.3  123.09  6928.2   129.8
  7200.2  131.46  7388.2   135.2  7427.8  135.94  7583.3  137.14  7719.7  136.48
  7856.2  134.76  7956.6  132.55  8046.8  127.33  8079.5  132.37  8498.6  137.63
#Mann= 20 ,-1 , 0
  4414.4    .035       0  4676.1     .07       0  4877.6    .033       0
  4957.9    .035       0    5009    .035       0  5252.3     .07       0
  5498.7     .05       0  5741.9    .035       0  5868.2     .05       0
  6057.5     .07       0  6393.4    .035       0  6491.6     .07       0
  7200.2    .035       0  7388.2     .05       0  7427.8    .035       0
  7583.3     .07       0  7719.7     .12       0  7856.2     .07       0
  7956.6     .12       0  8079.5     .07       0
Bank Sta=4957.9,5009
XS Rating Curve= 0 ,0
Exp/Cntr=0.3,0.1

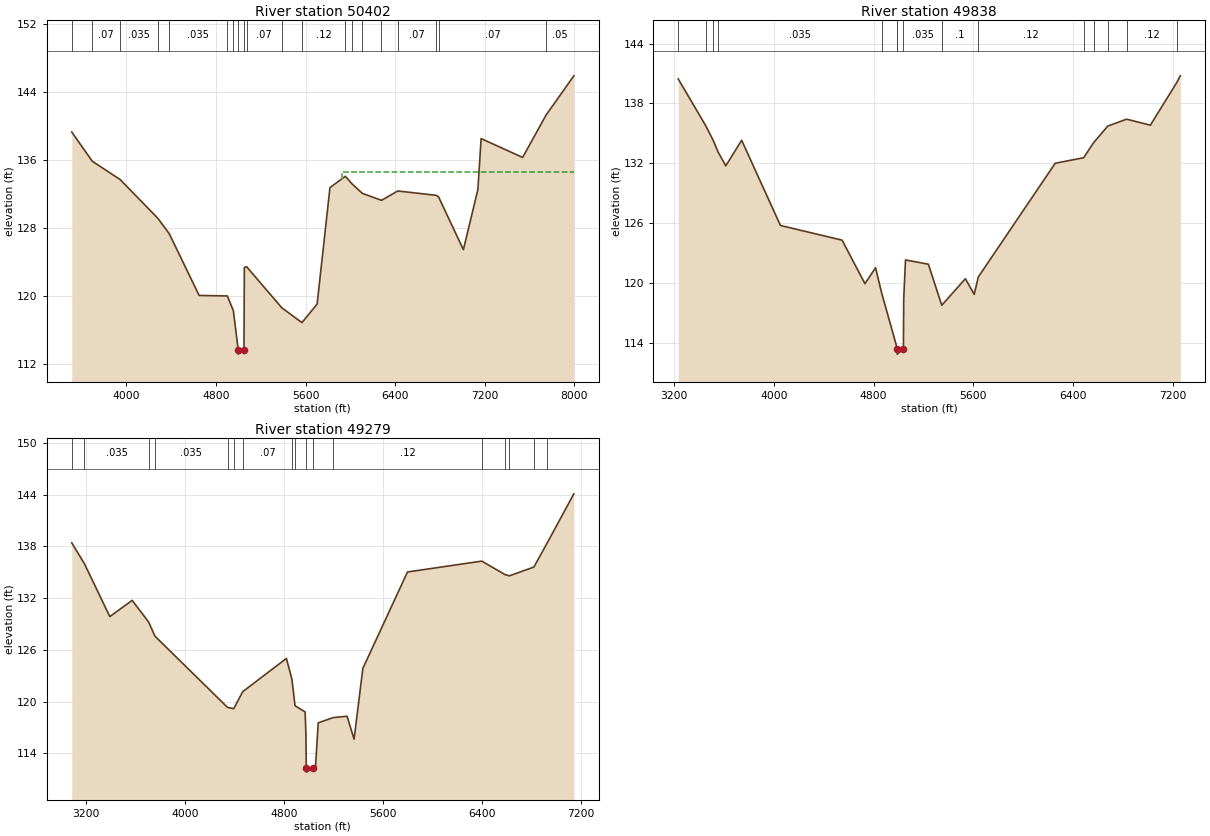
Type RM Length L Ch R = 1 ,50402   ,564,564,564
BEGIN DESCRIPTION:
PERDIDO CREEK 49.0
END DESCRIPTION:
XS GIS Cut Line= 3
        2525125.       13454725.        2523875.       13453925.
      2521474.99     13452124.99
#Sta/Elev= 30
  3511.6  139.26  3694.2  135.83  3944.2  133.66  4278.7  129.13  4381.9   127.3
    4649  120.02  4901.2  119.96    4955  118.22  4998.3  113.61  4999.3  113.11
  5049.4  113.61    5053  123.31  5073.3   123.4    5388  118.56  5567.4  116.82
    5703  119.01  5817.6  132.72    5955  134.05  6018.3  133.11    6107  132.04
  6277.8  131.22  6423.1  132.32  6766.2  131.81  6787.4  131.63  7009.2  125.41
  7138.4  132.47  7167.6  138.49  7538.4  136.27  7748.2  141.27  7995.7  145.88
#Mann= 20 ,-1 , 0
  3511.6     .05       0  3694.2     .07       0  3944.2    .035       0
  4278.7     .07       0  4381.9    .035       0  4901.2     .12       0
    4955      .1       0  4998.3     .05       0  5049.4      .1       0
  5073.3     .07       0    5388      .1       0  5567.4     .12       0
    5955     .07       0  6018.3     .12       0    6107     .07       0
  6277.8     .12       0  6423.1     .07       0  6766.2     .12       0
  6787.4     .07       0  7748.2     .05       0
#XS Ineff= 2 , 0
       0                  5923.8       0   134.6
Permanent Ineff=
       F       F
Bank Sta=4998.3,5049.4
XS Rating Curve= 0 ,0
Exp/Cntr=0.3,0.1

Type RM Length L Ch R = 1 ,49838   ,559,559,559
BEGIN DESCRIPTION:
PERDIDO CREEK 48.0
END DESCRIPTION:
XS GIS Cut Line= 3
      2525175.02     13454625.02        2523925.       13453375.
      2522325.03     13451775.03
#Sta/Elev= 30
  3232.2  140.46  3452.8  135.78  3512.5  134.32  3552.6  133.13  3614.1  131.76
  3741.3  134.32  4052.5  125.79  4547.5  124.32  4731.3  119.96  4816.2  121.56
  4864.4  119.07  4987.9  113.58  4988.6  113.41  4989.6  112.91  5039.7  113.41
  5042.4  118.45  5056.6  122.34  5240.4  121.91  5347.7   117.8  5537.4  120.46
  5608.1  118.89  5640.9  120.63  6258.6  132.02  6486.7  132.57  6566.7  134.08
  6680.4  135.74  6831.5  136.43  7022.3  135.83  7234.2   140.1  7262.7  140.77
#Mann= 15 ,-1 , 0
  3232.2     .05       0  3452.8    .035       0  3512.5     .07       0
  3552.6    .035       0  4864.4     .12       0  4987.9    .035       0
  4988.6     .05       0  5039.7    .035       0  5347.7      .1       0
  5640.9     .12       0  6486.7     .07       0  6566.7     .12       0
  6680.4     .07       0  6831.5     .12       0  7234.2     .07       0
Bank Sta=4988.6,5039.7
XS Rating Curve= 0 ,0
Exp/Cntr=0.3,0.1

Type RM Length L Ch R = 1 ,49279   ,1025,1025,1025
BEGIN DESCRIPTION:
PERDIDO CREEK 47.0
END DESCRIPTION:
XS GIS Cut Line= 3
      2525175.01     13454425.02        2524075.       13452875.
      2522474.97     13451424.97
#Sta/Elev= 30
  3082.1  138.41  3184.3  135.99  3389.7  129.86  3570.5  131.74  3703.3  129.24
  3754.8  127.59  4341.4  119.34  4391.5  119.18  4464.8  121.16  4817.9  125.01
  4862.4  122.59  4887.7  119.52  4969.3  118.81  4975.4  116.26  4978.5  112.33
  4979.5  111.83  5029.6  112.33  5053.4  112.54    5075  117.54  5195.5  118.15
  5308.2  118.31    5365  115.65  5435.9  123.85  5796.8  135.03  6397.6  136.29
    6584  134.74  6620.5  134.58  6818.8   135.6  6928.5  138.44  7142.1  144.09
#Mann= 17 ,-1 , 0
  3082.1     .05       0  3184.3    .035       0  3703.3     .05       0
  3754.8    .035       0  4341.4     .07       0  4391.5    .035       0
  4464.8     .07       0  4862.4    .035       0  4887.7     .07       0
  4978.5     .05       0  5029.6     .07       0  5195.5     .12       0
  6397.6     .07       0    6584     .12       0  6620.5     .07       0
  6818.8     .12       0  6928.5     .07       0
Bank Sta=4978.5,5029.6
XS Rating Curve= 0 ,0
Exp/Cntr=0.3,0.1