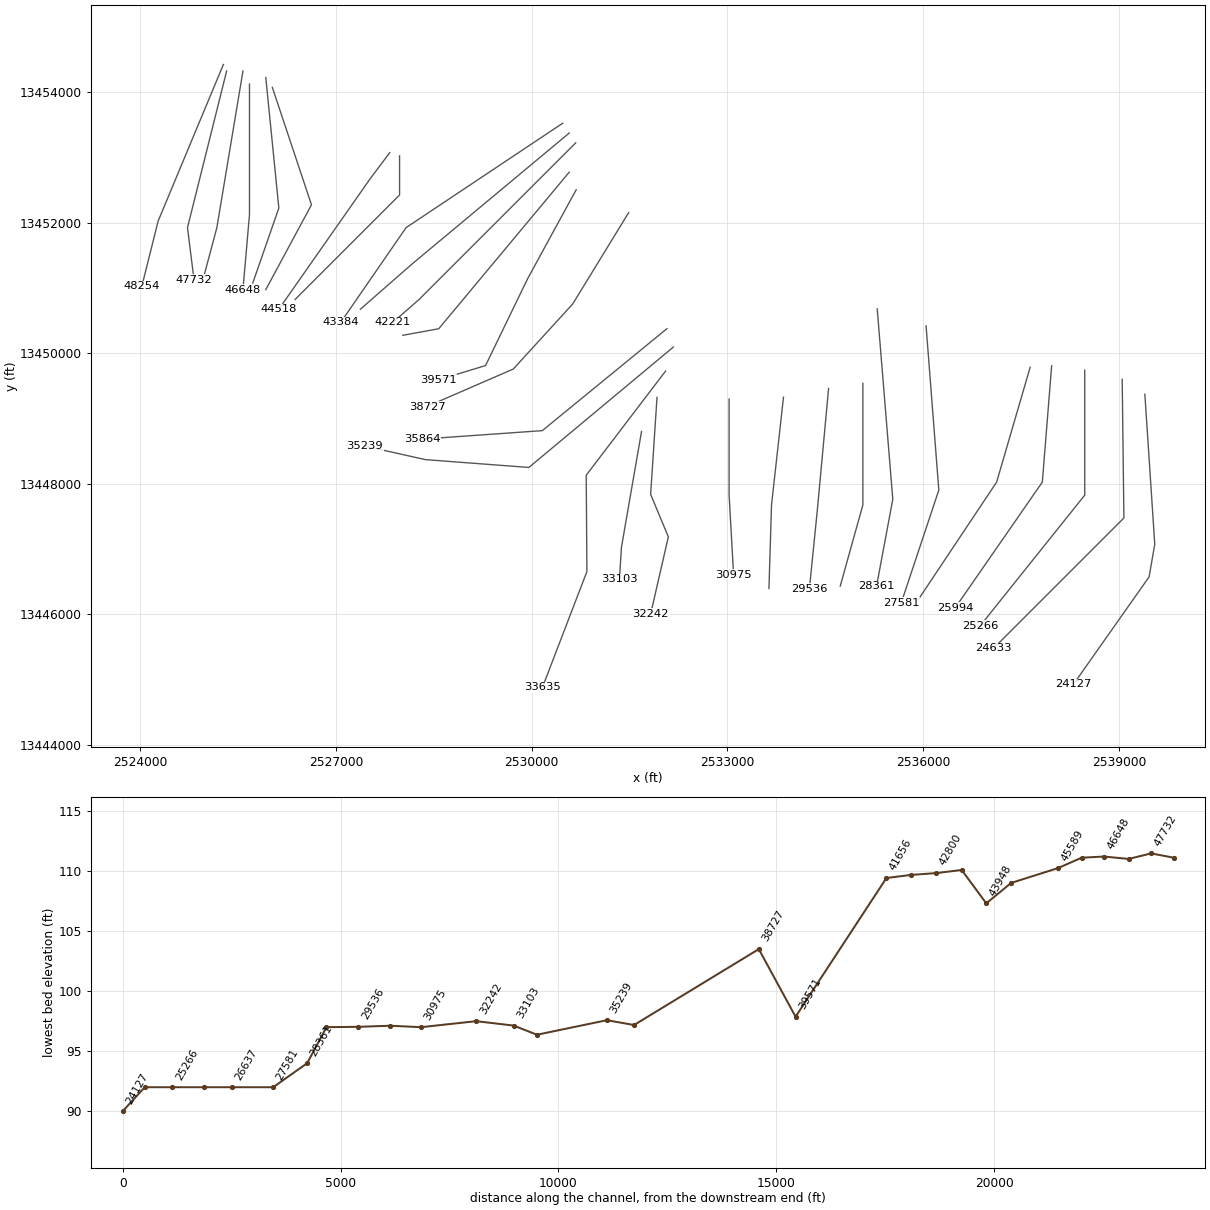
HEC-RAS study PERDIDO CREEK.prj: PERDIDO CREEK Base Level Engineering

--- PERDIDO CREEK.g01 (geometry) --- (continued)

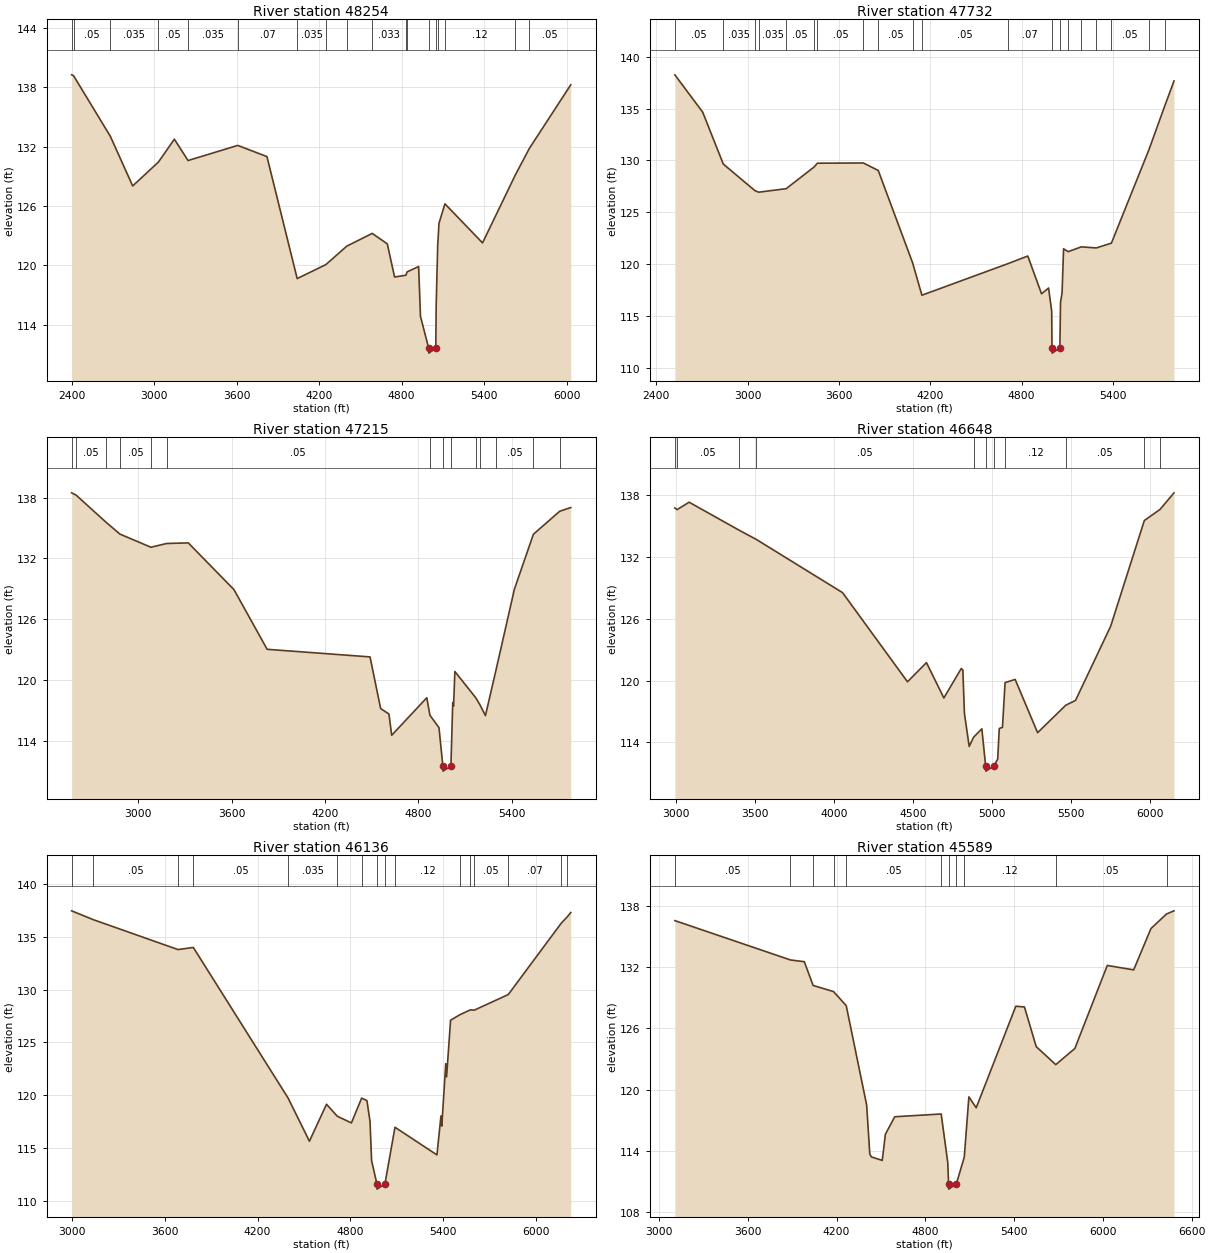
Type RM Length L Ch R = 1 ,48254   ,522,522,522
BEGIN DESCRIPTION:
PERDIDO CREEK 46.0
END DESCRIPTION:
XS GIS Cut Line= 3
      2525275.01     13454425.02        2524275.       13452025.
        2524025.       13451025.
#Sta/Elev= 30
  2400.2  139.26    2414  139.18  2682.3  133.03  2844.4  128.02  3031.8  130.44
  3147.7  132.75    3247  130.59  3608.5  132.12    3821  130.99    4041  118.65
  4249.1  120.06  4402.6  121.94  4587.1  123.22  4696.4  122.16  4749.4  118.81
    4832  118.99  4840.9  119.33  4924.4  119.87  4937.9  114.83  4997.5  111.61
  4998.5  111.11  5049.3  111.61  5051.8   115.8  5062.9  121.92  5072.4  124.24
  5115.7  126.21  5389.3  122.26  5627.7  129.13    5730  131.82    6031  138.25
#Mann= 18 ,-1 , 0
  2400.2     .07       0    2414     .05       0  2682.3    .035       0
  3031.8     .05       0    3247    .035       0  3608.5     .07       0
    4041    .035       0  4249.1     .05       0  4402.6     .07       0
  4587.1    .033       0    4832     .05       0  4840.9    .033       0
  4997.5    .033       0  5049.3    .033       0  5062.9     .07       0
  5115.7     .12       0  5627.7     .07       0    5730     .05       0
Bank Sta=4997.5,5049.3
XS Rating Curve= 0 ,0
Exp/Cntr=0.3,0.1

Type RM Length L Ch R = 1 ,47732   ,517,517,517
BEGIN DESCRIPTION:
PERDIDO CREEK 45.0
END DESCRIPTION:
XS GIS Cut Line= 3
      2525324.99     13454324.96        2524725.       13451925.
      2524824.99     13451125.04
#Sta/Elev= 30
  2521.9  138.24  2704.8  134.65    2840  129.66  3048.9  127.09  3073.1  126.95
  3253.6  127.29  3437.4  129.38  3458.4  129.74  3760.6  129.76  3858.4  129.04
  4083.9  120.17  4145.3  117.04  4713.2  120.09  4841.1  120.81  4931.3  117.18
  4977.7  117.73  4998.2   115.5  5000.1  111.97  5001.1  111.47  5051.9  111.97
  5056.2  116.35  5066.3  117.27  5076.3  121.51  5106.1  121.23  5192.4  121.69
  5291.4  121.59  5390.5  122.05  5637.8  131.06  5739.7  135.19  5801.9  137.65
#Mann= 20 ,-1 , 0
  2521.9     .05       0    2840    .035       0  3048.9     .05       0
  3073.1    .035       0  3253.6     .05       0  3437.4    .035       0
  3458.4     .05       0  3760.6    .033       0  3858.4     .05       0
  4083.9    .035       0  4145.3     .05       0  4713.2     .07       0
  5000.1     .05       0  5051.9     .07       0  5106.1     .07       0
  5192.4     .05       0  5291.4     .12       0  5390.5     .05       0
  5637.8     .07       0  5739.7     .05       0
Bank Sta=5000.1,5051.9
XS Rating Curve= 0 ,0
Exp/Cntr=0.3,0.1

Type RM Length L Ch R = 1 ,47215   ,567,567,567
BEGIN DESCRIPTION:
PERDIDO CREEK 44.0
END DESCRIPTION:
XS GIS Cut Line= 3
      2525575.01     13454325.05        2525175.       13451925.
      2524974.99     13451174.96
#Sta/Elev= 30
  2571.6  138.47  2600.7  138.24  2790.6   135.6  2881.9   134.4  3081.6   133.1
    3182  133.47  3321.9  133.53  3615.9  128.91  3828.8  123.03  4490.3  122.28
  4558.7  117.18  4611.9  116.65  4629.7  114.55  4855.2  118.25  4875.6  116.52
  4933.8   115.3  4958.6  111.51  4959.6  111.01  5010.4  111.51  5022.2  117.78
  5027.4  117.44  5035.8  120.84  5170.1  118.25  5195.7  117.59  5232.4  116.49
  5298.6  120.87  5418.7  128.97  5540.7  134.38    5710  136.65    5781  137.02
#Mann= 14 ,-1 , 0
  2571.6     .12       0  2600.7     .05       0  2790.6     .07       0
  2881.9     .05       0  3081.6    .035       0    3182     .05       0
  4875.6    .033       0  4958.6     .05       0  5010.4    .033       0
  5170.1     .12       0  5195.7     .07       0  5298.6     .05       0
  5540.7     .12       0    5710     .07       0
Bank Sta=4958.6,5010.4
XS Rating Curve= 0 ,0
Exp/Cntr=0.3,0.1

Type RM Length L Ch R = 1 ,46648   ,512,512,512
BEGIN DESCRIPTION:
PERDIDO CREEK 43.0
END DESCRIPTION:
XS GIS Cut Line= 3
        2525675.     13454125.01        2525675.       13452125.
        2525575.     13450974.95
#Sta/Elev= 30
  2995.1  136.75  3009.5  136.59  3085.1  137.31  3402.7  134.58  3509.6   133.7
  4055.1  128.53  4465.1  119.88  4585.1  121.74  4695.1  118.31  4805.1  121.17
  4815.1  121.02  4825.1  116.81  4855.1  113.61  4883.1   114.5  4935.1  115.32
  4959.2  111.71  4960.2  111.21  5011.1  111.71  5035.3  112.38  5045.3  115.35
  5065.4  115.46  5081.9   119.8  5145.7  120.11  5287.5  114.94  5465.7  117.61
  5527.1  118.07  5749.2  125.27  5961.9  135.53  6061.2  136.61  6149.5  138.22
#Mann= 11 ,-1 , 0
  2995.1     .07       0  3009.5     .05       0  3402.7    .035       0
  3509.6     .05       0  4883.1    .033       0  4959.2    .033       0
  5011.1    .033       0  5081.9     .12       0  5465.7     .05       0
  5961.9     .07       0  6061.2     .12       0
Bank Sta=4959.2,5011.1
XS Rating Curve= 0 ,0
Exp/Cntr=0.3,0.1

Type RM Length L Ch R = 1 ,46136   ,547,547,547
BEGIN DESCRIPTION:
PERDIDO CREEK 42.0
END DESCRIPTION:
XS GIS Cut Line= 3
        2525925.     13454224.98        2526125.       13452225.
      2525725.01     13451075.03
#Sta/Elev= 30
  2997.8  137.47  3138.4  136.63  3685.9   133.8  3784.7     134  4397.4  119.74
  4535.4  115.65    4646  119.15  4715.2  118.02  4806.8  117.38  4873.1  119.73
  4907.3   119.5  4927.4  117.51  4937.4  113.81  4971.7  111.61  4972.7  111.11
  5023.7  111.61  5088.7  116.97  5360.1  114.35  5385.9  118.04  5391.2  117.08
    5417  122.98  5422.3  121.74  5448.1  127.11  5508.5  127.63  5575.9  128.09
  5601.2  128.06  5821.3  129.54  6164.4  136.31  6203.8  136.92  6225.3  137.31
#Mann= 16 ,-1 , 0
  2997.8     .07       0  3138.4     .05       0  3685.9    .035       0
  3784.7     .05       0  4397.4    .035       0  4715.2     .05       0
  4873.1    .033       0  4971.7    .033       0  5023.7    .033       0
  5088.7     .12       0  5508.5     .05       0  5575.9     .12       0
  5601.2     .05       0  5821.3     .07       0  6164.4     .05       0
  6203.8     .07       0
Bank Sta=4971.7,5023.7
XS Rating Curve= 0 ,0
Exp/Cntr=0.3,0.1

Type RM Length L Ch R = 1 ,45589   ,1071,1071,1071
BEGIN DESCRIPTION:
PERDIDO CREEK 41.0
END DESCRIPTION:
XS GIS Cut Line= 3
        2526025.       13454075.        2526625.       13452275.
      2525924.98     13450974.96
#Sta/Elev= 30
  3106.8  136.58  3888.3  132.72  3981.7  132.55  4041.3  130.22  4179.2  129.62
  4265.1  128.24  4403.3  118.49  4424.4  113.69    4435   113.4  4508.7  113.06
  4529.8  115.62  4593.1  117.34    4907  117.61  4951.5  112.85  4957.1  110.74
  4958.1  110.24  5009.1  110.74    5063  113.37  5094.2  119.29  5143.7  118.22
  5411.4  128.18  5469.8  128.11  5549.3  124.22  5681.5  122.45  5810.6  124.04
  6029.6  132.18  6208.1  131.75  6324.9   135.8    6430  137.23  6480.7  137.54
#Mann= 11 ,-1 , 0
  3106.8     .05       0  3888.3    .035       0  4041.3     .05       0
  4179.2    .035       0  4265.1     .05       0    4907    .033       0
  4957.1    .033       0  5009.1    .033       0    5063     .12       0
  5681.5     .05       0    6430     .07       0
Bank Sta=4957.1,5009.1
XS Rating Curve= 0 ,0
Exp/Cntr=0.3,0.1

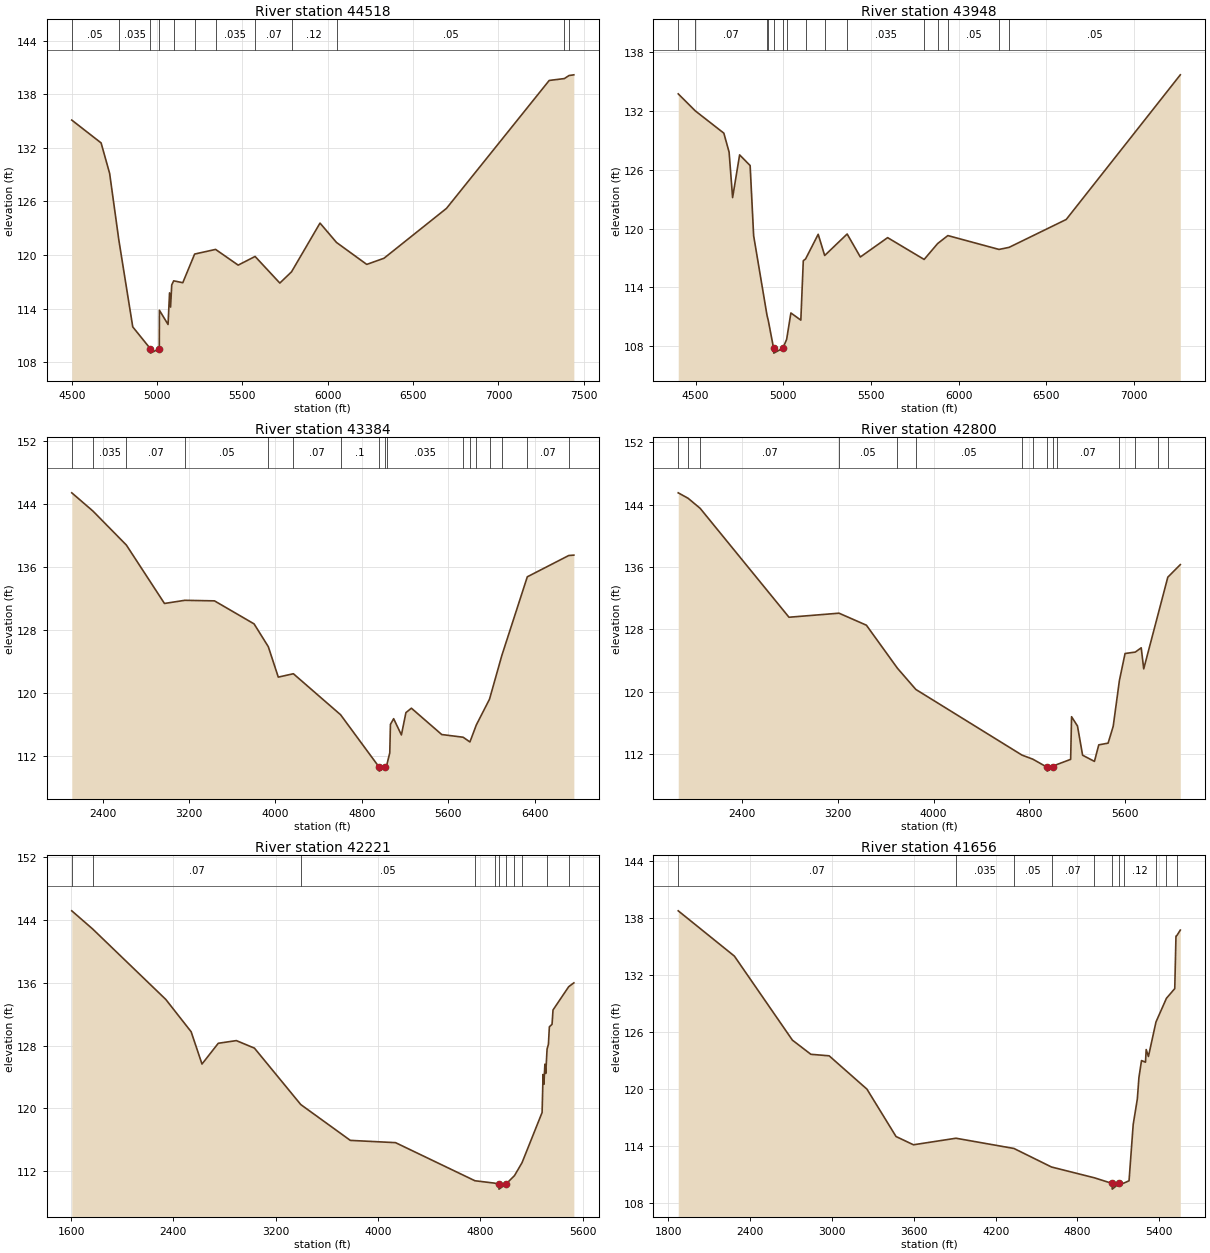
Type RM Length L Ch R = 1 ,44518   ,570,570,570
BEGIN DESCRIPTION:
PERDIDO CREEK 40.0
END DESCRIPTION:
XS GIS Cut Line= 3
      2527825.02     13453075.02        2527525.       13452675.
      2526125.02     13450675.03
#Sta/Elev= 30
  4500.4  135.12  4672.3  132.56  4722.3  129.14  4775.8  121.73  4857.7  111.95
  4960.6  109.51  4961.6  109.01  5013.1  109.51  5013.9  113.81  5064.5  112.22
  5073.2  115.76  5079.3  114.17  5085.9  116.64  5097.4  117.11  5150.8   116.9
  5220.2  120.11    5343  120.63  5475.2  118.87  5574.4  119.84  5719.3  116.86
  5787.9  118.12  5954.7  123.58  6051.3  121.41  6228.5  118.95  6329.6  119.64
  6695.8  125.23  7297.4  139.56  7386.3  139.77  7413.3  140.11  7441.7  140.19
#Mann= 12 ,-1 , 0
  4500.4     .05       0  4775.8    .035       0  4960.6    .035       0
  5013.1    .035       0  5097.4    .033       0  5220.2     .07       0
    5343    .035       0  5574.4     .07       0  5787.9     .12       0
  6051.3     .05       0  7386.3    .035       0  7413.3     .05       0
Bank Sta=4960.6,5013.1
XS Rating Curve= 0 ,0
Exp/Cntr=0.3,0.1

Type RM Length L Ch R = 1 ,43948   ,564,564,564
BEGIN DESCRIPTION:
PERDIDO CREEK 39.0
END DESCRIPTION:
XS GIS Cut Line= 3
        2527975.     13453024.96        2527975.       13452425.
        2526375.       13450825.
#Sta/Elev= 30
  4400.7  133.71  4498.6  131.97  4660.7  129.71  4690.7  127.78  4710.7  123.15
  4750.7   127.5  4810.7  126.41  4830.7  119.26  4906.7  111.18  4914.5   110.6
  4944.4  107.81  4945.4  107.31    4997  107.81  5018.7   108.7  5043.1   111.4
  5099.7  110.67  5113.8  116.72  5126.8   116.9  5198.7  119.41  5235.7  117.25
  5363.8  119.44  5439.1   117.1  5594.6  119.07  5802.8  116.85  5879.9  118.47
    5938  119.28  6229.7  117.87  6287.1  118.08  6612.9  120.92  7263.4  135.65
#Mann= 15 ,-1 , 0
  4400.7     .05       0  4498.6     .07       0  4906.7    .035       0
  4914.5      .1       0  4944.4     .05       0    4997      .1       0
  5018.7    .033       0  5126.8    .035       0  5235.7     .07       0
  5363.8    .035       0  5802.8     .05       0  5879.9     .12       0
    5938     .05       0  6229.7     .07       0  6287.1     .05       0
Bank Sta=4944.4,4997
XS Rating Curve= 0 ,0
Exp/Cntr=0.3,0.1

Type RM Length L Ch R = 1 ,43384   ,584,584,584
BEGIN DESCRIPTION:
PERDIDO CREEK 38.0
END DESCRIPTION:
XS GIS Cut Line= 3
      2530475.01     13453525.01        2528075.       13451925.
      2527075.02     13450475.03
#Sta/Elev= 30
  2115.4  145.38  2311.2  143.07  2620.4  138.76  2973.2  131.35  3160.9  131.75
  3435.9  131.68  3802.5  128.76    3934  125.87  4026.4  122.01  4165.9  122.44
  4602.8  117.24    4960  110.59  4961.1  110.09  5012.6  110.59  5031.5  110.94
    5058  112.41  5064.1  116.02  5093.8  116.74  5165.5  114.68  5207.4  117.51
  5258.1  118.07  5538.7  114.73  5736.4  114.39  5799.6  113.79  5858.6  115.94
  5980.8  119.21  6094.3  124.73  6330.6  134.73  6713.9  137.43  6761.2  137.48
#Mann= 17 ,-1 , 0
  2115.4     .07       0  2311.2    .035       0  2620.4     .07       0
  3160.9     .05       0    3934     .12       0  4165.9     .07       0
  4602.8      .1       0    4960     .05       0  5012.6      .1       0
  5031.5    .035       0  5736.4     .05       0  5799.6     .07       0
  5858.6     .05       0  5980.8     .07       0  6094.3     .12       0
  6330.6     .07       0  6713.9     .05       0
Bank Sta=4960,5012.6
XS Rating Curve= 0 ,0
Exp/Cntr=0.3,0.1

Type RM Length L Ch R = 1 ,42800   ,579,579,579
BEGIN DESCRIPTION:
PERDIDO CREEK 37.0
END DESCRIPTION:
XS GIS Cut Line= 3
        2530575.       13453375.        2528175.       13451375.
      2527375.01     13450675.01
#Sta/Elev= 30
    1871  145.53  1953.4  144.83  2053.9  143.54  2794.6  129.57  3211.9  130.09
  3440.2  128.55    3699  123.03  3852.3  120.31  4737.3  111.89  4828.6  111.36
  4947.3  110.33  4948.3  109.83    5000  110.33  5029.4  110.68  5143.6  111.34
  5151.2  116.81  5200.6  115.62  5243.3  111.87    5342  111.08  5378.1   113.2
  5455.9  113.42  5498.6  115.59    5550  121.44  5597.3  124.92  5682.7   125.1
  5732.1  125.65    5753  122.95  5871.1  129.86  5953.9  134.71  6058.1  136.32
#Mann= 15 ,-1 , 0
    1871     .12       0  1953.4    .035       0  2053.9     .07       0
  3211.9     .05       0    3699     .07       0  3852.3     .05       0
  4737.3    .035       0  4828.6    .033       0  4947.3    .033       0
    5000    .033       0  5029.4     .07       0    5550     .12       0
  5682.7     .07       0  5871.1     .12       0  5953.9     .07       0
Bank Sta=4947.3,5000
XS Rating Curve= 0 ,0
Exp/Cntr=0.3,0.1

Type RM Length L Ch R = 1 ,42221   ,565,565,565
BEGIN DESCRIPTION:
PERDIDO CREEK 36.0
END DESCRIPTION:
XS GIS Cut Line= 3
      2530674.98     13453224.98        2528275.       13450825.
      2527874.99     13450474.99
#Sta/Elev= 30
  1605.8  145.19  1768.7  142.88  2341.2  133.88  2539.2  129.76    2624  125.64
  2751.3  128.29  2892.7  128.63  3034.1  127.67  3396.4  120.47  3783.7   115.9
  4137.2  115.61  4757.9  110.75  4913.8  110.44  4945.1  110.28  4946.2  109.68
    4998  110.28  5067.2   111.4  5126.5  113.06  5283.2  119.46  5290.8  124.31
  5297.4  123.06    5305  125.62  5311.7  124.44  5322.2  127.56  5332.6  128.15
  5340.1  130.39    5361  130.71  5368.6  132.54  5491.2  135.51  5531.4     136
#Mann= 11 ,-1 , 0
  1605.8     .12       0  1768.7     .07       0  3396.4     .05       0
  4757.9    .035       0  4913.8    .033       0  4945.1    .033       0
    4998    .033       0  5067.2     .07       0  5126.5     .12       0
  5322.2     .07       0  5491.2     .12       0
Bank Sta=4945.1,4998
XS Rating Curve= 0 ,0
Exp/Cntr=0.3,0.1

Type RM Length L Ch R = 1 ,41656   ,2085,2085,2085
BEGIN DESCRIPTION:
PERDIDO CREEK 35.0
END DESCRIPTION:
XS GIS Cut Line= 3
      2530574.99     13452774.98        2528575.       13450375.
      2528024.99       13450275.
#Sta/Elev= 30
  1871.5  138.73  2283.5  133.96  2709.1  125.11  2844.5  123.62  2978.6  123.46
  3255.8  119.95  3469.3  114.96  3596.9  114.09    3909  114.78  4334.6   113.7
  4609.7  111.75    4925  110.61  5054.3  110.02  5055.3  109.42  5107.2  110.02
  5139.9  110.05  5178.5   110.3    5209  116.23  5239.5  118.93  5250.9  121.16
    5270  122.96  5299.2  122.79  5304.3  124.12  5320.8  123.39    5376  127.02
  5452.9  129.52  5513.9  130.54  5522.8  136.07  5528.9  136.12  5554.6   136.7
#Mann= 11 ,-1 , 0
  1871.5     .07       0    3909    .035       0  4334.6     .05       0
  4609.7     .07       0    4925    .035       0  5054.3    .035       0
  5107.2    .035       0  5139.9     .12       0    5376     .07       0
  5452.9     .12       0  5528.9     .07       0
Bank Sta=5054.3,5107.2
XS Rating Curve= 0 ,0
Exp/Cntr=0.3,0.1

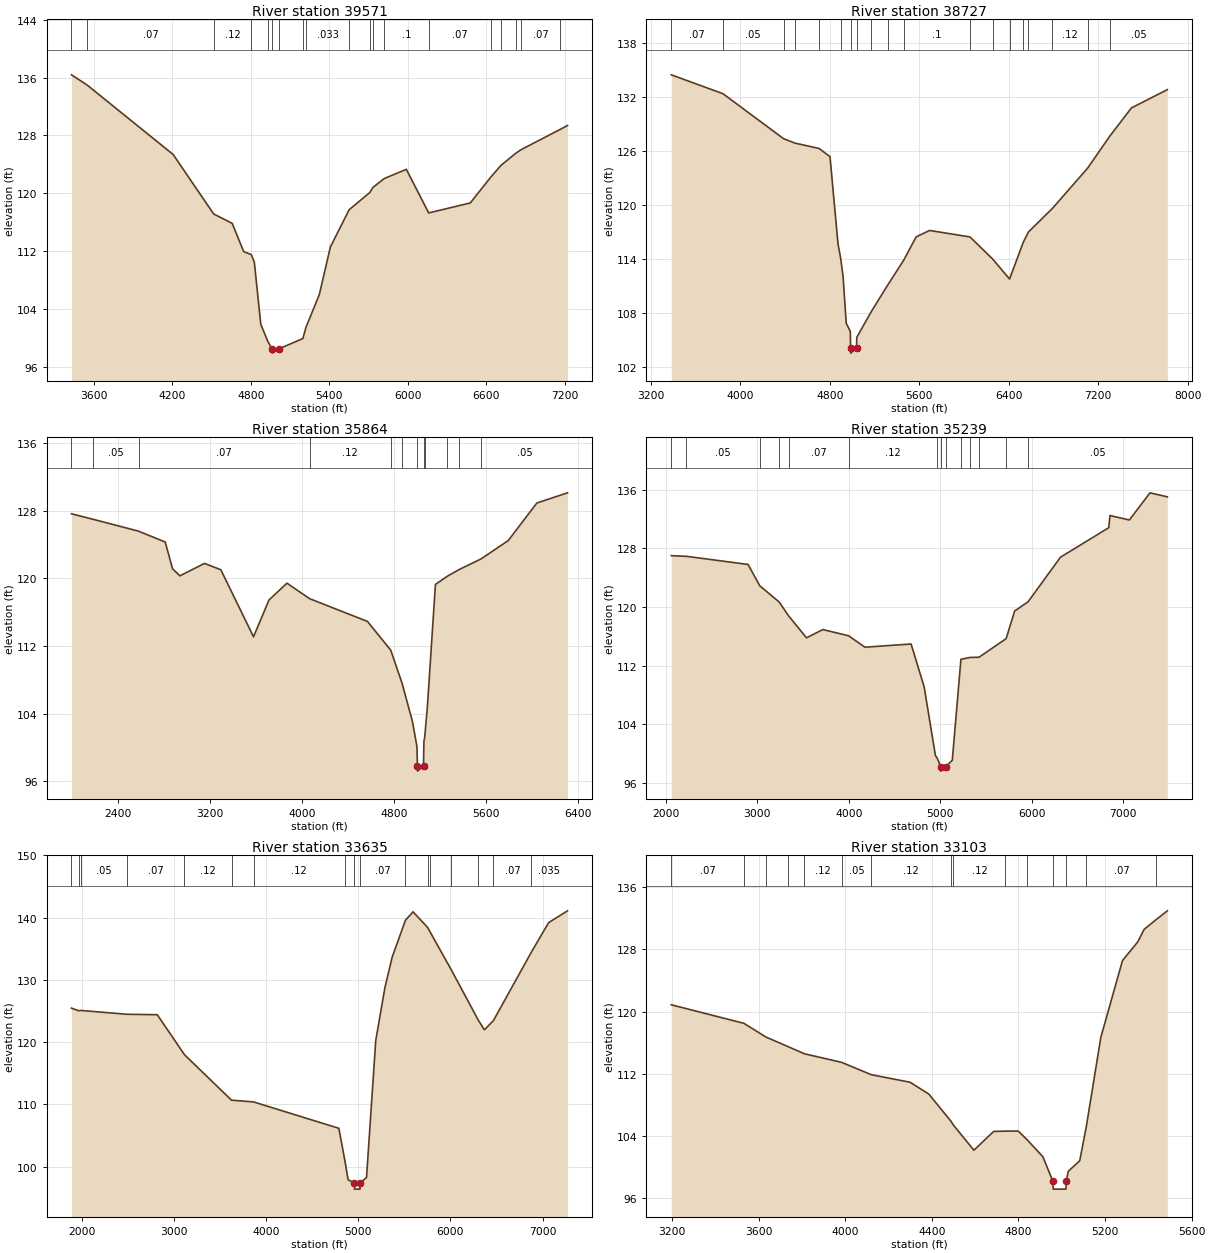
Type RM Length L Ch R = 1 ,39571   ,844,844,844
BEGIN DESCRIPTION:
Mapping XS e4a61733
END DESCRIPTION:
XS GIS Cut Line= 4
      2530681.58     13452505.44      2529938.51     13451144.31
      2529292.68     13449810.97      2528563.56     13449588.76
#Sta/Elev= 30
  3427.9  136.38  3549.1  134.95  4206.1  125.35  4515.6  117.13  4657.8  115.82
  4745.1  111.92  4803.6   111.5  4826.8  110.46  4876.1  101.86  4930.8   99.46
  4962.5   98.47  4963.6   97.87  5015.5   98.47  5197.7   99.88  5221.2  101.41
  5323.6  105.96  5408.4  112.55  5551.9  117.71  5709.8  120.09  5734.3  120.81
  5820.9  122.03  5989.6   123.3  6160.5  117.27  6478.6  118.65  6635.2  122.22
  6713.4  123.85  6826.3  125.52  6866.9  126.02  7165.6  128.82  7222.4  129.37
#Mann= 19 ,-1 , 0
  3427.9     .05       0  3549.1     .07       0  4515.6     .12       0
  4803.6     .07       0  4930.8    .033       0  4962.5    .033       0
  5015.5    .033       0  5197.7    .035       0  5221.2    .033       0
  5551.9     .07       0  5709.8      .1       0  5734.3     .07       0
  5820.9      .1       0  6160.5     .07       0  6635.2     .12       0
  6713.4     .07       0  6826.3     .12       0  6866.9     .07       0
  7165.6     .05       0
Bank Sta=4962.5,5015.5
XS Rating Curve= 0 ,0
Exp/Cntr=0.3,0.1

Type RM Length L Ch R = 1 ,38727   ,2863,2863,2863
BEGIN DESCRIPTION:
Mapping XS f23618e7
END DESCRIPTION:
XS GIS Cut Line= 4
      2531486.14     13452155.55      2530628.94     13450755.83
      2529717.48     13449757.56      2528393.72     13449182.49
#Sta/Elev= 30
  3382.1  134.49    3844  132.39  4386.5  127.38  4487.3  126.89  4703.5  126.29
  4801.6  125.38    4873  115.68  4897.7  114.01  4918.9  111.99  4946.5  106.83
  4983.2  105.91  4986.1   104.1  4987.2   103.5  5039.2   104.1  5040.8  105.25
  5169.7   108.1  5317.3  111.07  5459.9  113.83  5571.8  116.44  5692.1  117.16
  6053.5  116.44  6256.8  113.97  6407.5  111.75  6529.7  115.83  6576.4  116.99
  6788.2  119.58  7105.7   124.1  7302.7  127.64    7497   130.8  7818.5  132.84
#Mann= 19 ,-1 , 0
  3382.1     .07       0    3844     .05       0  4386.5     .07       0
  4487.3     .12       0  4703.5     .07       0  4897.7    .033       0
  4986.1    .033       0  5039.2    .033       0  5169.7      .1       0
  5317.3    .035       0  5459.9      .1       0  6053.5     .05       0
  6256.8     .07       0  6407.5     .05       0  6529.7     .07       0
  6576.4      .1       0  6788.2     .12       0  7105.7     .07       0
  7302.7     .05       0
Bank Sta=4986.1,5039.2
XS Rating Curve= 0 ,0
Exp/Cntr=0.3,0.1

Type RM Length L Ch R = 1 ,35864   ,625,625,625
BEGIN DESCRIPTION:
Mapping XS daab60f2
END DESCRIPTION:
XS GIS Cut Line= 3
      2532072.09     13450376.06      2530162.36     13448813.55
      2528318.84     13448683.42
#Sta/Elev= 30
  1993.2  127.66  2183.3     127  2576.5   125.6    2809  124.31  2872.9  121.14
  2936.8  120.31  3150.7  121.78  3292.8  121.03  3577.1  113.09  3711.3  117.44
  3867.8  119.44  4065.7   117.6  4568.3  114.91  4771.2   111.5  4869.5  107.59
  4959.3  103.09  4999.4  100.06  5002.8   97.78  5003.9   97.18  5056.1   97.78
  5059.5  100.71  5066.2  101.17  5089.6  104.77  5159.8  119.29  5262.8  120.26
  5361.2  121.02  5557.8  122.32  5792.8  124.48    6042  128.93  6308.8  130.14
#Mann= 12 ,-1 , 0
  1993.2     .07       0  2183.3     .05       0  2576.5     .07       0
  4065.7     .12       0  4771.2     .07       0  4869.5    .033       0
  5002.8    .033       0  5056.1    .033       0  5066.2     .12       0
  5262.8     .07       0  5361.2      .1       0  5557.8     .05       0
Bank Sta=5002.8,5056.1
XS Rating Curve= 0 ,0
Exp/Cntr=0.3,0.1

Type RM Length L Ch R = 1 ,35239   ,1604,1604,1604
BEGIN DESCRIPTION:
Mapping XS 414e81aa
END DESCRIPTION:
XS GIS Cut Line= 4
       2532169.7     13450093.91       2529956.2     13448249.32
      2528369.55     13448369.45      2527440.06     13448577.39
#Sta/Elev= 30
  2058.1     127  2224.2  126.91    2898   125.8  3025.7  122.89    3238  120.67
  3341.3  118.78  3537.1  115.78  3715.4  116.91  3997.6  116.06  4176.2   114.5
  4680.7  114.94  4823.2   109.1  4947.1   99.69  4965.4   99.39  5004.2   98.18
  5005.3   97.58  5057.6   98.18  5131.2   99.06  5225.8  112.85  5324.5   113.1
  5423.3  113.13  5720.2  115.67  5813.1  119.44  5960.6  120.71  6314.6  126.79
  6842.7  130.82  6855.9  132.48  7068.1  131.87  7293.6  135.58  7483.1  135.03
#Mann= 14 ,-1 , 0
  2058.1     .12       0  2224.2     .05       0  3025.7     .07       0
    3238     .12       0  3341.3     .07       0  3997.6     .12       0
  4965.4      .1       0  5004.2     .05       0  5057.6      .1       0
  5225.8     .07       0  5324.5     .12       0  5423.3      .1       0
  5720.2     .07       0  5960.6     .05       0
Bank Sta=5004.2,5057.6
XS Rating Curve= 0 ,0
Exp/Cntr=0.3,0.1

Type RM Length L Ch R = 1 ,33635   ,532,532,532
BEGIN DESCRIPTION:
Mapping XS df41af37
END DESCRIPTION:
XS GIS Cut Line= 4
      2532050.36     13449724.98       2530835.1     13448129.96
      2530845.95     13446654.26      2530165.57      13444881.3
#Sta/Elev= 30
  1889.9  125.45  1968.8  125.02  1988.2  125.08  2492.6  124.46  2820.5  124.39
  3115.5  117.97  3625.7  110.66  3865.1  110.38  4790.1  106.14  4857.9  100.74
  4890.1   97.88  4959.2   97.37  4960.7   96.37  5019.5   96.37    5021   97.37
  5090.1   98.23  5190.1  120.24  5290.1  128.78    5368  133.62  5512.7  139.58
    5595  140.92  5753.4   138.4  5776.6  137.77    6009  131.61  6301.2  123.55
    6368  121.96  6466.1  123.44  6877.2  134.42    7065  139.18  7269.9  141.08
#Mann= 17 ,-1 , 0
  1889.9     .07       0  1968.8      .1       0  1988.2     .05       0
  2492.6     .07       0  3115.5     .12       0  3625.7     .07       0
  3865.1     .12       0  4857.9     .07       0  4959.2     .05       0
    5021     .07       0  5512.7     .05       0  5753.4    .035       0
  5776.6     .05       0    6009     .07       0  6301.2      .1       0
  6466.1     .07       0  6877.2    .035       0
Bank Sta=4959.2,5021
XS Rating Curve= 0 ,0
Exp/Cntr=0.3,0.1

Type RM Length L Ch R = 1 ,33103   ,861,861,861
BEGIN DESCRIPTION:
PERDIDO CREEK 29.0
END DESCRIPTION:
XS GIS Cut Line= 3
      2531683.29     13448802.24        2531375.       13447025.
      2531344.86     13446538.32
#Sta/Elev= 30
  3196.2  120.87  3531.9  118.48  3632.5  116.73  3733.1  115.51  3811.4  114.56
  3982.5  113.46  4119.8  111.87  4299.7  110.89  4385.8  109.37  4486.9  105.92
  4499.7  105.37    4594  102.14  4685.4  104.56    4739   104.6  4798.6  104.61
  4839.6   103.5    4913  101.29  4958.9   98.13  4960.4   97.13  5019.2   97.13
  5020.7   98.13    5030   99.42    5083  100.79    5113  105.12  5180.3  116.66
  5280.5  126.57  5350.7  128.96  5380.7  130.59  5437.3  131.87  5487.6  132.97
#Mann= 15 ,-1 , 0
  3196.2     .07       0  3531.9     .05       0  3632.5     .07       0
  3733.1     .05       0  3811.4     .12       0  3982.5     .05       0
  4119.8     .12       0  4486.9     .07       0  4499.7     .12       0
    4739    .033       0  4839.6     .07       0  4958.9    .033       0
  5020.7     .07       0    5113     .07       0  5437.3     .05       0
Bank Sta=4958.9,5020.7
XS Rating Curve= 0 ,0
Exp/Cntr=0.3,0.1

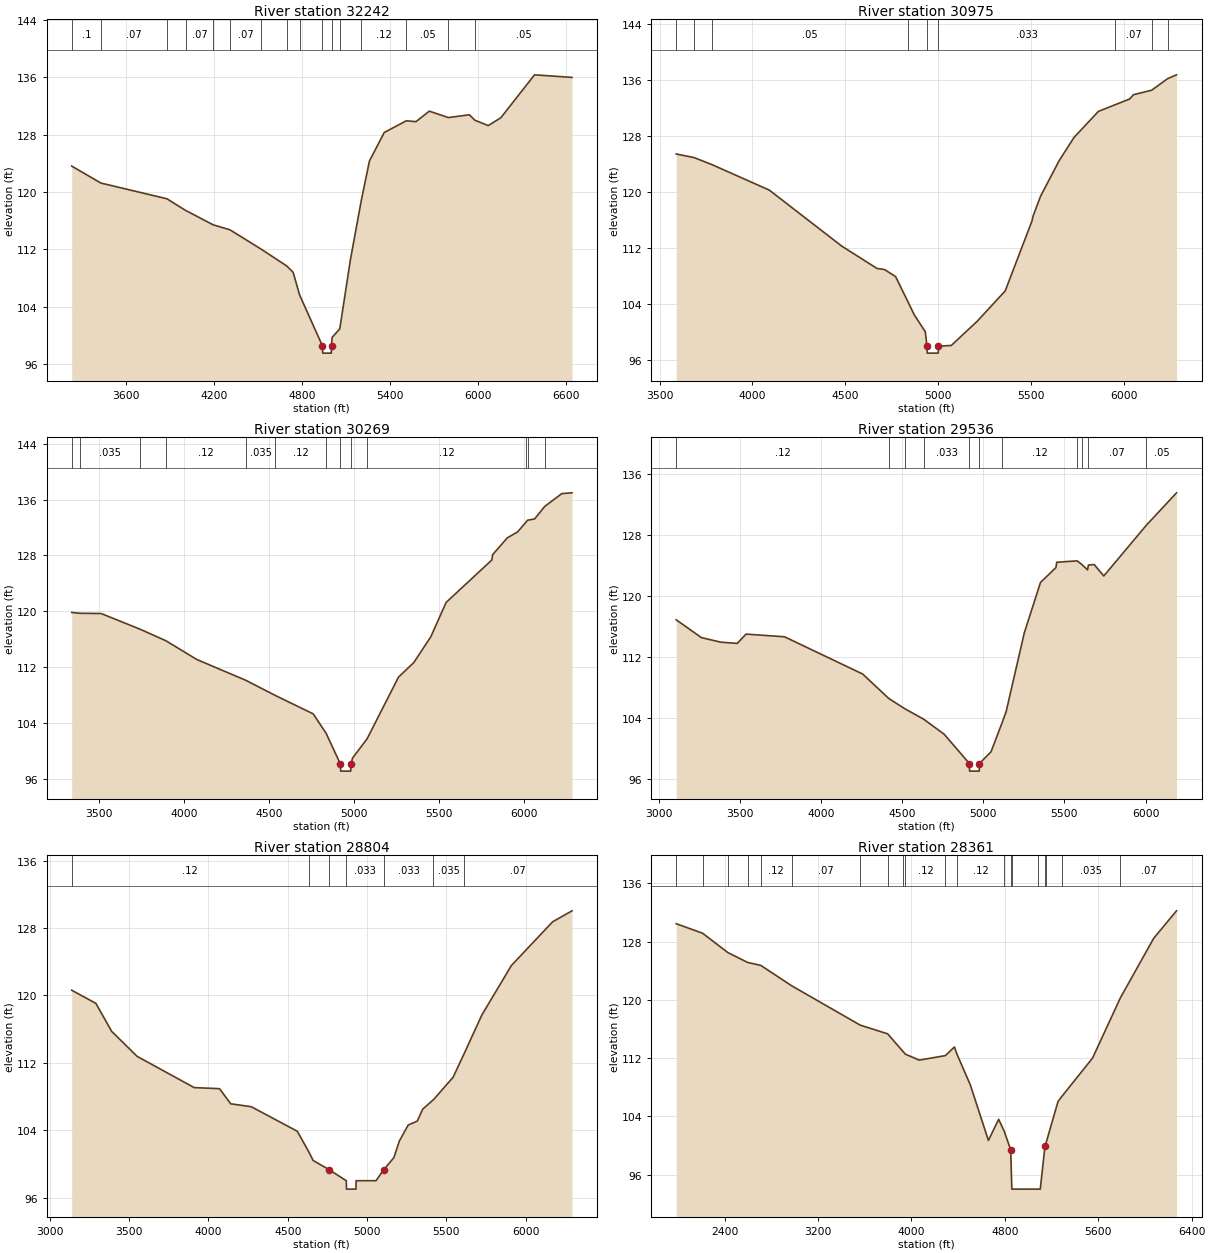
Type RM Length L Ch R = 1 ,32242   ,1267,1267,1267
BEGIN DESCRIPTION:
Mapping XS a8c21de2
END DESCRIPTION:
XS GIS Cut Line= 4
      2531920.17     13449323.58      2531822.52     13447836.99
      2532093.78     13447185.95      2531822.52     13446003.24
#Sta/Elev= 30
  3231.5  123.62  3430.3  121.25  3880.6  119.05  4007.3  117.43    4196  115.41
  4309.9  114.72  4520.7  112.04  4695.3  109.69  4740.2  108.79    4784  105.64
  4940.1    98.5  4941.6    97.5  5000.4    97.5  5001.9    98.5  5005.6   99.69
    5058  100.89  5130.2  110.51  5204.9  118.86  5260.2  124.33    5361  128.31
  5511.4  129.94    5577  129.82  5667.9  131.29  5797.7  130.39  5940.6  130.78
  5978.8  130.02  6069.3  129.27    6155  130.36  6384.9  136.36    6640     136
#Mann= 16 ,-1 , 0
  3231.5      .1       0  3430.3     .07       0  3880.6     .12       0
  4007.3     .07       0    4196     .05       0  4309.9     .07       0
  4520.7     .05       0  4695.3     .12       0    4784     .05       0
  4940.1     .05       0  5001.9     .05       0    5058    .033       0
  5204.9     .12       0  5511.4     .05       0  5797.7     .12       0
  5978.8     .05       0
Bank Sta=4940.1,5001.9
XS Rating Curve= 0 ,0
Exp/Cntr=0.3,0.1

Type RM Length L Ch R = 1 ,30975   ,706,706,706
BEGIN DESCRIPTION:
PERDIDO CREEK 26.0
END DESCRIPTION:
XS GIS Cut Line= 3
        2533025.     13449296.99        2533025.       13447825.
      2533093.93     13446603.53
#Sta/Elev= 30
  3589.8  125.46  3685.5  124.95  3784.1  123.92  4091.8  120.29  4481.8  112.29
  4671.8   109.1  4711.8  108.95  4771.8  107.94    4839   104.3  4871.8   102.5
  4931.8  100.05  4940.8      98  4942.3      97  5001.2      97  5002.7      98
  5071.8   98.09    5212  101.57  5362.3  105.89  5506.5  115.88  5512.5  116.59
  5552.6  119.41  5652.7  124.49  5732.9  127.82  5864.3  131.54    5954  132.49
  6033.2  133.32  6053.4  133.93  6151.3  134.57  6237.7  136.23  6285.2  136.77
#Mann= 9 ,-1 , 0
  3589.8     .12       0  3685.5     .07       0  3784.1     .05       0
    4839    .033       0  4940.8     .05       0  5002.7    .033       0
    5954     .07       0  6151.3     .12       0  6237.7     .07       0
Bank Sta=4940.8,5002.7
XS Rating Curve= 0 ,0
Exp/Cntr=0.3,0.1

Type RM Length L Ch R = 1 ,30269   ,733,733,733
BEGIN DESCRIPTION:
PERDIDO CREEK 25.0
END DESCRIPTION:
XS GIS Cut Line= 3
      2533858.53     13449326.74        2533675.       13447675.
       2533635.6     13446395.21
#Sta/Elev= 30
  3337.7  119.84  3386.7  119.72  3510.5  119.69  3739.2  117.45  3890.9   115.8
  4073.9   113.1  4360.4  110.14  4535.7  107.95  4758.1  105.32  4834.3  102.53
  4918.3   98.12  4919.8   97.12  4978.7   97.12  4980.2   98.12  4989.5   98.99
  5074.8  101.74  5259.7  110.58  5349.8  112.67  5449.8  116.36  5539.9  121.28
  5808.5  127.35  5813.5  128.12    5900  130.53  5960.1  131.37  6009.2  132.77
  6019.1  133.05  6060.1  133.23  6119.6  135.02  6220.2  136.86    6280  136.97
#Mann= 13 ,-1 , 0
  3337.7     .12       0  3386.7    .035       0  3739.2     .07       0
  3890.9     .12       0  4360.4    .035       0  4535.7     .12       0
  4834.3    .033       0  4918.3    .033       0  4980.2    .033       0
  5074.8     .12       0  6009.2      .1       0  6019.1     .12       0
  6119.6     .05       0
Bank Sta=4918.3,4980.2
XS Rating Curve= 0 ,0
Exp/Cntr=0.3,0.1

Type RM Length L Ch R = 1 ,29536   ,732,732,732
BEGIN DESCRIPTION:
PERDIDO CREEK 24.0
END DESCRIPTION:
XS GIS Cut Line= 3
      2534549.55     13449459.74        2534375.       13447575.
      2534255.39     13446390.03
#Sta/Elev= 30
  3107.1  116.89  3262.5  114.55    3383  113.95  3483.4  113.79  3537.3  115.01
  3774.7  114.66  4256.7  109.77  4416.5  106.58  4515.9  105.22  4632.9  103.84
  4758.9  101.87  4914.2   98.03  4915.7   97.03  4974.7   97.03  4976.2   98.03
  5047.4   99.56  5116.9  103.44  5140.6  104.82  5252.5  115.16  5352.6  121.79
  5447.6  123.74  5452.6  124.44  5578.2  124.62  5605.5  124.18  5642.6  123.44
  5647.7  124.07  5683.4  124.14  5742.7  122.64  6004.3  129.28  6190.9  133.55
#Mann= 11 ,-1 , 0
  3107.1     .12       0  4416.5    .035       0  4515.9     .12       0
  4632.9    .033       0  4914.2    .033       0  4976.2    .033       0
  5116.9     .12       0  5578.2     .07       0  5605.5     .12       0
  5642.6     .07       0  6004.3     .05       0
Bank Sta=4914.2,4976.2
XS Rating Curve= 0 ,0
Exp/Cntr=0.3,0.1

Type RM Length L Ch R = 1 ,28804   ,443,443,443
BEGIN DESCRIPTION:
PERDIDO CREEK 23.0
END DESCRIPTION:
XS GIS Cut Line= 3
        2535075.     13449537.39        2535075.       13447675.
      2534727.75     13446430.53
#Sta/Elev= 30
  3137.7  120.61  3290.1  119.05  3390.1  115.72  3550.1  112.76  3910.1  109.05
  4070.1  108.92  4140.1  107.13  4270.1  106.78  4560.1  103.87  4633.6   101.4
  4660.1   100.4  4760.1   99.32    4869      98  4870.5      97  4929.6      97
  4931.1      98  5056.5      98  5103.9   99.27  5169.5  100.75  5203.6  102.71
  5259.6  104.61  5316.5  105.07  5350.7  106.49  5418.4  107.61  5542.4  110.27
  5613.2  113.12  5723.6  117.66  5910.1  123.54  6170.1  128.73  6292.1  130.03
#Mann= 7 ,-1 , 0
  3137.7     .12       0  4633.6    .035       0  4760.1    .035       0
    4869    .033       0  5103.9    .033       0  5418.4    .035       0
  5613.2     .07       0
Bank Sta=4760.1,5103.9
XS Rating Curve= 0 ,0
Exp/Cntr=0.3,0.1

Type RM Length L Ch R = 1 ,28361   ,780,780,780
BEGIN DESCRIPTION:
Mapping XS a0781c2f
END DESCRIPTION:
XS GIS Cut Line= 3
      2535294.74     13450679.86      2535533.45     13447761.03
      2535284.22      13446428.2
#Sta/Elev= 30
  1985.9  130.46  2211.1  129.16    2429  126.49  2597.9  125.14  2710.9  124.73
    2974  121.94  3561.6  116.53    3797  115.33  3924.3  112.98  3949.4  112.53
  4067.7  111.72  4290.6  112.34  4368.7  113.53  4389.4  112.57  4504.1  108.34
  4659.7  100.69  4747.2  103.59  4795.4  101.94  4850.3    99.4  4860.3      94
  5084.1      94  5103.7      94  5144.4   99.97    5151  100.22  5255.5  106.03
  5285.9  106.68  5551.4     112  5790.2  120.29  6075.5  128.47  6270.4  132.23
#Mann= 20 ,-1 , 0
  1985.9     .12       0  2211.1    .035       0    2429     .12       0
  2597.9    .035       0  2710.9     .12       0    2974     .07       0
  3561.6    .035       0    3797     .12       0  3924.3    .035       0
  3949.4     .12       0  4290.6     .07       0  4389.4     .12       0
  4795.4    .033       0  4850.3    .033       0  4860.3     .03       0
  5084.1    .035       0  5144.4    .035       0    5151     .07       0
  5285.9    .035       0  5790.2     .07       0
Bank Sta=4850.3,5144.4
XS Rating Curve= 0 ,0
Exp/Cntr=0.3,0.1

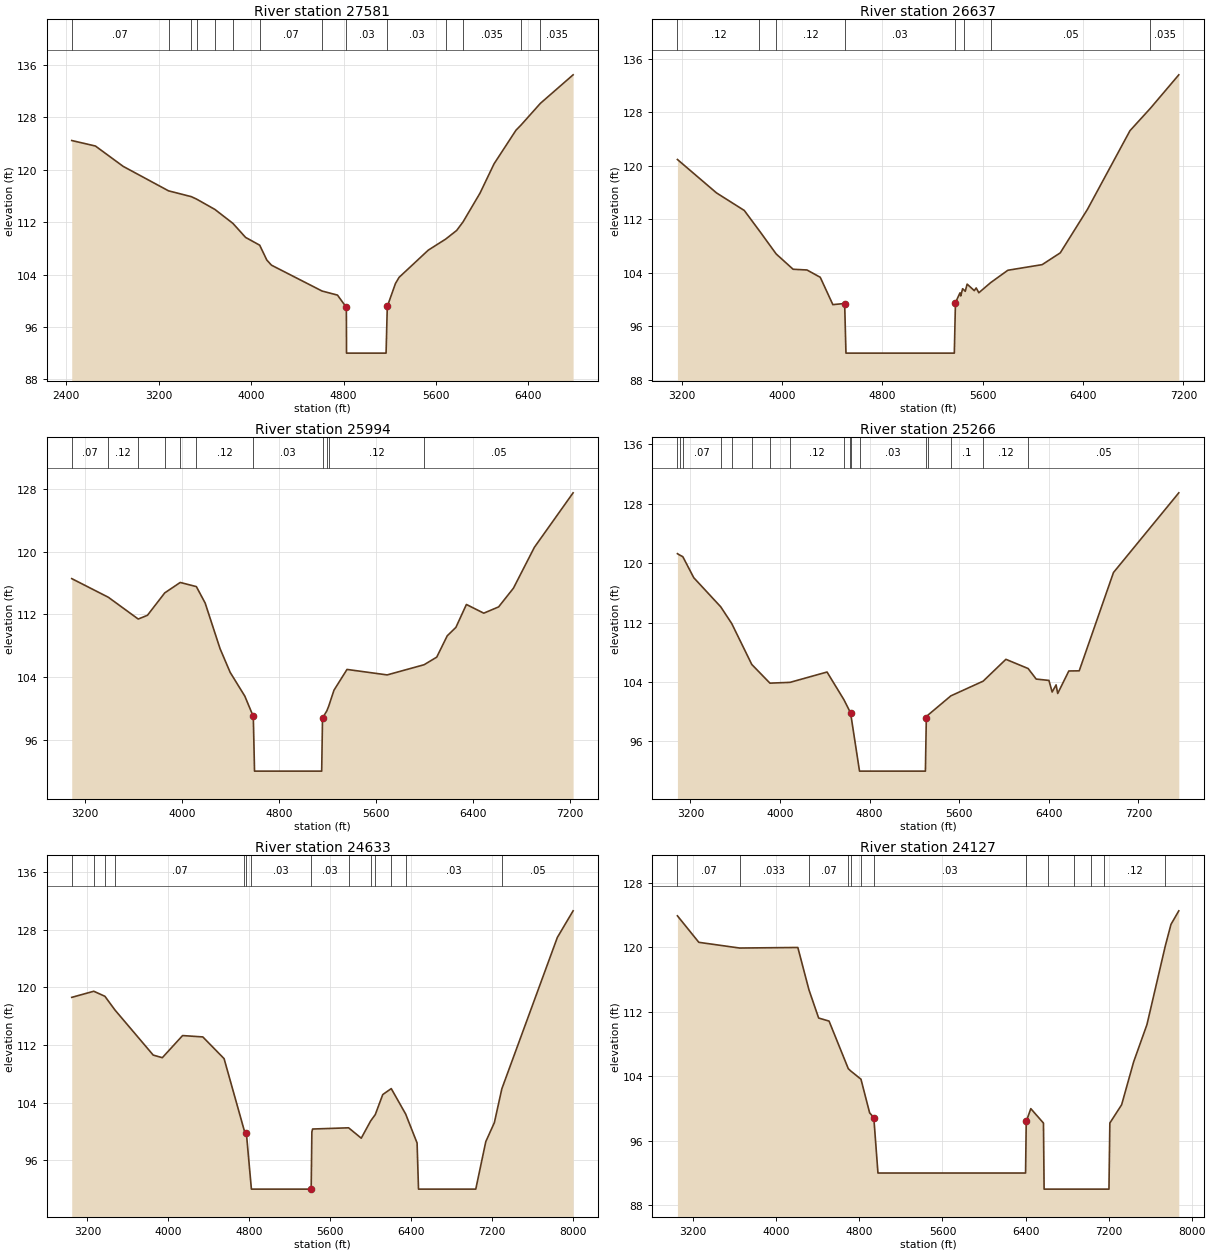
Type RM Length L Ch R = 1 ,27581   ,944,944,944
BEGIN DESCRIPTION:
Mapping XS d32992a5
END DESCRIPTION:
XS GIS Cut Line= 3
      2536043.44     13450419.44      2536238.75     13447902.09
       2535664.2     13446178.45
#Sta/Elev= 30
  2446.4  124.46  2651.5  123.62  2892.2  120.51  3284.4  116.78  3481.8  115.89
  3528.2  115.51    3686  113.94  3842.2  111.81  3951.8  109.67  4074.1  108.48
  4135.9  106.21    4176  105.43  4614.3  101.48  4747.7  100.86  4824.6   98.99
  4826.1      92  5168.5      92  5179.1   99.12  5249.8  102.63  5281.4  103.57
  5534.4  107.73  5684.8  109.41  5779.9  110.73  5835.2  112.04  5982.4  116.44
  6103.6   120.9  6293.3  126.03  6337.1  126.82  6505.1  130.14  6788.2  134.49
#Mann= 14 ,-1 , 0
  2446.4     .07       0  3284.4    .035       0  3481.8     .07       0
  3528.2     .05       0    3686     .07       0  3842.2     .05       0
  4074.1     .07       0  4614.3     .07       0  4824.6     .03       0
  5179.1     .03       0  5684.8     .05       0  5835.2    .035       0
  6337.1     .05       0  6505.1    .035       0
Bank Sta=4824.6,5179.1
XS Rating Curve= 0 ,0
Exp/Cntr=0.3,0.1

Type RM Length L Ch R = 1 ,26637   ,643,643,643
BEGIN DESCRIPTION:
PERDIDO CREEK 20.0
END DESCRIPTION:
XS GIS Cut Line= 3
      2537638.38     13449784.54        2537125.       13448025.
      2535925.02     13446225.03
#Sta/Elev= 30
  3167.1  120.95  3478.3  115.96    3700  113.33  3821.1  110.27  3954.1  106.83
  4089.1  104.54  4199.9  104.43  4305.5  103.34    4406   99.25    4500   99.42
  4510.4      92  5374.1      92  5383.1   99.54  5419.1  101.01  5425.2  100.55
  5440.2  101.63  5451.1  101.45  5461.2  101.24  5476.2  102.32  5533.3  101.34
  5548.3  101.75  5569.4  101.03  5665.1  102.56  5800.7  104.39  6074.2  105.23
  6218.4  106.99  6434.7  113.48  6774.2  125.26  6936.1  128.59  7163.3  133.61
#Mann= 8 ,-1 , 0
  3167.1     .12       0  3821.1     .07       0  3954.1     .12       0
    4500     .03       0  5383.1     .03       0  5451.1     .12       0
  5665.1     .05       0  6936.1    .035       0
Bank Sta=4500,5383.1
XS Rating Curve= 0 ,0
Exp/Cntr=0.3,0.1

Type RM Length L Ch R = 1 ,25994   ,728,728,728
BEGIN DESCRIPTION:
PERDIDO CREEK 19.0
END DESCRIPTION:
XS GIS Cut Line= 3
      2537967.85     13449807.34        2537825.       13448025.
      2536489.09     13446096.57
#Sta/Elev= 30
  3089.5  116.57  3391.4  114.19  3637.9  111.41  3713.8  111.89  3856.5  114.75
  3984.2  116.08  4117.2  115.55  4189.7  113.45  4312.5  107.63    4396   104.6
  4516.4  101.58  4586.6   98.98  4596.7      92  5150.5      92  5157.3   98.77
  5192.8   99.69  5208.5   100.3  5251.8  102.33  5359.3  104.98  5690.3  104.28
  5994.9  105.58  6099.1  106.55  6185.6  109.27  6257.2  110.35  6343.7  113.27
  6486.9  112.16  6609.2  112.96  6731.5  115.35  6904.4  120.57  7223.5  127.52
#Mann= 11 ,-1 , 0
  3089.5     .07       0  3391.4     .12       0  3637.9     .07       0
  3856.5     .12       0  3984.2     .07       0  4117.2     .12       0
  4586.6     .03       0  5157.3     .03       0  5192.8      .1       0
  5208.5     .12       0  5994.9     .05       0
Bank Sta=4586.6,5157.3
XS Rating Curve= 0 ,0
Exp/Cntr=0.3,0.1

Type RM Length L Ch R = 1 ,25266   ,633,633,633
BEGIN DESCRIPTION:
PERDIDO CREEK 18.0
END DESCRIPTION:
XS GIS Cut Line= 3
        2538475.      13449741.1        2538475.       13447825.
      2536874.97     13445824.96
#Sta/Elev= 30
  3083.9  121.27  3103.5  121.09  3132.2  120.86    3230  118.03  3470.4  114.12
    3569  111.86  3747.8  106.36  3910.2  103.84  4089.9  103.95    4420  105.34
  4571.3   101.6    4629   99.87    4630   99.86    4710      92  5298.5      92
  5306.6   99.18    5322   99.55  5525.6  102.13  5814.1  104.11  6017.3  107.05
  6215.8  105.81  6287.8  104.39  6401.5  104.21  6430.3  102.65  6465.5  103.61
  6479.9  102.45  6579.2  105.48    6672   105.5  6977.8  118.73  7561.3  129.46
#Mann= 17 ,-1 , 0
  3083.9     .07       0  3103.5     .12       0  3132.2     .07       0
  3470.4    .035       0    3569     .07       0  3747.8     .12       0
  3910.2     .07       0  4089.9     .12       0  4571.3     .07       0
    4629     .07       0    4630     .05       0    4710     .03       0
  5306.6     .03       0    5322     .07       0  5525.6      .1       0
  5814.1     .12       0  6215.8     .05       0
Bank Sta=4630,5306.6
XS Rating Curve= 0 ,0
Exp/Cntr=0.3,0.1

Type RM Length L Ch R = 1 ,24633   ,506,506,506
BEGIN DESCRIPTION:
PERDIDO CREEK 17.0
END DESCRIPTION:
XS GIS Cut Line= 3
      2539048.97     13449600.08        2539075.       13447475.
      2537074.97     13445474.97
#Sta/Elev= 30
    3045  118.61  3262.7  119.46  3372.8  118.76  3471.4  116.87  3850.1   110.6
  3940.1  110.24  4140.2  113.31  4340.2  113.12  4550.2  110.11  4749.2  100.16
  4770.2   99.81  4820.2      92  5410.7      92  5417.7   99.94  5424.8  100.34
  5780.5  100.51  5905.6   99.07  5998.7  101.47    6044  102.34  6117.8  105.12
  6201.9  105.95    6344  102.43  6457.2    98.4  6471.3      92    7037      92
    7136   98.59  7220.8  101.23  7294.5  105.92  7843.1  126.93  7998.7  130.62
#Mann= 14 ,-1 , 0
    3045     .12       0  3262.7     .07       0  3372.8    .035       0
  3471.4     .07       0  4749.2     .12       0  4770.2     .05       0
  4820.2     .03       0  5410.7     .03       0  5780.5     .07       0
  5998.7     .07       0    6044    .035       0  6201.9     .07       0
    6344     .03       0  7294.5     .05       0
Bank Sta=4770.2,5410.7
XS Rating Curve= 0 ,0
Exp/Cntr=0.3,0.1

Type RM Length L Ch R = 1 ,24127   ,991,991,991
BEGIN DESCRIPTION:
Mapping XS 13882e50
END DESCRIPTION:
XS GIS Cut Line= 4
      2539396.19     13449372.18       2539548.1     13447071.85
       2539461.3     13446572.72      2538300.29     13444923.44
#Sta/Elev= 30
  3047.5  123.93  3253.6  120.64  3646.5  119.93  4207.2     120  4314.1  114.75
  4407.6  111.24  4507.9  110.86    4693  104.96  4716.4  104.67  4815.1  103.65
  4898.7   99.47  4938.8   98.89  4978.9      92  6400.6      92    6407    98.4
  6451.1   99.99    6573    98.2  6579.1      90  6619.2      90    6867      90
  7030.3      90  7153.3      90  7203.7      90  7212.4   98.21  7325.6  100.47
  7441.5   105.8  7569.5  110.42  7746.7  120.21  7801.1  122.87  7876.4  124.55
#Mann= 13 ,-1 , 0
  3047.5     .07       0  3646.5    .033       0  4314.1     .07       0
    4693     .12       0  4716.4     .07       0  4815.1    .033       0
  4938.8     .03       0    6407     .03       0  6619.2    .033       0
    6867    .035       0  7030.3    .033       0  7153.3     .12       0
  7746.7     .05       0
Bank Sta=4938.8,6407
XS Rating Curve= 0 ,0
Exp/Cntr=0.3,0.1