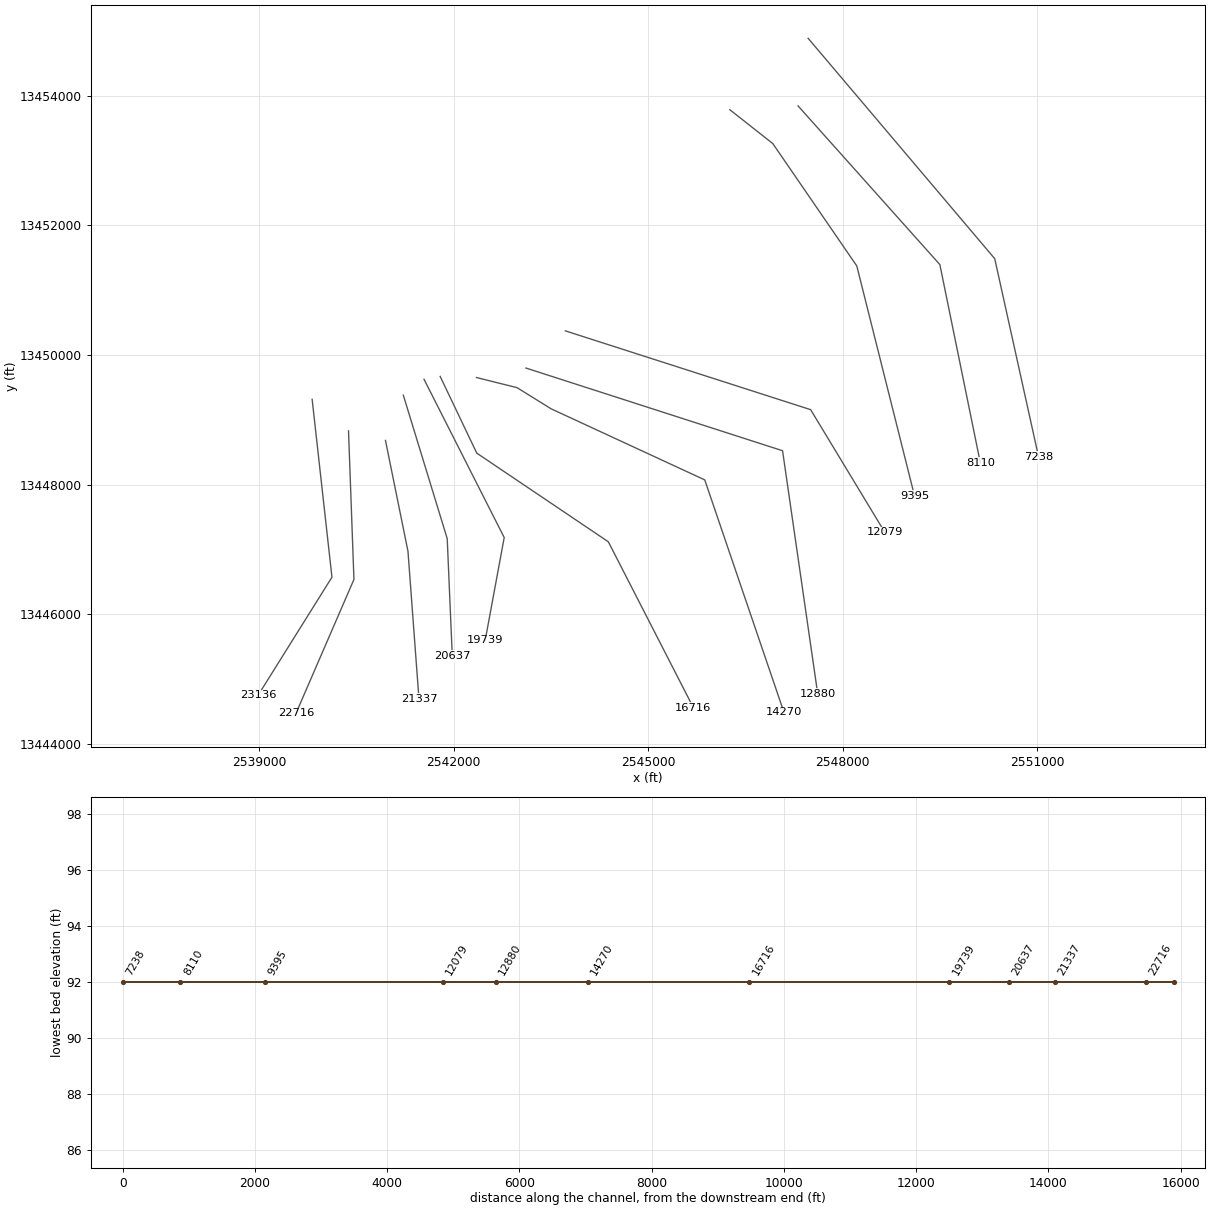
HEC-RAS study PERDIDO CREEK.prj: PERDIDO CREEK Base Level Engineering

--- PERDIDO CREEK.g01 (geometry) --- (continued)

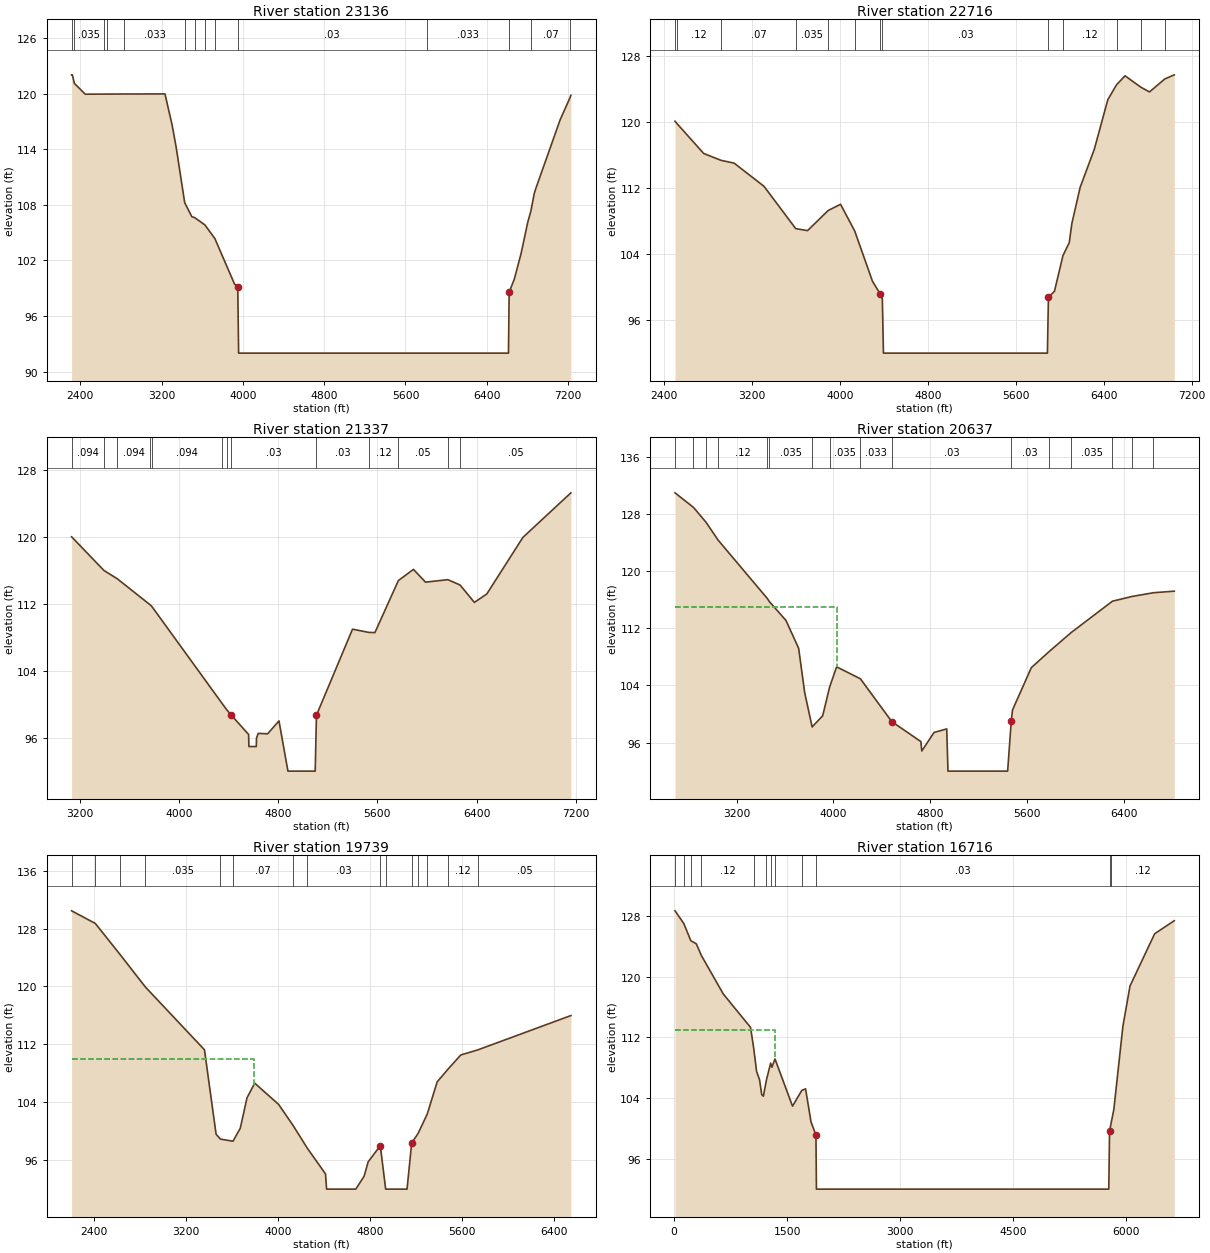
Type RM Length L Ch R = 1 ,23136   ,420,420,420
BEGIN DESCRIPTION:
PERDIDO CREEK 16.0
END DESCRIPTION:
XS GIS Cut Line= 3
      2539819.36     13449317.99        2540125.       13446575.
      2538983.94     13444749.92
#Sta/Elev= 30
  2315.5  122.04  2322.4  122.04  2342.6  121.12  2449.3  119.95  2636.6  119.96
    2665  119.96  2834.4  119.97  3234.1  119.98  3304.6   116.6  3344.8  114.18
    3428  108.24    3498  106.73    3527  106.62  3625.9  105.85  3724.8  104.37
  3918.4   99.45  3950.1   99.17  3958.6      92  5807.8      92  6613.7      92
  6620.4   98.58  6671.5     100  6738.4  102.78  6802.3  106.07    6834  107.33
  6868.1  109.26  6881.4  109.73  7121.9  117.18  7219.8  119.59  7227.9  119.83
#Mann= 14 ,-1 , 0
  2315.5     .12       0  2342.6    .035       0  2636.6    .033       0
    2665    .035       0  2834.4    .033       0    3428    .035       0
    3527     .12       0  3625.9     .12       0  3724.8     .07       0
  3950.1     .03       0  5807.8    .033       0  6620.4    .033       0
    6834     .07       0  7219.8     .12       0
Bank Sta=3950.1,6620.4
XS Rating Curve= 0 ,0
Exp/Cntr=0.3,0.1

Type RM Length L Ch R = 1 ,22716   ,1379,1379,1379
BEGIN DESCRIPTION:
Mapping XS a0a3b108
END DESCRIPTION:
XS GIS Cut Line= 3
      2540380.46     13448830.33      2540464.12     13446540.14
        2539570.     13444474.13
#Sta/Elev= 30
  2498.4  120.08  2512.3  119.85  2759.4  116.17  2916.4  115.34  3036.4     115
  3308.5  112.19  3596.9  107.07  3704.5  106.83  3892.7  109.27  4004.7  110.02
  4134.1  106.77  4294.9  100.71    4365   99.17    4385   98.57    4395      92
    5887      92  5896.2   98.78  5950.7   99.47  6028.7  103.82  6085.7  105.37
  6109.2  107.68  6185.1  112.08  6313.5  116.67  6436.3  122.67  6515.8  124.48
  6593.6  125.57  6737.4  124.19  6815.8  123.62    6955  125.19  7041.3  125.69
#Mann= 13 ,-1 , 0
  2498.4    .033       0  2512.3     .12       0  2916.4     .07       0
  3596.9    .035       0  3892.7     .07       0  4134.1    .035       0
    4365    .035       0    4385     .03       0  5896.2     .03       0
  6028.7     .12       0  6515.8     .07       0  6737.4    .035       0
    6955     .07       0
Bank Sta=4365,5896.2
XS Rating Curve= 0 ,0
Exp/Cntr=0.3,0.1

Type RM Length L Ch R = 1 ,21337   ,700,700,700
BEGIN DESCRIPTION:
Mapping XS 4585513a
END DESCRIPTION:
XS GIS Cut Line= 3
      2540950.47     13448683.62      2541297.45     13446974.17
      2541466.88     13444698.98
#Sta/Elev= 30
  3134.8  120.01  3395.2  115.99  3502.6     115  3770.6  111.85  3784.4  111.63
  4343.8  100.18  4384.9   99.35  4419.1   98.75  4561.9   96.38  4564.2   94.94
  4623.8   94.94  4625.3   95.94  4639.5   96.51    4715   96.46  4806.8      98
  4879.1      92  5098.9      92  5108.9   98.68  5399.7  108.97  5528.6  108.59
  5580.2  108.56  5769.5  114.78  5891.1  116.12  5988.5  114.59  6168.3  114.89
    6267  114.25  6382.4  112.17  6482.7  113.18  6773.5  119.94  7160.6  125.27
#Mann= 13 ,-1 , 0
  3134.8    .094       0  3395.2     .12       0  3502.6    .094       0
  3770.6    .063       0  3784.4    .094       0  4343.8    .035       0
  4384.9    .033       0  4419.1     .03       0  5108.9     .03       0
  5528.6     .12       0  5769.5     .05       0  6168.3    .035       0
    6267     .05       0
Bank Sta=4419.1,5108.9
XS Rating Curve= 0 ,0
Exp/Cntr=0.3,0.1

Type RM Length L Ch R = 1 ,20637   ,898,898,898
BEGIN DESCRIPTION:
Mapping XS e8ac1940
END DESCRIPTION:
XS GIS Cut Line= 3
      2541225.74     13449382.08      2541902.81     13447168.59
      2541980.91      13445359.3
#Sta/Elev= 30
  2691.6  130.94  2844.4   128.9  2946.7  126.85  3048.9   124.3  3454.8  116.15
  3471.8  115.71  3608.8  113.08  3713.4  109.18  3763.2  102.98  3824.9   98.18
  3912.1   99.75  3969.3  103.77  4027.1  106.59  4223.7  104.92  4482.9   98.93
  4722.9   96.14    4731   94.82  4832.3   97.41  4936.9   97.91  4947.3      92
  5440.3      92  5470.3   99.01  5480.4  100.55  5636.2  106.48  5781.4   108.7
  5963.9  111.37  6306.5  115.78  6471.6  116.45  6644.4  116.96  6817.3  117.18
#Mann= 16 ,-1 , 0
  2691.6     .07       0  2844.4    .063       0  2946.7    .094       0
  3048.9     .12       0  3454.8    .063       0  3471.8    .035       0
  3824.9    .063       0  3969.3    .035       0  4223.7    .033       0
  4482.9     .03       0  5470.3     .03       0  5781.4     .05       0
  5963.9    .035       0  6306.5     .07       0  6471.6     .05       0
  6644.4      .1       0
#XS Ineff= 2 , 0
       0  4027.1     115               0
Permanent Ineff=
       F       F
Bank Sta=4482.9,5470.3
XS Rating Curve= 0 ,0
Exp/Cntr=0.3,0.1

Type RM Length L Ch R = 1 ,19739   ,3023,3023,3023
BEGIN DESCRIPTION:
Mapping XS 61289924
END DESCRIPTION:
XS GIS Cut Line= 3
      2541544.76     13449627.31      2542781.72     13447185.95
      2542488.75     13445601.75
#Sta/Elev= 30
  2201.7  130.45  2407.7  128.71  2625.7  124.37  2844.7  119.91  3358.6  111.25
  3459.8   99.59  3497.9   98.91  3606.9   98.62  3670.4  100.41  3728.9  104.61
  3796.2  106.64  4004.5   103.7  4130.5  100.79  4255.3   97.63  4412.7    94.1
  4422.1      92  4676.2      92    4749   93.79  4784.1   95.77  4889.8      98
  4936.6      92  5122.6      92  5163.1   98.37  5219.4   99.71  5298.6  102.37
  5384.9  106.81  5480.3  108.59  5590.4  110.53    5743  111.26  6549.6  115.98
#Mann= 15 ,-1 , 0
  2201.7     .12       0  2407.7    .035       0  2625.7    .094       0
  2844.7    .035       0  3497.9     .12       0  3606.9     .07       0
  4130.5    .035       0  4255.3     .03       0  4889.8     .03       0
  4936.6     .03       0  5163.1     .03       0  5219.4     .12       0
  5298.6     .05       0  5480.3     .12       0    5743     .05       0
#XS Ineff= 2 , 0
       0  3787.4     110               0
Permanent Ineff=
       F       F
Bank Sta=4889.8,5163.1
XS Rating Curve= 0 ,0
Exp/Cntr=0.3,0.1

Type RM Length L Ch R = 1 ,16716   ,2446,2446,2446
BEGIN DESCRIPTION:
Mapping XS 85ed3c38
END DESCRIPTION:
XS GIS Cut Line= 4
      2541794.32     13449670.72      2542358.54     13448488.03
      2544387.62     13447120.84      2545700.27     13444560.62
#Sta/Elev= 30
    11.4  128.66   127.8     127   221.3  124.73   294.7  124.31   362.8  122.76
   653.2   117.7  1014.9  113.31  1056.1  110.64  1095.5  107.51  1135.3  106.39
  1163.5  104.45  1186.2  104.25  1225.5  106.35  1282.5   108.6  1299.7  108.05
  1339.9  109.15  1572.8  102.93  1696.6  105.01  1746.7  105.21  1818.6  100.86
  1884.2   99.12  1890.6      92  5775.4      92  5785.6   99.64  5801.7  100.46
  5842.8  102.51  5963.2  113.47  6057.6  118.76  6384.9  125.64  6645.6  127.36
#Mann= 12 ,-1 , 0
    11.4     .12       0   127.8    .035       0   221.3     .07       0
   362.8     .12       0  1056.1    .035       0  1225.5     .07       0
  1282.5     .12       0  1339.9     .07       0  1696.6     .07       0
  1884.2     .03       0  5785.6     .03       0  5801.7     .12       0
#XS Ineff= 2 , 0
       0  1335.9     113               0
Permanent Ineff=
       F       F
Bank Sta=1884.2,5785.6
XS Rating Curve= 0 ,0
Exp/Cntr=0.3,0.1

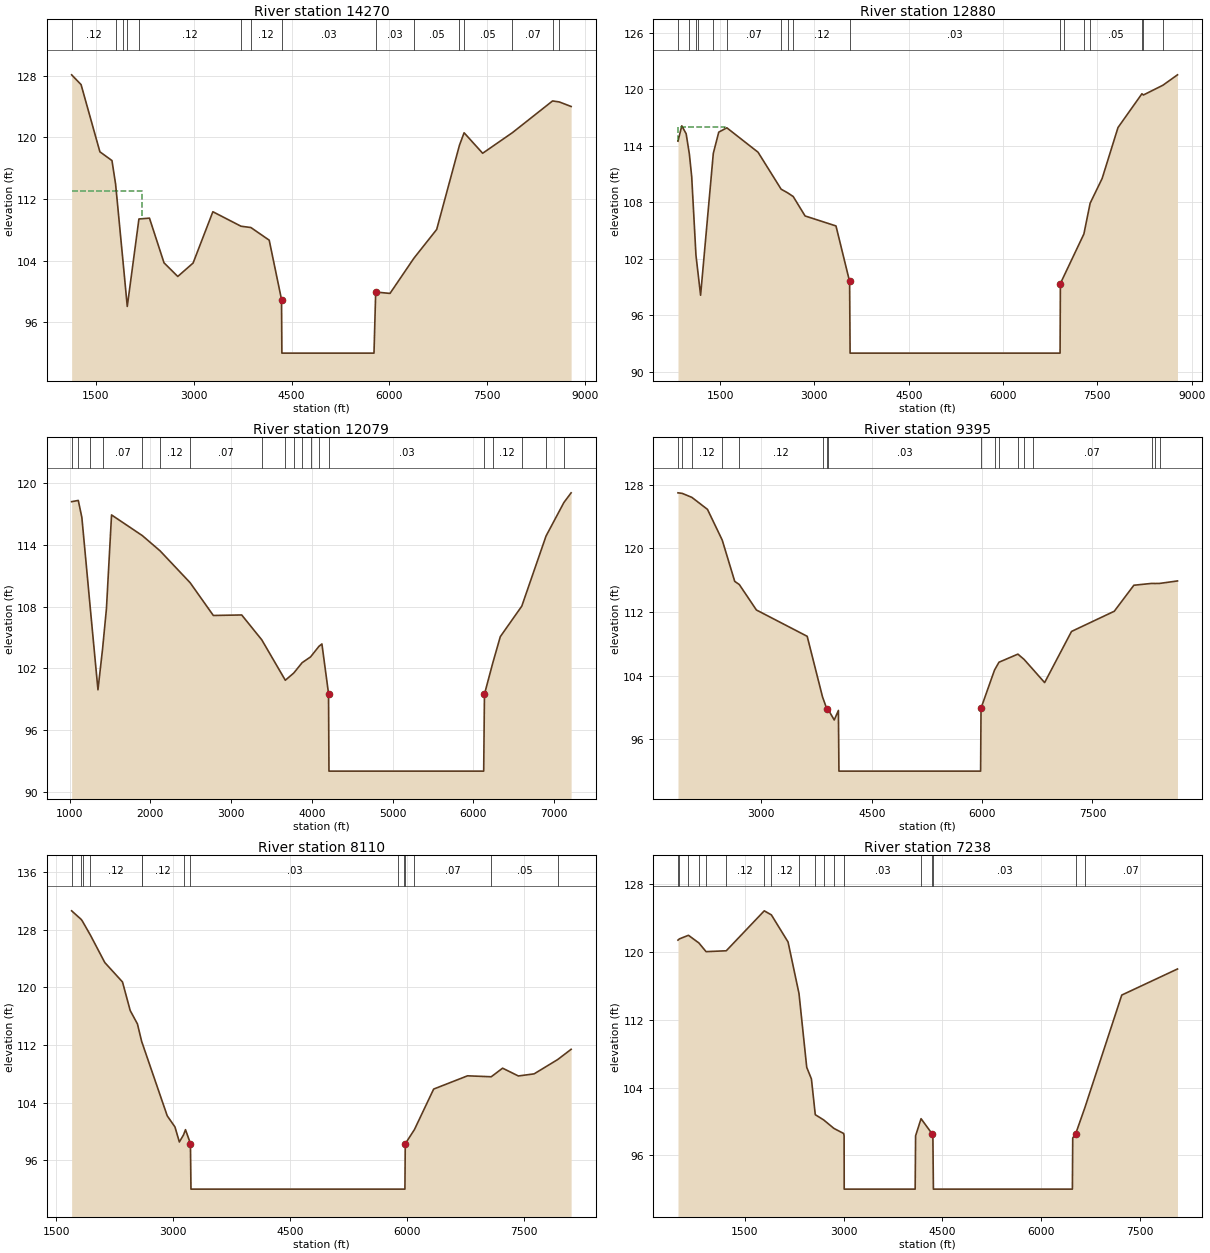
Type RM Length L Ch R = 1 ,14270   ,1390,1390,1390
BEGIN DESCRIPTION:
PERDIDO CREEK 9.0
END DESCRIPTION:
XS GIS Cut Line= 5
      2542354.94     13449653.94      2542980.77     13449497.44
      2543503.35     13449172.45        2545875.       13448075.
      2547096.05     13444491.57
#Sta/Elev= 30
  1126.3  128.12    1271  126.85  1559.6  118.13  1744.8  116.99  1800.7  113.92
    1915  103.82  1979.4   98.06  2158.1  109.41  2319.8  109.52  2542.9  103.72
  2753.8  101.95  2988.5  103.69  3292.1  110.35  3723.6  108.47  3874.9   108.3
  4155.9  106.66  4344.8   98.96  4350.3      92  5762.8      92  5788.9   99.93
  6008.3   99.75    6375  104.32  6724.1  108.05  7073.7  118.99  7144.6   120.6
  7429.2  117.94  7886.5  120.62    8501  124.73  8604.2   124.6  8785.8  124.01
#Mann= 15 ,-1 , 0
  1126.3     .12       0  1800.7     .07       0    1915     .12       0
  1979.4     .07       0  2158.1     .12       0  3723.6     .07       0
  3874.9     .12       0  4344.8     .03       0  5788.9     .03       0
    6375     .05       0  7073.7    .063       0  7144.6     .05       0
  7886.5     .07       0    8501     .05       0  8604.2     .07       0
#XS Ineff= 2 , 0
       0    2200     113               0
Permanent Ineff=
       F       F
Bank Sta=4344.8,5788.9
XS Rating Curve= 0 ,0
Exp/Cntr=0.3,0.1

Type RM Length L Ch R = 1 ,12880   ,801,801,801
BEGIN DESCRIPTION:
PERDIDO CREEK 8.0
END DESCRIPTION:
XS GIS Cut Line= 3
      2543117.47     13449800.16        2547075.       13448525.
      2547616.75     13444778.96
#Sta/Elev= 30
   831.3  114.48   891.7  116.11   961.1  115.27  1012.8  113.09  1049.3  110.72
    1117  102.39  1149.1  100.54  1190.8   98.14  1392.9  113.19  1479.4  115.44
    1608   115.9  2104.4  113.31  2471.5  109.39  2575.7     109  2663.7  108.61
  2852.3  106.55  3343.8  105.49  3560.3    99.6  3568.2      92  6907.2      92
  6912.3   99.38  6975.4  100.27    7286  104.64  7385.2   107.9  7575.8  110.52
  7828.4  115.93  8208.7  119.51  8232.3  119.38  8543.1  120.42  8774.2  121.52
#Mann= 17 ,-1 , 0
   831.3     .12       0  1012.8     .07       0    1117     .12       0
  1149.1     .07       0  1392.9     .12       0    1608     .07       0
  2471.5    .035       0  2575.7     .07       0  2663.7     .12       0
  3560.3     .03       0  6912.3     .03       0  6975.4     .05       0
    7286    .035       0  7385.2     .05       0  8208.7    .035       0
  8232.3     .05       0  8543.1     .07       0
#XS Ineff= 2 , 0
       0  1586.1  115.95               0
Permanent Ineff=
       F       F
Bank Sta=3560.3,6912.3
XS Rating Curve= 0 ,0
Exp/Cntr=0.3,0.1

Type RM Length L Ch R = 1 ,12079   ,2684,2684,2684
BEGIN DESCRIPTION:
Mapping XS 251f3db3
END DESCRIPTION:
XS GIS Cut Line= 3
       2543724.6     13450373.93      2547508.05     13449158.45
      2548652.07     13447266.67
#Sta/Elev= 30
  1026.1  118.21  1108.3  118.33  1152.6  116.68  1256.5  107.89  1352.1   99.91
  1409.2   103.9  1457.2  107.82  1520.2  116.92  1901.2  114.91  2120.6  113.43
    2493  110.33  2780.6  107.14  3131.9  107.19  3380.5  104.77  3671.9  100.84
  3776.1  101.54  3880.3  102.55  3984.4  103.11  4088.6  104.14    4125  104.37
    4207   99.55  4212.3      92  6128.2      92  6137.6   99.48  6241.7  102.55
  6333.8  105.08    6600  108.05  6900.2  114.87  7121.5  118.13  7210.8  119.07
#Mann= 19 ,-1 , 0
  1026.1     .12       0  1108.3     .07       0  1256.5    .033       0
  1409.2     .07       0  1901.2     .12       0  2120.6     .12       0
    2493     .07       0  3380.5     .12       0  3671.9     .12       0
  3776.1     .07       0  3880.3     .12       0  3984.4    .033       0
  4088.6     .07       0    4207     .03       0  6137.6     .03       0
  6241.7     .12       0    6600     .05       0  6900.2    .035       0
  7121.5    .035       0
#XS Ineff= 2 , 0
       0  1520.2  116.92               0
Permanent Ineff=
       F       F
Bank Sta=4207,6137.6
XS Rating Curve= 0 ,0
Exp/Cntr=0.3,0.1

Type RM Length L Ch R = 1 ,9395    ,1285,1285,1285
BEGIN DESCRIPTION:
PERDIDO CREEK 5.0
END DESCRIPTION:
XS GIS Cut Line= 4
      2546261.47     13453785.11      2546924.79     13453261.98
        2548220.     13451375.01      2549109.99     13447829.92
#Sta/Elev= 30
  1866.5  126.99    1924  126.92  2054.9  126.42  2267.2  124.91  2467.7  121.05
  2637.6  115.86  2699.8  115.46  2932.3  112.26  3622.5  108.95  3830.9  101.33
  3888.5   99.84  3903.4   99.82    3990   98.43  4046.8   99.63  4053.9      92
  5979.5      92  5985.2   99.92  6168.2   104.7  6228.9  105.69    6486  106.71
    6570  106.05  6687.3  104.83  6849.4  103.13  7214.7  109.56    7796   112.1
  8062.2  115.37    8303   115.6    8350  115.59  8412.6   115.6  8655.1  115.91
#Mann= 17 ,-1 , 0
  1866.5     .07       0    1924     .07       0  2054.9     .12       0
  2467.7     .07       0  2699.8     .12       0  3830.9     .07       0
  3888.5     .05       0  3903.4     .03       0  5985.2     .03       0
  6168.2     .07       0  6228.9     .12       0    6486     .07       0
    6570     .12       0  6687.3     .07       0    8303    .035       0
    8350     .07       0  8412.6     .05       0
Bank Sta=3888.5,5985.2
XS Rating Curve= 0 ,0
Exp/Cntr=0.3,0.1

Type RM Length L Ch R = 1 ,8110    ,872,872,872
BEGIN DESCRIPTION:
Mapping XS 6fa4172b
END DESCRIPTION:
XS GIS Cut Line= 3
       2547313.5     13453843.97      2549501.01     13451396.04
      2550125.61      13448338.1
#Sta/Elev= 30
  1695.6  130.61  1819.1  129.41  1835.8  129.14  1937.1  127.22  2121.1  123.43
  2347.7  120.74  2446.3  116.78  2539.1  114.92  2594.7  112.43  2597.8  112.35
  2921.2  102.17  3020.6  100.62  3076.7   98.54  3130.4   99.53  3155.2  100.25
  3218.7   98.33  3225.5      92  5884.4      92    5952      92  5968.7      92
  5972.9   98.29  6090.5  100.26    6337  105.88  6771.6  107.72  7075.4  107.59
    7221  108.78    7423   107.7    7625  107.99  7927.8  109.98  8099.6   111.4
#Mann= 14 ,-1 , 0
  1695.6     .07       0  1819.1     .12       0  1835.8     .07       0
  1937.1     .12       0  2594.7     .07       0  2597.8     .12       0
  3130.4    .033       0  3218.7     .03       0  5884.4    .033       0
    5952    .033       0  5972.9    .033       0  6090.5     .07       0
  7075.4     .05       0  7927.8     .07       0
Bank Sta=3218.7,5972.9
XS Rating Curve= 0 ,0
Exp/Cntr=0.3,0.1

Type RM Length L Ch R = 1 ,7238    ,943,943,943
BEGIN DESCRIPTION:
Mapping XS 7b236e49
END DESCRIPTION:
XS GIS Cut Line= 3
      2547469.74     13454885.65      2550347.36     13451487.19
      2551024.14     13448428.69
#Sta/Elev= 30
   483.9  121.41   506.4  121.56   642.8  121.98     802  121.07   910.3  120.05
  1216.9  120.15  1794.1  124.87  1902.1  124.39  2155.5  121.19  2321.7   115.1
  2438.9  106.39  2510.4  105.01  2568.9  100.79  2695.2  100.18  2852.3   99.17
  3000.4   98.57  3006.9   98.27  3008.1      92  4085.8      92  4092.4    98.3
  4175.3  100.32  4340.6   98.56  4354.9    98.3  4362.7      92  6473.5      92
  6478.7   98.04  6522.3   98.51  6662.5  101.61  7223.2  114.92  8069.5     118
#Mann= 18 ,-1 , 0
   483.9     .12       0   506.4     .07       0   642.8     .12       0
     802     .12       0   910.3     .07       0  1216.9     .12       0
  1794.1     .07       0  1902.1     .12       0  2321.7     .12       0
  2568.9     .07       0  2695.2     .12       0  2852.3     .07       0
  3008.1     .03       0  4175.3     .05       0  4340.6     .05       0
  4362.7     .03       0  6522.3     .03       0  6662.5     .07       0
Bank Sta=4340.6,6522.3
XS Rating Curve= 0 ,0
Exp/Cntr=0.3,0.1