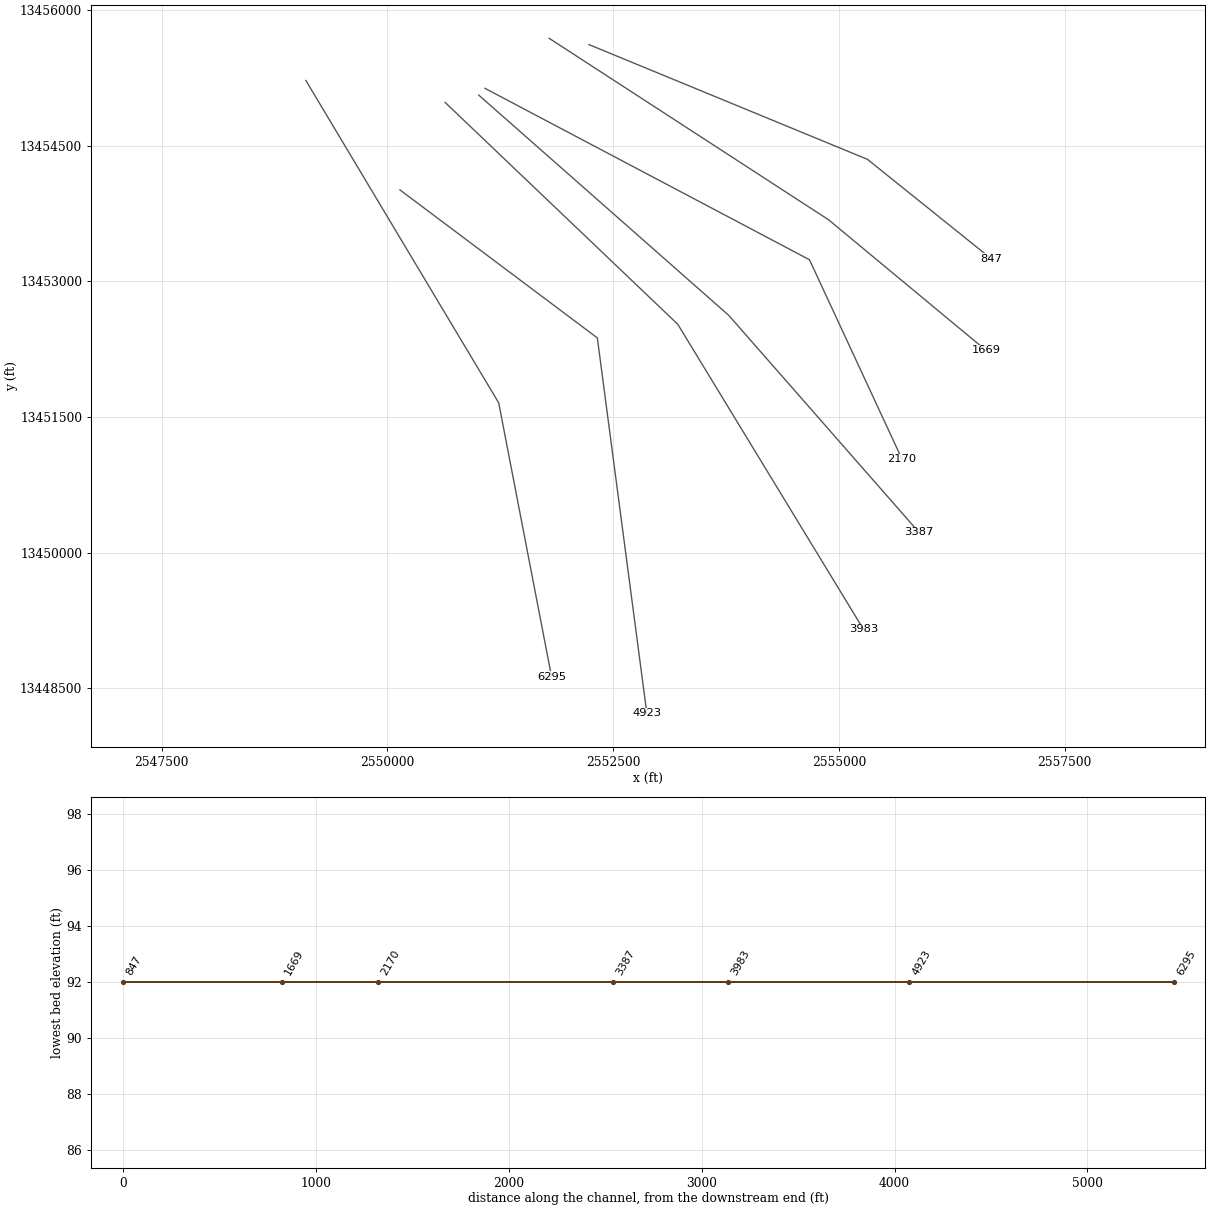
HEC-RAS study PERDIDO CREEK.prj: PERDIDO CREEK Base Level Engineering

--- PERDIDO CREEK.g01 (geometry) --- (continued)

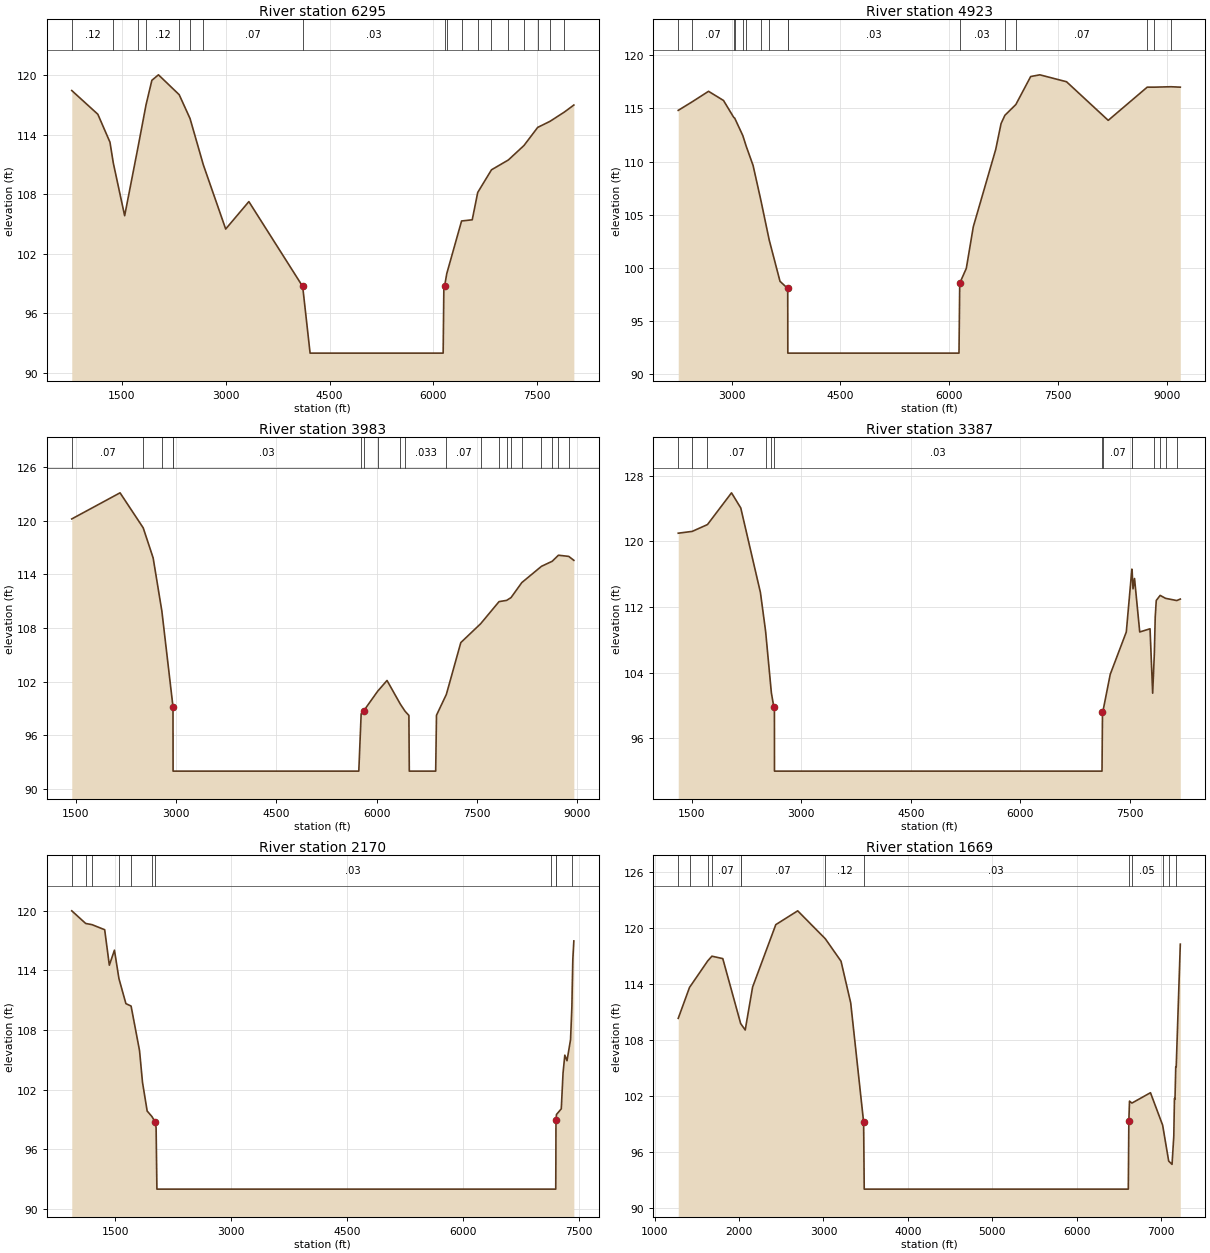
Type RM Length L Ch R = 1 ,6295    ,1372,1372,1372
BEGIN DESCRIPTION:
Mapping XS f98b0734
END DESCRIPTION:
XS GIS Cut Line= 3
      2549097.36     13455224.17      2551232.78     13451656.46
      2551818.72     13448622.58
#Sta/Elev= 30
   779.1  118.43  1155.6  116.04  1330.6  113.23  1379.1  111.12  1542.6  105.83
  1738.4  112.84  1851.5     117  1935.4  119.46  2030.7  120.01    2330  118.01
  2486.6  115.61  2678.9  110.94  3001.1  104.49  3335.6  107.25  4112.5   98.71
  4219.6      92  6140.4      92  6150.5   98.56  6160.7   98.72  6192.1   99.99
  6406.4   105.3  6560.1  105.42  6639.3  108.17    6838  110.45  7081.7  111.44
  7307.5   112.9  7505.4  114.72  7682.9  115.33  7889.6  116.26    8027  116.97
#Mann= 18 ,-1 , 0
   779.1     .12       0  1379.1     .12       0  1738.4     .07       0
  1851.5     .12       0    2330     .07       0  2486.6     .12       0
  2678.9     .07       0  4112.5     .03       0  6160.7     .03       0
  6192.1     .07       0  6406.4     .07       0  6639.3     .05       0
    6838     .07       0  7081.7     .05       0  7307.5     .05       0
  7505.4    .035       0  7682.9     .07       0  7889.6     .12       0
Bank Sta=4112.5,6160.7
XS Rating Curve= 0 ,0
Exp/Cntr=0.3,0.1

Type RM Length L Ch R = 1 ,4923    ,940,940,940
BEGIN DESCRIPTION:
PERDIDO CREEK 4.0
END DESCRIPTION:
XS GIS Cut Line= 3
      2550139.04     13454013.22        2552325.       13452375.
      2552873.33     13448219.52
#Sta/Elev= 30
  2263.8  114.82  2452.8  115.61  2681.7  116.61    2888  115.75  3028.9  114.16
  3042.5  114.09  3154.3  112.45    3201  111.45    3296  109.64  3405.2  106.31
  3518.1  102.64  3667.2   98.75  3773.5   98.08  3774.9      92  6135.3      92
  6145.4   98.57  6236.2   99.97  6332.6  103.88  6641.8  111.15  6715.4  113.58
  6767.7  114.35  6919.2  115.37  7123.8     118  7250.2  118.16    7618  117.51
    8193  113.88  8730.4     117  8829.6     117  9057.5  117.04    9187     117
#Mann= 16 ,-1 , 0
  2263.8     .12       0  2452.8     .07       0  3028.9     .12       0
  3042.5     .07       0  3154.3     .12       0    3201     .07       0
  3405.2     .12       0  3518.1    .033       0  3773.5    .033       0
  3774.9     .03       0  6145.4     .03       0  6767.7     .12       0
  6919.2     .07       0  8730.4    .035       0  8829.6     .05       0
  9057.5     .07       0
Bank Sta=3773.5,6145.4
XS Rating Curve= 0 ,0
Exp/Cntr=0.3,0.1

Type RM Length L Ch R = 1 ,3983    ,596,596,596
BEGIN DESCRIPTION:
Mapping XS 1900319d
END DESCRIPTION:
XS GIS Cut Line= 3
      2550639.82     13454981.06      2553215.94     13452525.82
      2555271.91     13449149.71
#Sta/Elev= 30
  1439.9  120.21  2162.3  123.13    2509  119.21  2657.4  115.85    2788  109.89
  2954.3    99.2  2955.8      92  5734.2      92  5769.6   98.42  5807.5   98.74
  6015.6  100.93  6156.4  102.14  6356.2   99.49  6427.4   98.69  6483.8   98.23
  6489.6      92  6884.6      92  6896.4   98.25    7044  100.58  7260.5  106.38
  7557.5  108.49  7832.3  110.96  7945.9   111.1  8011.7  111.41    8173  113.09
    8467  114.91  8627.1  115.47    8721  116.15  8875.3  116.02  8951.5  115.58
#Mann= 20 ,-1 , 0
  1439.9     .07       0    2509     .07       0    2788    .033       0
  2954.3    .033       0  2955.8     .03       0  5769.6     .05       0
  5807.5     .05       0  6015.6    .035       0  6356.2     .05       0
  6427.4    .033       0    7044     .07       0  7557.5     .07       0
  7832.3    .035       0  7945.9     .07       0  8011.7    .035       0
    8173     .12       0    8467     .07       0  8627.1     .05       0
    8721    .035       0  8875.3     .05       0
Bank Sta=2954.3,5807.5
XS Rating Curve= 0 ,0
Exp/Cntr=0.3,0.1

Type RM Length L Ch R = 1 ,3387    ,1217,1217,1217
BEGIN DESCRIPTION:
PERDIDO CREEK 3.0
END DESCRIPTION:
XS GIS Cut Line= 3
      2551011.43      13455062.7      2553780.04     13452624.91
      2555887.54     13450222.23
#Sta/Elev= 30
  1311.1     121    1503  121.22  1711.9  122.05  2041.8  125.92  2168.9  124.07
  2438.4  113.76  2509.2  109.05  2588.5  101.53  2622.4    99.8    2630    99.8
    2631      92  7122.3      92  7128.9   99.26  7136.5   99.37  7235.2   103.8
  7455.4  108.96  7531.9  116.62  7535.6  116.38  7547.4  114.22  7568.3  115.48
  7639.5  108.96  7780.9  109.35  7816.9   101.5  7839.8   106.3    7852  110.77
  7866.3   112.8  7919.7  113.42  7993.7  113.06  8147.6  112.79    8196  112.97
#Mann= 14 ,-1 , 0
  1311.1     .07       0    1503     .12       0  1711.9     .07       0
  2509.2     .12       0  2588.5    .033       0  2622.4     .03       0
  7128.9     .03       0  7136.5     .07       0  7531.9    .035       0
  7535.6     .05       0  7839.8     .07       0  7919.7     .12       0
  7993.7     .07       0  8147.6     .05       0
Bank Sta=2622.4,7128.9
XS Rating Curve= 0 ,0
Exp/Cntr=0.3,0.1

Type RM Length L Ch R = 1 ,2170    ,501,501,501
BEGIN DESCRIPTION:
Mapping XS f442833e
END DESCRIPTION:
XS GIS Cut Line= 3
      2551080.73     13455137.34      2554674.06     13453240.39
      2555698.77     13451033.15
#Sta/Elev= 30
   936.7     120  1116.6  118.73  1198.2  118.61  1362.5   118.1  1422.9  114.53
  1488.9  116.04  1546.9  113.19  1637.4  110.66  1704.2  110.42  1813.6  105.94
  1851.9  102.75  1912.3   99.86  1974.2    99.3  2015.8   98.76  2028.1   98.15
  2038.4      92  7132.8      92  7199.4      92  7200.9   94.63  7202.2   98.93
  7208.9   99.51  7270.9  100.08  7293.8  103.68  7316.7  105.48  7345.1  104.92
  7390.9  107.04  7408.3  110.38  7412.8  112.34  7420.4  115.13  7433.5  116.97
#Mann= 12 ,-1 , 0
   936.7     .07       0  1116.6     .12       0  1198.2     .07       0
  1546.9     .12       0  1704.2     .07       0  1974.2     .12       0
  2015.8     .03       0  7132.8    .033       0  7200.9    .033       0
  7202.2    .033       0  7208.9     .07       0  7412.8    .035       0
Bank Sta=2015.8,7202.2
XS Rating Curve= 0 ,0
Exp/Cntr=0.3,0.1

Type RM Length L Ch R = 1 ,1669    ,822,822,822
BEGIN DESCRIPTION:
Mapping XS 3245d84e
END DESCRIPTION:
XS GIS Cut Line= 3
      2551792.13     13455690.73      2554884.58     13453683.34
      2556627.21     13452238.89
#Sta/Elev= 30
  1278.8   110.3  1412.4  113.61  1627.9  116.45  1677.9  116.96  1806.8   116.7
  2018.4  109.75  2018.8  109.74  2072.5  109.05  2160.1  113.65    2435  120.34
  2694.7  121.82  3022.6  118.82  3208.1  116.42  3322.8  111.96  3475.9   99.18
    3483      92  6612.7      92  6619.2   99.32  6627.1  101.43  6655.6  101.22
  6875.5  102.33  7019.8   98.85  7091.4   95.01  7131.1   94.65  7151.9   97.69
  7159.7  101.72  7166.2  101.64  7175.1   105.1  7180.6  105.11  7229.1  118.25
#Mann= 13 ,-1 , 0
  1278.8     .12       0  1412.4     .07       0  1627.9     .12       0
  1677.9     .07       0  2018.4     .12       0  2018.8     .07       0
  3022.6     .12       0  3475.9     .03       0  6619.2     .03       0
  6655.6     .05       0  7019.8     .07       0  7091.4    .033       0
  7175.1    .063       0
Bank Sta=3475.9,6619.2
XS Rating Curve= 0 ,0
Exp/Cntr=0.3,0.1

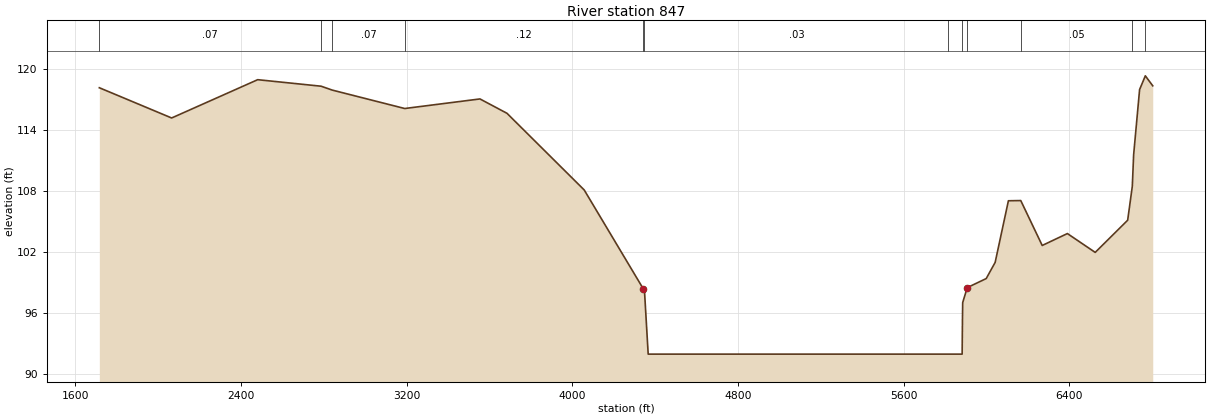
Type RM Length L Ch R = 1 ,847     ,0,0,0
BEGIN DESCRIPTION:
PERDIDO CREEK 1.0
END DESCRIPTION:
XS GIS Cut Line= 3
      2552232.71     13455621.26      2555315.91     13454351.58
      2556683.84     13453253.72
#Sta/Elev= 30
  1715.2  118.16  2064.5  115.19  2480.1  118.95  2786.5  118.31  2840.1  117.93
  3190.3  116.12  3553.8  117.06  3684.3  115.65  4057.4  108.12  4342.5   98.42
  4347.9   98.42  4366.4      92  5816.3      92  5882.9      92  5884.4   95.33
  5885.6   97.06  5907.5   98.53  5999.2   99.42  6042.4  101.01  6106.4  107.06
  6166.1  107.08  6269.7  102.67  6391.3  103.84  6525.7  101.99  6682.5  105.15
  6704.9  108.48  6711.3  111.57  6740.1  117.98  6767.8  119.33  6803.6  118.35
#Mann= 12 ,-1 , 0
  1715.2     .07       0  2786.5     .12       0  2840.1     .07       0
  3190.3     .12       0  4342.5     .05       0  4347.9     .03       0
  5816.3    .033       0  5884.4    .033       0  5907.5    .033       0
  6166.1     .05       0  6704.9    .035       0  6767.8     .05       0
Bank Sta=4342.5,5907.5
XS Rating Curve= 0 ,0
Exp/Cntr=0.3,0.1

Chan Stop Cuts=-1
Use User Specified Reach Order=0
Composite Channel Slope=5