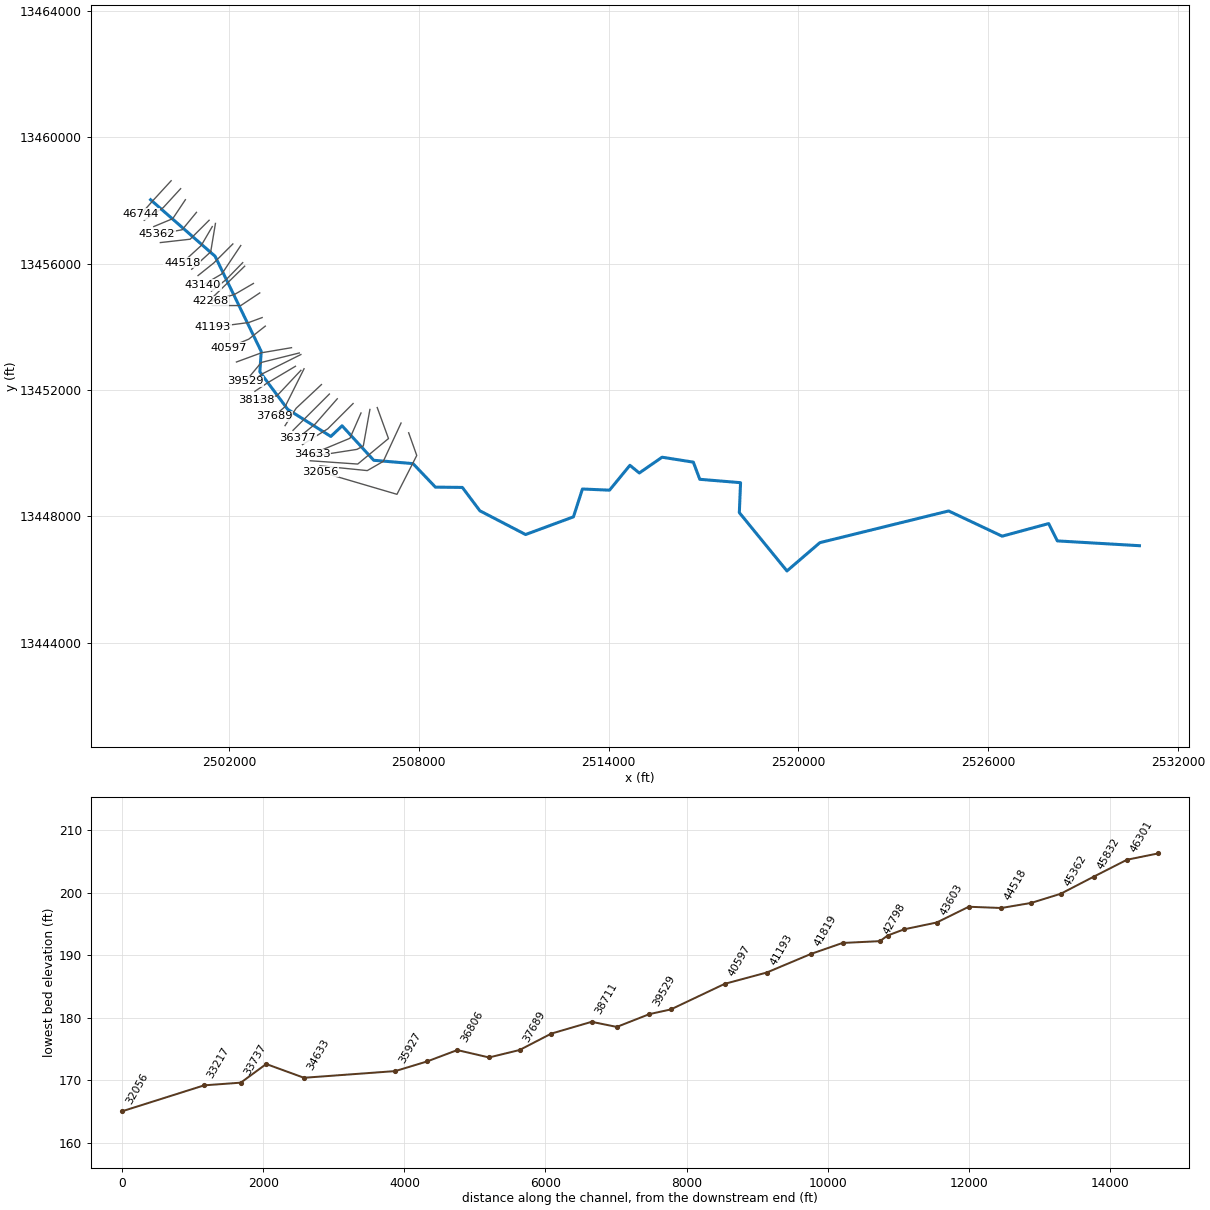
--- ROAD CREEK.prj (project) ---

Proj Title=ROAD CREEK Base Level Engineering
Current Plan=p01
Default Exp/Contr=0.3,0.1
English Units
Geom File=g01
Flow File=f01
Plan File=p01
Y Axis Title=Elevation
X Axis Title(PF)=Main Channel Distance
X Axis Title(XS)=Station
BEGIN DESCRIPTION:
ROAD CREEK
END DESCRIPTION:
DSS Export Rating Curves= 0
DSS Export Rating Curve Sorted= 0
DSS Export Volume Flow Curves= 0
DXF OffsetX= 0
DXF OffsetY= 0
DXF ScaleX= 1
DXF ScaleY= 10

--- ROAD CREEK.p01 (plan) ---

Plan Title=Multiple Run
Short Identifier=Multiple
Geom File=g01
Flow File=f01
Subcritical Flow
K Sum by GR= 0
Std Step Tol= 0.01
Critical Tol= 0.01
Num of Std Step Trials= 20
Max Error Tol= 0.3
Flow Tol Ratio= 0.001
Split Flow NTrial= 30
Split Flow Tol= 0.02
Split Flow Ratio= 0.02
Log Output Level= 0
Friction Slope Method= 1
Unsteady Friction Slope Method= 2
Unsteady Bridges Friction Slope Method= 1
Parabolic Critical Depth
Global Vel Dist=  1 , 1 , 1
Global Log Level= 0
CheckData=True
Encroach Param= -1, 0, 0, 0
BEGIN DESCRIPTION:
Multiple Run
END DESCRIPTION:

--- ROAD CREEK.f01 (steady flow) ---

Flow Title=Multiple
Program Version=4.10
Number of Profiles= 7
Profile Names=10-year,25-year,50-year,1pct_min,100-year,1pct_plu,500-year
River Rch & RM=ROAD CREEK,Reach-1         ,46744
     400     619     807     511    1019    2033    1603
River Rch & RM=ROAD CREEK,Reach-1         ,44057
     648    1032    1373     883    1763    3517    2874
River Rch & RM=ROAD CREEK,Reach-1         ,39833
     872    1410    1895    1230    2454    4896    4075
River Rch & RM=ROAD CREEK,Reach-1         ,35927
    1111    1815    2456    1604    3200    6384    5376
River Rch & RM=ROAD CREEK,Reach-1         ,26575
    1322    2179    2966    1947    3884    7749    6598
River Rch & RM=ROAD CREEK,Reach-1         ,22676
    1652    2741    3747    2469    4927    9830    8432
River Rch & RM=ROAD CREEK,Reach-1         ,18012
    2066    3458    4757    3151    6287   12544   10875
River Rch & RM=ROAD CREEK,Reach-1         ,13019
    3021    5133    7132    4767    9512   18979   16755
River Rch & RM=ROAD CREEK,Reach-1         ,8852
    3151    5356    7444    4976    9929   19812   17493
River Rch & RM=ROAD CREEK,Reach-1         ,5092
    3164    5373    7463    4985    9947   19847   17500
River Rch & RM=ROAD CREEK,Reach-1         ,1861
    3746    6413    8957    6015   12002   23946   21334
Boundary for River Rch & Prof#=ROAD CREEK,Reach-1         , 1
Up Type= 0
Dn Type= 3
Dn Slope=0.00107
Boundary for River Rch & Prof#=ROAD CREEK,Reach-1         , 2
Up Type= 0
Dn Type= 3
Dn Slope=0.00107
Boundary for River Rch & Prof#=ROAD CREEK,Reach-1         , 3
Up Type= 0
Dn Type= 3
Dn Slope=0.00107
Boundary for River Rch & Prof#=ROAD CREEK,Reach-1         , 4
Up Type= 0
Dn Type= 3
Dn Slope=0.00107
Boundary for River Rch & Prof#=ROAD CREEK,Reach-1         , 5
Up Type= 0
Dn Type= 3
Dn Slope=0.00107
Boundary for River Rch & Prof#=ROAD CREEK,Reach-1         , 6
Up Type= 0
Dn Type= 3
Dn Slope=0.00107
Boundary for River Rch & Prof#=ROAD CREEK,Reach-1         , 7
Up Type= 0
Dn Type= 3
Dn Slope=0.00107
DSS Import GetInterval= 0
DSS Import GetPeak= 0
DSS Import FillOption= 0

--- ROAD CREEK.g01 (geometry) ---

Geom Title=Existing Conditions
Program Version=4.10

River Reach=ROAD CREEK      ,Reach-1
Reach XY= 30
        2499525.       13458025.      2501563.92     13456235.05
      2503021.45     13453223.53      2502978.37     13452576.28
      2503858.29     13451391.29      2505221.65     13450532.58
      2505577.29     13450869.94      2506576.46     13449778.54
      2507819.07     13449672.76       2508526.5     13448928.46
      2509377.42     13448919.46      2509930.58     13448180.58
      2511376.52     13447428.74      2512888.63     13447988.46
      2513172.56     13448869.48      2514028.42     13448832.79
      2514672.58     13449619.59      2514968.91     13449376.56
      2515690.09     13449875.77      2516677.32     13449719.18
      2516881.02     13449176.61      2518169.59     13449069.82
      2518130.46     13448122.54      2519635.42     13446276.02
      2520676.45     13447171.47      2524745.03     13448174.94
       2526435.5     13447376.22      2527905.02     13447775.04
      2528180.84     13447227.05        2530775.       13447075.

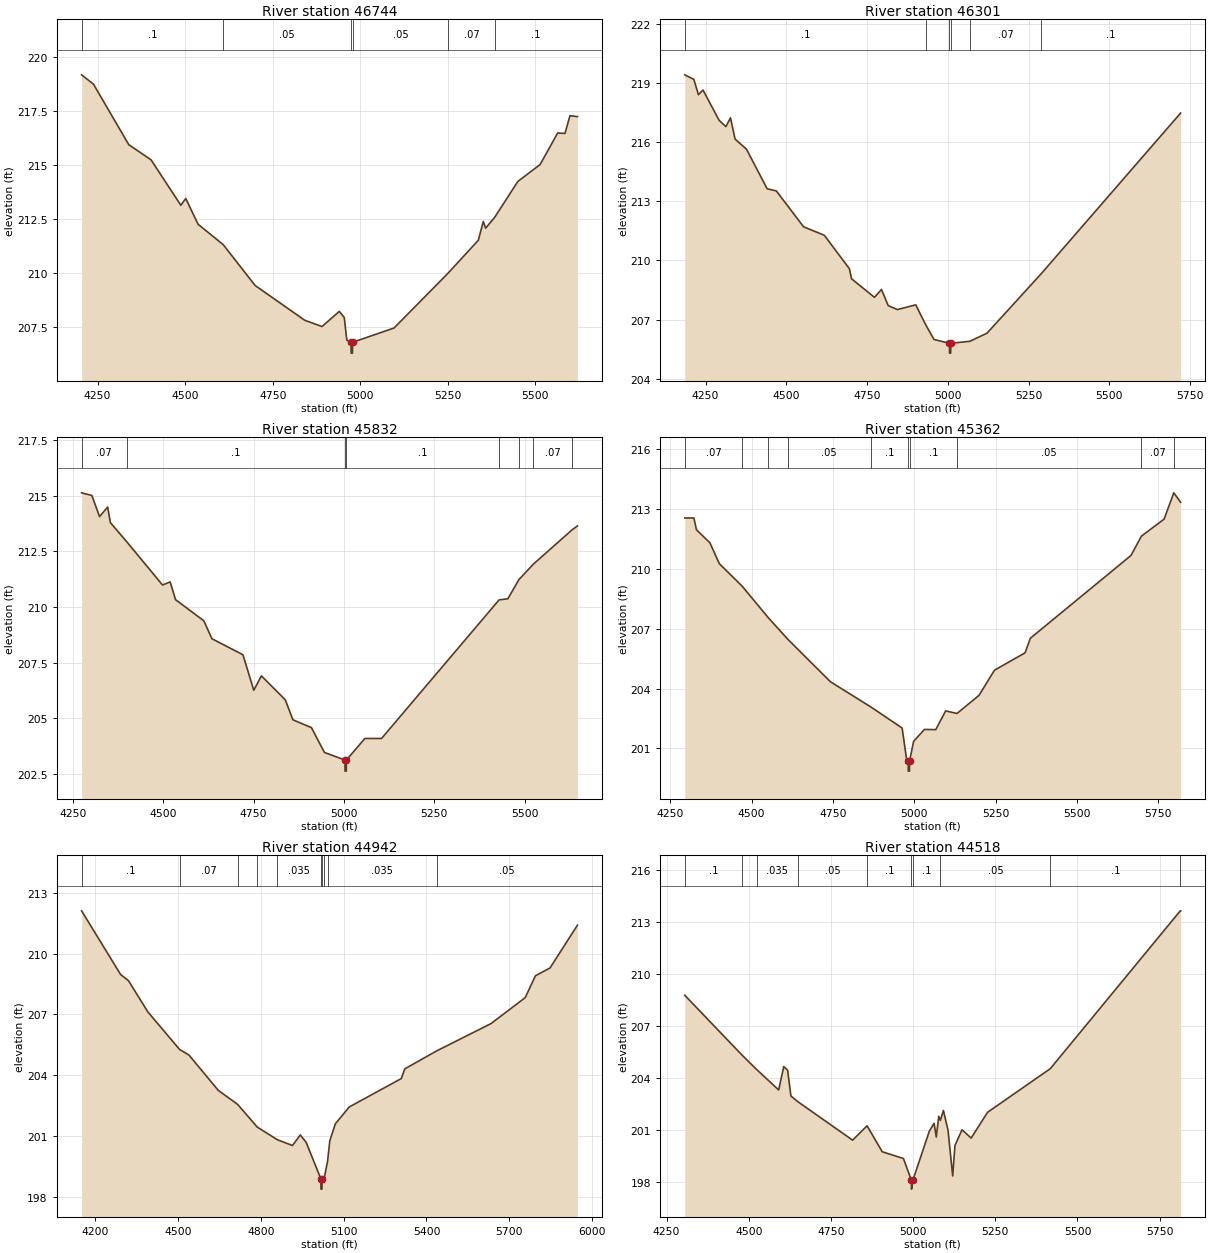
Type RM Length L Ch R = 1 ,46744   ,443,443,443
BEGIN DESCRIPTION:
ROAD CREEK 76.0
END DESCRIPTION:
XS GIS Cut Line= 3
      2500175.02     13458625.02        2499625.       13458025.
      2499225.03     13457575.03
#Sta/Elev= 30
  4204.2  219.18  4238.1  218.75    4339  215.95  4402.5  215.25  4487.6  213.15
  4501.7  213.46  4536.9  212.27  4608.5  211.33  4699.7  209.44  4841.5  207.83
  4890.8  207.54  4940.2  208.24  4954.3  207.96  4961.7  206.91  4973.9  206.81
  4974.2  206.31  4977.7  206.31  4977.9  206.81  5096.4  207.47    5251  210.01
  5337.2  211.53  5351.4   212.4  5358.1  212.09  5383.9  212.59  5450.1  214.25
  5513.6  215.03  5563.8  216.49  5584.7  216.47  5598.9  217.29  5620.2  217.25
#Mann= 6 ,-1 , 0
  4204.2      .1       0  4608.5     .05       0  4973.9     .05       0
  4977.9     .05       0    5251     .07       0  5383.9      .1       0
Bank Sta=4973.9,4977.9
XS Rating Curve= 0 ,0
Exp/Cntr=0.3,0.1

Type RM Length L Ch R = 1 ,46301   ,469,469,469
BEGIN DESCRIPTION:
ROAD CREEK 75.0
END DESCRIPTION:
XS GIS Cut Line= 3
      2500475.01     13458375.01        2499925.       13457775.
      2499324.97     13457374.98
#Sta/Elev= 30
  4185.8  219.42  4213.9  219.19  4228.1  218.41  4242.2  218.65  4292.2  217.11
  4313.1  216.79  4327.3  217.24  4341.5  216.16  4376.7  215.65  4440.8  213.64
  4469.2  213.53  4553.6  211.71  4617.8  211.28  4695.5  209.58  4702.2  209.07
  4773.1  208.13  4794.7  208.53  4815.7  207.71  4844.1  207.51  4900.8  207.75
    4932  206.73  4957.5  205.99  5005.3   205.8  5005.5   205.3    5009   205.3
  5009.3   205.8  5068.2   205.9  5121.4  206.31  5289.9  209.34  5720.9  217.48
#Mann= 6 ,-1 , 0
  4185.8      .1       0    4932      .1       0  5005.3     .05       0
  5009.3      .1       0  5068.2     .07       0  5289.9      .1       0
Bank Sta=5005.3,5009.3
XS Rating Curve= 0 ,0
Exp/Cntr=0.3,0.1

Type RM Length L Ch R = 1 ,45832   ,470,470,470
BEGIN DESCRIPTION:
ROAD CREEK 74.0
END DESCRIPTION:
XS GIS Cut Line= 3
      2500624.99     13458024.98        2500225.       13457425.
      2499624.99     13457174.99
#Sta/Elev= 30
  4274.6  215.14  4303.1  215.02  4324.2  214.07  4346.7   214.5  4354.2   213.8
  4399.3  212.94  4498.4  210.99  4519.5  211.13  4534.5  210.33  4612.6  209.38
  4635.1  208.57  4720.8  207.85  4750.8  206.25  4771.8   206.9  4837.9  205.82
    4859  204.92  4910.1  204.57  4946.1  203.45  5002.9  203.11  5003.1  202.61
  5006.6  202.61  5006.9  203.11    5058  204.08    5104  204.08  5429.1  210.32
  5453.4  210.37  5483.7  211.23  5523.9  211.93  5631.4  213.48  5645.7  213.65
#Mann= 8 ,-1 , 0
  4274.6     .07       0  4399.3      .1       0  5002.9     .05       0
  5006.9      .1       0  5429.1     .07       0  5483.7     .05       0
  5523.9     .07       0  5631.4      .1       0
Bank Sta=5002.9,5006.9
XS Rating Curve= 0 ,0
Exp/Cntr=0.3,0.1

Type RM Length L Ch R = 1 ,45362   ,420,420,420
BEGIN DESCRIPTION:
ROAD CREEK 73.0
END DESCRIPTION:
XS GIS Cut Line= 3
        2500975.       13457625.        2500525.       13457075.
      2499724.98       13456925.
#Sta/Elev= 30
  4294.3  212.55  4322.3  212.55  4330.2  211.96  4371.8   211.3  4400.5  210.26
  4470.8  209.13  4550.6  207.56  4611.1  206.47  4742.2  204.34  4866.1  203.08
  4962.6  202.02  4976.9  200.39  4981.4  200.36  4981.6  199.86  4985.1  199.86
  4985.4  200.36  4997.8  201.35  5031.2  201.95    5066  201.94  5096.5  202.88
  5131.3  202.75  5199.1  203.66  5246.6  204.92  5340.7  205.79  5356.8  206.52
  5666.3  210.67  5698.4  211.64    5768  212.49  5797.9  213.81  5818.9  213.34
#Mann= 10 ,-1 , 0
  4294.3     .07       0  4470.8      .1       0  4550.6     .07       0
  4611.1     .05       0  4866.1      .1       0  4981.4     .05       0
  4985.4      .1       0  5131.3     .05       0  5698.4     .07       0
  5797.9      .1       0
Bank Sta=4981.4,4985.4
XS Rating Curve= 0 ,0
Exp/Cntr=0.3,0.1

Type RM Length L Ch R = 1 ,44942   ,424,424,424
BEGIN DESCRIPTION:
ROAD CREEK 72.0
END DESCRIPTION:
XS GIS Cut Line= 3
      2501374.97     13457374.97        2500775.       13456775.
      2499833.99     13456668.52
#Sta/Elev= 30
  4151.2  212.11  4292.6  208.97  4320.9  208.67  4391.6  207.12  4505.8  205.28
  4540.1     205  4646.1  203.26  4716.2  202.57  4787.3  201.45  4859.7  200.83
  4914.8  200.54  4943.1  201.06  4964.3   200.7  5017.8  198.89  5018.1  198.39
  5021.6  198.39  5021.8  198.89  5029.2  198.89    5042  199.77    5050  200.77
  5070.1  201.61  5120.4  202.44  5308.8  203.84  5321.7  204.32  5436.4   205.2
  5633.7  206.55  5757.6  207.83  5794.7  208.91  5847.3  209.29  5946.7   211.4
#Mann= 10 ,-1 , 0
  4151.2      .1       0  4505.8     .07       0  4716.2      .1       0
  4787.3     .05       0  4859.7    .035       0  5017.8    .035       0
  5021.8    .035       0  5029.2     .05       0    5042    .035       0
  5436.4     .05       0
Bank Sta=5017.8,5021.8
XS Rating Curve= 0 ,0
Exp/Cntr=0.3,0.1

Type RM Length L Ch R = 1 ,44518   ,461,461,461
BEGIN DESCRIPTION:
ROAD CREEK 71.0
END DESCRIPTION:
XS GIS Cut Line= 3
      2501474.98     13457174.96        2501125.       13456575.
      2500525.01     13456025.01
#Sta/Elev= 30
  4305.3  208.78  4478.7  205.34  4523.5   204.5    4591  203.31  4606.3  204.66
  4618.2  204.45  4628.2  202.96  4650.2  202.62  4815.9  200.41  4859.9  201.24
    4906  199.74  4970.5  199.35    4995  198.08  4995.2  197.58    4999  198.08
  5049.5  200.94  5063.7  201.38  5070.5  200.59  5077.9  201.79  5082.9  201.55
  5092.1  202.13  5106.2  200.98  5120.4  198.34  5127.2   200.1  5148.8  201.01
  5176.5  200.53  5226.5  202.02  5417.3  204.54  5812.8  213.66  5813.8  213.66
#Mann= 10 ,-1 , 0
  4305.3      .1       0  4478.7     .07       0  4523.5    .035       0
  4650.2     .05       0  4859.9      .1       0    4995     .05       0
    4999      .1       0  5082.9     .05       0  5417.3      .1       0
  5812.8     .05       0
Bank Sta=4995,4999
XS Rating Curve= 0 ,0
Exp/Cntr=0.3,0.1

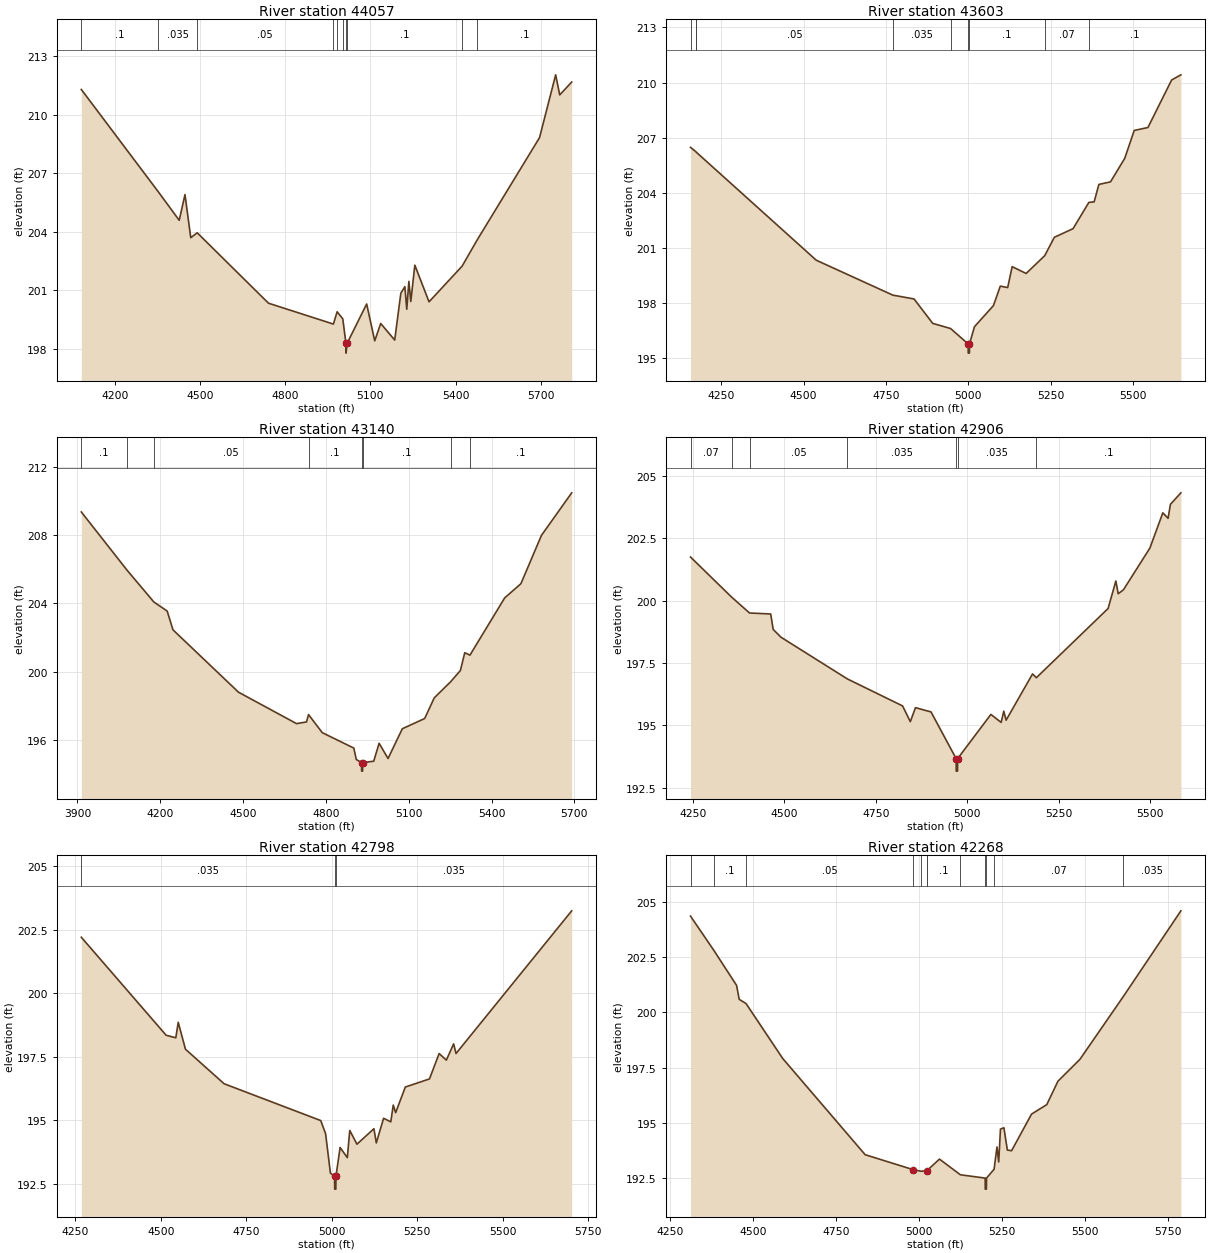
Type RM Length L Ch R = 1 ,44057   ,454,454,454
BEGIN DESCRIPTION:
ROAD CREEK 70.0
END DESCRIPTION:
XS GIS Cut Line= 3
      2501575.01     13457275.03        2501425.       13456375.
      2500824.99     13455824.99
#Sta/Elev= 30
  4082.6   211.3  4351.7  206.09  4427.3  204.59  4447.6  205.91  4467.9   203.7
  4490.7  203.95  4741.6  200.34    4970  199.27  4983.2   199.9  5003.1  199.54
  5014.3  198.28  5014.6  197.78  5018.3  198.28  5087.2   200.3  5115.6  198.41
  5136.6   199.3  5185.9  198.45  5207.5  200.85  5221.7  201.19  5228.4  200.03
  5235.8  201.46  5242.6  200.43  5256.8  202.29  5306.8  200.41  5423.2  202.24
  5475.3  203.56  5695.8  208.83  5752.6  212.05  5766.8  211.02    5809  211.68
#Mann= 10 ,-1 , 0
  4082.6      .1       0  4351.7    .035       0  4490.7     .05       0
    4970      .1       0  4983.2      .1       0  5003.1      .1       0
  5014.3     .05       0  5018.3      .1       0  5423.2     .07       0
  5475.3      .1       0
Bank Sta=5014.3,5018.3
XS Rating Curve= 0 ,0
Exp/Cntr=0.3,0.1

Type RM Length L Ch R = 1 ,43603   ,463,463,463
BEGIN DESCRIPTION:
ROAD CREEK 69.0
END DESCRIPTION:
XS GIS Cut Line= 3
      2502125.01     13456625.01        2501525.       13456025.
      2501024.97     13455624.97
#Sta/Elev= 30
  4156.4  206.47  4172.8  206.23    4173  206.22  4538.3  200.32  4770.6  198.42
  4835.2  198.21  4891.8  196.88  4946.1   196.6  4999.4  195.76  4999.7  195.26
  5003.2  195.26  5003.4  195.76  5018.6   196.7  5076.2  197.85    5097  198.91
  5119.4  198.83    5133  199.97  5175.4   199.6  5231.9  200.57  5261.1  201.57
  5317.9  202.04  5365.9  203.47  5381.9   203.5  5396.3  204.45  5431.6  204.59
  5474.8  205.87  5503.6  207.39  5545.2  207.55  5617.2  210.14  5645.3  210.42
#Mann= 9 ,-1 , 0
  4156.4      .1       0  4172.8     .07       0    4173     .05       0
  4770.6    .035       0  4946.1      .1       0  4999.4     .05       0
  5003.4      .1       0  5231.9     .07       0  5365.9      .1       0
Bank Sta=4999.4,5003.4
XS Rating Curve= 0 ,0
Exp/Cntr=0.3,0.1

Type RM Length L Ch R = 1 ,43140   ,234,234,234
BEGIN DESCRIPTION:
ROAD CREEK 68.0
END DESCRIPTION:
XS GIS Cut Line= 3
      2502375.03     13456575.04        2501775.       13455675.
      2501175.03     13455325.02
#Sta/Elev= 30
  3913.9  209.34  4079.7  205.93  4176.7  204.07  4224.9  203.54    4246  202.44
  4483.3  198.79  4693.6  196.95  4729.7  197.05  4736.9  197.48  4786.8  196.42
    4901  195.52    4910  194.85    4929  194.67  4929.3  194.17  4932.8  194.17
    4933  194.67  4973.1  194.75  4992.6   195.8    5025  194.91  5076.7  196.65
  5157.7  197.25  5192.4  198.46  5251.6   199.4  5287.1  200.06  5302.8   201.1
  5321.7  200.96  5447.5  204.31  5506.2  205.14  5580.7  207.97  5690.2  210.46
#Mann= 8 ,-1 , 0
  3913.9      .1       0  4079.7     .07       0  4176.7     .05       0
  4736.9      .1       0    4929     .05       0    4933      .1       0
  5251.6     .07       0  5321.7      .1       0
Bank Sta=4929,4933
XS Rating Curve= 0 ,0
Exp/Cntr=0.3,0.1

Type RM Length L Ch R = 1 ,42906   ,108,108,108
BEGIN DESCRIPTION:
Mapping XS e638bf89
END DESCRIPTION:
XS GIS Cut Line= 3
       2502436.6      13456033.2      2501915.75     13455498.46
      2501448.47     13455131.55
#Sta/Elev= 30
  4243.5  201.74  4356.3  200.13  4404.9   199.5  4462.7  199.46  4469.6  198.84
  4490.9  198.53  4672.4  196.86  4823.3  195.78  4844.4  195.15  4858.5  195.71
    4901  195.54  4969.7  193.67    4970  193.17  4973.5  193.17  4973.7  193.67
  5064.7  195.44  5092.7  195.12  5099.9  195.57  5106.3  195.21  5178.5  197.06
    5189  196.91  5385.1  199.68  5406.3  200.78  5412.7  200.27  5427.1  200.43
  5499.4   202.1  5534.7  203.51  5549.1  203.29  5555.5  203.85  5584.1  204.31
#Mann= 7 ,-1 , 0
  4243.5     .07       0  4356.3    .035       0  4404.9     .05       0
  4672.4    .035       0  4969.7    .035       0  4973.7    .035       0
    5189      .1       0
Bank Sta=4969.7,4973.7
XS Rating Curve= 0 ,0
Exp/Cntr=0.3,0.1

Type RM Length L Ch R = 1 ,42798   ,530,530,530
BEGIN DESCRIPTION:
ROAD CREEK 67.0
END DESCRIPTION:
XS GIS Cut Line= 3
      2502499.07     13455922.05      2501975.05     13455409.66
      2501472.02     13454919.29
#Sta/Elev= 30
  4267.1   202.2  4515.4  198.34  4543.7  198.24  4550.8  198.85    4572  197.79
  4685.1  196.43    4968  194.98  4982.2  194.46  4996.3  192.91  5008.4  192.78
  5008.7  192.28  5012.2  192.28  5012.4  192.78  5024.6  193.92  5045.7  193.52
  5052.9  194.59    5074  194.05  5123.6  194.66  5130.6   194.1  5151.9  195.07
    5173  194.93  5180.2  195.59  5187.2  195.29  5215.5   196.3  5286.2  196.62
  5314.5  197.62  5335.6  197.36  5356.9     198  5363.9  197.62  5702.5  203.24
#Mann= 3 ,-1 , 0
  4267.1    .035       0  5008.4    .035       0  5012.4    .035       0
Bank Sta=5008.4,5012.4
XS Rating Curve= 0 ,0
Exp/Cntr=0.3,0.1

Type RM Length L Ch R = 1 ,42268   ,449,449,449
BEGIN DESCRIPTION:
ROAD CREEK 66.0
END DESCRIPTION:
XS GIS Cut Line= 3
      2502774.96     13455374.98        2502175.       13455025.
      2501422.69     13454807.48
#Sta/Elev= 30
  4311.2  204.36  4381.9   202.8  4450.1  201.22  4457.9  200.59  4478.5   200.4
    4589  197.91  4837.5  193.55  4982.6  192.87  5005.9   192.8  5022.6  192.82
  5023.1  192.82  5061.4  193.35  5124.5  192.64  5199.1  192.49  5199.3  191.99
  5202.8  191.99  5203.1  192.49    5226  192.89  5234.7   193.9  5239.9  193.22
  5245.2  194.71  5255.6  194.77    5266  193.76  5278.7  193.73  5338.9  195.39
  5384.8  195.82  5418.4  196.88  5484.6  197.87  5615.1  200.71  5788.9   204.6
#Mann= 12 ,-1 , 0
  4311.2     .05       0  4381.9      .1       0  4478.5     .05       0
  4982.6     .05       0  5005.9     .05       0  5022.6      .1       0
  5023.1      .1       0  5124.5      .1       0  5199.1     .05       0
  5203.1      .1       0    5226     .07       0  5615.1    .035       0
Bank Sta=4982.6,5022.6
XS Rating Curve= 0 ,0
Exp/Cntr=0.3,0.1

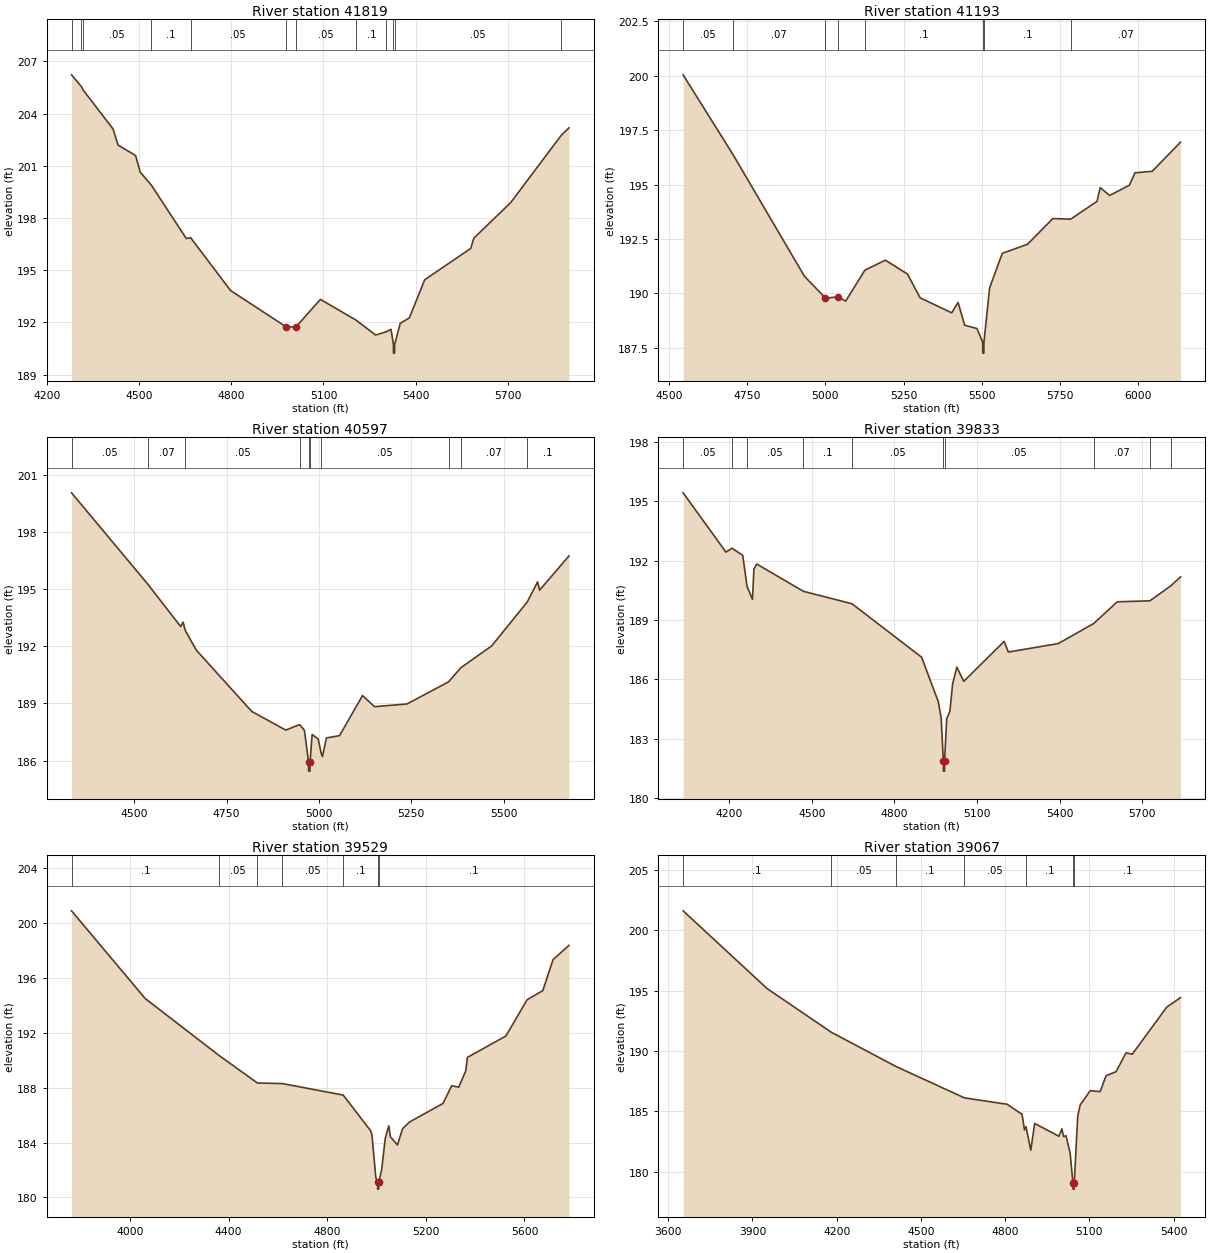
Type RM Length L Ch R = 1 ,41819   ,626,626,626
BEGIN DESCRIPTION:
ROAD CREEK 65.0
END DESCRIPTION:
XS GIS Cut Line= 3
      2502974.98     13455074.98        2502375.       13454675.
      2501474.98       13454675.
#Sta/Elev= 30
  4278.9  206.23  4311.2  205.55  4316.5  205.36  4414.1  203.12  4430.6  202.19
  4487.7  201.59  4502.7  200.64  4538.5   199.9  4652.9  196.82  4666.8  196.87
  4797.2  193.83  4977.4  191.75    5010  191.73    5090  193.32  5206.8  192.12
    5270  191.27  5305.1  191.46    5320   191.6    5328  190.73  5328.2  190.23
  5331.7  190.23    5332  190.73    5350  191.94    5380  192.26    5430  194.45
    5580  196.25    5590  196.84    5710  198.88  5875.2  202.76    5900  203.18
#Mann= 12 ,-1 , 0
  4278.9     .05       0  4311.2      .1       0  4316.5     .05       0
  4538.5      .1       0  4666.8     .05       0  4977.4     .05       0
    5010     .05       0  5206.8      .1       0  5305.1     .05       0
    5328     .05       0    5332     .05       0  5875.2    .035       0
Bank Sta=4977.4,5010
XS Rating Curve= 0 ,0
Exp/Cntr=0.3,0.1

Type RM Length L Ch R = 1 ,41193   ,596,596,596
BEGIN DESCRIPTION:
Mapping XS f32a239a
END DESCRIPTION:
XS GIS Cut Line= 3
       2503051.2     13454295.34      2502629.29     13454139.08
      2501500.68     13453987.96
#Sta/Elev= 30
  4545.9  200.04  4705.1  196.38  4933.3  190.79  5000.5  189.79  5040.5  189.84
    5065  189.65  5126.4  191.07  5191.8  191.53  5262.5  190.89  5302.8   189.8
  5403.7  189.11  5423.9  189.59  5445.1  188.54  5484.4  188.39  5502.6  187.76
  5502.9  187.26  5506.4  187.26  5506.6  187.76  5524.8  190.26  5565.1  191.84
  5645.9  192.26  5726.6  193.44  5783.3  193.41  5867.8  194.23  5877.9  194.86
  5908.2   194.5  5971.1  194.97  5988.9  195.54  6044.1  195.61  6134.5  196.95
#Mann= 8 ,-1 , 0
  4545.9     .05       0  4705.1     .07       0  5000.5     .05       0
  5040.5     .07       0  5126.4      .1       0  5502.6     .07       0
  5506.6      .1       0  5783.3     .07       0
Bank Sta=5000.5,5040.5
XS Rating Curve= 0 ,0
Exp/Cntr=0.3,0.1

Type RM Length L Ch R = 1 ,40597   ,764,764,764
BEGIN DESCRIPTION:
Mapping XS b68c37f0
END DESCRIPTION:
XS GIS Cut Line= 3
      2503150.15     13454024.52      2502629.29     13453613.04
      2501999.99      13453347.8
#Sta/Elev= 30
  4330.4  200.04  4536.1  195.27  4625.9  193.03  4632.3  193.26  4638.7  192.81
  4668.3  191.79  4818.3  188.58  4910.4   187.6  4947.8  187.89  4960.9  187.59
    4972  185.95  4972.3  185.45    4976  185.45  4976.3  185.95  4981.8  187.37
  4998.1  187.14  5006.2  186.39  5009.7  186.21  5020.5  187.19    5056  187.31
  5118.2  189.41  5150.8  188.83  5238.4  188.97  5351.2  190.13  5384.4  190.87
  5468.2  192.02  5564.2  194.32  5592.2  195.37  5597.7  194.94  5677.1  196.73
#Mann= 10 ,-1 , 0
  4330.4     .05       0  4536.1     .07       0  4638.7     .05       0
  4947.8     .07       0    4972     .05       0  4976.3     .07       0
  5006.2     .05       0  5351.2      .1       0  5384.4     .07       0
  5564.2      .1       0
Bank Sta=4972,4976.3
XS Rating Curve= 0 ,0
Exp/Cntr=0.3,0.1

Type RM Length L Ch R = 1 ,39833   ,304,304,304
BEGIN DESCRIPTION:
Mapping XS d154677f
END DESCRIPTION:
XS GIS Cut Line= 3
      2503978.25     13453342.21      2503030.33     13453180.75
      2502238.62     13452889.06
#Sta/Elev= 30
  4033.2  195.43  4188.7  192.43  4210.4  192.63  4249.5  192.27  4265.3   190.7
  4284.8  190.04  4290.1  191.57  4300.2  191.83    4470  190.45  4646.2  189.82
  4898.7  187.12  4959.6  184.86  4969.7  184.04  4977.7  181.86    4978  181.36
  4981.8  181.36    4982  181.86  4989.9  184.01  5001.4  184.39  5011.1  185.75
  5026.5  186.62  5051.6   185.9  5198.5  187.92  5213.6  187.38  5394.8  187.81
    5523  188.82  5608.8  189.92  5727.2  189.97  5802.4  190.72  5838.5  191.18
#Mann= 10 ,-1 , 0
  4033.2     .05       0  4210.4      .1       0  4265.3     .05       0
    4470      .1       0  4646.2     .05       0  4977.7     .05       0
    4982     .05       0    5523     .07       0  5727.2      .1       0
  5802.4     .07       0
Bank Sta=4977.7,4982
XS Rating Curve= 0 ,0
Exp/Cntr=0.3,0.1

Type RM Length L Ch R = 1 ,39529   ,462,462,462
BEGIN DESCRIPTION:
ROAD CREEK 60.0
END DESCRIPTION:
XS GIS Cut Line= 3
      2504225.03     13453175.01        2503025.       13452875.
      2502524.99     13452274.99
#Sta/Elev= 30
  3762.5  200.91  4061.5  194.51    4361  190.36  4516.7  188.35  4617.3  188.31
  4864.7  187.47  4976.3  184.86  4981.4  184.54  4996.9  181.47  5004.3  181.11
  5004.6  180.61  5008.6  180.61    5009  181.11  5020.9  182.06  5035.3  184.31
  5049.6  185.23  5056.1  184.43  5084.7  183.83  5105.6  185.02  5134.2  185.51
  5269.6  186.86  5304.7  188.15  5333.4  188.05    5362  189.24  5368.5  190.22
  5524.7  191.78  5610.6  194.42  5674.4  195.09  5716.1  197.35  5780.5  198.39
#Mann= 7 ,-1 , 0
  3762.5      .1       0    4361     .05       0  4516.7      .1       0
  4617.3     .05       0  4864.7      .1       0  5004.3     .05       0
    5009      .1       0
Bank Sta=5004.3,5009
XS Rating Curve= 0 ,0
Exp/Cntr=0.3,0.1

Type RM Length L Ch R = 1 ,39067   ,356,356,356
BEGIN DESCRIPTION:
ROAD CREEK 59.0
END DESCRIPTION:
XS GIS Cut Line= 3
      2504274.97     13453124.99        2503075.       13452525.
      2502725.02     13452275.02
#Sta/Elev= 30
  3653.2  201.62  3952.2  195.18    4181  191.56  4410.7  188.73  4655.3  186.12
  4807.5  185.59  4860.6  184.75    4869  183.46  4874.4  183.74  4891.4  181.78
  4905.4     184    4992  182.94  5002.2  183.56  5008.3  182.91  5016.9  182.99
  5031.7  181.54  5041.6  179.06    5042  178.56    5046  178.56  5046.3  179.06
  5058.7  184.61  5067.3  185.53    5103  186.71  5138.6  186.64  5159.5  187.95
  5195.1  188.29  5230.8  189.85  5252.9  189.74  5375.8  193.64  5424.9  194.43
#Mann= 7 ,-1 , 0
  3653.2      .1       0    4181     .05       0  4410.7      .1       0
  4655.3     .05       0  4874.4      .1       0  5041.6     .05       0
  5046.3      .1       0
Bank Sta=5041.6,5046.3
XS Rating Curve= 0 ,0
Exp/Cntr=0.3,0.1

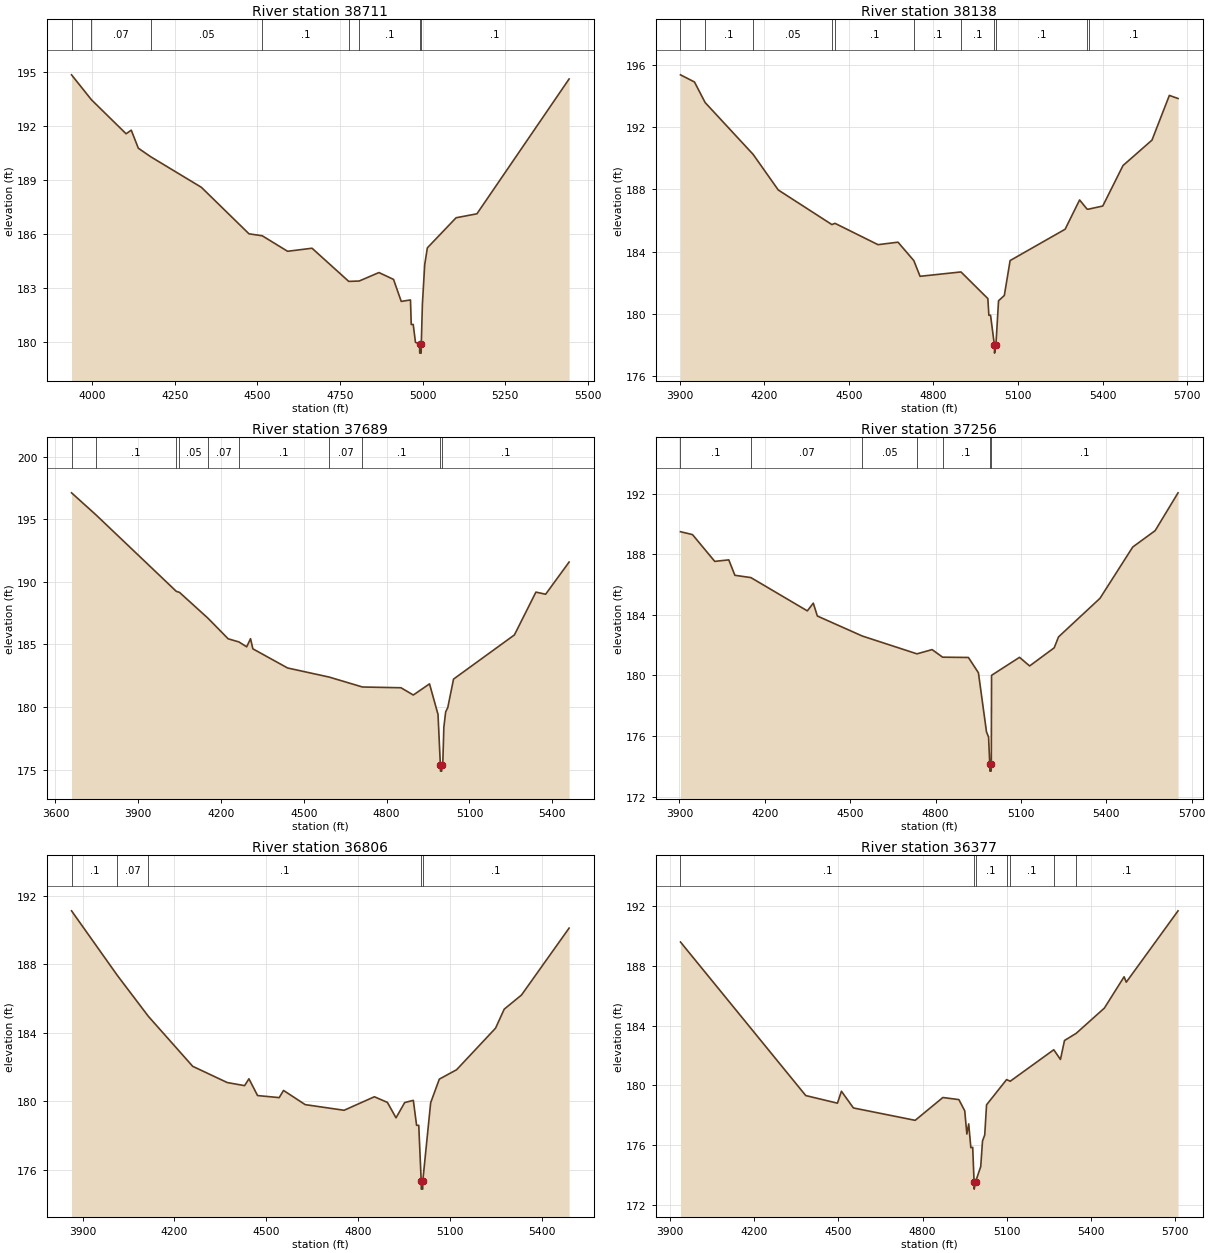
Type RM Length L Ch R = 1 ,38711   ,573,573,573
BEGIN DESCRIPTION:
Mapping XS 60f25421
END DESCRIPTION:
XS GIS Cut Line= 3
      2504103.21     13452753.64      2503217.83     13452227.62
      2502821.96     13451961.97
#Sta/Elev= 30
  3937.2  194.82  3997.3  193.44  4102.4  191.55    4118  191.75  4139.4  190.75
  4177.4  190.27  4330.3  188.58  4474.5     186  4514.7  185.89  4591.4  185.03
  4665.4   185.2  4776.6  183.36  4808.2  183.38    4868  183.85  4912.2  183.47
  4935.5  182.25  4963.5  182.33  4965.8  180.97  4971.8  180.97  4978.6  179.98
  4991.1  179.88  4991.5  179.38  4995.8  179.38  4996.2  179.88  4999.6   182.1
  5006.6  184.29  5014.6  185.22  5101.6  186.89  5164.7  187.11  5443.8  194.59
#Mann= 8 ,-1 , 0
  3937.2      .1       0  3997.3     .07       0  4177.4     .05       0
  4514.7      .1       0  4776.6      .1       0  4808.2      .1       0
  4991.1     .05       0  4996.2      .1       0
Bank Sta=4991.1,4996.2
XS Rating Curve= 0 ,0
Exp/Cntr=0.3,0.1

Type RM Length L Ch R = 1 ,38138   ,449,449,449
BEGIN DESCRIPTION:
ROAD CREEK 57.0
END DESCRIPTION:
XS GIS Cut Line= 3
      2504274.99     13452624.99        2503525.       13451825.
      2502874.96     13451674.99
#Sta/Elev= 30
  3903.4  195.35    3953  194.89  3990.8  193.57  4161.1  190.24    4250  187.96
  4440.1  185.74    4451  185.82  4603.6  184.45  4674.4  184.61  4730.4  183.43
  4752.6  182.42  4897.7   182.7  4992.9  180.99  4996.5  179.92  5002.5  179.92
  5016.2  177.99  5016.6  177.49  5021.4  177.99  5030.8  180.85  5051.3  181.19
  5071.8  183.43  5266.8  185.44  5318.1  187.32  5344.7  186.73  5349.7  186.73
  5400.2  186.93  5472.1  189.53  5574.7  191.16  5636.3  194.03  5667.1  193.83
#Mann= 11 ,-1 , 0
  3903.4     .07       0  3990.8      .1       0  4161.1     .05       0
  4440.1     .07       0    4451      .1       0  4730.4      .1       0
  4897.7      .1       0  5016.2     .05       0  5021.4      .1       0
  5344.7    .035       0  5349.7      .1       0
Bank Sta=5016.2,5021.4
XS Rating Curve= 0 ,0
Exp/Cntr=0.3,0.1

Type RM Length L Ch R = 1 ,37689   ,433,433,433
BEGIN DESCRIPTION:
ROAD CREEK 56.0
END DESCRIPTION:
XS GIS Cut Line= 3
      2504375.01     13452675.01        2503775.       13451475.
      2503425.02     13451175.02
#Sta/Elev= 30
  3658.3   197.1  3746.8  195.34  4037.9  189.23  4049.3  189.15  4152.8  187.08
  4225.7  185.44  4264.7  185.19  4292.8   184.8  4306.8  185.45  4315.2  184.64
  4440.9  183.11  4592.1  182.38  4712.1  181.59  4851.8  181.53  4896.5  180.95
  4955.2  181.84    4986   179.4  4994.5  175.37  4994.9  174.87  4999.4  174.87
  4999.8  175.37  5003.2  175.37  5007.1  178.37  5013.7   179.6  5021.4  179.95
  5042.2  182.22  5262.8  185.75  5340.7  189.17  5375.9     189  5460.9  191.57
#Mann= 10 ,-1 , 0
  3658.3     .07       0  3746.8      .1       0  4037.9     .07       0
  4049.3     .05       0  4152.8     .07       0  4264.7      .1       0
  4592.1     .07       0  4712.1      .1       0  4994.5     .05       0
  4999.8      .1       0
Bank Sta=4994.5,4999.8
XS Rating Curve= 0 ,0
Exp/Cntr=0.3,0.1

Type RM Length L Ch R = 1 ,37256   ,450,450,450
BEGIN DESCRIPTION:
ROAD CREEK 55.0
END DESCRIPTION:
XS GIS Cut Line= 3
      2504924.98     13452174.98        2504125.       13451425.
      2503774.99     13450874.98
#Sta/Elev= 30
  3903.8   189.5    3946  189.31  4024.2  187.54  4073.5  187.64    4095  186.62
  4151.1  186.47  4349.5  184.27  4370.5  184.78  4384.7  183.93  4542.3  182.61
  4734.8  181.43  4788.1  181.71  4824.8  181.21  4915.6  181.19  4950.8  180.18
  4979.1  176.28  4986.4  175.93  4990.6  174.18    4991  173.68  4995.5  173.68
    4996  174.18  4996.9  180.01  5095.2   181.2  5130.7  180.63  5217.1  181.83
  5232.3  182.55    5378   185.1  5493.1  188.49  5571.8  189.57  5652.3  192.07
#Mann= 7 ,-1 , 0
  3903.8      .1       0  4151.1     .07       0  4542.3     .05       0
  4734.8     .07       0  4824.8      .1       0  4990.6     .05       0
    4996      .1       0
Bank Sta=4990.6,4996
XS Rating Curve= 0 ,0
Exp/Cntr=0.3,0.1

Type RM Length L Ch R = 1 ,36806   ,429,429,429
BEGIN DESCRIPTION:
ROAD CREEK 54.0
END DESCRIPTION:
XS GIS Cut Line= 3
      2505174.98     13451874.98        2504375.       13451075.
      2504025.02     13450725.02
#Sta/Elev= 30
  3863.8  191.13  4013.7  187.35    4115  184.96  4259.8  182.04  4372.9  181.09
  4429.5  180.91  4443.6  181.31  4471.9  180.33  4542.6  180.21  4556.7  180.63
  4627.5   179.8  4754.7  179.47  4853.7  180.26  4896.2  179.93  4924.4  179.03
  4952.7  179.92    4981  180.05  4991.6  178.59  4998.7  178.59  5006.6  175.36
    5007  174.86  5011.6  174.86    5012  175.36  5037.6  179.91  5065.9  181.29
  5122.4  181.84  5249.7  184.27    5278  185.38  5334.6  186.21  5490.1  190.12
#Mann= 5 ,-1 , 0
  3863.8      .1       0  4013.7     .07       0    4115      .1       0
  5006.6     .05       0    5012      .1       0
Bank Sta=5006.6,5012
XS Rating Curve= 0 ,0
Exp/Cntr=0.3,0.1

Type RM Length L Ch R = 1 ,36377   ,450,450,450
BEGIN DESCRIPTION:
ROAD CREEK 53.0
END DESCRIPTION:
XS GIS Cut Line= 3
      2505424.99     13451724.98        2504725.       13450925.
      2504175.02     13450475.02
#Sta/Elev= 30
    3937   189.6  4383.5  179.31  4496.5   178.8  4510.7   179.6  4553.4  178.48
  4773.6  177.65  4872.3  179.18  4929.3  179.04  4950.2  178.29  4957.8  176.73
  4964.4  177.41    4972  175.82  4978.6  175.84  4983.5  173.54  4983.9  173.04
  4988.9  173.54  5007.2  174.55  5013.6  176.27  5021.5  176.67    5028  178.69
  5099.4  180.38  5112.3  180.27  5267.6  182.38  5291.4  181.73  5305.8     183
  5347.5  183.48  5447.9  185.17  5518.3  187.27  5526.1  186.91  5710.6  191.69
#Mann= 7 ,-1 , 0
    3937      .1       0  4983.5     .05       0  4988.9      .1       0
  5099.4     .07       0  5112.3      .1       0  5267.6     .07       0
  5347.5      .1       0
Bank Sta=4983.5,4988.9
XS Rating Curve= 0 ,0
Exp/Cntr=0.3,0.1

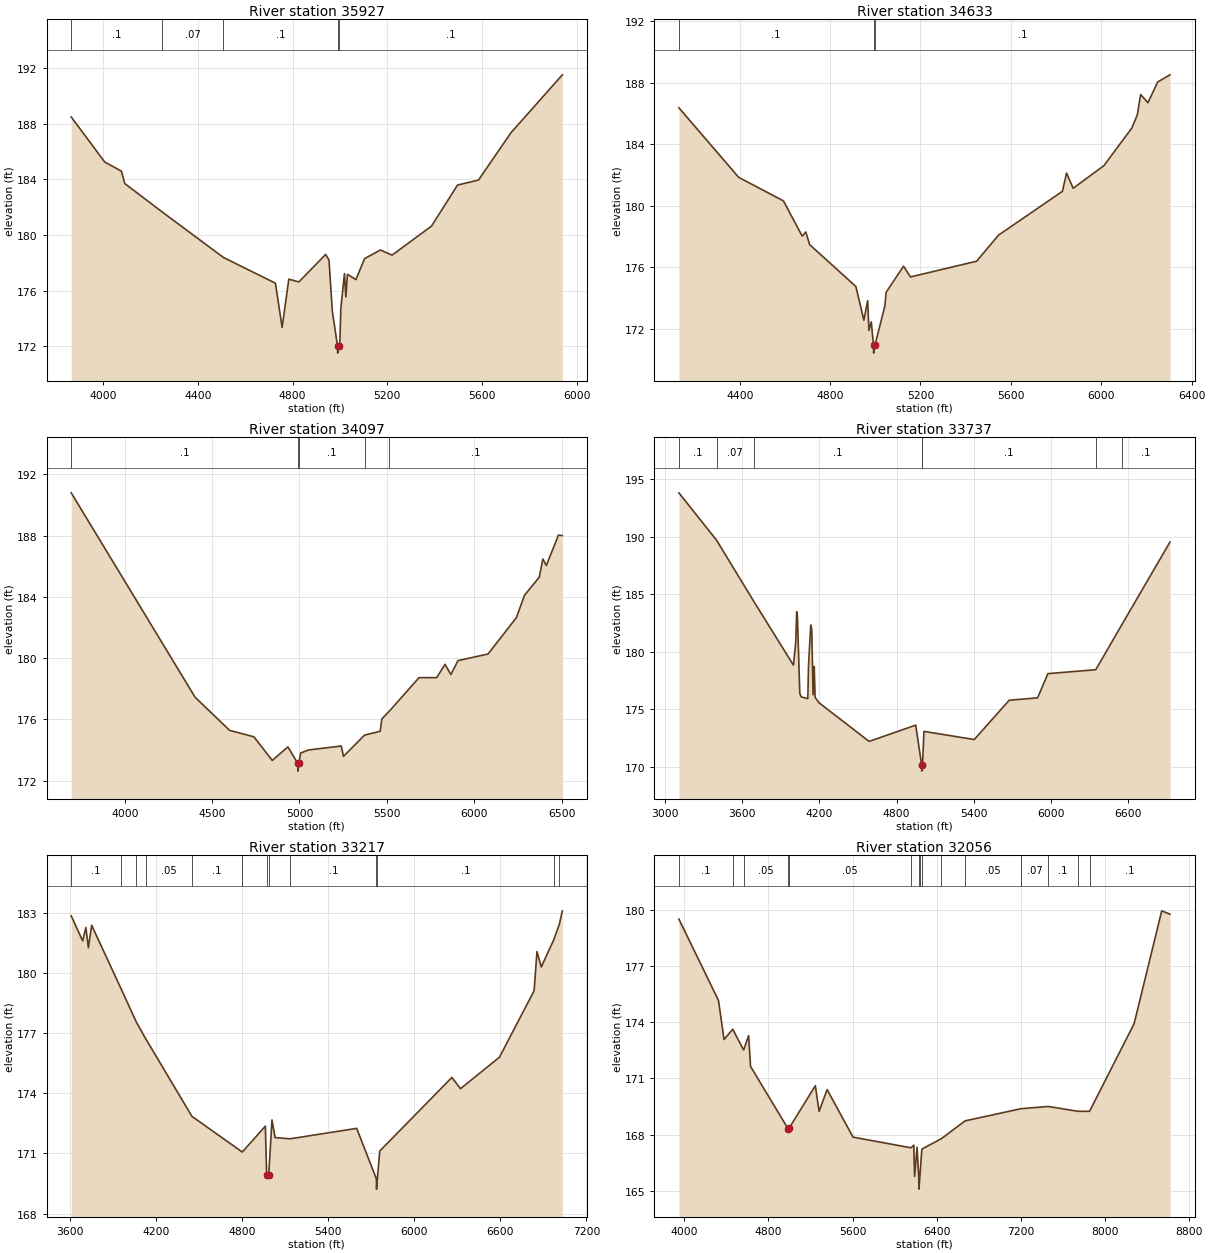
Type RM Length L Ch R = 1 ,35927   ,1294,1294,1294
BEGIN DESCRIPTION:
ROAD CREEK 52.0
END DESCRIPTION:
XS GIS Cut Line= 3
      2505925.03     13451575.03        2505125.       13450775.
      2504325.01     13450275.01
#Sta/Elev= 30
  3864.8  188.49  4006.3  185.25    4077  184.59  4091.1   183.7  4247.2  181.68
    4508  178.38  4727.5  176.53  4755.8  173.35  4784.1  176.82  4826.5  176.62
  4939.7   178.6  4953.8  178.19  4967.9  174.52  4989.9     172  4990.4   171.5
  4995.4     172  4999.2     172  5003.9  174.73  5019.2  177.23  5025.1  175.54
  5031.6  177.17  5067.6  176.79  5104.1   178.3  5171.3  178.92  5220.3  178.55
  5387.1  180.64  5496.8  183.59  5585.3  183.95    5722  187.34  5939.6  191.52
#Mann= 5 ,-1 , 0
  3864.8      .1       0  4247.2     .07       0    4508      .1       0
  4989.9     .05       0  4995.4      .1       0
Bank Sta=4989.9,4995.4
XS Rating Curve= 0 ,0
Exp/Cntr=0.3,0.1

Type RM Length L Ch R = 1 ,34633   ,536,536,536
BEGIN DESCRIPTION:
ROAD CREEK 51.0
END DESCRIPTION:
XS GIS Cut Line= 3
        2506175.     13451274.99        2505825.       13450475.
      2504625.01       13449975.
#Sta/Elev= 30
  4130.9  186.37  4395.6  181.85  4593.6  180.32  4676.7  178.03  4692.6   178.3
  4709.4  177.48  4914.1  174.76  4949.5  172.57  4966.3  173.84  4971.8  171.91
  4982.3  172.46  4992.2  170.93  4992.7  170.43  4998.1  170.93  5042.6   173.5
    5048  174.38  5124.9  176.08  5155.8  175.38  5448.3   176.4  5545.8   178.1
    5828  180.94  5846.4  182.13  5875.6  181.14  6011.6  182.61  6135.6  185.06
  6159.5  185.91  6174.1  187.23  6206.6   186.7  6249.9  188.05  6304.1  188.51
#Mann= 3 ,-1 , 0
  4130.9      .1       0  4992.2     .05       0  4998.1      .1       0
Bank Sta=4992.2,4998.1
XS Rating Curve= 0 ,0
Exp/Cntr=0.3,0.1

Type RM Length L Ch R = 1 ,34097   ,360,360,360
BEGIN DESCRIPTION:
Mapping XS 5ad573d6
END DESCRIPTION:
XS GIS Cut Line= 4
      2506456.02     13451387.01       2506247.7     13450232.54
      2506048.05     13450124.03      2504654.79     13449907.02
#Sta/Elev= 30
  3693.7  190.79  4402.7  177.45  4600.1  175.29  4739.3  174.87    4844  173.33
  4933.7  174.21  4990.6  173.13  4991.1  172.63  4996.6  173.13  5006.5  173.81
    5052  174.01  5238.8  174.27  5252.1   173.6  5372.5  174.98  5461.5  175.23
  5471.6  176.04  5513.9  176.54  5684.1  178.73  5785.3  178.73  5832.9   179.6
  5866.3  178.93  5906.8  179.84  6078.8  180.27  6240.8  182.64    6288  184.11
  6372.3  185.29  6392.6  186.47  6412.8  186.05  6481.7  188.03  6504.1     188
#Mann= 5 ,-1 , 0
  3693.7      .1       0  4990.6     .05       0  4996.6      .1       0
  5372.5     .07       0  5513.9      .1       0
Bank Sta=4990.6,4996.6
XS Rating Curve= 0 ,0
Exp/Cntr=0.3,0.1

Type RM Length L Ch R = 1 ,33737   ,520,520,520
BEGIN DESCRIPTION:
Mapping XS b4936304
END DESCRIPTION:
XS GIS Cut Line= 4
       2506687.4     13451447.35      2507043.32     13450466.41
       2506071.1     13449659.12      2504569.72     13449763.26
#Sta/Elev= 30
  3110.1   193.8  3402.6  189.69  3689.5  184.42  3999.1  178.85  4016.8  180.74
  4024.4  183.48  4029.7  183.21  4048.7  176.39  4060.3  176.09  4110.9  175.94
  4116.2  178.76  4133.8  182.33  4141.5  181.96  4151.7  176.28  4160.8  178.74
  4167.3  176.07  4195.9   175.6  4586.6  172.23  4948.6  173.64    4995  170.15
  4995.5  169.65    5001  170.15  5012.4   173.1    5403  172.39    5674   175.8
  5894.6  176.01  5974.7  178.11  6346.2  178.45  6553.4  182.45  6922.3  189.53
#Mann= 7 ,-1 , 0
  3110.1      .1       0  3402.6     .07       0  3689.5      .1       0
    4995     .05       0    5001      .1       0  6346.2     .07       0
  6553.4      .1       0
Bank Sta=4995,5001
XS Rating Curve= 0 ,0
Exp/Cntr=0.3,0.1

Type RM Length L Ch R = 1 ,33217   ,1161,1161,1161
BEGIN DESCRIPTION:
Mapping XS 88d66417
END DESCRIPTION:
XS GIS Cut Line= 4
      2507440.84     13450957.36      2506878.34     13449743.83
      2506373.13     13449452.16      2504879.16     13449603.12
#Sta/Elev= 30
  3609.4  182.85  3689.2   181.6  3711.6  182.27    3729  181.26  3751.9  182.38
  3957.6   179.2  4063.9  177.54  4127.9  176.73  4450.6  172.85  4801.5  171.07
  4962.4  172.36  4971.4   169.9  4985.5   169.9  5008.6  172.67  5030.2  171.79
  5135.4  171.73  5598.8  172.25  5736.5  169.72    5737  169.22  5742.5  169.72
  5759.6  171.12  6262.2  174.79  6322.5  174.23  6593.8   175.8  6835.1  179.11
  6855.2  181.07  6885.3   180.3  6971.8  181.65  7011.4  182.44  7031.9   183.1
#Mann= 13 ,-1 , 0
  3609.4      .1       0  3957.6     .05       0  4063.9      .1       0
  4127.9     .05       0  4450.6      .1       0  4801.5      .1       0
  4971.4     .05       0  4985.5     .05       0  5135.4      .1       0
  5736.5     .07       0  5742.5      .1       0  6971.8     .07       0
  7011.4      .1       0
Bank Sta=4971.4,4985.5
XS Rating Curve= 0 ,0
Exp/Cntr=0.3,0.1

Type RM Length L Ch R = 1 ,32056   ,593,593,593
BEGIN DESCRIPTION:
Mapping XS b139b0ec
END DESCRIPTION:
XS GIS Cut Line= 4
      2507681.35     13450649.55      2507936.55     13449930.82
      2507311.55     13448701.65      2504889.81     13449415.15
#Sta/Elev= 30
  3950.1  179.52  4326.3  175.17  4379.4  173.08  4461.6  173.63  4565.2  172.52
  4612.9  173.29  4631.1  171.64  4987.5  168.31  4999.8  168.36  5246.6  170.61
  5282.3  169.24  5358.8   170.4  5604.9  167.86  6155.6  167.29    6182  167.43
  6189.6  165.76  6213.2  167.32  6230.7  165.58  6231.2  165.08  6237.5  165.58
  6258.9  167.22  6444.8  167.78  6669.8  168.73  7200.3  169.38  7459.3   169.5
  7743.7  169.24  7852.2  169.24  8275.9  173.93    8538  179.96  8616.4  179.78
#Mann= 15 ,-1 , 0
  3950.1      .1       0  4461.6    .035       0  4565.2     .05       0
  4987.5     .05       0  4999.8     .05       0  6155.6    .035       0
  6230.7    .035       0  6237.5    .035       0  6258.9     .05       0
  6444.8     .07       0  6669.8     .05       0  7200.3     .07       0
  7459.3      .1       0  7743.7     .05       0  7852.2      .1       0
Bank Sta=4987.5,4999.8
XS Rating Curve= 0 ,0
Exp/Cntr=0.3,0.1