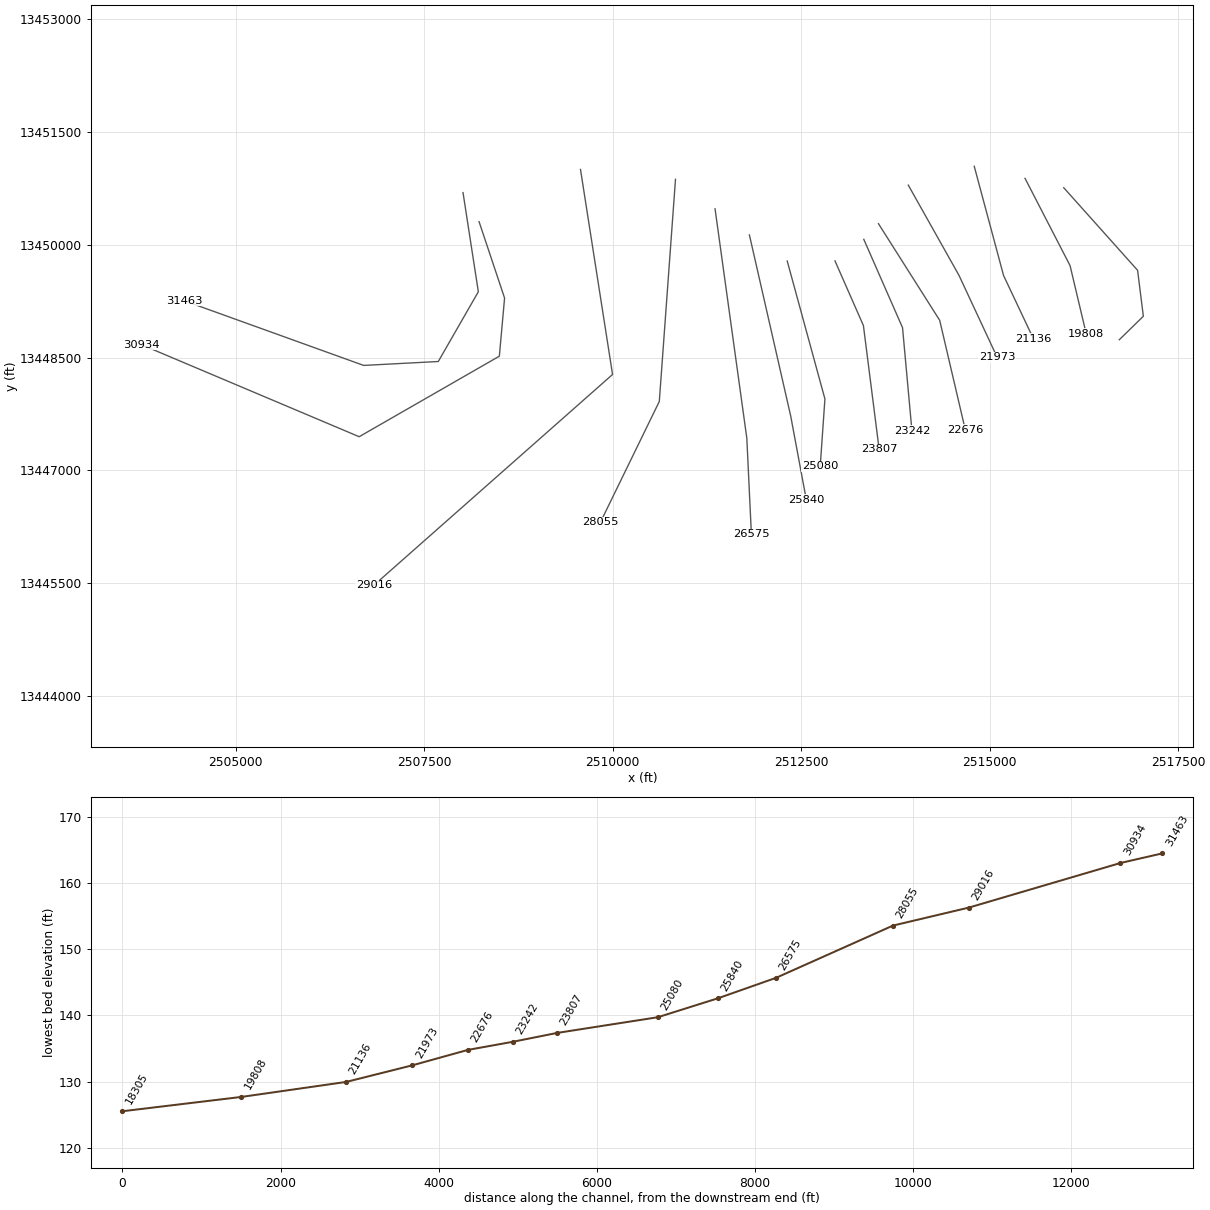
HEC-RAS study ROAD CREEK.prj: ROAD CREEK Base Level Engineering

--- ROAD CREEK.g01 (geometry) --- (continued)

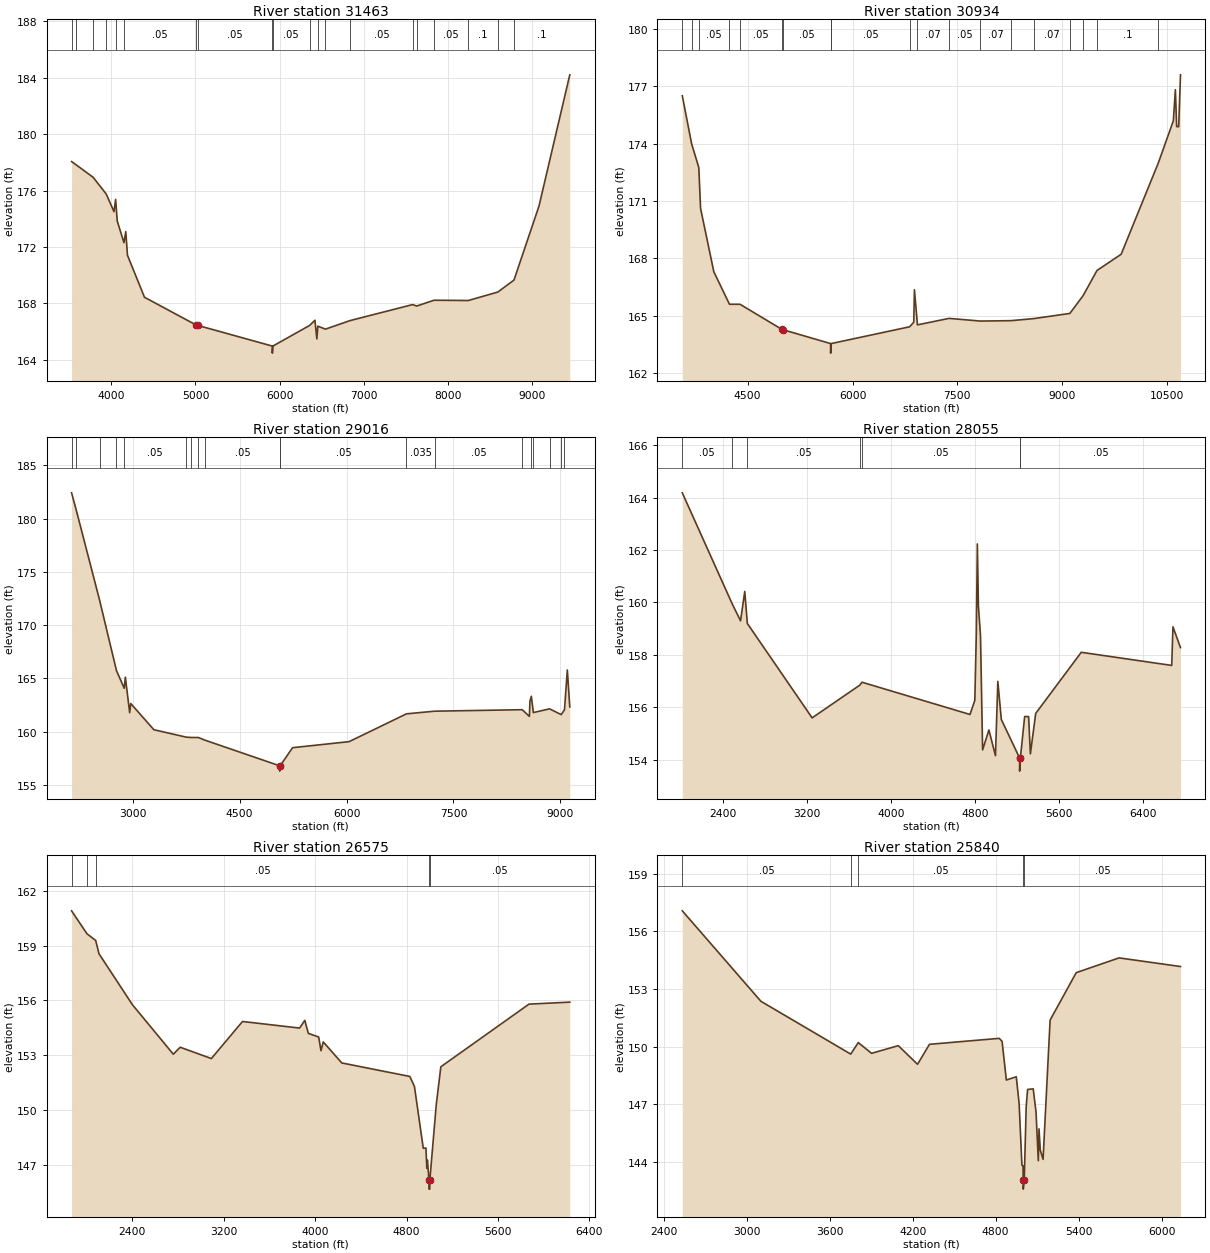
Type RM Length L Ch R = 1 ,31463   ,529,529,529
BEGIN DESCRIPTION:
Mapping XS 73acd4cd
END DESCRIPTION:
XS GIS Cut Line= 5
      2508013.76     13450691.76      2508216.88     13449374.03
      2507685.63     13448446.95      2506696.05     13448394.87
      2504315.88     13449254.23
#Sta/Elev= 30
  3527.1  178.06  3583.8  177.82  3784.3  176.94  3938.9  175.76  4031.2  174.51
  4050.6  175.38  4070.2  173.84    4150  172.31  4171.4   173.1  4191.6  171.42
    4394  168.44  5009.1  166.47  5030.8  166.44  5913.6  164.98  5914.1  164.48
  5920.4  164.98  6356.5  166.44  6420.2  166.81  6443.5  165.49  6454.7  166.39
  6545.6  166.18  6840.1  166.79  7581.4  167.92    7631  167.82  7836.8  168.23
  8244.6  168.21  8595.1  168.81  8787.1  169.66  9084.6  174.91  9450.4  184.21
#Mann= 20 ,-1 , 0
  3527.1     .07       0  3583.8      .1       0  3784.3     .05       0
  3938.9      .1       0  4050.6    .035       0    4150     .05       0
  5009.1     .05       0  5030.8     .05       0  5913.6    .035       0
  5920.4     .05       0  6356.5    .035       0  6454.7     .05       0
  6545.6     .07       0  6840.1     .05       0  7581.4     .07       0
    7631      .1       0  7836.8     .05       0  8244.6      .1       0
  8595.1     .07       0  8787.1      .1       0
Bank Sta=5009.1,5030.8
XS Rating Curve= 0 ,0
Exp/Cntr=0.3,0.1

Type RM Length L Ch R = 1 ,30934   ,1918,1918,1918
BEGIN DESCRIPTION:
Mapping XS 58d10e9b
END DESCRIPTION:
XS GIS Cut Line= 5
      2508226.47     13450305.83      2508565.02     13449290.19
      2508495.58     13448517.62      2506636.12     13447447.28
      2503747.14     13448670.65
#Sta/Elev= 30
  3564.4  176.51  3697.8     174  3800.8  172.75    3826  170.61  4015.8  167.29
  4239.7  165.59  4390.4  165.59  4991.6  164.27  5001.6  164.26  5686.9  163.53
  5687.4  163.03  5693.7  163.53    6818  164.41  6876.7  164.65  6885.9  166.35
  6929.6  164.51  7380.9  164.85  7828.7  164.71  8265.9  164.73  8596.6  164.84
    9110  165.11  9299.7  166.04  9498.7  167.36  9844.4  168.21 10374.8  172.98
   10591   175.2 10620.1  176.83 10638.3   174.9 10667.4  174.89 10693.5  177.61
#Mann= 19 ,-1 , 0
  3564.4     .05       0  3697.8    .035       0  3800.8     .05       0
  4239.7      .1       0  4390.4     .05       0  4991.6     .05       0
  5001.6     .05       0  5686.9    .035       0  5693.7     .05       0
    6818    .035       0  6929.6     .07       0  7380.9     .05       0
  7828.7     .07       0  8265.9    .035       0  8596.6     .07       0
    9110      .1       0  9299.7     .07       0  9498.7      .1       0
 10374.8     .07       0
Bank Sta=4991.6,5001.6
XS Rating Curve= 0 ,0
Exp/Cntr=0.3,0.1

Type RM Length L Ch R = 1 ,29016   ,961,961,961
BEGIN DESCRIPTION:
Mapping XS 7e274ebf
END DESCRIPTION:
XS GIS Cut Line= 3
      2509571.97     13451000.23      2509997.31     13448274.57
      2506829.71     13445471.06
#Sta/Elev= 30
  2143.2  182.43  2207.2  180.85  2538.4  172.29  2773.1  165.73    2882  164.07
  2897.4  165.12  2958.2  161.78  2973.5  162.64  3297.5  160.18    3753  159.48
  3820.9  159.45  3920.7  159.45  4017.8  159.19  5062.2  156.79  5062.7  156.29
  5069.2  156.79  5243.1  158.49  6036.9  159.06  6840.9  161.67  7235.1  161.92
  8464.5  162.06  8565.4  161.43  8572.9  162.85  8592.5  163.32  8621.2  161.79
  8848.6  162.14  9011.4   161.6  9057.6  162.05  9097.4  165.79  9131.9  162.32
#Mann= 19 ,-1 , 0
  2143.2     .05       0  2207.2     .07       0  2538.4     .05       0
  2773.1    .035       0    2882     .05       0    3753    .035       0
  3820.9     .05       0  3920.7    .035       0  4017.8     .05       0
  5062.2    .035       0  5069.2     .05       0  6840.9    .035       0
  7235.1     .05       0  8464.5    .035       0  8592.5      .1       0
  8621.2     .07       0  8848.6     .05       0  9011.4      .1       0
  9057.6     .05       0
Bank Sta=5062.2,5069.2
XS Rating Curve= 0 ,0
Exp/Cntr=0.3,0.1

Type RM Length L Ch R = 1 ,28055   ,1480,1480,1480
BEGIN DESCRIPTION:
Mapping XS 323b0aba
END DESCRIPTION:
XS GIS Cut Line= 3
      2510832.23     13450868.68      2510617.45     13447915.52
       2509836.3     13446309.81
#Sta/Elev= 30
  2013.9  164.18  2490.2  159.94    2569   159.3  2609.1  160.42  2633.6   159.2
  3250.8   155.6  3705.8  156.85  3725.4  156.96  4754.8  155.73  4800.9  156.27
    4815  158.77    4825  162.23    4835  159.88  4855.1  158.73  4875.1  154.38
    4935  155.14  4997.7  154.16  5020.1  156.99  5053.3  155.54  5227.5  154.07
    5228  153.57  5234.9  154.07  5275.7  155.65  5313.3  155.65  5330.3  154.23
  5380.9  155.77  5814.9   158.1  6676.9   157.6  6688.5  159.07  6760.5  158.28
#Mann= 7 ,-1 , 0
  2013.9     .05       0  2490.2    .035       0  2633.6     .05       0
  3705.8    .035       0  3725.4     .05       0  5227.5    .035       0
  5234.9     .05       0
Bank Sta=5227.5,5234.9
XS Rating Curve= 0 ,0
Exp/Cntr=0.3,0.1

Type RM Length L Ch R = 1 ,26575   ,735,735,735
BEGIN DESCRIPTION:
Mapping XS bacb0692
END DESCRIPTION:
XS GIS Cut Line= 3
        2511357.     13450476.33      2511778.47     13447427.23
      2511839.09     13446148.26
#Sta/Elev= 30
  1869.5  160.91  2004.7  159.65  2080.3  159.29  2109.3  158.56  2401.7  155.77
  2759.2  153.06  2819.8  153.44  3092.3  152.82  3364.9  154.85  3863.9  154.49
    3910  154.91  3940.8   154.2  4031.2     154  4051.4  153.25  4071.6  153.73
  4233.3  152.58  4828.7  151.84  4869.1  151.29  4946.2  147.91  4969.8  147.92
  4977.3  146.81  4982.4  147.26  4996.1  146.17  4996.6  145.67  5003.2  145.67
  5003.7  146.17  5059.9   150.3    5100  152.37  5870.9   155.8    6228  155.91
#Mann= 5 ,-1 , 0
  1869.5     .05       0  2004.7    .035       0  2080.3     .05       0
  4996.1    .035       0  5003.7     .05       0
Bank Sta=4996.1,5003.7
XS Rating Curve= 0 ,0
Exp/Cntr=0.3,0.1

Type RM Length L Ch R = 1 ,25840   ,760,760,760
BEGIN DESCRIPTION:
Mapping XS a85607f5
END DESCRIPTION:
XS GIS Cut Line= 3
      2511812.73      13450129.1      2512359.95      13447725.2
      2512568.01     13446608.31
#Sta/Elev= 30
  2534.6  157.07  3102.9  152.36  3752.2  149.61  3806.7  150.21  3902.8  149.65
  4095.9  150.05  4235.2  149.08  4321.3  150.12  4825.9  150.43  4846.4  150.27
  4877.1  148.26  4948.9  148.43  4969.4  147.05  4989.9  143.82  4997.5   143.8
  4998.9  143.08  4999.4  142.58  5006.7  143.08  5020.5  146.85  5030.7  147.77
  5071.4   147.8  5091.7   146.6  5108.2  144.06  5113.3  145.72  5122.3  144.62
  5142.6  144.13  5193.5  151.38  5382.1  153.85  5691.9  154.62  6136.1  154.17
#Mann= 5 ,-1 , 0
  2534.6     .05       0  3752.2     .07       0  3806.7     .05       0
  4998.9    .035       0  5006.7     .05       0
Bank Sta=4998.9,5006.7
XS Rating Curve= 0 ,0
Exp/Cntr=0.3,0.1

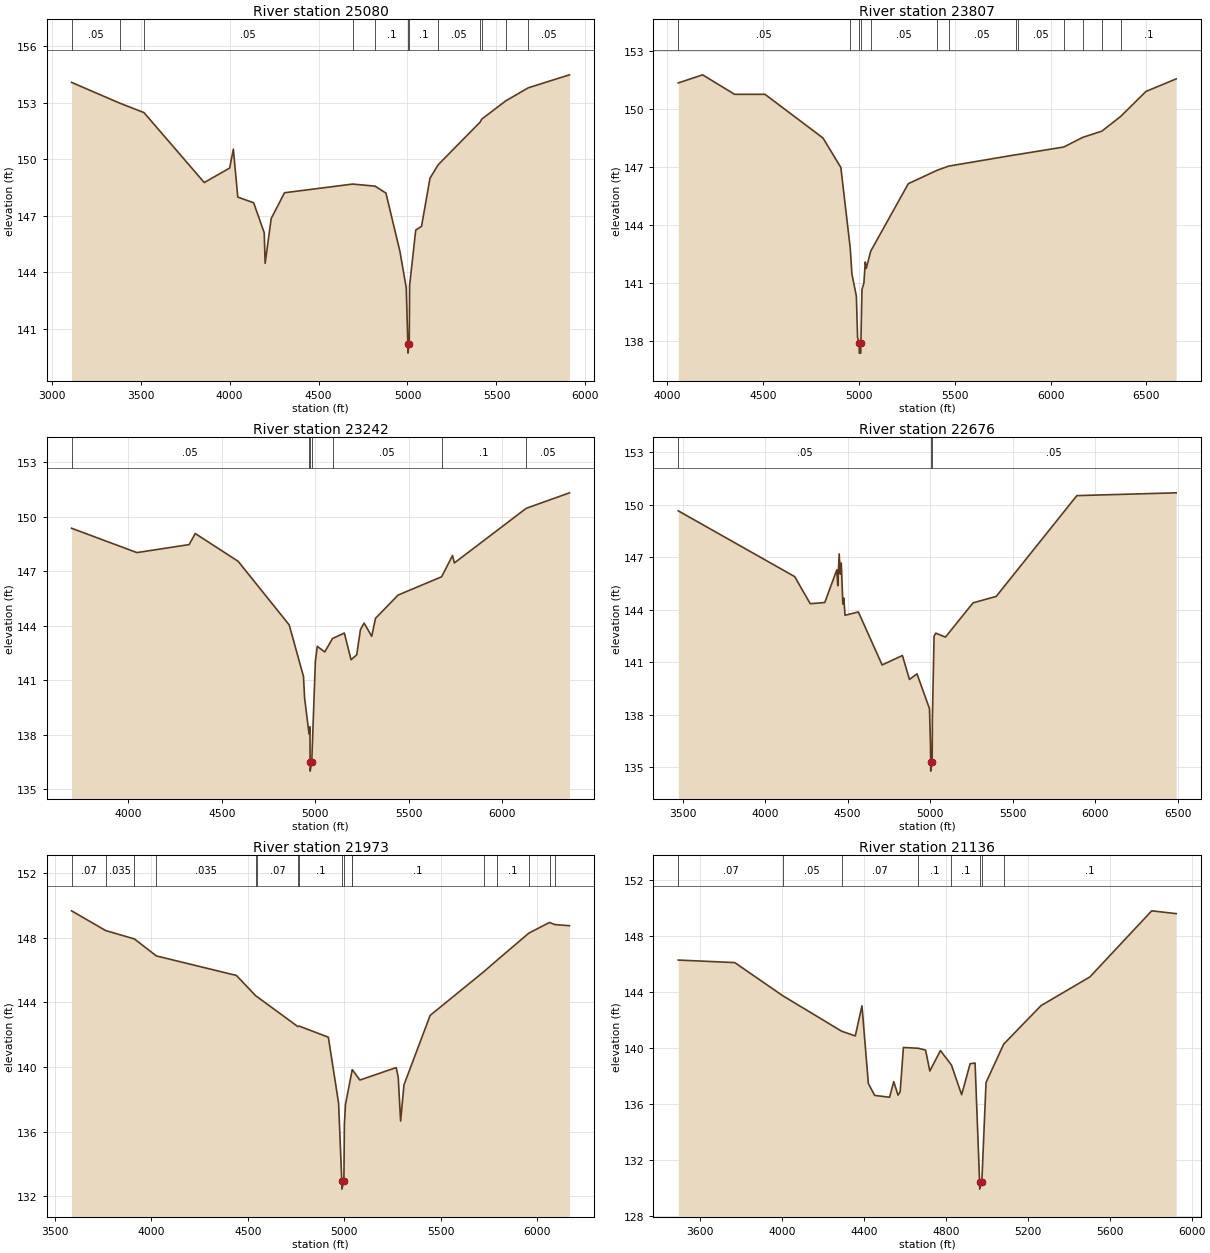
Type RM Length L Ch R = 1 ,25080   ,1273,1273,1273
BEGIN DESCRIPTION:
Mapping XS f250bd65
END DESCRIPTION:
XS GIS Cut Line= 3
      2512314.47      13449782.3      2512814.47     13447948.98
      2512751.97     13447053.14
#Sta/Elev= 30
    3112  154.07  3382.4  152.97  3518.9  152.47  3857.9  148.76  4000.6  149.53
  4021.3  150.53  4046.2  147.99  4135.4  147.69  4194.8   146.1    4200  144.48
  4233.8  146.85  4308.8  148.22  4691.6  148.68  4817.9  148.57  4878.9   148.2
  4957.3  145.12  4992.9  143.19  5002.1  140.22  5002.6  139.72  5009.9  140.22
  5011.8   143.3  5046.3  146.24  5078.9  146.44  5126.5  148.99  5172.1   149.7
  5408.8  151.97  5416.9  152.12  5552.3  153.09  5678.4  153.78  5910.3  154.47
#Mann= 12 ,-1 , 0
    3112     .05       0  3382.4     .07       0  3518.9     .05       0
  4691.6     .07       0  4817.9      .1       0  5002.1     .05       0
  5009.9      .1       0  5172.1     .05       0  5408.8      .1       0
  5416.9     .05       0  5552.3     .07       0  5678.4     .05       0
Bank Sta=5002.1,5009.9
XS Rating Curve= 0 ,0
Exp/Cntr=0.3,0.1

Type RM Length L Ch R = 1 ,23807   ,565,565,565
BEGIN DESCRIPTION:
ROAD CREEK 42.0
END DESCRIPTION:
XS GIS Cut Line= 3
      2512948.17     13449784.01        2513325.       13448925.
      2513533.93     13447278.73
#Sta/Elev= 30
  4057.7  151.35  4184.5  151.77  4351.5  150.76  4510.1  150.76  4812.3   148.5
  4905.8  146.97  4954.8  142.79  4963.4  141.46  4986.8   140.3    4993  138.17
  5001.4  137.85  5001.9  137.35  5009.8  137.35  5010.3  137.85  5015.9  140.64
    5026  140.98  5033.2  142.07  5038.3  141.74  5061.9  142.64  5257.8  146.13
  5409.4  146.83  5468.6  147.04  5818.9  147.63  5827.7  147.64  6068.9  148.03
    6168  148.53  6267.1  148.85  6366.1  149.62  6497.7  150.91  6655.2  151.56
#Mann= 13 ,-1 , 0
  4057.7     .05       0  4954.8      .1       0  5001.4     .05       0
  5010.3      .1       0  5061.9     .05       0  5409.4     .07       0
  5468.6     .05       0  5818.9      .1       0  5827.7     .05       0
  6068.9     .07       0    6168     .05       0  6267.1     .07       0
  6366.1      .1       0
Bank Sta=5001.4,5010.3
XS Rating Curve= 0 ,0
Exp/Cntr=0.3,0.1

Type RM Length L Ch R = 1 ,23242   ,566,566,566
BEGIN DESCRIPTION:
Mapping XS 709d2491
END DESCRIPTION:
XS GIS Cut Line= 3
      2513330.11     13450070.78      2513843.99     13448897.18
      2513968.99     13447522.23
#Sta/Elev= 30
  3696.6  149.37  4046.1  148.03  4325.2  148.47  4357.9  149.08  4587.2  147.55
  4860.1  144.05  4936.5  141.21  4942.4  140.03  4966.1  138.04  4971.3  138.44
  4971.7   136.5  4972.2     136  4980.7   136.5    5000  142.05  5010.1  142.87
  5050.3  142.56  5091.6   143.3  5155.1   143.6  5190.8  142.13    5221   142.4
    5241  143.79  5260.6  144.15  5301.3  143.42  5321.4  144.41  5441.9  145.69
  5675.2   146.7  5733.1  147.87  5743.1  147.46  6127.6  150.47  6358.4  151.32
#Mann= 7 ,-1 , 0
  3696.6     .05       0  4966.1      .1       0  4971.7     .05       0
  4980.7      .1       0  5091.6     .05       0  5675.2      .1       0
  6127.6     .05       0
Bank Sta=4971.7,4980.7
XS Rating Curve= 0 ,0
Exp/Cntr=0.3,0.1

Type RM Length L Ch R = 1 ,22676   ,703,703,703
BEGIN DESCRIPTION:
Mapping XS a89c5b53
END DESCRIPTION:
XS GIS Cut Line= 3
      2513524.56      13450279.1      2514337.05     13448994.41
      2514677.33     13447536.03
#Sta/Elev= 30
  3473.4  149.66    4179   145.9  4273.1  144.35  4361.3  144.42  4434.2  146.29
  4440.1  145.38  4448.5   147.2  4455.4  146.04  4461.3  146.68  4470.7  144.33
  4476.6  144.67    4484  143.69  4564.8  143.88  4708.8  140.85  4831.8  141.39
  4874.4  140.02    4920  140.34  4995.7  138.36  5002.2  136.17  5002.8  135.28
  5003.3  134.78    5012  135.28  5013.4  137.78  5023.7  142.49  5033.9  142.67
  5092.4  142.44  5259.8   144.4  5400.5  144.77    5889  150.53    6491  150.69
#Mann= 3 ,-1 , 0
  3473.4     .05       0  5002.8     .05       0    5012     .05       0
Bank Sta=5002.8,5012
XS Rating Curve= 0 ,0
Exp/Cntr=0.3,0.1

Type RM Length L Ch R = 1 ,21973   ,837,837,837
BEGIN DESCRIPTION:
Mapping XS 34ac1279
END DESCRIPTION:
XS GIS Cut Line= 3
      2513920.42     13450791.35      2514594.01     13449589.99
      2515100.42     13448500.87
#Sta/Elev= 30
  3587.8  149.67  3764.2  148.45  3913.2  147.93  4026.9  146.88  4441.7  145.67
  4541.7  144.41    4548  144.36  4759.5  142.51    4766  142.54  4917.6  141.85
  4970.6  137.77  4987.3  132.95  4987.8  132.45    4998  132.95  5000.6  136.45
  5006.1  137.68  5041.4  139.84  5041.5  139.84  5080.9   139.2  5268.9  139.97
  5279.4  139.39  5291.8  136.66  5309.2   138.9  5444.8   143.2  5722.3   145.9
  5791.8  146.62  5955.9  148.29  6062.9  148.95  6090.1  148.82  6166.2  148.75
#Mann= 17 ,-1 , 0
  3587.8     .07       0  3764.2    .035       0  3913.2     .07       0
  4026.9    .035       0  4541.7     .05       0    4548     .07       0
  4759.5     .05       0    4766      .1       0  4987.3     .05       0
    4998      .1       0  5041.4     .07       0  5041.5      .1       0
  5722.3    .035       0  5791.8      .1       0  5955.9     .07       0
  6062.9    .035       0  6090.1     .07       0
Bank Sta=4987.3,4998
XS Rating Curve= 0 ,0
Exp/Cntr=0.3,0.1

Type RM Length L Ch R = 1 ,21136   ,1328,1328,1328
BEGIN DESCRIPTION:
Mapping XS a6531d8f
END DESCRIPTION:
XS GIS Cut Line= 3
      2514795.41     13451041.35      2515184.29     13449589.99
        2515580.     13448749.98
#Sta/Elev= 30
  3493.5  146.27  3769.2  146.09  4003.4  143.73  4290.9   141.2  4357.7  140.86
  4390.4  143.01  4421.5  137.47  4452.5  136.62    4525  136.49  4545.7   137.6
  4566.4  136.64  4576.8  136.87  4592.7  140.04  4666.3  139.98    4701  139.85
  4721.7  138.36  4773.5  139.82  4827.1  138.79    4877  136.67  4918.4  138.88
  4942.6  138.93  4964.8  130.44  4965.3  129.94  4975.6  130.44  4996.1  137.54
  5082.5  140.28  5264.5  143.02  5503.4  145.07  5805.1  149.78  5924.6  149.58
#Mann= 8 ,-1 , 0
  3493.5     .07       0  4003.4     .05       0  4290.9     .07       0
  4666.3      .1       0  4827.1      .1       0  4964.8     .05       0
  4975.6      .1       0  5082.5      .1       0
Bank Sta=4964.8,4975.6
XS Rating Curve= 0 ,0
Exp/Cntr=0.3,0.1

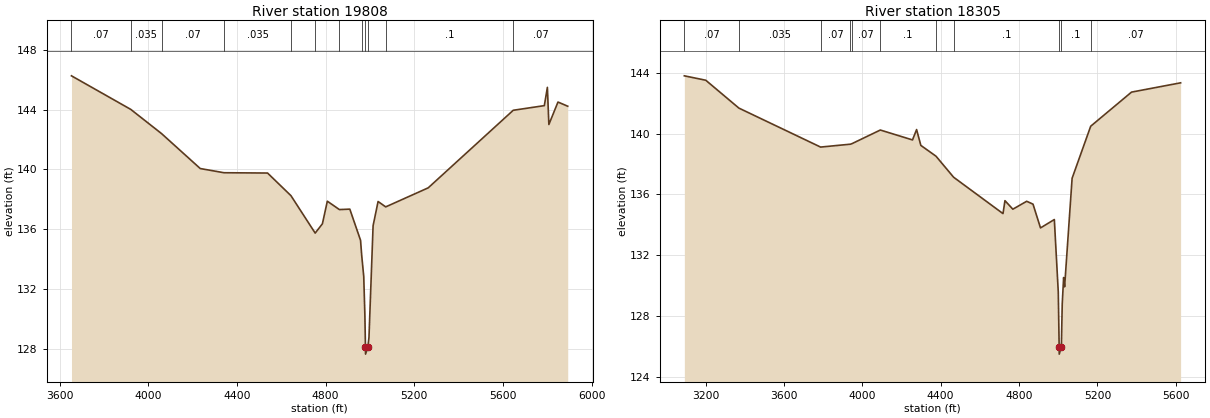
Type RM Length L Ch R = 1 ,19808   ,1503,1503,1503
BEGIN DESCRIPTION:
Mapping XS 12c56e8e
END DESCRIPTION:
XS GIS Cut Line= 3
      2515469.02     13450881.64      2516066.23     13449721.94
      2516281.51     13448812.21
#Sta/Elev= 30
    3653  146.25  3920.4  144.01  4059.7  142.39  4234.1  140.06  4341.3  139.78
  4537.8  139.76  4643.3  138.25  4752.7  135.75  4785.3  136.37  4807.5  137.88
    4862  137.32    4909  137.35  4957.4  135.27  4962.7  134.25  4971.8  132.86
  4976.9   130.3  4979.5  128.17    4980  127.67  4990.7  128.17  4995.4  128.78
    5014  136.24  5036.5  137.86  5070.9   137.5  5262.6  138.77  5646.4  143.95
  5786.7  144.26  5800.5  145.48  5807.2     143  5848.3   144.5  5892.3  144.22
#Mann= 12 ,-1 , 0
    3653     .07       0  3920.4    .035       0  4059.7     .07       0
  4341.3    .035       0  4643.3     .07       0  4752.7      .1       0
    4862      .1       0  4962.7      .1       0  4979.5     .05       0
  4990.7      .1       0  5070.9      .1       0  5646.4     .07       0
Bank Sta=4979.5,4990.7
XS Rating Curve= 0 ,0
Exp/Cntr=0.3,0.1

Type RM Length L Ch R = 1 ,18305   ,293,293,293
BEGIN DESCRIPTION:
Mapping XS e5ef4f74
END DESCRIPTION:
XS GIS Cut Line= 4
      2515982.89     13450756.68      2516962.07     13449659.44
      2517038.46     13449048.33      2516719.49     13448736.29
#Sta/Elev= 30
    3092  143.79  3201.3   143.5  3370.4  141.67  3787.4  139.11  3939.8   139.3
  3948.4  139.34  4092.2  140.23  4256.4  139.58  4277.3  140.26    4299  139.22
  4376.4  138.51  4466.2  137.13  4718.3  134.74  4728.3  135.59  4768.6  135.03
  4839.2  135.55  4871.5  135.36  4909.7   133.8  4980.3  134.35  5000.4  129.59
  5004.9  126.01  5005.4  125.51  5016.2  126.01  5020.6  128.81  5027.7  130.54
  5032.7  129.93    5071  137.06  5165.9  140.48  5374.2  142.72  5624.7  143.33
#Mann= 11 ,-1 , 0
    3092     .07       0  3370.4    .035       0  3787.4     .07       0
  3939.8    .035       0  3948.4     .07       0  4092.2      .1       0
  4376.4     .07       0  4466.2      .1       0  5004.9     .05       0
  5016.2      .1       0  5165.9     .07       0
Bank Sta=5004.9,5016.2
XS Rating Curve= 0 ,0
Exp/Cntr=0.3,0.1