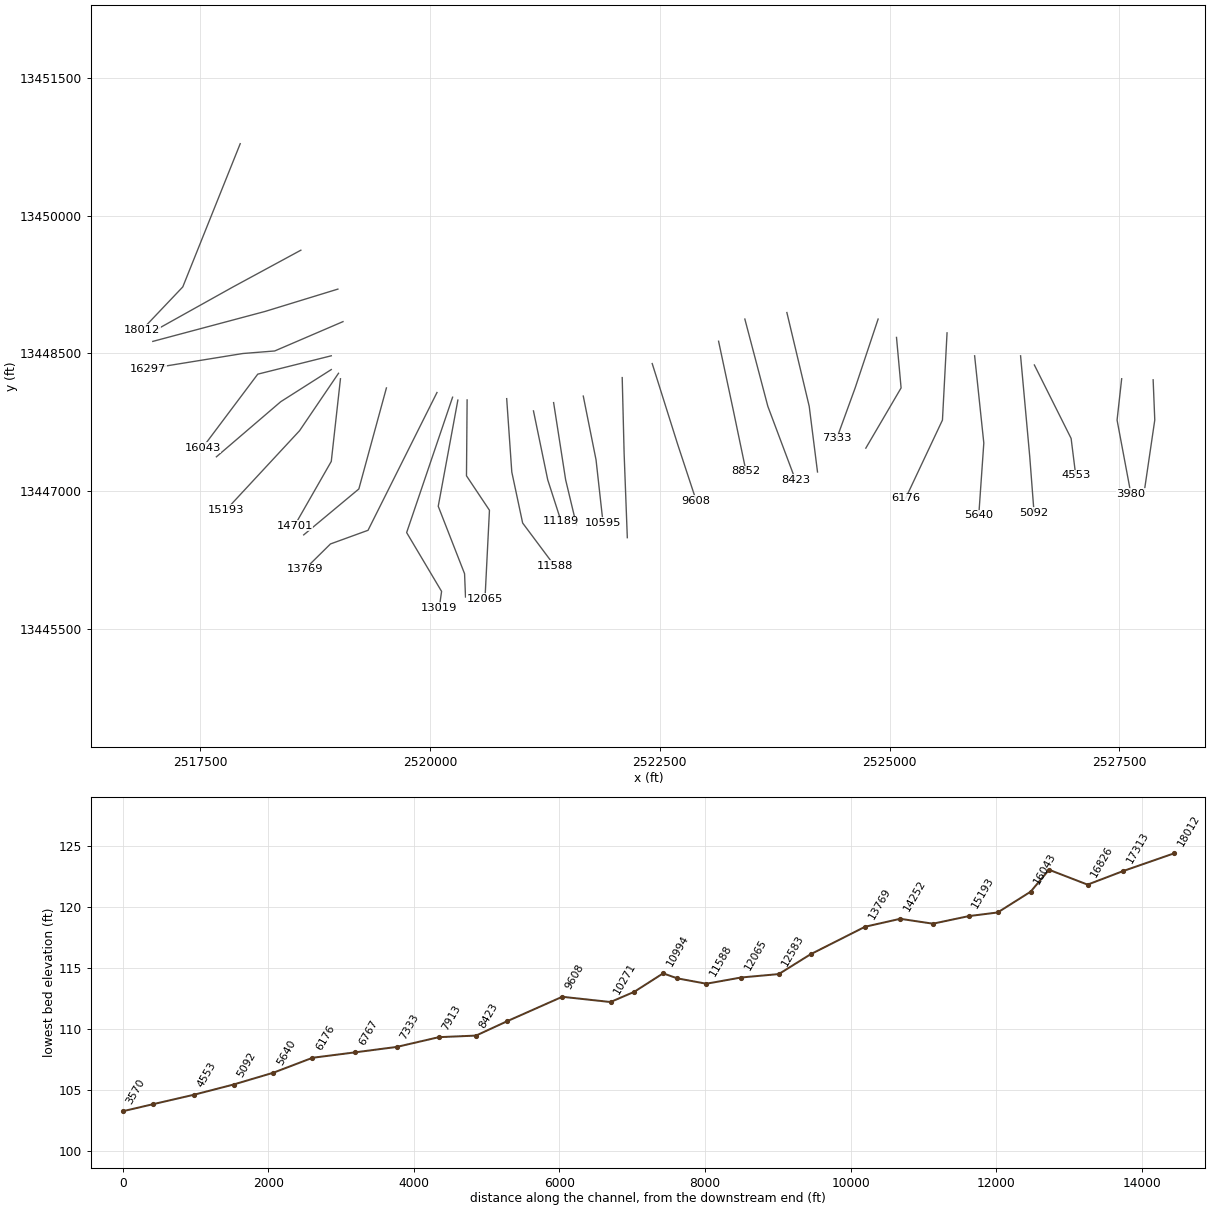
HEC-RAS study ROAD CREEK.prj: ROAD CREEK Base Level Engineering

--- ROAD CREEK.g01 (geometry) --- (continued)

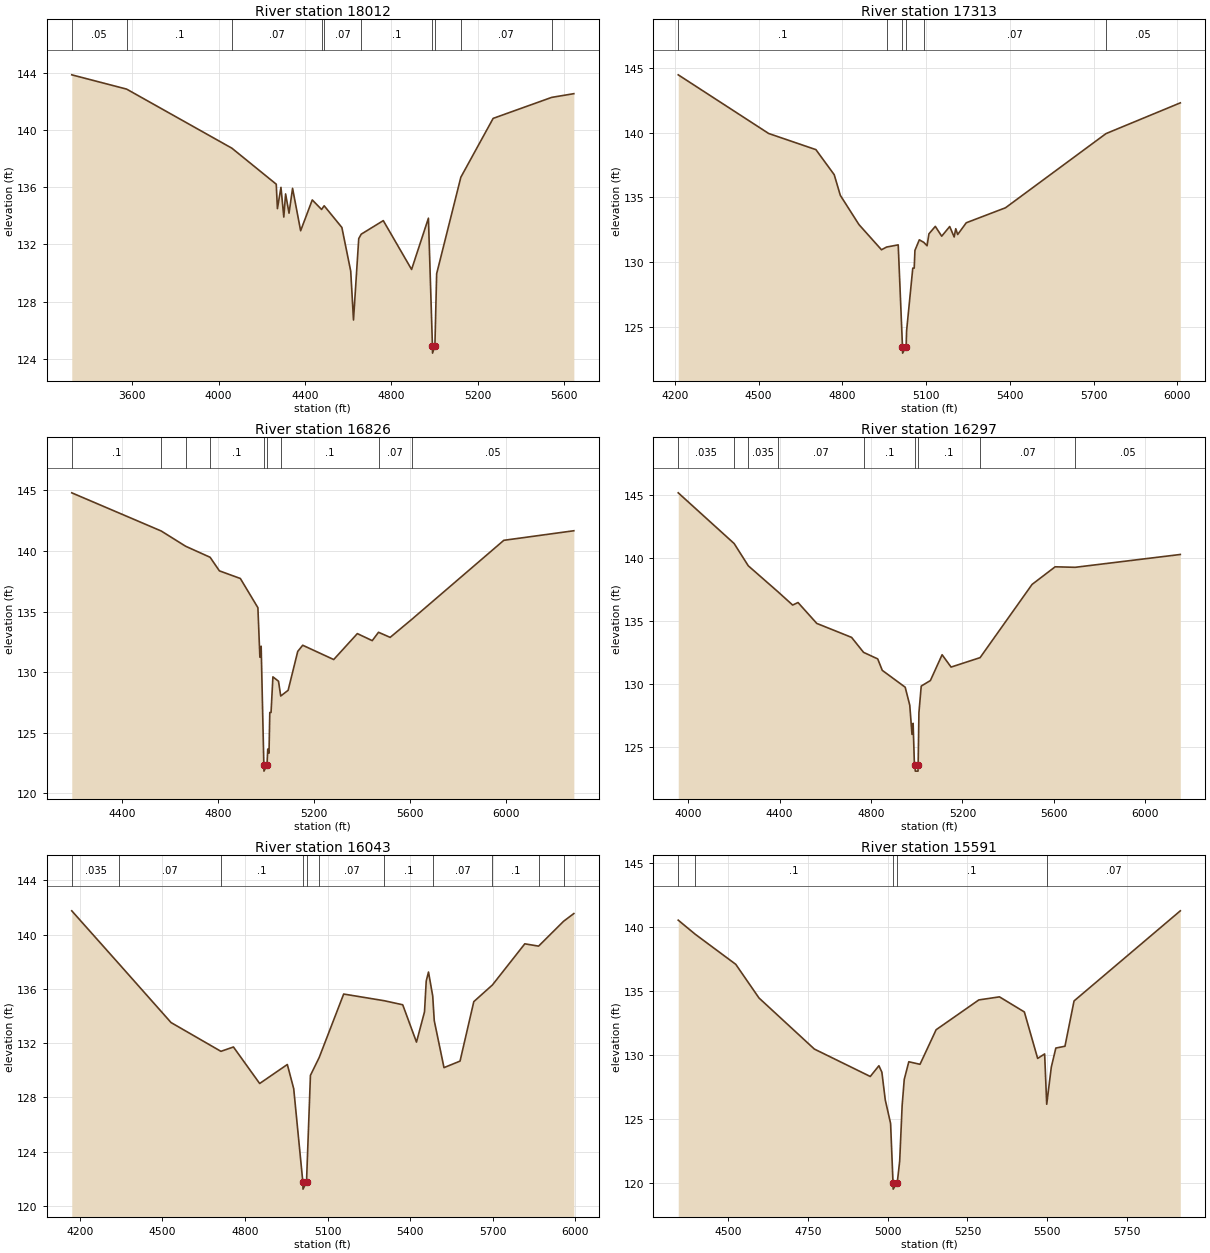
Type RM Length L Ch R = 1 ,18012   ,699,699,699
BEGIN DESCRIPTION:
Mapping XS 7eab1466
END DESCRIPTION:
XS GIS Cut Line= 3
      2517934.28     13450784.43      2517309.29     13449225.01
      2516864.82     13448756.63
#Sta/Elev= 30
    3320  143.88  3574.1  142.88  4061.9  138.74  4267.2  136.22  4272.6  134.51
    4289     136  4302.2  133.92  4310.5  135.54  4326.4  134.19  4342.8  135.93
  4380.2  132.96    4434  135.12  4477.2  134.45  4489.1  134.71  4571.2  133.19
  4612.2  130.13    4625  126.71  4649.3  132.41  4660.7  132.72    4763  133.67
  4894.1  130.25  4972.1  133.84  4990.7  124.89  4991.2  124.39  5002.1  124.89
  5010.2  129.95  5122.3  136.71  5271.9  140.83    5543   142.3  5645.7  142.56
#Mann= 10 ,-1 , 0
    3320     .05       0  3574.1      .1       0  4061.9     .07       0
  4477.2      .1       0  4489.1     .07       0  4660.7      .1       0
  4990.7     .05       0  5002.1      .1       0  5122.3     .07       0
    5543     .05       0
Bank Sta=4990.7,5002.1
XS Rating Curve= 0 ,0
Exp/Cntr=0.3,0.1

Type RM Length L Ch R = 1 ,17313   ,487,487,487
BEGIN DESCRIPTION:
Mapping XS 612ba84f
END DESCRIPTION:
XS GIS Cut Line= 3
      2518594.04     13449624.73      2517850.96     13449221.94
      2517018.81     13448757.32
#Sta/Elev= 30
    4212  144.48  4535.9  139.94  4705.1  138.69  4770.7  136.75  4792.6  135.15
  4859.3  132.89    4940  130.94  4958.3  131.15  4999.9  131.32  5015.2  123.44
  5015.7  122.94  5028.3  123.44  5029.9  124.66  5052.1  129.52  5057.2  129.52
  5059.8  130.89  5075.5  131.71  5091.7  131.51  5103.2  131.25  5109.9  132.17
  5132.8  132.75  5155.7  131.99  5184.3  132.74  5200.3  131.93    5206  132.57
  5212.9  132.12  5243.7  133.03  5384.2  134.19  5744.1  139.93  6010.3  142.31
#Mann= 6 ,-1 , 0
    4212      .1       0  4958.3      .1       0  5015.2     .05       0
  5028.3      .1       0  5091.7     .07       0  5744.1     .05       0
Bank Sta=5015.2,5028.3
XS Rating Curve= 0 ,0
Exp/Cntr=0.3,0.1

Type RM Length L Ch R = 1 ,16826   ,529,529,529
BEGIN DESCRIPTION:
Mapping XS f4c0b0b6
END DESCRIPTION:
XS GIS Cut Line= 3
      2518996.82     13449201.11      2518205.12     13448958.05
      2516982.92     13448631.67
#Sta/Elev= 30
  4191.6   144.8  4564.5  141.65  4666.4  140.39  4768.4  139.48  4807.1  138.36
  4894.4  137.73  4967.6  135.32  4975.9  131.23  4981.2  132.14  4992.4  122.33
  4992.9  121.83  5005.5  122.33  5008.7  123.65  5013.9  123.31  5017.2  126.67
  5022.4  126.67  5030.2  129.61  5053.5  129.25  5062.8  128.03  5093.6   128.5
  5133.7  131.71  5154.4  132.22  5283.7  131.04  5382.2  133.18  5444.3   132.6
  5470.4  133.29    5519  132.87  5608.2  134.34  5992.8  140.88  6284.8  141.67
#Mann= 9 ,-1 , 0
  4191.6      .1       0  4564.5    .035       0  4666.4     .07       0
  4768.4      .1       0  4992.4     .05       0  5005.5      .1       0
  5062.8      .1       0  5470.4     .07       0  5608.2     .05       0
Bank Sta=4992.4,5005.5
XS Rating Curve= 0 ,0
Exp/Cntr=0.3,0.1

Type RM Length L Ch R = 1 ,16297   ,254,254,254
BEGIN DESCRIPTION:
Mapping XS c933a944
END DESCRIPTION:
XS GIS Cut Line= 4
      2519052.39     13448846.96      2518309.29     13448527.49
      2517962.07     13448499.72      2516934.28     13448333.05
#Sta/Elev= 30
  3955.8  145.17  4200.6  141.14  4262.5  139.37  4391.6  137.32  4456.8  136.25
  4480.3  136.45  4562.5  134.79  4714.9  133.68  4767.3  132.49  4829.2  131.97
  4849.2  131.06  4949.5  129.72  4969.6  128.29  4979.3  125.97  4984.3  126.85
  4989.7   123.7  4993.1  123.55  4993.6  123.05  5005.8  123.05  5006.3  123.55
  5009.7   127.7  5019.8  129.81  5059.9  130.25  5111.2   132.3  5150.5  131.32
  5277.5  132.07  5505.1  137.89  5606.2  139.29  5693.8  139.25  6154.2  140.27
#Mann= 9 ,-1 , 0
  3955.8    .035       0  4200.6     .07       0  4262.5    .035       0
  4391.6     .07       0  4767.3      .1       0  4993.1     .05       0
  5006.3      .1       0  5277.5     .07       0  5693.8     .05       0
Bank Sta=4993.1,5006.3
XS Rating Curve= 0 ,0
Exp/Cntr=0.3,0.1

Type RM Length L Ch R = 1 ,16043   ,452,452,452
BEGIN DESCRIPTION:
ROAD CREEK 29.0
END DESCRIPTION:
XS GIS Cut Line= 3
      2518925.04     13448475.01        2518125.       13448275.
      2517524.98     13447474.97
#Sta/Elev= 30
  4170.4  141.75  4343.5  137.81  4531.2  133.52  4712.5   131.4    4758  131.72
  4853.3  129.03  4953.8  130.43    4977  128.65  5010.3  121.75  5010.8  121.25
  5023.5  121.75  5037.8  129.63  5069.7  130.95  5158.6  135.62  5305.5  135.13
  5373.2  134.83  5423.2  132.08  5452.4  134.31  5458.6  136.58  5466.9  137.24
  5482.2  135.48  5487.8  133.66  5523.2   130.2  5581.5  130.68  5631.5  135.06
  5699.2  136.29  5816.9  139.32    5867  139.15  5957.8  140.98  5995.1  141.55
#Mann= 11 ,-1 , 0
  4170.4    .035       0  4343.5     .07       0  4712.5      .1       0
  5010.3     .05       0  5023.5      .1       0  5069.7     .07       0
  5305.5      .1       0  5482.2     .07       0  5699.2      .1       0
    5867     .07       0  5957.8     .05       0
Bank Sta=5010.3,5023.5
XS Rating Curve= 0 ,0
Exp/Cntr=0.3,0.1

Type RM Length L Ch R = 1 ,15591   ,398,398,398
BEGIN DESCRIPTION:
ROAD CREEK 28.0
END DESCRIPTION:
XS GIS Cut Line= 3
      2518925.04     13448325.03        2518375.       13447975.
      2517675.02     13447375.01
#Sta/Elev= 30
  4343.6  140.56  4396.4  139.47    4524  137.11  4596.8  134.48  4770.4  130.49
  4945.6  128.35  4972.7  129.19    4982  128.68  4992.6  126.52  5009.3  124.68
  5016.9  120.05  5017.4  119.55  5030.2  120.05  5037.8  121.74  5045.5  126.08
  5052.1  128.12  5066.4   129.5  5101.5   129.3    5152     132  5285.9  134.33
  5350.6  134.57  5428.6  133.39  5470.3  129.76  5492.2  130.11  5498.7  126.18
  5513.1  129.08  5527.3  130.57  5555.9  130.71  5584.4  134.25  5917.5  141.29
#Mann= 5 ,-1 , 0
  4343.6     .07       0  4396.4      .1       0  5016.9     .05       0
  5030.2      .1       0  5498.7     .07       0
Bank Sta=5016.9,5030.2
XS Rating Curve= 0 ,0
Exp/Cntr=0.3,0.1

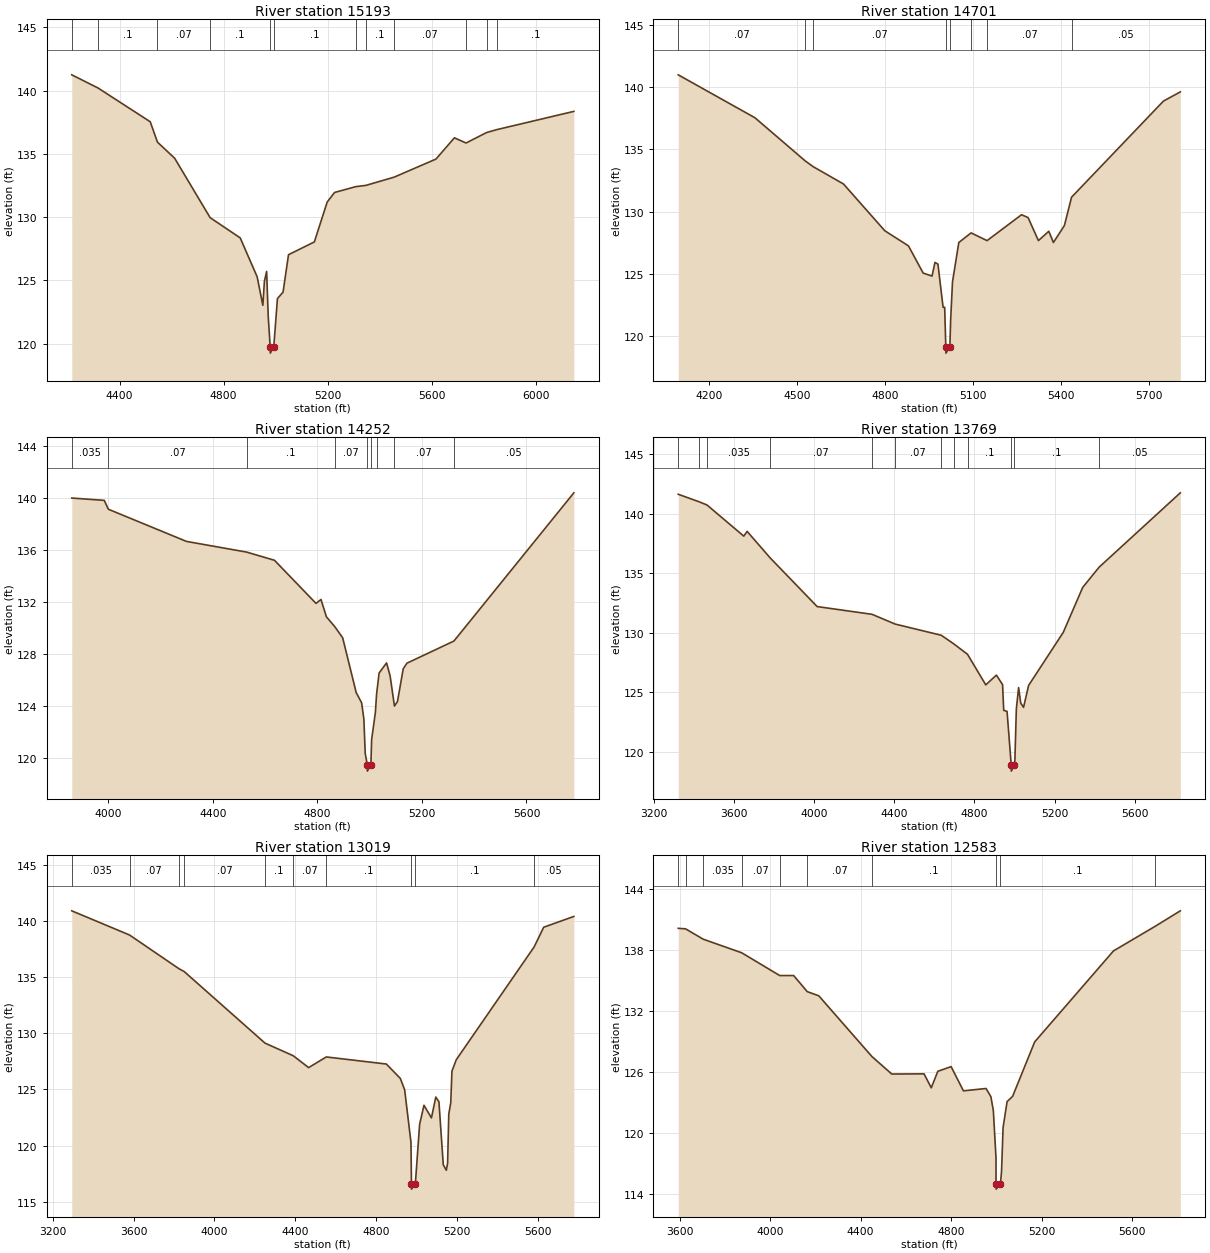
Type RM Length L Ch R = 1 ,15193   ,492,492,492
BEGIN DESCRIPTION:
Mapping XS 93081d0b
END DESCRIPTION:
XS GIS Cut Line= 3
      2519003.76     13448284.47      2518580.12     13447659.44
      2517782.26     13446799.14
#Sta/Elev= 30
  4216.6  141.25  4317.4  140.21    4518  137.54  4545.7  135.93    4612  134.65
    4748  129.96  4863.6  128.36  4928.7  125.28  4950.5  123.03  4956.5  124.93
    4965  125.71  4971.3  122.11  4978.7  119.75  4979.2  119.25  4992.5  119.75
  5006.5  123.56  5028.1  124.07  5049.1  127.03  5148.3  128.04  5197.6  131.19
  5225.9  131.95  5307.4  132.41  5346.4  132.51  5454.7  133.16  5615.4  134.59
  5686.3  136.27    5731  135.86  5810.1  136.69  5849.6  136.92    6145  138.36
#Mann= 12 ,-1 , 0
  4216.6     .07       0  4317.4      .1       0  4545.7     .07       0
    4748      .1       0  4978.7     .05       0  4992.5      .1       0
  5307.4     .07       0  5346.4      .1       0  5454.7     .07       0
    5731     .05       0  5810.1     .07       0  5849.6      .1       0
Bank Sta=4978.7,4992.5
XS Rating Curve= 0 ,0
Exp/Cntr=0.3,0.1

Type RM Length L Ch R = 1 ,14701   ,449,449,449
BEGIN DESCRIPTION:
ROAD CREEK 26.0
END DESCRIPTION:
XS GIS Cut Line= 3
        2519025.     13448224.98        2518925.       13447325.
      2518525.02     13446625.04
#Sta/Elev= 30
  4094.5  140.99  4356.1  137.54  4527.6  134.07  4555.3   133.6  4657.9  132.22
  4798.8  128.46  4879.3  127.25  4929.6  125.06  4959.8  124.82  4969.8  125.92
  4979.9  125.78  4997.5  122.31  5002.9  122.31  5006.7  119.13  5007.2  118.63
  5020.6  119.13  5023.1  121.21  5029.5  124.35  5051.1  127.52  5092.9  128.29
  5147.4  127.67  5264.9  129.75  5287.2  129.52  5322.5  127.67  5357.8  128.42
  5373.6  127.52    5411  128.88  5435.5  131.16  5748.7  138.88  5806.2  139.62
#Mann= 8 ,-1 , 0
  4094.5     .07       0  4527.6      .1       0  4555.3     .07       0
  5006.7     .05       0  5020.6     .07       0  5092.9      .1       0
  5147.4     .07       0  5435.5     .05       0
Bank Sta=5006.7,5020.6
XS Rating Curve= 0 ,0
Exp/Cntr=0.3,0.1

Type RM Length L Ch R = 1 ,14252   ,483,483,483
BEGIN DESCRIPTION:
ROAD CREEK 25.0
END DESCRIPTION:
XS GIS Cut Line= 3
      2519525.01     13448125.03        2519225.       13447025.
      2518625.03     13446525.02
#Sta/Elev= 30
    3860     140  3984.4  139.82    4000  139.14  4298.8  136.67    4529  135.85
  4635.7  135.22  4794.6  131.91  4813.6  132.21  4834.4  130.88    4867  130.11
  4896.6  129.27  4948.4  125.06  4969.1  124.28  4977.7  123.04  4982.9  120.39
  4990.7  119.53  4991.2  119.03  5004.6  119.53  5007.4  121.45  5021.7  123.52
  5026.4  124.94    5036  126.56  5064.6  127.34  5078.3  126.33  5094.7  124.03
  5106.3  124.37  5128.4  126.89  5142.7  127.32  5322.4  129.02  5781.2   140.4
#Mann= 9 ,-1 , 0
    3860    .035       0    4000     .07       0    4529      .1       0
    4867     .07       0  4990.7     .05       0  5004.6     .07       0
  5026.4      .1       0  5094.7     .07       0  5322.4     .05       0
Bank Sta=4990.7,5004.6
XS Rating Curve= 0 ,0
Exp/Cntr=0.3,0.1

Type RM Length L Ch R = 1 ,13769   ,750,750,750
BEGIN DESCRIPTION:
ROAD CREEK 24.0
END DESCRIPTION:
XS GIS Cut Line= 4
      2520075.01     13448075.02        2519325.       13446575.
      2518916.29     13446426.38      2518636.54     13446150.03
#Sta/Elev= 30
  3322.5  141.65  3424.7  141.03  3465.9  140.75  3649.6  138.13  3666.3  138.53
  3780.7  136.31  4015.7  132.21  4289.4  131.56  4404.9  130.74  4634.7   129.8
  4696.3  129.09  4765.9   128.2    4857  125.63  4910.1  126.45  4940.9  125.65
  4946.5  123.49  4963.2   123.4  4984.1  118.88  4984.6  118.38  4998.3  118.88
  5002.2  119.26  5009.6  123.61  5020.9   125.4  5031.5   124.1  5045.5  123.74
  5070.7  125.58  5243.6  130.04  5340.7  133.82  5422.5  135.52  5827.7  141.77
#Mann= 12 ,-1 , 0
  3322.5    .035       0  3424.7     .07       0  3465.9    .035       0
  3780.7     .07       0  4289.4      .1       0  4404.9     .07       0
  4634.7      .1       0  4696.3     .07       0  4765.9      .1       0
  4984.1     .05       0  4998.3      .1       0  5422.5     .05       0
Bank Sta=4984.1,4998.3
XS Rating Curve= 0 ,0
Exp/Cntr=0.3,0.1

Type RM Length L Ch R = 1 ,13019   ,436,436,436
BEGIN DESCRIPTION:
Mapping XS a2b3e913
END DESCRIPTION:
XS GIS Cut Line= 4
      2520245.06     13448024.04      2519745.05     13446550.06
      2520125.26     13445909.44      2520099.43     13445728.61
#Sta/Elev= 30
  3294.4  140.88  3580.1  138.73  3824.8  135.73  3850.5  135.48  4250.5  129.11
  4389.9  127.99  4466.4  126.93  4553.6  127.88  4850.9  127.25    4920  125.97
  4941.5  124.95  4972.7  120.27    4975  116.62  4975.5  116.12  4994.4  116.62
  5015.5  121.89    5037  123.58    5074  122.46  5095.4  124.31    5111  123.89
  5132.5  118.29  5147.5   117.8  5153.9  118.42  5159.7  122.79  5169.5  123.81
  5175.3  126.61  5196.7  127.63  5582.1  137.67  5629.3  139.42  5778.5  140.38
#Mann= 10 ,-1 , 0
  3294.4    .035       0  3580.1     .07       0  3824.8    .035       0
  3850.5     .07       0  4250.5      .1       0  4389.9     .07       0
  4553.6      .1       0    4975     .05       0  4994.4      .1       0
  5582.1     .05       0
Bank Sta=4975,4994.4
XS Rating Curve= 0 ,0
Exp/Cntr=0.3,0.1

Type RM Length L Ch R = 1 ,12583   ,518,518,518
BEGIN DESCRIPTION:
Mapping XS 32203470
END DESCRIPTION:
XS GIS Cut Line= 4
      2520302.34     13447992.75       2520088.8     13446836.52
      2520375.26     13446102.15      2520385.61     13445848.51
#Sta/Elev= 30
  3594.3  140.13  3626.6  140.08  3704.9  139.06  3874.4  137.73  4042.6  135.49
  4104.2  135.49  4164.1  133.91  4215.1   133.5  4449.9  127.53  4537.7  125.81
  4680.1  125.83  4712.1  124.46  4741.1  126.08  4799.7  126.54  4854.1  124.16
  4954.2  124.39  4975.7  123.57  4986.4  122.19    4998  117.57  4998.2     115
  4998.7   114.5  5017.6     115  5022.5  116.26  5029.3  120.55    5047   123.1
  5071.5  123.62  5168.9  128.97    5517  137.91  5699.7  140.31  5812.2  141.85
#Mann= 10 ,-1 , 0
  3594.3    .035       0  3626.6     .07       0  3704.9    .035       0
  3874.4     .07       0  4042.6    .035       0  4164.1     .07       0
  4449.9      .1       0  4998.2     .05       0  5017.6      .1       0
  5699.7     .07       0
Bank Sta=4998.2,5017.6
XS Rating Curve= 0 ,0
Exp/Cntr=0.3,0.1

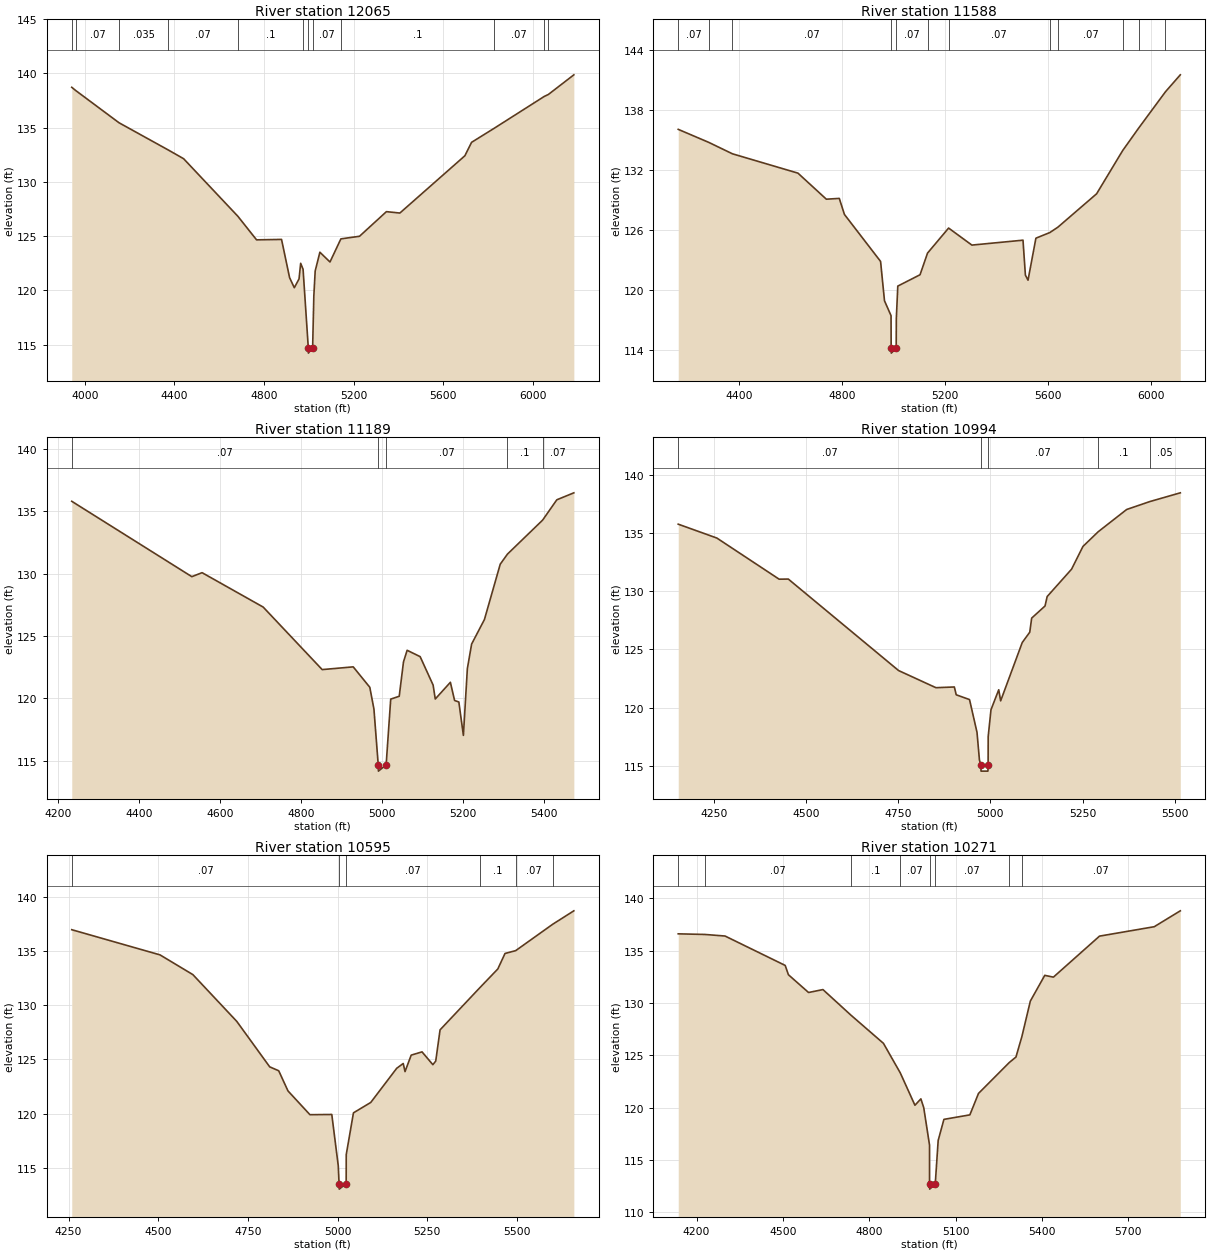
Type RM Length L Ch R = 1 ,12065   ,477,477,477
BEGIN DESCRIPTION:
Mapping XS 822f1ed7
END DESCRIPTION:
XS GIS Cut Line= 4
      2520403.04     13447994.48      2520396.09     13447168.12
      2520646.09     13446793.12      2520597.54     13445828.92
#Sta/Elev= 30
  3941.4  138.72  3959.2  138.42  4152.6  135.45  4372.7  132.94  4440.9  132.14
  4683.4  126.83  4766.8  124.66  4878.3   124.7  4914.4  121.17  4935.4  120.25
  4956.5  121.06  4963.8   122.5  4974.5  121.95  4997.8  114.72  4998.3  114.22
  5017.2  114.72  5022.6  119.49  5028.6  121.79  5049.6  123.52  5094.7  122.62
  5143.4  124.75  5226.6  124.99  5346.8  127.26  5406.8  127.13  5697.2  132.41
  5727.2  133.65  5827.9  134.94  6051.9  137.88  6070.2  138.06  6183.9  139.87
#Mann= 12 ,-1 , 0
  3941.4    .035       0  3959.2     .07       0  4152.6    .035       0
  4372.7     .07       0  4683.4      .1       0  4974.5     .07       0
  4997.8     .05       0  5017.2     .07       0  5143.4      .1       0
  5827.9     .07       0  6051.9      .1       0  6070.2     .07       0
Bank Sta=4997.8,5017.2
XS Rating Curve= 0 ,0
Exp/Cntr=0.3,0.1

Type RM Length L Ch R = 1 ,11588   ,399,399,399
BEGIN DESCRIPTION:
Mapping XS ff5a5083
END DESCRIPTION:
XS GIS Cut Line= 4
      2520833.59     13448008.45      2520889.15     13447209.79
      2521007.21     13446654.23      2521354.06     13446189.44
#Sta/Elev= 30
  4163.9  136.04  4282.3  134.74  4374.2   133.6  4628.5  131.67  4738.7  129.07
  4788.9  129.15  4808.9  127.55  4949.2  122.86  4964.4  118.93  4989.8  117.45
  4990.3  114.21  4990.8  113.71  5009.8  114.21  5010.3  117.16    5016   120.4
  5102.3  121.53  5131.4  123.69  5213.2  126.19  5303.5  124.49  5501.9  124.98
  5511.2  121.49  5521.4  120.99    5552  125.18    5606  125.74  5637.4  126.28
  5787.6  129.61  5888.9  133.93  5951.5  136.19  6054.8  139.79  6112.4  141.48
#Mann= 12 ,-1 , 0
  4163.9     .07       0  4282.3      .1       0  4374.2     .07       0
  4990.3     .05       0  5009.8     .07       0  5131.4      .1       0
  5213.2     .07       0    5606      .1       0  5637.4     .07       0
  5888.9      .1       0  5951.5     .07       0  6054.8     .05       0
Bank Sta=4990.3,5009.8
XS Rating Curve= 0 ,0
Exp/Cntr=0.3,0.1

Type RM Length L Ch R = 1 ,11189   ,195,195,195
BEGIN DESCRIPTION:
ROAD CREEK 19.0
END DESCRIPTION:
XS GIS Cut Line= 3
      2521124.99     13447875.05        2521280.       13447125.
      2521425.01     13446674.98
#Sta/Elev= 30
  4234.1  135.81  4530.3  129.76  4555.6  130.08  4706.3  127.32  4851.9   122.3
  4928.5  122.52  4969.4  120.88  4979.6  119.13  4990.2  114.65  4990.7  114.15
  5009.7  114.65    5021  119.93    5042  120.16  5052.5  122.92  5061.5  123.85
  5093.6  123.34  5125.6  121.06  5130.9  119.94  5168.2  121.28  5178.6  119.82
  5189.1   119.7  5200.3  117.02  5210.1  122.38  5220.6  124.35  5252.2  126.32
  5291.2  130.76    5309  131.57  5395.8   134.3  5430.8  135.93  5472.8  136.49
#Mann= 5 ,-1 , 0
  4234.1     .07       0  4990.2     .05       0  5009.7     .07       0
    5309      .1       0  5395.8     .07       0
Bank Sta=4990.2,5009.7
XS Rating Curve= 0 ,0
Exp/Cntr=0.3,0.1

Type RM Length L Ch R = 1 ,10994   ,399,399,399
BEGIN DESCRIPTION:
ROAD CREEK 18.0
END DESCRIPTION:
XS GIS Cut Line= 3
      2521344.16     13447965.22        2521475.       13447125.
      2521593.76     13446628.35
#Sta/Elev= 30
  4153.9  135.75  4258.6  134.56  4427.4  131.03  4452.3  131.04  4751.2  123.19
  4852.4  121.72  4902.4  121.78  4907.4  121.11  4943.5   120.7  4963.8  117.89
  4970.3  115.54  4974.2  115.06  4974.7  114.56  4993.4  114.56  4993.9  115.06
  4994.1  117.52  5001.7  119.83  5022.7  121.54  5027.9  120.59  5086.5   125.6
  5106.8  126.48    5112  127.69  5148.2  128.73    5154  129.54  5220.2  131.89
    5251  133.84  5292.3   135.1  5369.5  137.01  5432.3  137.69  5514.9  138.44
#Mann= 5 ,-1 , 0
  4153.9     .07       0  4974.2     .05       0  4993.9     .07       0
  5292.3      .1       0  5432.3     .05       0
Bank Sta=4974.2,4993.9
XS Rating Curve= 0 ,0
Exp/Cntr=0.3,0.1

Type RM Length L Ch R = 1 ,10595   ,324,324,324
BEGIN DESCRIPTION:
Mapping XS f1250eac
END DESCRIPTION:
XS GIS Cut Line= 3
      2521666.93     13448036.19      2521805.82     13447341.73
       2521882.2     13446654.27
#Sta/Elev= 30
  4258.9  136.95  4504.9  134.63  4596.6  132.81    4719   128.5  4810.8  124.31
  4835.9  123.95  4861.8  122.09    4923   119.9  4983.9  119.92    5002  115.18
  5004.2  113.54  5004.7  113.04    5024  113.54  5024.2  116.22  5044.3  120.07
  5092.6  121.03    5165  124.18  5183.1  124.62  5188.1  123.87  5205.3  125.39
  5235.5  125.69  5265.7  124.51  5273.7  124.84  5285.8  127.72  5397.7  131.64
  5446.8  133.33  5466.9  134.76  5496.6  135.02  5600.2  137.46  5658.8  138.69
#Mann= 6 ,-1 , 0
  4258.9     .07       0  5004.2     .05       0    5024     .07       0
  5397.7      .1       0  5496.6     .07       0  5600.2     .05       0
Bank Sta=5004.2,5024
XS Rating Curve= 0 ,0
Exp/Cntr=0.3,0.1

Type RM Length L Ch R = 1 ,10271   ,663,663,663
BEGIN DESCRIPTION:
Mapping XS 8c378602
END DESCRIPTION:
XS GIS Cut Line= 3
      2522090.54     13448237.56      2522111.37     13447411.17
       2522146.1     13446494.48
#Sta/Elev= 30
  4136.3  136.62  4229.6  136.56  4298.9  136.41  4507.8   133.6    4519  132.71
    4589  131.01    4639  131.29    4736  128.85  4849.1  126.15  4907.5  123.33
  4958.5  120.23  4979.1  120.84  4989.1     120  5009.2  116.42  5009.3  112.71
  5009.8  112.21  5029.1  112.71  5039.2  116.86  5059.2  118.88  5149.3  119.31
  5179.3  121.36    5286  124.31  5309.4  124.84  5330.1  126.81  5359.4  130.19
  5409.4  132.65  5439.5  132.48  5599.6   136.4  5789.7   137.3  5880.3  138.82
#Mann= 8 ,-1 , 0
  4136.3    .035       0  4229.6     .07       0    4736      .1       0
  4907.5     .07       0  5009.3     .05       0  5029.1     .07       0
    5286      .1       0  5330.1     .07       0
Bank Sta=5009.3,5029.1
XS Rating Curve= 0 ,0
Exp/Cntr=0.3,0.1

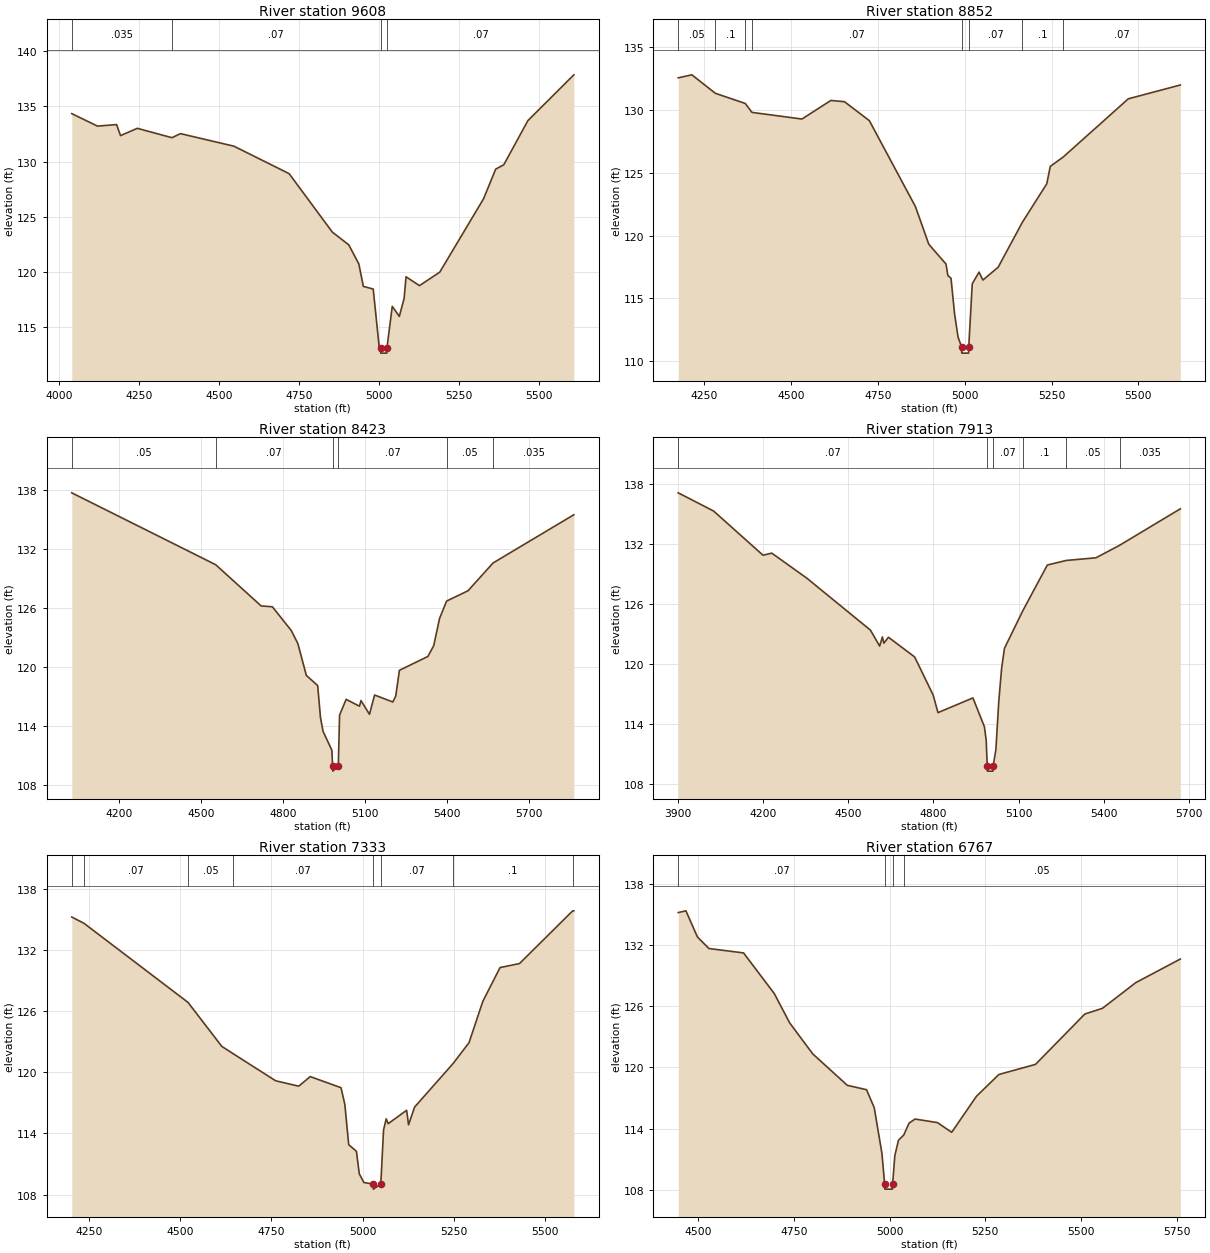
Type RM Length L Ch R = 1 ,9608    ,756,756,756
BEGIN DESCRIPTION:
Mapping XS 77fcfe05
END DESCRIPTION:
XS GIS Cut Line= 3
      2522416.94     13448390.31      2522694.71      13447508.4
      2522896.11     13446897.25
#Sta/Elev= 30
  4040.4  134.35  4120.9  133.22  4180.4  133.36  4192.7  132.36  4245.1  133.02
  4353.5  132.17  4379.8  132.54  4546.9   131.4  4719.3  128.91    4854  123.62
  4905.7  122.45  4937.1  120.72  4951.1  118.69  4981.9  118.45  5000.2  113.29
  5004.9  113.14  5005.4  112.64  5024.4  112.64  5024.9  113.14  5041.4  116.88
  5063.4  115.97  5078.5  117.61  5084.4  119.56  5126.5  118.76  5189.7  119.98
  5326.6  126.64  5364.4  129.32  5389.8  129.72    5465  133.72  5608.5  137.87
#Mann= 4 ,-1 , 0
  4040.4    .035       0  4353.5     .07       0  5004.9     .05       0
  5024.9     .07       0
Bank Sta=5004.9,5024.9
XS Rating Curve= 0 ,0
Exp/Cntr=0.3,0.1

Type RM Length L Ch R = 1 ,8852    ,429,429,429
BEGIN DESCRIPTION:
Mapping XS 89858018
END DESCRIPTION:
XS GIS Cut Line= 3
      2523139.14     13448633.44      2523298.87      13447883.4
      2523437.43     13447218.34
#Sta/Elev= 30
  4174.5  132.56  4213.8   132.8  4281.4  131.33  4367.7  130.52  4386.8  129.81
  4530.8  129.28  4614.2  130.76  4653.4  130.66    4725  129.15  4857.9   122.3
  4896.2  119.31  4945.9  117.73    4951  116.83  4960.2   116.6  4970.4  113.79
  4980.6   111.9  4990.8  111.14  4991.3  110.64  5010.8  110.64  5011.3  111.14
  5021.4  116.16  5040.9  117.09  5052.1  116.46    5096  117.48    5166  121.07
    5236  124.12  5246.2  125.51  5283.6  126.26  5470.9  130.89  5620.7  131.99
#Mann= 8 ,-1 , 0
  4174.5     .05       0  4281.4      .1       0  4367.7     .05       0
  4386.8     .07       0  4990.8     .05       0  5011.3     .07       0
    5166      .1       0  5283.6     .07       0
Bank Sta=4990.8,5011.3
XS Rating Curve= 0 ,0
Exp/Cntr=0.3,0.1

Type RM Length L Ch R = 1 ,8423    ,510,510,510
BEGIN DESCRIPTION:
ROAD CREEK 13.0
END DESCRIPTION:
XS GIS Cut Line= 3
      2523425.01     13448874.95        2523675.       13447925.
        2523975.       13447125.
#Sta/Elev= 30
  4025.9  137.76  4552.4  130.45  4718.7  126.26    4760  126.17  4829.3  123.74
  4853.1  122.42  4884.1  119.19  4925.5  118.16  4935.8   114.9  4945.1  113.51
  4977.2   111.6  4980.4  109.96  4980.9  109.46  5000.9  109.96  5005.6  115.15
  5029.6  116.76  5078.5  116.06  5083.8  116.64    5115  115.24  5133.7   117.2
  5200.4  116.49  5211.1   117.1  5224.5  119.71  5328.6  121.12    5350  122.22
  5371.3  124.98  5397.1  126.75  5475.4   127.8  5567.2  130.63  5862.6  135.53
#Mann= 6 ,-1 , 0
  4025.9     .05       0  4552.4     .07       0  4980.4     .05       0
  5000.9     .07       0  5397.1     .05       0  5567.2    .035       0
Bank Sta=4980.4,5000.9
XS Rating Curve= 0 ,0
Exp/Cntr=0.3,0.1

Type RM Length L Ch R = 1 ,7913    ,580,580,580
BEGIN DESCRIPTION:
Mapping XS 0c0baa2c
END DESCRIPTION:
XS GIS Cut Line= 3
      2523882.22     13448945.86      2524125.26     13447925.06
      2524215.53     13447209.87
#Sta/Elev= 30
  3900.1  137.16  4024.8  135.34  4199.1  130.92  4229.9  131.13  4353.3  128.63
  4577.8  123.43  4610.3  121.83    4620  122.75  4625.1  122.12  4641.1  122.72
  4733.6  120.75  4798.8  116.95  4815.9  115.18  4939.2  116.65  4979.7  113.76
    4986  112.39  4989.5  109.83    4990  109.33  5009.7  109.33  5010.2  109.83
    5020  111.45  5030.1  116.23  5040.2   119.6  5050.3  121.61  5115.4  125.39
  5201.5  129.94  5268.6   130.4  5372.8  130.66    5456  131.91  5670.3  135.56
#Mann= 6 ,-1 , 0
  3900.1     .07       0  4989.5     .05       0  5010.2     .07       0
  5115.4      .1       0  5268.6     .05       0    5456    .035       0
Bank Sta=4989.5,5010.2
XS Rating Curve= 0 ,0
Exp/Cntr=0.3,0.1

Type RM Length L Ch R = 1 ,7333    ,566,566,566
BEGIN DESCRIPTION:
ROAD CREEK 11.0
END DESCRIPTION:
XS GIS Cut Line= 3
        2524875.     13448874.99        2524625.       13448125.
        2524425.     13447574.99
#Sta/Elev= 30
  4202.9  135.25  4236.2  134.64  4521.4  126.87    4614  122.55  4645.6  121.82
  4761.6  119.17  4824.8  118.64  4856.4  119.58  4940.8  118.49  4951.3  116.82
  4961.8  112.89  4982.9  112.25  4990.8  110.03  5003.4  109.18  5028.9  109.03
  5029.4  108.53  5049.7  109.03  5057.3  114.36  5064.6  115.43  5069.9  114.96
  5120.5  116.27  5125.8  114.85  5142.4  116.59  5248.4  120.89  5291.4  122.91
  5329.3  126.97  5376.5  130.29  5429.7  130.68  5575.3  135.85  5578.7  135.86
#Mann= 8 ,-1 , 0
  4202.9    .035       0  4236.2     .07       0  4521.4     .05       0
  4645.6     .07       0  5028.9     .05       0  5049.7     .07       0
  5248.4      .1       0  5575.3    .035       0
Bank Sta=5028.9,5049.7
XS Rating Curve= 0 ,0
Exp/Cntr=0.3,0.1

Type RM Length L Ch R = 1 ,6767    ,591,591,591
BEGIN DESCRIPTION:
ROAD CREEK 10.0
END DESCRIPTION:
XS GIS Cut Line= 3
        2525075.     13448674.98        2525125.       13448125.
      2524741.25     13447469.52
#Sta/Elev= 30
  4447.9  135.16    4468  135.33  4498.1  132.77  4528.2  131.64  4618.6  131.21
  4698.9  127.23  4739.1  124.36  4799.3  121.33  4889.7  118.25  4939.9  117.82
    4960  116.06  4980.1  111.59  4987.2  108.59  4987.7  108.09  5007.5  108.09
    5008  108.59  5013.8  111.36  5023.3  112.87  5037.2  113.39    5051  114.55
  5066.7  114.95  5125.3   114.6  5162.4  113.65  5226.9  117.17  5285.6  119.31
  5381.4   120.3  5510.3  125.23  5556.4  125.79  5643.3   128.3  5759.7  130.61
#Mann= 4 ,-1 , 0
  4447.9     .07       0  4987.2     .05       0    5008     .07       0
  5037.2     .05       0
Bank Sta=4987.2,5008
XS Rating Curve= 0 ,0
Exp/Cntr=0.3,0.1

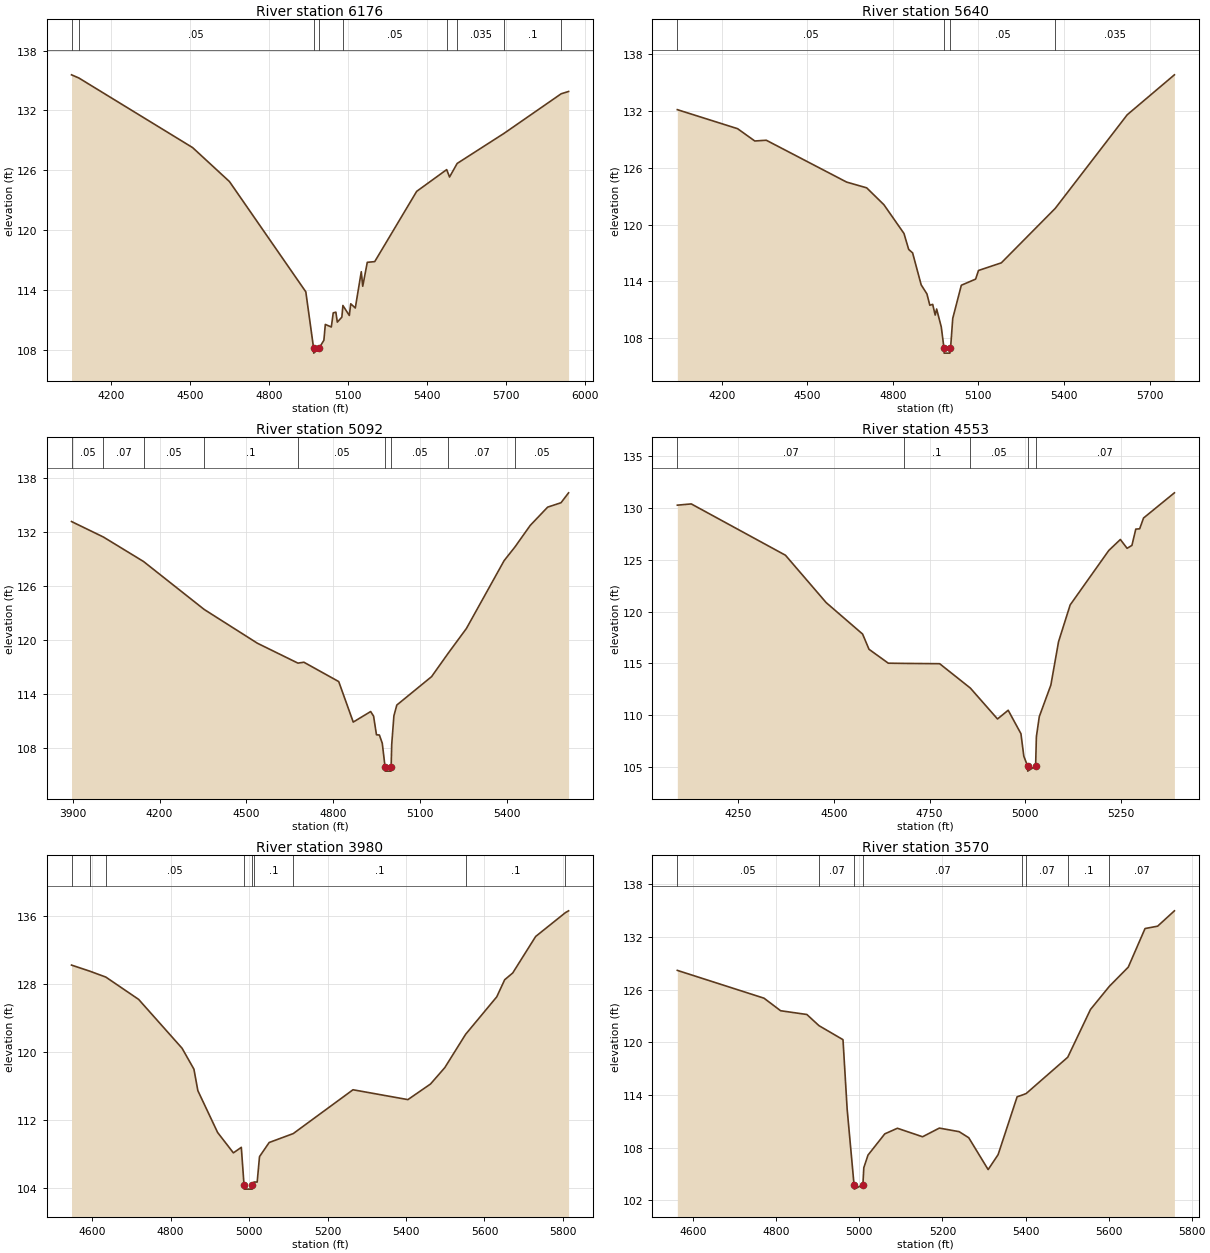
Type RM Length L Ch R = 1 ,6176    ,536,536,536
BEGIN DESCRIPTION:
ROAD CREEK 9.0
END DESCRIPTION:
XS GIS Cut Line= 3
        2525625.     13448724.97        2525575.       13447775.
        2525175.       13446925.
#Sta/Elev= 30
  4048.7  135.56  4076.8  135.24  4509.3  128.26  4649.5  124.85  4939.9  113.79
  4969.5  108.14    4970  107.64  4990.4  108.14  5008.6  108.93  5014.1  110.52
  5036.9  110.26  5044.2  111.68  5054.2  111.75  5059.7  110.75    5077  111.25
    5081  112.42  5105.3  111.42  5110.8  112.59  5128.1  112.17  5150.9  115.81
  5156.4  114.35  5173.7  116.75    5202  116.82  5361.6  123.87  5475.7  126.05
  5486.6  125.31  5515.6  126.67  5693.5  129.68  5911.3  133.66  5939.4  133.89
#Mann= 9 ,-1 , 0
  4048.7    .035       0  4076.8     .05       0  4969.5     .05       0
  4990.4     .05       0    5081     .05       0  5475.7     .07       0
  5515.6    .035       0  5693.5      .1       0  5911.3     .05       0
Bank Sta=4969.5,4990.4
XS Rating Curve= 0 ,0
Exp/Cntr=0.3,0.1

Type RM Length L Ch R = 1 ,5640    ,548,548,548
BEGIN DESCRIPTION:
ROAD CREEK 8.0
END DESCRIPTION:
XS GIS Cut Line= 3
      2525924.99     13448475.05        2526025.       13447525.
      2525970.18     13446740.01
#Sta/Elev= 30
  4044.7  132.14  4255.9  130.13  4316.2  128.83  4356.5  128.91    4638  124.49
  4708.4  123.88  4768.7   122.1  4839.1  119.06  4855.5  117.38  4869.3  117.01
  4899.4  113.63  4919.6  112.67  4929.6  111.48  4939.7  111.57  4948.5  110.44
  4953.5  111.08  4969.8  109.19  4979.4  106.92  4979.9  106.42  4999.9  106.42
  5000.4  106.92  5002.5     107    5010  110.09  5040.1  113.59  5090.2  114.24
  5100.2  115.15  5180.4  115.96  5369.2  121.71  5621.5   131.6  5786.9  135.82
#Mann= 4 ,-1 , 0
  4044.7     .05       0  4979.4     .05       0  5000.4     .05       0
  5369.2    .035       0
Bank Sta=4979.4,5000.4
XS Rating Curve= 0 ,0
Exp/Cntr=0.3,0.1

Type RM Length L Ch R = 1 ,5092    ,539,539,539
BEGIN DESCRIPTION:
ROAD CREEK 7.0
END DESCRIPTION:
XS GIS Cut Line= 3
        2526425.     13448474.99        2526525.       13447375.
      2526571.91     13446762.82
#Sta/Elev= 30
  3895.4  133.18  4005.6  131.46  4144.4  128.74  4354.2  123.41    4538  119.66
  4678.2  117.45  4698.7  117.55  4819.2   115.4  4869.4   110.9  4929.6  112.07
  4939.7  111.56  4949.7  109.49  4959.8  109.46  4969.8  108.54  4979.3  105.95
  4979.8  105.45  4999.9  105.45  5000.4  105.95  5002.4  108.41    5010   111.6
    5020  112.79  5140.3  115.95  5197.5  118.54  5260.7   121.3  5391.1  128.84
  5428.3  130.35  5481.3  132.75  5541.5  134.78  5587.7  135.27  5613.9  136.37
#Mann= 9 ,-1 , 0
  3895.4     .05       0  4005.6     .07       0  4144.4     .05       0
  4354.2      .1       0  4678.2     .05       0  4979.3     .05       0
  5000.4     .05       0  5197.5     .07       0  5428.3     .05       0
Bank Sta=4979.3,5000.4
XS Rating Curve= 0 ,0
Exp/Cntr=0.3,0.1

Type RM Length L Ch R = 1 ,4553    ,573,573,573
BEGIN DESCRIPTION:
ROAD CREEK 6.0
END DESCRIPTION:
XS GIS Cut Line= 3
      2526574.98     13448375.04        2526975.       13447575.
        2527025.     13447174.98
#Sta/Elev= 30
  4091.7  130.27  4128.1  130.39    4374  125.44  4480.3  120.87  4575.3  117.84
  4592.1  116.37  4642.4  115.03  4682.3  115.01  4776.5  114.98  4856.6  112.63
  4927.5  109.65  4955.4  110.49  4988.7  108.23  4996.2  106.06  5005.9  105.12
  5006.4  104.62    5027  105.12    5029  107.94  5036.6  109.88  5066.8  112.92
  5086.9  117.11  5117.2  120.65    5218   125.9  5248.2  126.96  5265.8  126.11
  5278.4  126.39  5288.5  127.96  5298.6  127.99  5308.7  129.03  5389.3  131.46
#Mann= 5 ,-1 , 0
  4091.7     .07       0  4682.3      .1       0  4856.6     .05       0
  5005.9     .05       0    5027     .07       0
Bank Sta=5005.9,5027
XS Rating Curve= 0 ,0
Exp/Cntr=0.3,0.1

Type RM Length L Ch R = 1 ,3980    ,410,410,410
BEGIN DESCRIPTION:
ROAD CREEK 5.0
END DESCRIPTION:
XS GIS Cut Line= 3
        2527525.     13448225.01        2527475.       13447775.
        2527625.     13446975.02
#Sta/Elev= 30
  4547.6  130.21  4593.9   129.5    4635   128.8  4718.7  126.17  4829.3  120.42
  4859.5  117.96  4869.6  115.42  4919.9   110.5  4960.1   108.1  4980.3  108.75
  4987.2  104.33  4987.7  103.83    5008  103.83  5008.5  104.33  5012.8  104.67
  5020.7  104.66  5026.7  107.66  5051.3  109.32  5112.6  110.37  5264.9  115.53
  5404.8  114.37  5462.5  116.21  5498.9  118.14  5551.9  122.06  5631.2  126.47
  5651.5  128.49  5671.9  129.28  5730.4  133.58  5806.3  136.39  5814.3   136.6
#Mann= 9 ,-1 , 0
  4547.6     .05       0  4593.9     .07       0    4635     .05       0
  4987.2     .05       0  5008.5     .05       0  5012.8      .1       0
  5112.6      .1       0  5551.9      .1       0  5806.3     .05       0
Bank Sta=4987.2,5008.5
XS Rating Curve= 0 ,0
Exp/Cntr=0.3,0.1

Type RM Length L Ch R = 1 ,3570    ,778,778,778
BEGIN DESCRIPTION:
ROAD CREEK 4.0
END DESCRIPTION:
XS GIS Cut Line= 3
      2527867.43     13448213.54      2527885.21      13447775.5
      2527775.01     13447025.05
#Sta/Elev= 30
  4561.6   128.2  4770.3  125.03  4810.3   123.6  4873.5  123.17  4902.6   121.9
  4960.5   120.3  4970.5  112.38  4987.1  103.76  4987.6  103.26  5008.4  103.76
  5010.6   105.7  5020.7  107.14  5061.1  109.56  5091.5   110.2  5152.1  109.23
  5192.5  110.22  5240.2  109.81  5263.3  109.12    5310  105.49    5334  107.19
  5379.8  113.79  5392.3  113.99  5401.6  114.16  5501.7   118.3  5556.4  123.74
  5601.8  126.38  5647.4  128.57  5687.8  132.97  5718.1  133.24  5758.5  134.99
#Mann= 8 ,-1 , 0
  4561.6     .05       0  4902.6     .07       0  4987.1     .05       0
  5008.4     .07       0  5392.3      .1       0  5401.6     .07       0
  5501.7      .1       0  5601.8     .07       0
Bank Sta=4987.1,5008.4
XS Rating Curve= 0 ,0
Exp/Cntr=0.3,0.1