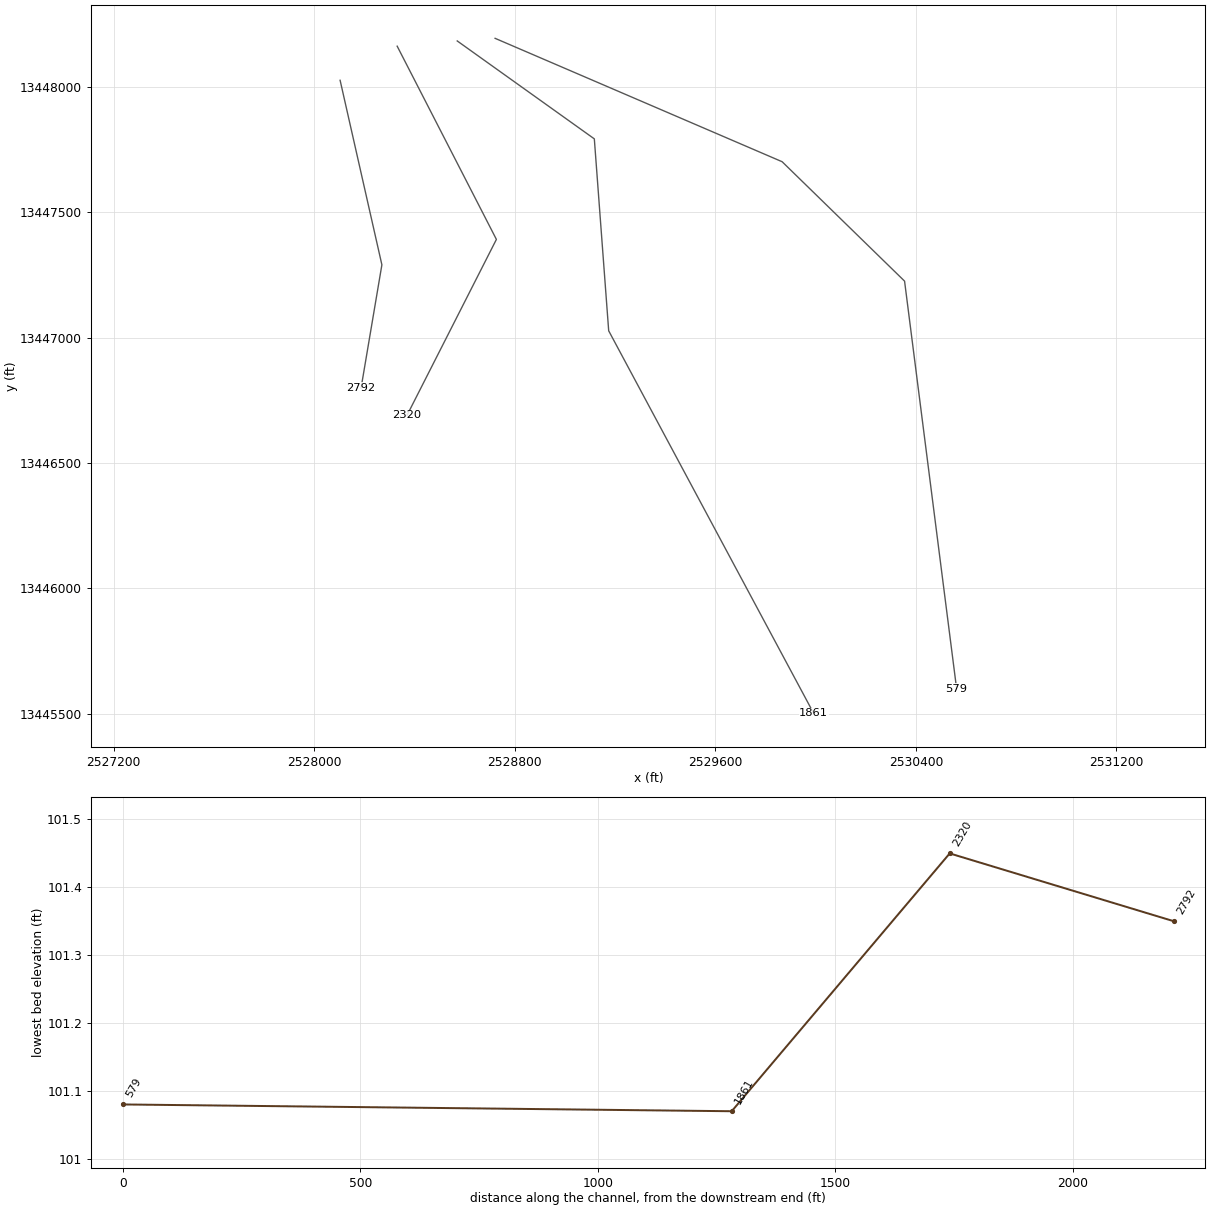
HEC-RAS study ROAD CREEK.prj: ROAD CREEK Base Level Engineering

--- ROAD CREEK.g01 (geometry) --- (continued)

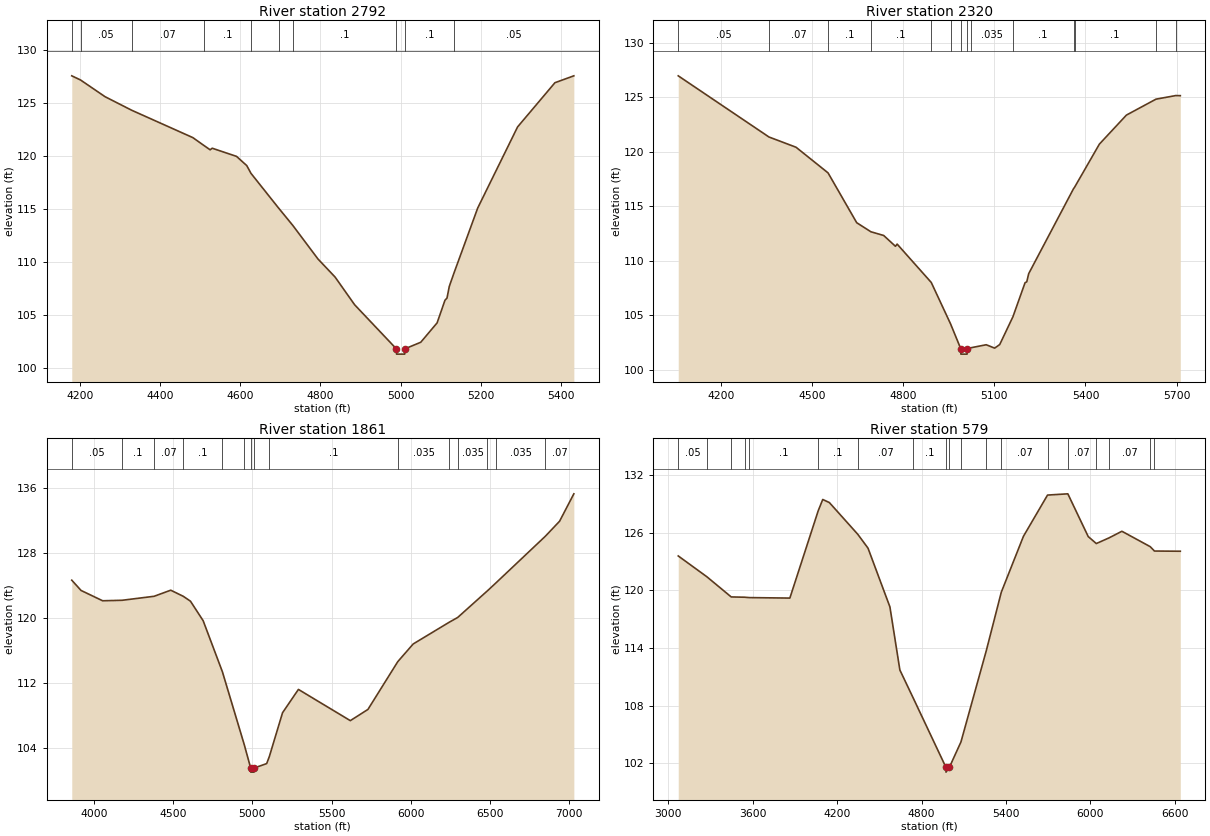
Type RM Length L Ch R = 1 ,2792    ,472,472,472
BEGIN DESCRIPTION:
Mapping XS 6ecfae58
END DESCRIPTION:
XS GIS Cut Line= 3
      2528103.55     13448026.05      2528270.21     13447289.98
      2528187.13     13446798.45
#Sta/Elev= 30
  4179.2  127.61    4201  127.22  4262.3  125.64  4328.9  124.36  4481.4  121.78
  4510.1  121.01  4524.6  120.63  4529.7  120.78  4590.4  120.01    4616  119.14
  4626.5  118.41  4695.3  115.14  4730.8   113.5  4793.7  110.33  4836.5  108.62
  4885.2  106.01  4989.4  101.85  4989.9  101.35  5010.2  101.35  5010.7  101.85
  5050.3  102.47  5091.1   104.3  5110.7  106.43  5115.8  106.64  5121.5  107.74
  5132.9  108.97  5192.5  115.14    5292  122.79  5385.2  126.96  5432.4  127.61
#Mann= 10 ,-1 , 0
  4179.2     .07       0    4201     .05       0  4328.9     .07       0
  4510.1      .1       0  4626.5     .07       0  4695.3      .1       0
  4730.8      .1       0  4989.4     .05       0  5010.7      .1       0
  5132.9     .05       0
Bank Sta=4989.4,5010.7
XS Rating Curve= 0 ,0
Exp/Cntr=0.3,0.1

Type RM Length L Ch R = 1 ,2320    ,459,459,459
BEGIN DESCRIPTION:
Mapping XS 1dceaa7e
END DESCRIPTION:
XS GIS Cut Line= 3
      2528331.18     13448162.11      2528726.99     13447391.32
      2528370.59     13446689.96
#Sta/Elev= 30
    4059  126.97  4357.8  121.36    4447  120.42  4552.3  118.07  4646.7   113.5
  4693.4  112.67  4735.5  112.33  4774.2  111.34  4779.8  111.54  4892.2  108.02
  4955.6  104.23  4989.2  101.95  4989.7  101.45  5010.1  101.45  5010.6  101.95
  5023.8  102.04  5073.1  102.31  5100.9     102  5117.6  102.33  5161.1  104.88
    5201     108  5206.6  108.08    5213  108.83  5360.6  116.62  5363.8  116.74
  5445.8  120.71  5534.8  123.37  5632.1  124.83  5697.3  125.16  5712.2  125.15
#Mann= 14 ,-1 , 0
    4059     .05       0  4357.8     .07       0  4552.3      .1       0
  4693.4      .1       0  4892.2    .035       0  4955.6      .1       0
  4989.2     .05       0  5010.6      .1       0  5023.8    .035       0
  5161.1      .1       0  5360.6    .035       0  5363.8      .1       0
  5632.1     .07       0  5697.3      .1       0
Bank Sta=4989.2,5010.6
XS Rating Curve= 0 ,0
Exp/Cntr=0.3,0.1

Type RM Length L Ch R = 1 ,1861    ,1282,1282,1282
BEGIN DESCRIPTION:
Mapping XS 03e148eb
END DESCRIPTION:
XS GIS Cut Line= 4
      2528570.75     13448182.97      2529117.61     13447792.36
      2529174.91     13447026.73       2529992.6     13445500.71
#Sta/Elev= 30
  3859.3  124.67  3917.9  123.41  4054.3  122.14  4177.2   122.2  4379.1  122.69
  4484.4  123.44  4563.5  122.69  4608.9  122.09  4689.1  119.69  4810.7  113.41
  4948.7  104.45  4989.3  101.57  4989.8  101.07  5010.2  101.07  5010.7  101.57
  5090.3  102.12  5107.1  102.98  5190.5  108.37  5290.8  111.24  5618.7   107.4
  5729.9  108.78  5918.6  114.66  6015.8  116.83  6244.1  119.51    6297  120.09
  6484.9  123.37    6538  124.33  6850.2  130.07  6940.3  131.92  7030.4  135.29
#Mann= 15 ,-1 , 0
  3859.3     .05       0  4177.2      .1       0  4379.1     .07       0
  4563.5      .1       0  4810.7      .1       0  4948.7      .1       0
  4989.3     .05       0  5010.7      .1       0  5107.1      .1       0
  5918.6    .035       0  6244.1     .07       0    6297    .035       0
  6484.9     .07       0    6538    .035       0  6850.2     .07       0
Bank Sta=4989.3,5010.7
XS Rating Curve= 0 ,0
Exp/Cntr=0.3,0.1

Type RM Length L Ch R = 1 ,579     ,0,0,0
BEGIN DESCRIPTION:
ROAD CREEK 1.0
END DESCRIPTION:
XS GIS Cut Line= 5
      2528721.82     13448193.38      2529866.74     13447701.22
      2530355.12     13447224.93      2530502.61     13446069.76
      2530562.68     13445599.32
#Sta/Elev= 30
  3071.6   123.6  3274.3  121.44    3448  119.33  3542.6   119.3    3575  119.26
  3864.7  119.21    4066   128.3  4098.3  129.48  4145.4  129.16  4347.6  125.85
    4420  124.41  4575.6  118.29  4646.3  111.72  4741.8  108.78  4973.6  101.58
  4974.1  101.08    4998  101.58  5080.2  104.22  5260.1  113.72  5366.9  119.82
  5524.1  125.64  5695.4  129.94  5839.8  130.07  5984.4  125.62    6042  124.89
  6133.8  125.49  6223.8  126.17  6424.5  124.57  6455.3  124.11  6638.8  124.09
#Mann= 19 ,-1 , 0
  3071.6     .05       0  3274.3     .07       0    3448      .1       0
  3542.6     .07       0    3575      .1       0    4066      .1       0
  4347.6     .07       0  4741.8      .1       0  4973.6     .05       0
    4998      .1       0  5080.2     .07       0  5260.1      .1       0
  5366.9     .07       0  5695.4    .035       0  5839.8     .07       0
    6042    .035       0  6133.8     .07       0  6424.5      .1       0
  6455.3     .07       0
Bank Sta=4973.6,4998
XS Rating Curve= 0 ,0
Exp/Cntr=0.3,0.1

Chan Stop Cuts=-1
Use User Specified Reach Order=0
Composite Channel Slope=5