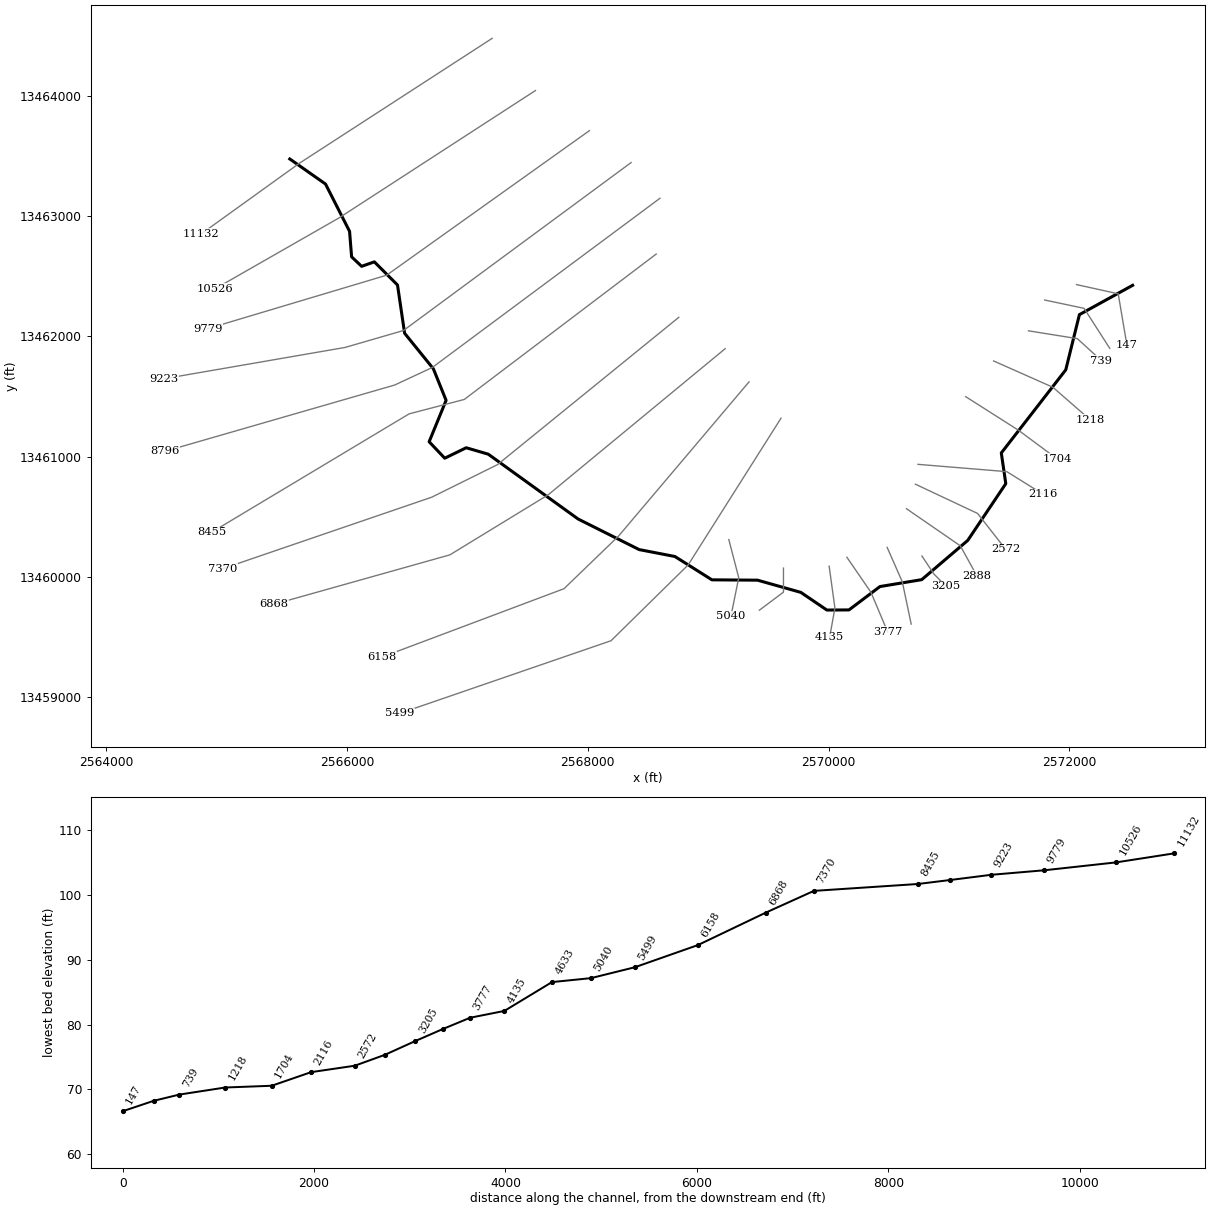
--- TRIB 1 TO BOGGY CREEK.prj (project) ---

Proj Title=TRIB 1 TO BOGGY CREEK Base Level Engineering
Current Plan=p01
Default Exp/Contr=0.3,0.1
English Units
Geom File=g01
Flow File=f01
Plan File=p01
Y Axis Title=Elevation
X Axis Title(PF)=Main Channel Distance
X Axis Title(XS)=Station
BEGIN DESCRIPTION:
TRIB 1 TO BOGGY CREEK
END DESCRIPTION:
DSS Export Rating Curves= 0
DSS Export Rating Curve Sorted= 0
DSS Export Volume Flow Curves= 0
DXF OffsetX= 0
DXF OffsetY= 0
DXF ScaleX= 1
DXF ScaleY= 10

--- TRIB 1 TO BOGGY CREEK.p01 (plan) ---

Plan Title=Multiple Run
Short Identifier=Multiple
Geom File=g01
Flow File=f01
Subcritical Flow
K Sum by GR= 0
Std Step Tol= 0.01
Critical Tol= 0.01
Num of Std Step Trials= 20
Max Error Tol= 0.3
Flow Tol Ratio= 0.001
Split Flow NTrial= 30
Split Flow Tol= 0.02
Split Flow Ratio= 0.02
Log Output Level= 0
Friction Slope Method= 1
Unsteady Friction Slope Method= 2
Unsteady Bridges Friction Slope Method= 1
Parabolic Critical Depth
Global Vel Dist=  1 , 1 , 1
Global Log Level= 0
CheckData=True
Encroach Param= -1, 0, 0, 0
BEGIN DESCRIPTION:
Multiple Run
END DESCRIPTION:

--- TRIB 1 TO BOGGY CREEK.f01 (steady flow) ---

Flow Title=Multiple
Number of Profiles=7
Profile Names=10-year,25-year,50-year,1pct_min,100-year,1pct_plu,500-year
River Rch & RM= TRIB 1 TO BOGGY ,Reach-1,11132
     468     712     917     572    1140    2275    1741
River Rch & RM= TRIB 1 TO BOGGY ,Reach-1,10526
     549     841    1091     683    1364    2721    2105
River Rch & RM= TRIB 1 TO BOGGY ,Reach-1,7370
     809    1274    1683    1073    2142    4273    3427
River Rch & RM= TRIB 1 TO BOGGY ,Reach-1,5040
    1044    1674    2238    1444    2881    5748    4720
Boundary for River Rch & Prof#=TRIB 1 TO BOGGY ,Reach-1,1
Up Type=0
Dn Type=3
Dn Slope=0.005
Boundary for River Rch & Prof#=TRIB 1 TO BOGGY ,Reach-1,2
Up Type=0
Dn Type=3
Dn Slope=0.005
Boundary for River Rch & Prof#=TRIB 1 TO BOGGY ,Reach-1,3
Up Type=0
Dn Type=3
Dn Slope=0.005
Boundary for River Rch & Prof#=TRIB 1 TO BOGGY ,Reach-1,4
Up Type=0
Dn Type=3
Dn Slope=0.005
Boundary for River Rch & Prof#=TRIB 1 TO BOGGY ,Reach-1,5
Up Type=0
Dn Type=3
Dn Slope=0.005
Boundary for River Rch & Prof#=TRIB 1 TO BOGGY ,Reach-1,6
Up Type=0
Dn Type=3
Dn Slope=0.005
Boundary for River Rch & Prof#=TRIB 1 TO BOGGY ,Reach-1,7
Up Type=0
Dn Type=3
Dn Slope=0.005

--- TRIB 1 TO BOGGY CREEK.g01 (geometry) ---

Geom Title=Existing Conditions
Program Version=4.10

River Reach=TRIB 1 TO BOGGY ,Reach-1
Reach XY= 30
        2565525.       13463475.      2565821.83     13463266.66
      2566021.45     13462873.53      2566038.37     13462661.62
      2566121.58     13462582.81       2566227.3     13462619.89
      2566419.54     13462427.66      2566478.62      13462026.5
      2566717.25     13461731.45       2566823.2     13461468.89
      2566682.29     13461124.91      2566811.79     13460988.11
      2566990.34     13461075.04       2567173.5     13461021.38
      2567918.94     13460483.14       2568426.5     13460228.62
      2568723.44     13460171.24      2569030.93     13459977.24
      2569409.78     13459974.48      2569769.31     13459872.98
       2569985.5     13459726.22      2570169.07     13459727.24
      2570426.46     13459921.46      2570773.42     13459978.82
      2571155.37     13460304.85      2571471.45     13460776.47
      2571434.15     13461031.73      2571969.52     13461722.56
       2572082.8     13462181.21        2572525.       13462425.

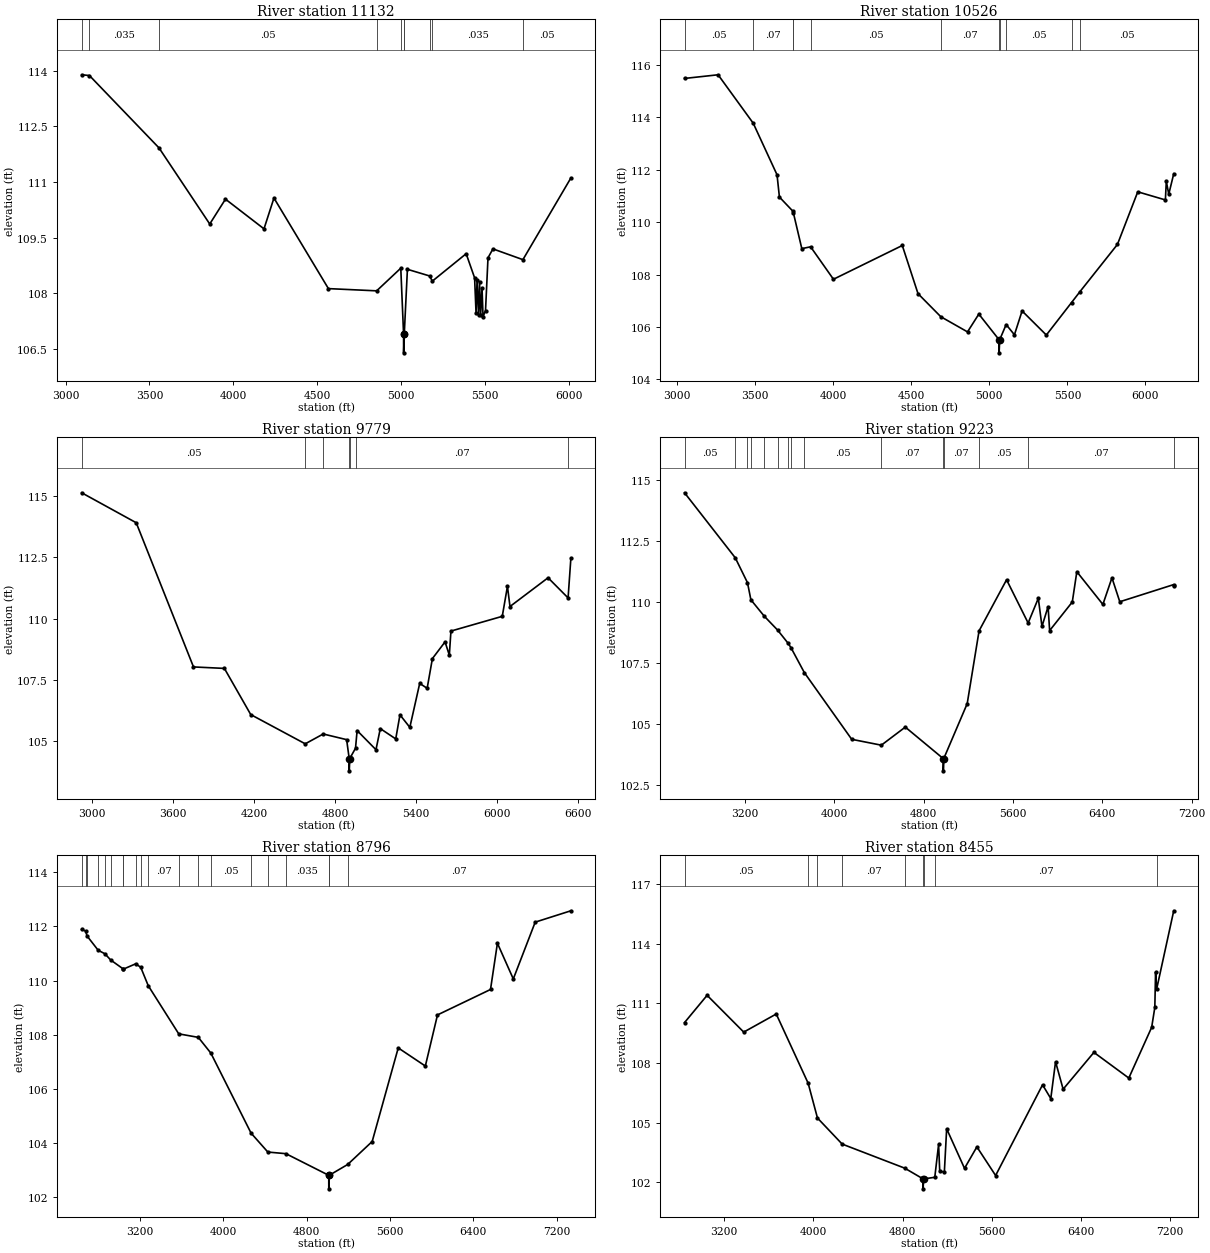
Type RM Length L Ch R = 1 ,11132   ,606,606,606
BEGIN DESCRIPTION:
TRIB 1 TO BOGGY CREEK 22.0
END DESCRIPTION:
XS GIS Cut Line= 3
      2567205.82     13464477.59      2565608.46     13463441.97
      2564788.75     13462852.08
#Sta/Elev= 30
  3096.3  113.89  3142.3  113.87  3556.9  111.92    3859  109.87  3952.6  110.54
  4182.1  109.74  4241.4  110.57  4565.8  108.13  4853.2  108.07  4996.8  108.68
  5013.5   106.9  5013.7   106.4  5017.5   106.9  5036.3  108.65  5169.2  108.47
  5184.4  108.33  5386.2  109.07  5436.5  108.42  5445.1  107.47  5451.2  108.37
  5459.8  107.41  5465.9   108.3  5472.4  107.42  5480.7  108.15  5486.8  107.37
  5501.5  107.54  5516.3  108.96  5545.7   109.2  5724.2  108.91  6009.9  111.11
#Mann= 10 ,-1 , 0
  3096.3     .05       0  3142.3    .035       0  3556.9     .05       0
  4853.2     .07       0  4996.8    .035       0  5013.5    .035       0
  5017.5    .035       0  5169.2     .05       0  5184.4    .035       0
  5724.2     .05       0
Bank Sta=5013.5,5017.5
XS Rating Curve= 0 ,0
Exp/Cntr=0.3,0.1

Type RM Length L Ch R = 1 ,10526   ,747,747,747
BEGIN DESCRIPTION:
Mapping XS 70f53312
END DESCRIPTION:
XS GIS Cut Line= 3
      2567565.15     13464043.77      2565933.23     13462984.76
      2564901.94     13462394.46
#Sta/Elev= 30
  3047.5  115.49  3262.4  115.63  3487.5  113.78    3640  111.81  3655.2  110.96
  3743.1  110.41  3744.2  110.37  3798.7  108.99  3855.1  109.06  4001.4  107.82
  4442.4  109.11  4543.1  107.27    4689  106.39  4860.2  105.81  4932.7  106.49
  5062.3  105.51  5062.6  105.01  5066.3  105.51  5107.7  106.09  5160.7   105.7
  5209.8  106.61  5365.1  105.69  5526.5  106.93  5580.9  107.35  5820.5  109.15
  5950.8  111.16  6127.8  110.85  6133.6  111.56  6149.4  111.07  6181.2  111.85
#Mann= 11 ,-1 , 0
  3047.5     .05       0  3487.5     .07       0  3743.1     .05       0
  3744.2     .07       0  3855.1     .05       0    4689     .07       0
  5062.3     .05       0  5066.3     .07       0  5107.7     .05       0
  5526.5     .07       0  5580.9     .05       0
Bank Sta=5062.3,5066.3
XS Rating Curve= 0 ,0
Exp/Cntr=0.3,0.1

Type RM Length L Ch R = 1 ,9779    ,556,556,556
BEGIN DESCRIPTION:
Mapping XS 7766300c
END DESCRIPTION:
XS GIS Cut Line= 3
      2568013.44     13463710.45      2566329.41     13462509.06
      2564843.29     13462064.62
#Sta/Elev= 30
  2925.9  115.12  3329.4   113.9  3753.2  108.03  3981.8  107.97  4176.9  106.09
  4580.1   104.9  4713.1   105.3  4886.4  105.07  4905.3   104.3  4905.5   103.8
  4909.4   104.3  4952.1  104.72  4963.9  105.44  5103.5  104.66  5135.5  105.52
  5249.7   105.1    5281  106.08    5354  105.57  5427.1  107.36  5482.2  107.16
    5521  108.37  5614.6  109.05  5646.3  108.51  5658.2  109.49    6038  110.09
  6076.3  111.31  6095.1  110.49  6376.9  111.66    6525  110.84  6545.7  112.46
#Mann= 7 ,-1 , 0
  2925.9     .05       0  4580.1     .07       0  4713.1     .05       0
  4905.3     .05       0  4909.4     .05       0  4952.1     .07       0
    6525    .035       0
Bank Sta=4905.3,4909.4
XS Rating Curve= 0 ,0
Exp/Cntr=0.3,0.1

Type RM Length L Ch R = 1 ,9223    ,427,427,427
BEGIN DESCRIPTION:
Mapping XS 28ba56e6
END DESCRIPTION:
XS GIS Cut Line= 4
      2568359.63     13463445.18        2566469.     13462049.34
      2565984.62     13461908.72      2564479.73     13461648.36
#Sta/Elev= 30
  2657.2  114.48  3111.4  111.82    3221   110.8  3251.5   110.1  3371.2  109.43
  3490.9  108.86  3584.9  108.32  3610.6  108.14  3730.3  107.12  4154.6  104.39
  4419.9  104.15  4634.5  104.89  4974.7   103.6    4975   103.1  4978.9   103.6
    5189  105.85  5295.3  108.83  5541.7  110.92  5734.8  109.15  5825.9  110.16
  5858.7  109.01  5913.4  109.82  5927.4  108.84  6130.3  110.01  6170.9  111.25
  6404.3  109.91  6485.5     111  6555.7  110.02  7036.9  110.72  7038.9  110.66
#Mann= 15 ,-1 , 0
  2657.2     .05       0  3111.4    .035       0    3221     .05       0
  3251.5    .035       0  3371.2     .05       0  3490.9    .035       0
  3584.9     .05       0  3610.6    .035       0  3730.3     .05       0
  4419.9     .07       0  4974.7     .05       0  4978.9     .07       0
  5295.3     .05       0  5734.8     .07       0  7036.9    .035       0
Bank Sta=4974.7,4978.9
XS Rating Curve= 0 ,0
Exp/Cntr=0.3,0.1

Type RM Length L Ch R = 1 ,8796    ,341,341,341
BEGIN DESCRIPTION:
Mapping XS 67a90a9f
END DESCRIPTION:
XS GIS Cut Line= 4
      2568599.18     13463148.28      2566708.58     13461742.05
      2566396.08     13461596.22       2564484.6     13461044.13
#Sta/Elev= 30
  2643.9  111.89    2682  111.83    2695  111.65    2802  111.12  2866.7  110.99
    2922  110.76  3038.4  110.44    3042  110.42  3162.1  110.62  3210.1  110.49
  3282.1  109.81  3574.4  108.03  3762.1   107.9  3882.1  107.32    4268  104.36
  4428.9  103.66  4602.1   103.6    5013   102.8  5013.3   102.3  5017.2   102.8
  5194.3   103.2  5429.4  104.05  5679.2  107.51  5939.1  106.84  6055.6  108.73
  6563.9  109.67  6630.2  111.38  6782.5  110.06  6992.5  112.16  7334.6  112.58
#Mann= 20 ,-1 , 0
  2643.9    .035       0    2682     .05       0    2695    .035       0
    2802     .05       0  2866.7    .035       0    2922     .05       0
  3038.4    .035       0    3042     .05       0  3162.1     .07       0
  3210.1     .05       0  3282.1     .07       0  3574.4     .05       0
  3762.1    .035       0  3882.1     .05       0    4268     .07       0
  4428.9     .05       0  4602.1    .035       0    5013    .035       0
  5017.2    .035       0  5194.3     .07       0
Bank Sta=5013,5017.2
XS Rating Curve= 0 ,0
Exp/Cntr=0.3,0.1

Type RM Length L Ch R = 1 ,8455    ,1085,1085,1085
BEGIN DESCRIPTION:
Mapping XS 69301086
END DESCRIPTION:
XS GIS Cut Line= 4
      2568567.96     13462684.76      2566974.21     13461476.43
      2566515.87     13461356.63      2564875.28     13460372.28
#Sta/Elev= 30
  2845.2  110.04  3047.6  111.41    3376  109.56  3667.5  110.47  3953.7  106.99
  4037.3  105.24  4258.8  103.93  4819.6  102.72  4984.4  102.18  4984.7  101.68
  4988.9  102.18  5089.3  102.26  5123.5  103.91  5133.8  102.56  5175.2  102.53
  5195.8   104.7    5356  102.71  5466.8  103.79  5634.9  102.35  6055.8  106.91
  6129.6  106.22  6172.4  108.07  6240.4  106.69  6516.4  108.54  6829.3  107.25
  7034.3   109.8  7062.6   110.8  7069.3  112.58  7079.2  111.73  7232.2  115.66
#Mann= 9 ,-1 , 0
  2845.2     .05       0  3953.7    .035       0  4037.3     .05       0
  4258.8     .07       0  4819.6    .035       0  4984.4    .035       0
  4988.9    .035       0  5089.3     .07       0  7079.2    .035       0
Bank Sta=4984.4,4988.9
XS Rating Curve= 0 ,0
Exp/Cntr=0.3,0.1

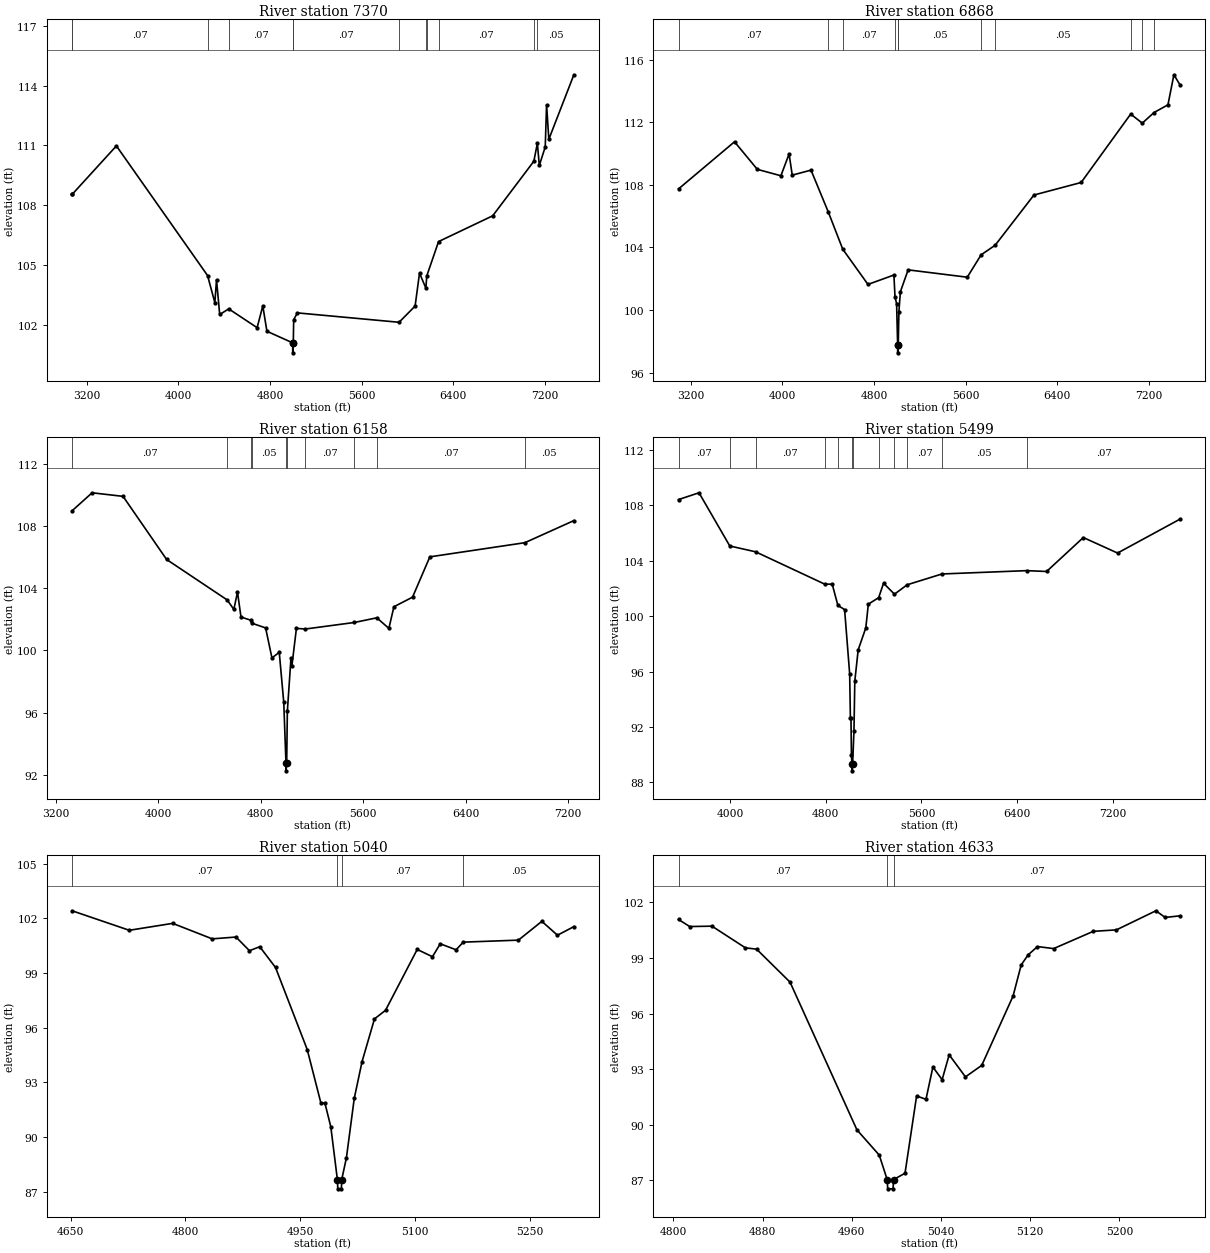
Type RM Length L Ch R = 1 ,7370    ,502,502,502
BEGIN DESCRIPTION:
Mapping XS 7cdc8523
END DESCRIPTION:
XS GIS Cut Line= 4
      2568755.43     13462158.69      2567250.25     13460934.76
      2566703.37     13460663.93      2564969.52     13460070.36
#Sta/Elev= 30
  3070.7  108.56  3072.7  108.56  3457.9  110.98  4254.2  104.49  4317.9  103.13
  4332.3  104.28  4360.1  102.54  4439.4  102.82  4687.1  101.88  4736.6  102.97
  4772.6   101.7  4997.7  101.12  4998.1  100.62  5002.9  101.12  5006.5  102.28
  5038.6  102.62  5926.8  102.15  6066.9  102.96  6105.5  104.61    6161  103.86
  6168.9  104.47  6271.8  106.19  6744.7  107.48    7104  110.21  7134.9  111.11
  7151.9     110  7203.6  110.93  7215.3  113.04  7234.9  111.31  7453.6  114.54
#Mann= 12 ,-1 , 0
  3070.7     .05       0  3072.7     .07       0  4254.2    .035       0
  4439.4     .07       0  4997.7     .05       0  5002.9     .07       0
  5926.8    .035       0    6161     .07       0  6168.9    .035       0
  6271.8     .07       0    7104    .035       0  7134.9     .05       0
Bank Sta=4997.7,5002.9
XS Rating Curve= 0 ,0
Exp/Cntr=0.3,0.1

Type RM Length L Ch R = 1 ,6868    ,710,710,710
BEGIN DESCRIPTION:
Mapping XS f21ded98
END DESCRIPTION:
XS GIS Cut Line= 4
      2569140.88     13461898.31      2567672.12     13460684.76
      2566854.41     13460184.76      2565390.86      13459773.3
#Sta/Elev= 30
  3091.7  107.74  3580.8  110.75  3780.1  108.99  3985.9  108.58  4057.6  109.97
  4085.2  108.62  4249.1  108.94  4401.5  106.24  4526.4  103.89  4746.7  101.64
  4973.4  102.24    4983  100.84  4996.9  100.41    5006   97.77  5006.4   97.27
  5011.2   97.77    5017    99.9  5029.9  101.17  5097.6  102.57  5614.2   102.1
  5735.3  103.53  5857.6  104.14  6196.8  107.35  6609.2  108.15    7042  112.52
  7143.3  111.94  7246.1  112.62  7367.5  113.11  7419.5  115.03  7475.7  114.35
#Mann= 11 ,-1 , 0
  3091.7     .07       0  4401.5    .035       0  4526.4     .07       0
    4983     .05       0    5006     .05       0  5011.2     .05       0
  5735.3     .07       0  5857.6     .05       0    7042     .07       0
  7143.3    .035       0  7246.1     .07       0
Bank Sta=5006,5011.2
XS Rating Curve= 0 ,0
Exp/Cntr=0.3,0.1

Type RM Length L Ch R = 1 ,6158    ,659,659,659
BEGIN DESCRIPTION:
Mapping XS d22fc37d
END DESCRIPTION:
XS GIS Cut Line= 4
      2569338.81     13461622.28      2568255.46     13460341.01
      2567802.33     13459903.51      2566291.95     13459335.81
#Sta/Elev= 30
    3325  108.98  3481.6  110.14  3723.3  109.91    4064  105.85    4537  103.25
  4589.2  102.64  4617.7  103.75  4645.1  102.15  4720.5  101.95  4727.8  101.76
  4837.5  101.45  4886.9   99.52  4944.1   99.88  4979.2   96.67  4996.6   92.76
  4997.1   92.26  5002.1   92.76  5007.4    96.1  5035.7   99.51  5042.9   99.02
  5078.2  101.42  5148.5  101.38  5530.9   101.8  5706.5   102.1  5800.8  101.42
    5840  102.81  5985.8  103.43  6120.9  106.02  6863.4  106.93  7246.3  108.35
#Mann= 10 ,-1 , 0
    3325     .07       0    4537    .035       0  4720.5     .07       0
  4727.8     .05       0  4996.6     .05       0  5002.1     .05       0
  5148.5     .07       0  5530.9     .05       0  5706.5     .07       0
  6863.4     .05       0
Bank Sta=4996.6,5002.1
XS Rating Curve= 0 ,0
Exp/Cntr=0.3,0.1

Type RM Length L Ch R = 1 ,5499    ,459,459,459
BEGIN DESCRIPTION:
Mapping XS 05c10ccc
END DESCRIPTION:
XS GIS Cut Line= 4
      2569604.41     13461320.16      2568833.58     13460101.43
      2568192.96     13459471.22      2566438.85     13458867.43
#Sta/Elev= 30
  3568.6  108.42  3739.8  108.91  3997.2  105.07  4212.8  104.65  4789.9  102.32
  4853.7  102.31    4901  100.78  4957.2  100.48  4999.6   95.83  5005.6   92.63
  5010.6   92.63  5014.2   89.99  5018.6   89.34    5019   88.84  5024.1   89.34
  5035.4   91.69  5042.5   95.32  5070.7   97.57  5134.5   99.16  5155.6  100.87
  5241.9  101.34  5282.9  102.38  5374.2  101.59  5480.4  102.27  5771.3  103.05
  6479.6  103.29  6646.3  103.23  6953.3  105.68  7239.7  104.56  7764.4  107.02
#Mann= 12 ,-1 , 0
  3568.6     .07       0  3997.2     .05       0  4212.8     .07       0
  4789.9    .035       0    4901     .05       0  5018.6     .05       0
  5024.1     .05       0  5241.9     .07       0  5374.2     .05       0
  5480.4     .07       0  5771.3     .05       0  6479.6     .07       0
Bank Sta=5018.6,5024.1
XS Rating Curve= 0 ,0
Exp/Cntr=0.3,0.1

Type RM Length L Ch R = 1 ,5040    ,407,407,407
BEGIN DESCRIPTION:
Mapping XS f8008f53
END DESCRIPTION:
XS GIS Cut Line= 3
      2569171.11     13460312.06      2569253.57     13459995.23
      2569188.46     13459674.04
#Sta/Elev= 30
    4652  102.41  4726.7  101.34  4783.3  101.72    4835  100.87    4866  100.97
  4883.6  100.22    4897  100.44  4917.6    99.3    4959    94.8  4976.9   91.86
  4982.1   91.86  4989.8   90.56  4998.4   87.66  4998.9   87.16  5003.6   87.16
    5004   87.66  5010.2   88.87  5020.4   92.12  5030.6   94.14  5046.8   96.48
  5061.2   96.95  5102.6  100.29  5122.5   99.89  5132.7   100.6  5153.3  100.27
  5162.7  100.69  5234.7   100.8  5265.3  101.83  5285.7  101.07  5307.1  101.54
#Mann= 4 ,-1 , 0
    4652     .07       0  4998.4     .05       0    5004     .07       0
  5162.7     .05       0
Bank Sta=4998.4,5004
XS Rating Curve= 0 ,0
Exp/Cntr=0.3,0.1

Type RM Length L Ch R = 1 ,4633    ,498,498,498
BEGIN DESCRIPTION:
TRIB 1 TO BOGGY CREEK 10.0
END DESCRIPTION:
XS GIS Cut Line= 3
        2569625.     13460074.98        2569625.       13459875.
      2569424.98     13459724.99
#Sta/Elev= 30
  4804.6  101.08  4814.6   100.7  4834.6  100.72  4864.6   99.55  4874.6   99.48
  4904.6    97.7  4964.6   89.73  4984.6   88.37  4991.7   87.05  4992.2   86.55
    4997   86.55  4997.4   87.05  5007.7   87.39  5018.1   91.56  5026.5   91.38
  5032.7   93.12    5041   92.44  5047.3   93.78  5061.9   92.59  5076.5   93.21
  5104.6   96.95  5111.9   98.63  5118.1   99.17  5126.5   99.62    5141   99.51
  5176.5  100.44  5197.3  100.52  5232.7  101.55    5241  101.19  5254.6  101.28
#Mann= 3 ,-1 , 0
  4804.6     .07       0  4991.7     .05       0  4997.4     .07       0
Bank Sta=4991.7,4997.4
XS Rating Curve= 0 ,0
Exp/Cntr=0.3,0.1

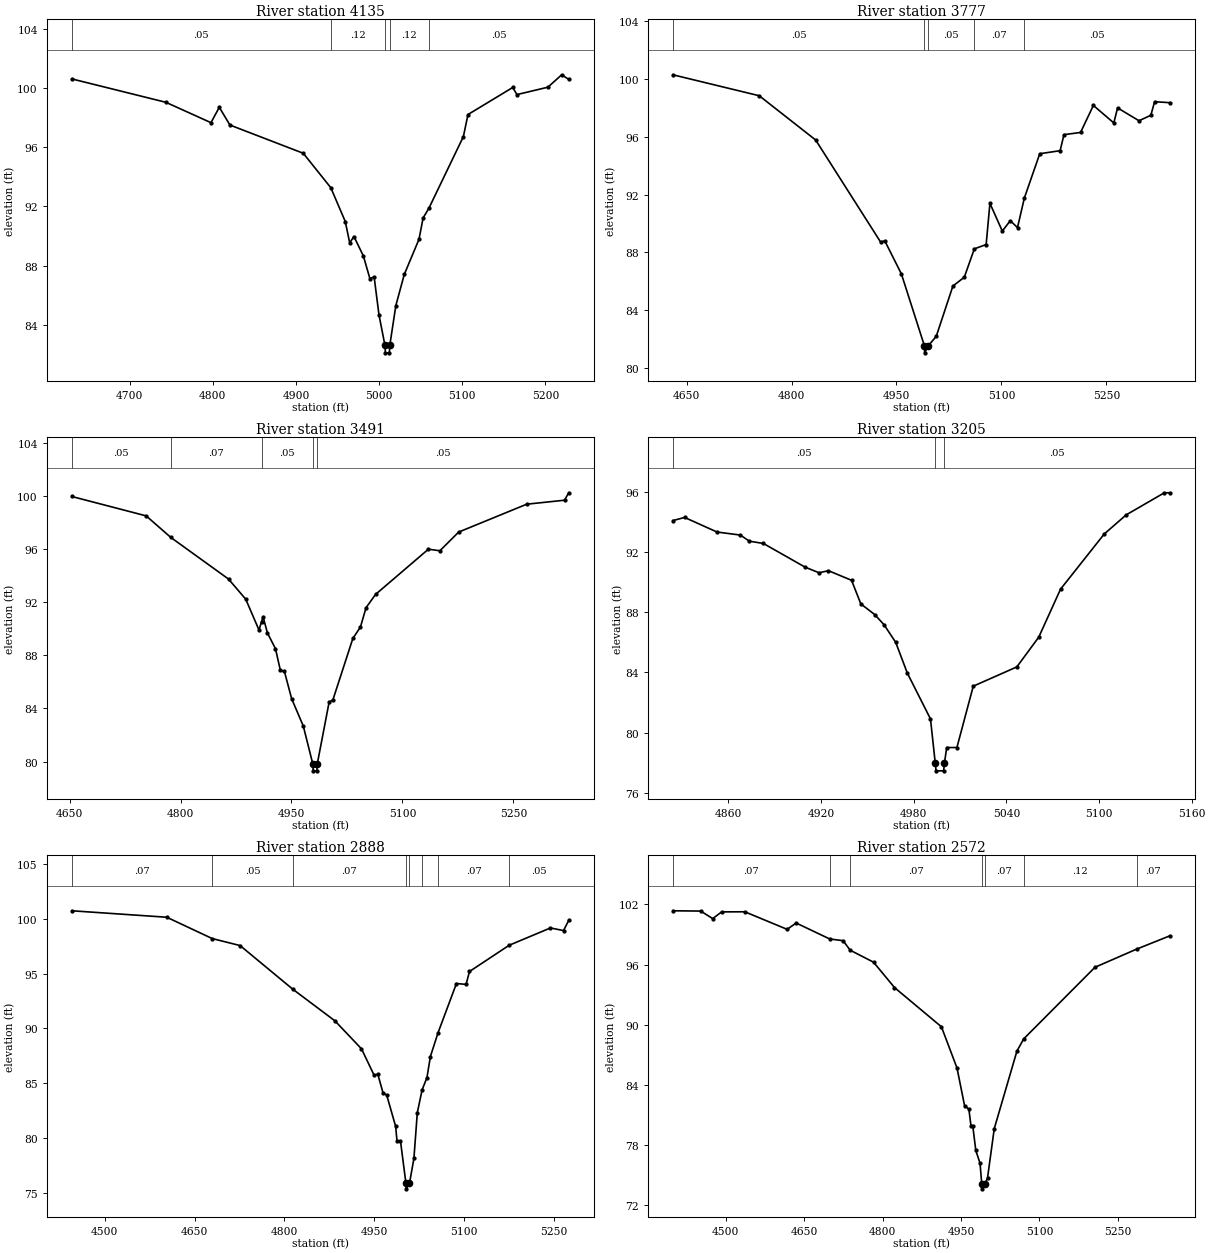
Type RM Length L Ch R = 1 ,4135    ,358,358,358
BEGIN DESCRIPTION:
Mapping XS cc72da79
END DESCRIPTION:
XS GIS Cut Line= 3
      2570004.44     13460090.69      2570052.18     13459743.49
      2570008.77     13459500.41
#Sta/Elev= 30
  4630.5  100.63  4743.5   99.05  4797.8   97.67  4807.8   98.71  4820.6   97.51
  4908.8    95.6  4941.9   93.27  4959.3   90.98  4964.6   89.54  4969.7   89.97
    4981   88.66  4988.9   87.12    4994   87.23  4999.8   84.67    5007    82.6
  5007.5    82.1  5012.3    82.1  5012.8    82.6  5020.1    85.3  5030.2    87.4
  5047.9   89.78  5052.9   91.23  5059.8   91.88  5101.3   96.73  5106.8   98.22
  5160.6  100.05  5165.7   99.57  5202.9  100.07  5219.5  100.91  5227.9   100.6
#Mann= 5 ,-1 , 0
  4630.5     .05       0  4941.9     .12       0    5007     .05       0
  5012.8     .12       0  5059.8     .05       0
Bank Sta=5007,5012.8
XS Rating Curve= 0 ,0
Exp/Cntr=0.3,0.1

Type RM Length L Ch R = 1 ,3777    ,286,286,286
BEGIN DESCRIPTION:
Mapping XS c0240ee8
END DESCRIPTION:
XS GIS Cut Line= 3
        2570152.      13460164.5      2570351.66      13459873.7
      2570490.26     13459544.53
#Sta/Elev= 30
  4630.5  100.28  4753.9   98.83  4834.5   95.77  4927.2   88.72  4933.3   88.79
    4957   86.51  4989.8   81.55  4990.2   81.05  4995.6   81.55  5006.8   82.19
  5030.6   85.67  5046.9   86.28  5061.2   88.24  5078.1   88.54  5083.5   91.39
  5101.2   89.47  5112.6   90.19  5122.9   89.71  5132.7   91.76  5154.7   94.82
  5183.8   95.03  5189.3   96.14    5213   96.29  5231.3   98.16  5260.5   96.95
  5265.9   97.99  5296.5    97.1  5313.4   97.48  5318.8   98.42  5340.4   98.35
#Mann= 5 ,-1 , 0
  4630.5     .05       0  4989.8     .05       0  4995.6     .05       0
  5061.2     .07       0  5132.7     .05       0
Bank Sta=4989.8,4995.6
XS Rating Curve= 0 ,0
Exp/Cntr=0.3,0.1

Type RM Length L Ch R = 1 ,3491    ,286,286,286
BEGIN DESCRIPTION:
Mapping XS c4930652
END DESCRIPTION:
XS GIS Cut Line= 3
      2570486.19       13460247.      2570612.08      13459960.5
      2570685.75     13459609.48
#Sta/Elev= 30
  4653.1   99.97  4753.6   98.51  4786.8   96.89  4864.9   93.75  4888.2   92.23
  4906.1   89.91  4909.6   90.55  4911.6   90.92  4917.4    89.7  4928.4    88.5
  4934.9   86.89  4940.4    86.8  4950.2   84.74    4966   82.67  4978.9    79.8
  4979.4    79.3  4984.3    79.3  4984.8    79.8  5000.9   84.48    5006   84.65
    5033   89.28  5043.2   90.13  5050.8   91.59  5063.6   92.59  5135.1      96
  5150.6   95.88    5176   97.29    5268   99.39  5319.1   99.69  5324.7  100.25
#Mann= 5 ,-1 , 0
  4653.1     .05       0  4786.8     .07       0  4909.6     .05       0
  4978.9     .05       0  4984.8     .05       0
Bank Sta=4978.9,4984.8
XS Rating Curve= 0 ,0
Exp/Cntr=0.3,0.1

Type RM Length L Ch R = 1 ,3205    ,317,317,317
BEGIN DESCRIPTION:
TRIB 1 TO BOGGY CREEK 7.0
END DESCRIPTION:
XS GIS Cut Line= 3
      2570774.98     13460175.03        2570875.       13460025.
      2570974.97     13459925.03
#Sta/Elev= 30
  4824.1    94.1  4831.7   94.31  4852.7   93.34  4867.7   93.14  4873.7   92.73
  4882.7   92.58  4909.8      91  4918.8   90.63  4924.8   90.77  4939.8   90.13
  4945.8   88.56  4954.8   87.85  4960.8   87.18  4968.4      86  4975.9   83.96
  4990.9   80.91    4994   77.96  4994.5   77.46  4999.4   77.46  4999.9   77.96
  5001.4   79.01    5008   79.01  5018.6   83.09  5046.8   84.37    5061   86.35
  5075.1   89.54  5103.4   93.21  5117.6   94.48  5142.3   95.95  5145.8   95.95
#Mann= 3 ,-1 , 0
  4824.1     .05       0    4994     .05       0  4999.9     .05       0
Bank Sta=4994,4999.9
XS Rating Curve= 0 ,0
Exp/Cntr=0.3,0.1

Type RM Length L Ch R = 1 ,2888    ,316,316,316
BEGIN DESCRIPTION:
Mapping XS 30136633
END DESCRIPTION:
XS GIS Cut Line= 3
      2570646.81     13460568.13      2571093.85     13460259.98
      2571232.27     13460009.09
#Sta/Elev= 30
  4445.1  100.76  4603.6  100.17  4679.5   98.22    4726   97.58    4814   93.59
  4884.3    90.7  4928.7   88.14  4949.9   85.71  4955.9   85.83  4964.7    84.1
  4970.8   83.91  4985.7   81.05    4988   79.71  4993.8   79.71  5002.9   75.84
  5003.3   75.34  5008.8   75.84  5016.2   78.12  5021.9   82.31  5029.9   84.39
    5038   85.51  5043.7   87.43  5056.5   89.61  5087.2   94.11  5103.3   94.03
    5109   95.21  5175.3   97.61  5244.2   99.19    5266   98.95  5274.6   99.88
#Mann= 8 ,-1 , 0
  4445.1     .07       0  4679.5     .05       0    4814     .07       0
  5002.9     .05       0  5008.8     .07       0  5029.9     .12       0
  5056.5     .07       0  5175.3     .05       0
Bank Sta=5002.9,5008.8
XS Rating Curve= 0 ,0
Exp/Cntr=0.3,0.1

Type RM Length L Ch R = 1 ,2572    ,456,456,456
BEGIN DESCRIPTION:
Mapping XS 6e4468a6
END DESCRIPTION:
XS GIS Cut Line= 3
      2570720.57     13460772.14      2571237.08     13460529.08
      2571470.57     13460230.73
#Sta/Elev= 30
  4399.3  101.36  4452.6  101.33  4475.4  100.58  4492.6  101.25  4536.8  101.26
  4617.7   99.51    4635  100.14  4699.1   98.55  4724.7   98.38  4738.2   97.43
  4782.8   96.24  4822.9   93.71  4912.6    89.8  4942.4   85.69  4956.8   81.95
  4965.1   81.58  4969.1   79.94  4972.5   79.94  4978.3   77.48  4986.4    76.2
  4989.7   74.15  4990.2   73.65  4995.7   74.15  5000.7   74.72  5013.6   79.65
  5056.9   87.37  5069.8   88.59  5206.1   95.73  5285.8   97.54    5349   98.86
#Mann= 7 ,-1 , 0
  4399.3     .07       0  4699.1     .05       0  4738.2     .07       0
  4989.7     .05       0  4995.7     .07       0  5069.8     .12       0
  5285.8     .07       0
Bank Sta=4989.7,4995.7
XS Rating Curve= 0 ,0
Exp/Cntr=0.3,0.1

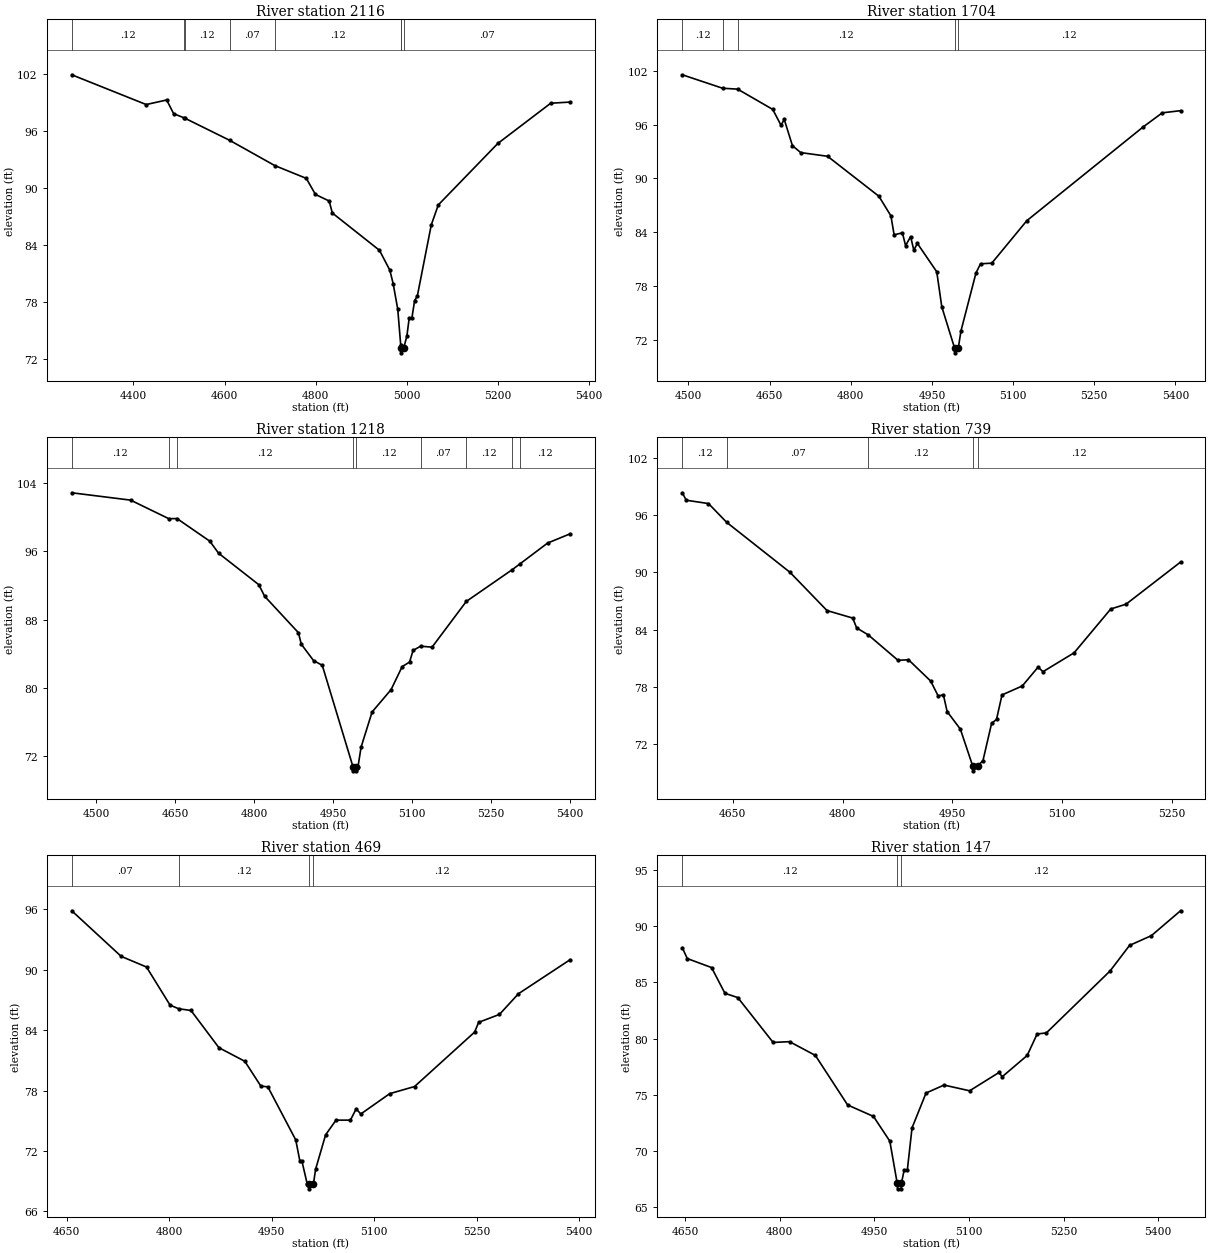
Type RM Length L Ch R = 1 ,2116    ,412,412,412
BEGIN DESCRIPTION:
Mapping XS 53039ca1
END DESCRIPTION:
XS GIS Cut Line= 3
      2570742.24     13460937.07      2571480.13      13460876.3
      2571779.39     13460689.81
#Sta/Elev= 30
  4264.6  101.89  4427.9   98.76  4472.8   99.24  4488.1    97.8  4510.5   97.37
  4512.1   97.34    4611      95  4709.8   92.35  4779.1      91  4799.2   89.31
  4829.3   88.62  4836.2   87.36  4939.6   83.44  4962.3   81.36  4969.7   79.93
  4979.8   77.23  4986.3   73.45  4986.8   73.16  4987.3   72.66  4992.8   73.16
  4999.8   74.43  5004.9   76.33  5010.8   76.33  5016.8   78.16  5022.7   78.63
  5053.3   86.11  5068.7   88.21  5199.3   94.67  5315.3    98.9  5357.6   99.02
#Mann= 8 ,-1 , 0
  4264.6     .12       0  4510.5     .07       0  4512.1     .12       0
    4611     .07       0  4709.8     .12       0  4986.3     .07       0
  4986.8     .05       0  4992.8     .07       0
Bank Sta=4986.8,4992.8
XS Rating Curve= 0 ,0
Exp/Cntr=0.3,0.1

Type RM Length L Ch R = 1 ,1704    ,486,486,486
BEGIN DESCRIPTION:
Mapping XS 5c70523b
END DESCRIPTION:
XS GIS Cut Line= 3
      2571138.55     13461499.57      2571576.05     13461220.92
      2571898.97     13460981.33
#Sta/Elev= 30
  4488.6  101.54  4563.1  100.04  4590.9   99.94  4655.8   97.68  4671.1   95.91
    4677   96.57  4692.2   93.64  4707.5   92.87  4757.1   92.46  4851.9   88.01
  4874.2   85.82  4880.1   83.71  4895.4   83.93  4901.3    82.5  4910.6   83.51
  4916.5      82  4923.1   82.75  4958.9   79.59  4968.2   75.69    4992   71.06
  4992.5   70.56  4998.6   71.06  5003.7   73.01  5031.4   79.46  5039.8   80.48
  5060.6   80.55  5125.3   85.28  5340.2   95.72  5375.7    97.3  5409.4   97.54
#Mann= 5 ,-1 , 0
  4488.6     .12       0  4563.1     .07       0  4590.9     .12       0
    4992     .05       0  4998.6     .12       0
Bank Sta=4992,4998.6
XS Rating Curve= 0 ,0
Exp/Cntr=0.3,0.1

Type RM Length L Ch R = 1 ,1218    ,479,479,479
BEGIN DESCRIPTION:
Mapping XS bf261944
END DESCRIPTION:
XS GIS Cut Line= 3
      2571370.34     13461796.43      2571862.51     13461577.69
      2572169.51     13461309.72
#Sta/Elev= 30
  4453.3  102.84    4565  101.98  4637.5   99.81  4653.2   99.82  4715.5   97.17
    4732   95.77  4808.5   92.08  4819.5   90.73  4883.7   86.46  4889.2   85.11
  4912.4    83.2    4929   82.64  4987.2   70.79  4987.7   70.29  4993.3   70.29
  4993.8   70.79  4996.9   70.79  5002.7   73.06  5023.6   77.18  5059.7    79.8
  5080.6   82.48  5094.8   83.03  5101.4   84.38  5115.6   84.88  5137.5   84.77
  5202.5   90.12    5290   93.85  5304.7   94.53  5356.8   96.95  5399.4   98.03
#Mann= 9 ,-1 , 0
  4453.3     .12       0  4637.5     .07       0  4653.2     .12       0
  4987.2     .05       0  4993.8     .12       0  5115.6     .07       0
  5202.5     .12       0    5290     .07       0  5304.7     .12       0
Bank Sta=4987.2,4993.8
XS Rating Curve= 0 ,0
Exp/Cntr=0.3,0.1

Type RM Length L Ch R = 1 ,739     ,270,270,270
BEGIN DESCRIPTION:
Mapping XS 8af4ec98
END DESCRIPTION:
XS GIS Cut Line= 3
      2571659.68     13462046.86      2572065.51     13461981.76
      2572264.89     13461799.72
#Sta/Elev= 30
    4581   98.36  4586.4   97.58  4616.8   97.23  4641.7   95.26  4728.2   90.02
  4778.8   86.01    4814   85.22  4819.3   84.19  4835.3   83.45  4875.9   80.79
  4890.2   80.85  4920.6   78.61  4930.7   77.06  4937.9   77.17    4943   75.42
  4961.1   73.57    4978    69.7  4978.5    69.2  4984.7    69.7    4992   70.28
  5003.8   74.18  5010.5   74.59    5018   77.16  5045.7    78.1  5067.3   80.07
  5074.1    79.6  5116.6   81.58  5166.6   86.17  5187.6   86.68    5262   91.09
#Mann= 5 ,-1 , 0
    4581     .12       0  4641.7     .07       0  4835.3     .12       0
    4978     .05       0  4984.7     .12       0
Bank Sta=4978,4984.7
XS Rating Curve= 0 ,0
Exp/Cntr=0.3,0.1

Type RM Length L Ch R = 1 ,469     ,322,322,322
BEGIN DESCRIPTION:
Mapping XS 0afe9e56
END DESCRIPTION:
XS GIS Cut Line= 3
      2571794.26     13462302.93      2572121.93     13462233.49
      2572334.63     13461901.42
#Sta/Elev= 30
  4657.2   95.87  4729.5   91.34  4766.6   90.28  4801.1   86.49  4813.8   86.13
  4831.7   85.96  4872.6   82.26  4910.5   80.91    4934   78.44  4944.2   78.37
  4985.1   73.09  4991.2   70.96  4994.2   70.96  5001.7   68.76  5004.3   68.73
  5004.8   68.23    5011   68.73  5014.1   70.17  5028.8    73.6    5044   75.06
  5065.1   75.06  5073.5   76.18  5080.3   75.67  5122.6   77.69    5159    78.4
  5246.9   83.81  5252.8   84.78  5283.3   85.57    5311   87.62  5386.5      91
#Mann= 4 ,-1 , 0
  4657.2     .07       0  4813.8     .12       0  5004.3     .05       0
    5011     .12       0
Bank Sta=5004.3,5011
XS Rating Curve= 0 ,0
Exp/Cntr=0.3,0.1

Type RM Length L Ch R = 1 ,147     ,0,0,0
BEGIN DESCRIPTION:
TRIB 1 TO BOGGY CREEK 1.0
END DESCRIPTION:
XS GIS Cut Line= 3
      2572059.02     13462430.97      2572405.19     13462354.55
      2572477.83     13461925.36
#Sta/Elev= 30
  4645.5   88.08  4653.4   87.11  4691.9   86.31  4713.1   84.02  4733.5   83.64
  4789.5   79.65  4815.5   79.72  4856.4    78.5  4907.6   74.09  4948.6   73.07
  4974.5   70.87  4986.2   67.13  4986.7   66.63  4992.4   66.63  4992.9   67.13
  4997.3   68.32  5002.3   68.32  5009.7   72.05  5031.9   75.15  5060.4   75.86
    5101   75.35  5147.6   76.98  5152.7    76.6  5192.2   78.49    5208    80.4
  5222.7    80.5  5323.7   86.01  5354.5   88.28  5389.2   89.15  5435.3   91.36
#Mann= 3 ,-1 , 0
  4645.5     .12       0  4986.2     .05       0  4992.9     .12       0
Bank Sta=4986.2,4992.9
XS Rating Curve= 0 ,0
Exp/Cntr=0.3,0.1

Chan Stop Cuts=-1
Use User Specified Reach Order=0
Composite Channel Slope=5