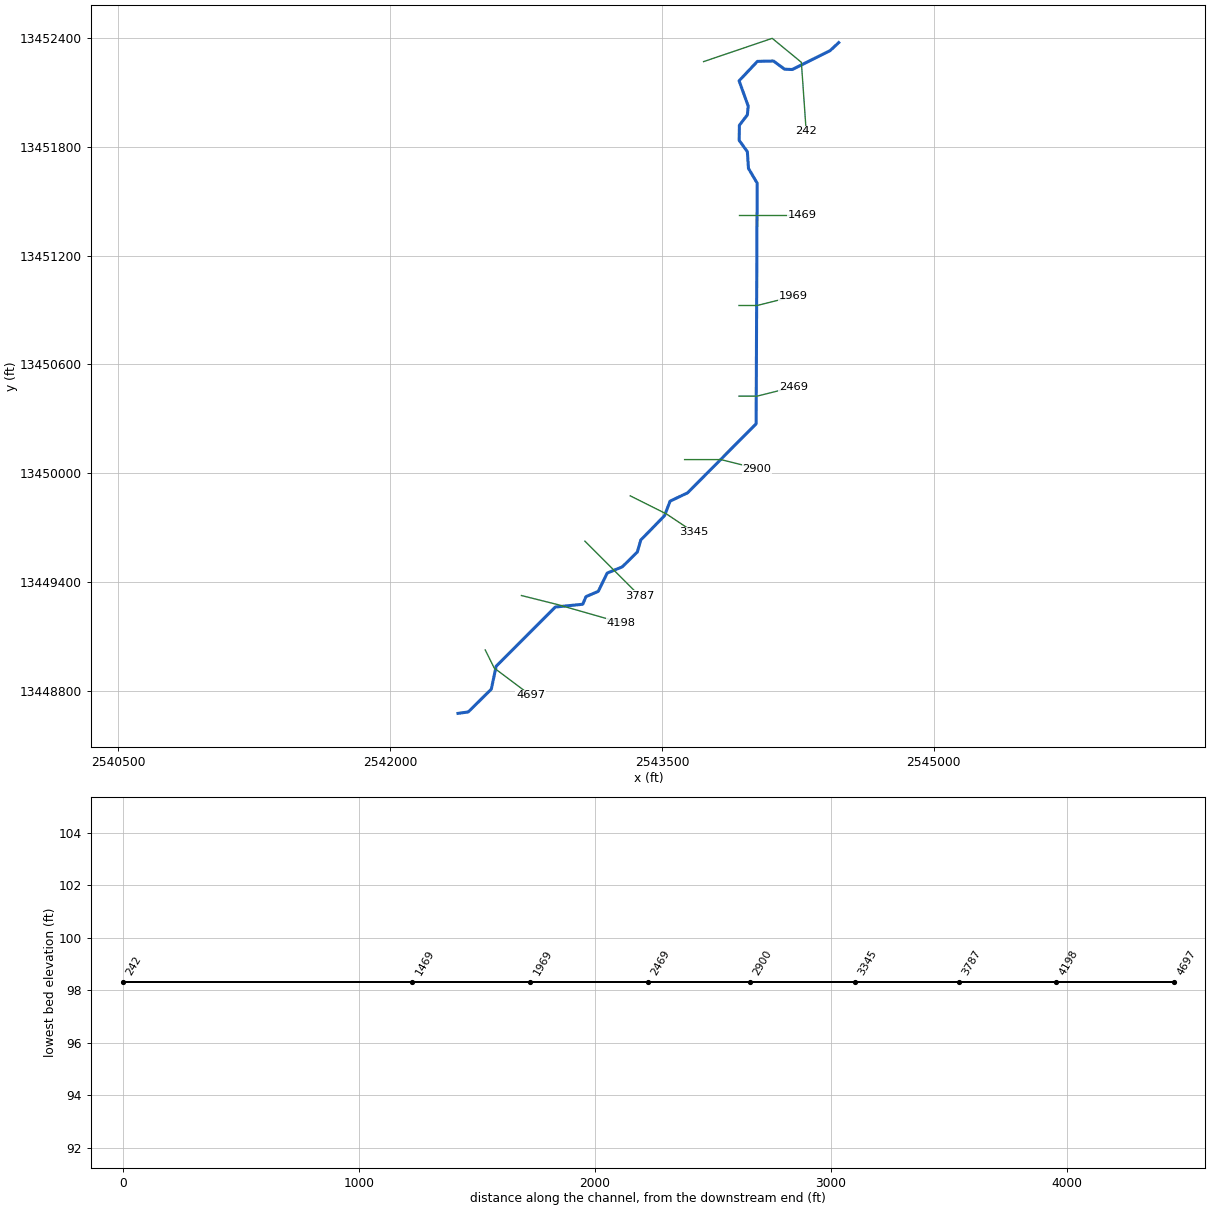
--- TRIB 1 TO COLETO CREEK RESERVOIR.prj (project) ---

Proj Title=TRIB 1 TO COLETO CREEK RESERVOIR Base Level Engineering
Current Plan=p01
Default Exp/Contr=0.3,0.1
English Units
Geom File=g01
Flow File=f01
Plan File=p01
Y Axis Title=Elevation
X Axis Title(PF)=Main Channel Distance
X Axis Title(XS)=Station
BEGIN DESCRIPTION:
TRIB 1 TO COLETO CREEK RESERVOIR
END DESCRIPTION:
DSS Export Rating Curves= 0
DSS Export Rating Curve Sorted= 0
DSS Export Volume Flow Curves= 0
DXF OffsetX= 0
DXF OffsetY= 0
DXF ScaleX= 1
DXF ScaleY= 10

--- TRIB 1 TO COLETO CREEK RESERVOIR.p01 (plan) ---

Plan Title=Multiple Run
Short Identifier=Multiple
Geom File=g01
Flow File=f01
Subcritical Flow
K Sum by GR= 0
Std Step Tol= 0.01
Critical Tol= 0.01
Num of Std Step Trials= 20
Max Error Tol= 0.3
Flow Tol Ratio= 0.001
Split Flow NTrial= 30
Split Flow Tol= 0.02
Split Flow Ratio= 0.02
Log Output Level= 0
Friction Slope Method= 1
Unsteady Friction Slope Method= 2
Unsteady Bridges Friction Slope Method= 1
Parabolic Critical Depth
Global Vel Dist=  1 , 1 , 1
Global Log Level= 0
CheckData=True
Encroach Param= -1, 0, 0, 0
BEGIN DESCRIPTION:
Multiple Run
END DESCRIPTION:

--- TRIB 1 TO COLETO CREEK RESERVOIR.f01 (steady flow) ---

Flow Title=Multiple
Program Version=4.10
Number of Profiles= 7
Profile Names=10-year,25-year,50-year,1pct_min,100-year,1pct_plu,500-year
River Rch & RM=TRIB 1 TO COLETO,Reach-1         ,4697
      32      39      43      23      46      92      53
Boundary for River Rch & Prof#=TRIB 1 TO COLETO,Reach-1         , 1
Up Type= 0
Dn Type= 3
Dn Slope=0.0001
Boundary for River Rch & Prof#=TRIB 1 TO COLETO,Reach-1         , 2
Up Type= 0
Dn Type= 3
Dn Slope=0.0001
Boundary for River Rch & Prof#=TRIB 1 TO COLETO,Reach-1         , 3
Up Type= 0
Dn Type= 3
Dn Slope=0.0001
Boundary for River Rch & Prof#=TRIB 1 TO COLETO,Reach-1         , 4
Up Type= 0
Dn Type= 3
Dn Slope=0.0001
Boundary for River Rch & Prof#=TRIB 1 TO COLETO,Reach-1         , 5
Up Type= 0
Dn Type= 3
Dn Slope=0.0001
Boundary for River Rch & Prof#=TRIB 1 TO COLETO,Reach-1         , 6
Up Type= 0
Dn Type= 3
Dn Slope=0.0001
Boundary for River Rch & Prof#=TRIB 1 TO COLETO,Reach-1         , 7
Up Type= 0
Dn Type= 3
Dn Slope=0.0001
DSS Import GetInterval= 0
DSS Import GetPeak= 0
DSS Import FillOption= 0

--- TRIB 1 TO COLETO CREEK RESERVOIR.g01 (geometry) ---

Geom Title=Existing Conditions
Program Version=4.10

River Reach=TRIB 1 TO COLETO,Reach-1
Reach XY= 30
        2542375.       13448675.      2542431.21     13448682.76
      2542558.54     13448808.25      2542585.52     13448934.79
      2542911.69     13449261.63      2543063.05     13449276.93
      2543080.83     13449318.93       2543148.7     13449347.91
      2543197.86     13449448.83      2543281.05     13449483.16
      2543364.23      13449565.3      2543383.16     13449631.05
      2543514.21     13449765.34      2543544.63     13449845.47
      2543641.66     13449891.66      2544019.54     13450272.55
       2544025.2     13451600.08      2543977.36     13451680.98
      2543971.14      13451773.4       2543926.1     13451835.55
      2543927.17     13451919.03      2543971.29      13451976.6
      2543975.81       13452025.      2543925.59     13452164.39
      2544026.48     13452271.54      2544114.45     13452273.88
      2544176.74     13452228.37      2544218.89      13452226.8
      2544427.36     13452330.67        2544475.       13452375.

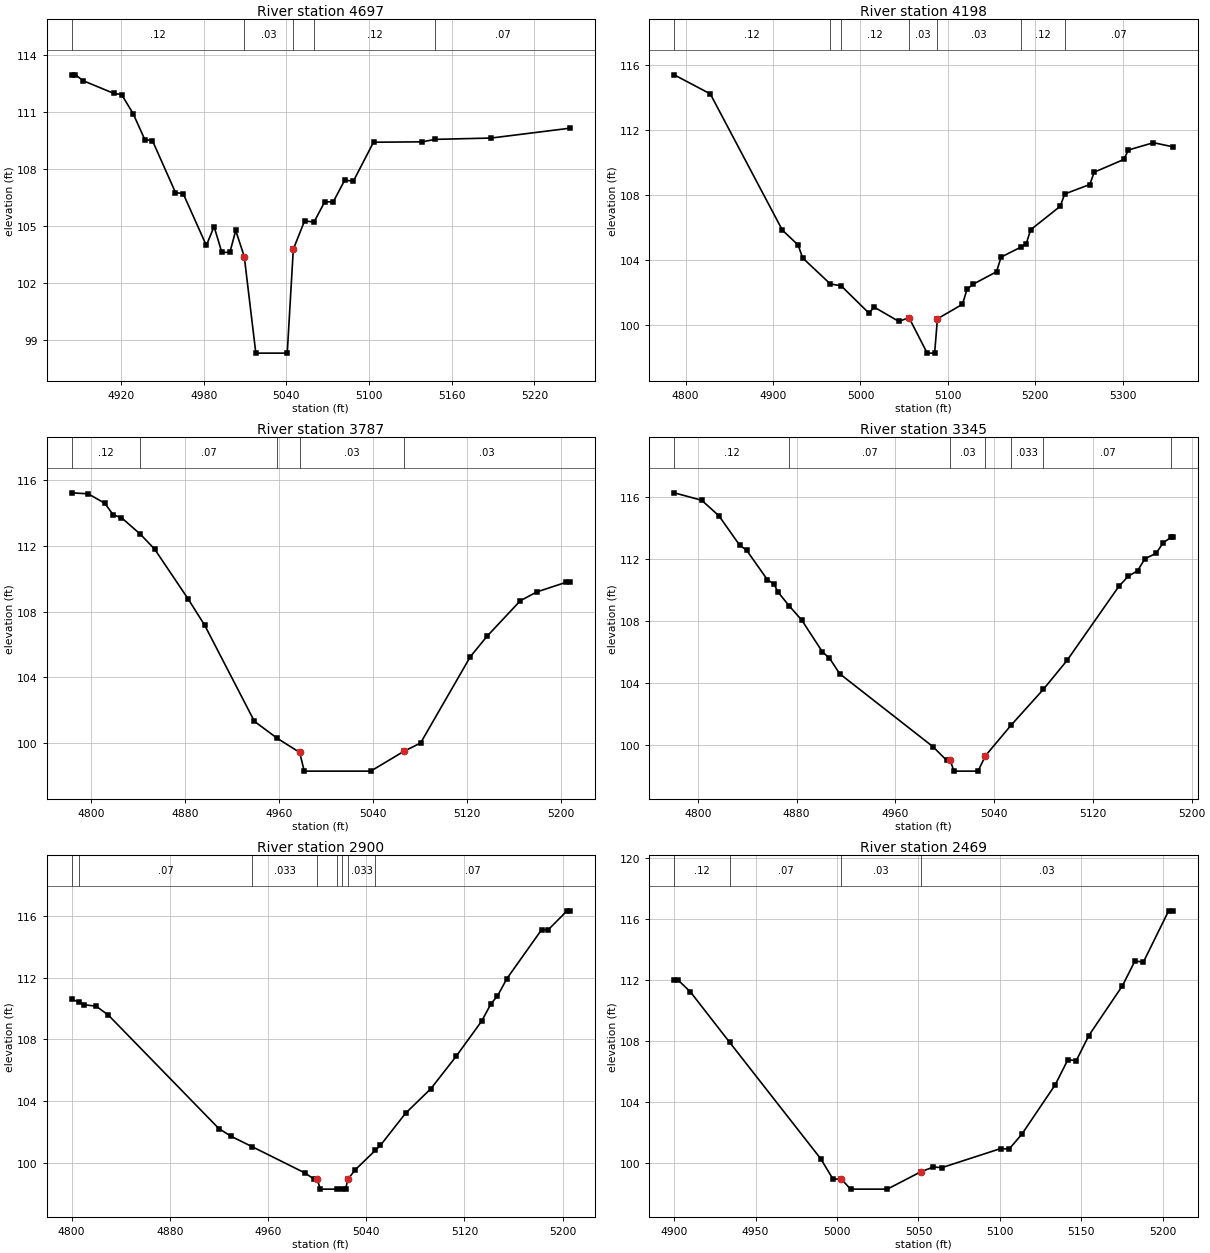
Type RM Length L Ch R = 1 ,4697    ,499,499,499
BEGIN DESCRIPTION:
TRIB 1 TO COLETO CREEK RESERVOIR 9.0
END DESCRIPTION:
XS GIS Cut Line= 3
      2542525.01     13449024.98        2542575.       13448925.
      2542775.01     13448774.99
#Sta/Elev= 30
  4884.1  112.96  4886.9  112.96  4892.5  112.65  4914.8  111.98  4920.4  111.92
  4928.8  110.91  4937.2  109.55  4942.8  109.49  4959.5  106.76  4965.1   106.7
  4981.9  103.97  4987.5  104.97  4993.1  103.61    4999  103.61  5003.2  104.76
  5009.4  103.39  5017.8    98.3  5040.6    98.3    5045 103.773  5053.2  105.27
    5060   105.2  5067.8  106.27    5074  106.27  5082.3  107.41  5088.6  107.36
  5103.2  109.41  5138.6  109.43  5147.9  109.56  5188.6  109.63  5245.9  110.15
#Mann= 5 ,-1 , 0
  4884.1     .12       0  5009.4     .03       0    5045     .03       0
    5060     .12       0  5147.9     .07       0
Bank Sta=5009.4,5045
XS Rating Curve= 0 ,0
Exp/Cntr=0.3,0.1

Type RM Length L Ch R = 1 ,4198    ,411,411,411
BEGIN DESCRIPTION:
TRIB 1 TO COLETO CREEK RESERVOIR 8.0
END DESCRIPTION:
XS GIS Cut Line= 3
      2542724.97     13449325.01        2542925.       13449275.
      2543275.01       13449175.
#Sta/Elev= 30
  4786.9   115.4  4828.2  114.23  4910.6  105.86  4928.7  104.94  4933.8  104.15
  4965.5  102.55  4977.8  102.44    5010  100.74  5015.2  101.14  5043.8  100.25
  5055.5  100.48  5076.3    98.3  5084.8    98.3    5088  100.41  5116.6   101.3
  5121.8  102.21  5128.3  102.52  5155.6   103.3  5160.8   104.2  5183.7  104.82
  5189.4  104.99  5194.6  105.88  5228.4  107.32  5233.6  108.08  5262.2  108.66
  5267.4  109.42  5301.2   110.2  5306.4  110.78    5335  111.23  5357.1  110.98
#Mann= 7 ,-1 , 0
  4786.9     .12       0  4965.5     .07       0  4977.8     .12       0
  5055.5     .03       0    5088     .03       0  5183.7     .12       0
  5233.6     .07       0
Bank Sta=5055.5,5088
XS Rating Curve= 0 ,0
Exp/Cntr=0.3,0.1

Type RM Length L Ch R = 1 ,3787    ,442,442,442
BEGIN DESCRIPTION:
TRIB 1 TO COLETO CREEK RESERVOIR 7.0
END DESCRIPTION:
XS GIS Cut Line= 3
      2543074.99     13449625.01        2543225.       13449475.
      2543375.02     13449324.98
#Sta/Elev= 22
  4783.2  115.24  4797.4  115.18  4811.5   114.6  4818.6   113.9  4825.6  113.73
  4841.6  112.73  4853.9  111.81  4882.2   108.8  4896.4  107.19  4938.8  101.33
  4958.2   100.3  4977.3   99.44  4981.2    98.3  5037.8    98.3  5066.1   99.51
  5080.2  100.01  5122.6  105.27  5136.8  106.51  5165.1  108.67  5179.2  109.21
  5203.9  109.79  5207.5  109.79
#Mann= 5 ,-1 , 0
  4783.2     .12       0  4841.6     .07       0  4958.2     .12       0
  4977.3     .03       0  5066.1     .03       0
Bank Sta=4977.3,5066.1
XS Rating Curve= 0 ,0
Exp/Cntr=0.3,0.1

Type RM Length L Ch R = 1 ,3345    ,445,445,445
BEGIN DESCRIPTION:
TRIB 1 TO COLETO CREEK RESERVOIR 6.0
END DESCRIPTION:
XS GIS Cut Line= 3
      2543325.04     13449874.98        2543525.       13449775.
      2543674.97     13449675.02
#Sta/Elev= 30
  4780.8  116.28  4803.1   115.8  4817.1  114.79  4833.9  112.89  4839.4  112.58
  4856.2  110.68  4861.8  110.37  4864.6   109.9  4873.9  108.98  4884.2  108.05
  4900.9     106  4906.5  105.61  4914.9  104.59  4990.4   99.88  5001.6   98.99
  5004.4   98.99  5007.4    98.3  5026.9    98.3  5032.9   99.29  5053.6  101.26
  5079.8  103.58    5099  105.45  5141.1  110.25  5148.6  110.89  5156.1  111.24
  5162.1  112.02  5171.1  112.37  5177.1  113.07  5183.6  113.42  5184.6  113.42
#Mann= 7 ,-1 , 0
  4780.8     .12       0  4873.9     .07       0  5004.4     .03       0
  5032.9     .03       0  5053.6    .033       0  5079.8     .07       0
  5183.6     .12       0
Bank Sta=5004.4,5032.9
XS Rating Curve= 0 ,0
Exp/Cntr=0.3,0.1

Type RM Length L Ch R = 1 ,2900    ,431,431,431
BEGIN DESCRIPTION:
TRIB 1 TO COLETO CREEK RESERVOIR 5.0
END DESCRIPTION:
XS GIS Cut Line= 3
      2543625.03       13450075.        2543825.       13450075.
      2544024.97     13450025.01
#Sta/Elev= 30
    4800  110.59  4805.8  110.44    4810  110.25    4820  110.15    4830  109.57
    4920  102.22    4930  101.72  4947.3  101.04    4990   99.35  4997.5   98.95
    5000   98.95  5002.6    98.3    5016    98.3    5020    98.3  5023.2    98.3
    5025  98.927  5030.9   99.54  5047.4  100.81  5051.5  101.13  5072.1  103.22
  5092.7  104.81  5113.4  106.92    5134  109.18  5141.7  110.32  5146.9  110.81
  5154.6  111.94  5182.9  115.11  5188.1  115.09  5203.6  116.33  5206.1  116.33
#Mann= 8 ,-1 , 0
    4800     .12       0  4805.8     .07       0  4947.3    .033       0
    5000    .033       0    5016    .033       0    5020    .033       0
    5025    .033       0  5047.4     .07       0
Bank Sta=5000,5025
XS Rating Curve= 0 ,0
Exp/Cntr=0.3,0.1

Type RM Length L Ch R = 1 ,2469    ,500,500,500
BEGIN DESCRIPTION:
TRIB 1 TO COLETO CREEK RESERVOIR 4.0
END DESCRIPTION:
XS GIS Cut Line= 3
      2543925.02       13450425.        2544025.       13450425.
      2544224.97     13450474.99
#Sta/Elev= 24
    4900     112  4902.5     112    4910  111.23  4934.1  107.92    4990  100.29
  4997.5   98.96  5002.6   98.96  5008.3    98.3  5030.9    98.3  5051.5   99.44
  5059.2   99.75  5064.4   99.71  5100.5  100.96  5105.6  100.92  5113.4  101.89
    5134  105.15  5141.7  106.78  5146.9  106.73  5154.6  108.37  5175.2  111.63
  5182.9  113.26  5188.1  113.19  5203.6  116.55  5206.1  116.55
#Mann= 4 ,-1 , 0
    4900     .12       0  4934.1     .07       0  5002.6     .03       0
  5051.5     .03       0
Bank Sta=5002.6,5051.5
XS Rating Curve= 0 ,0
Exp/Cntr=0.3,0.1

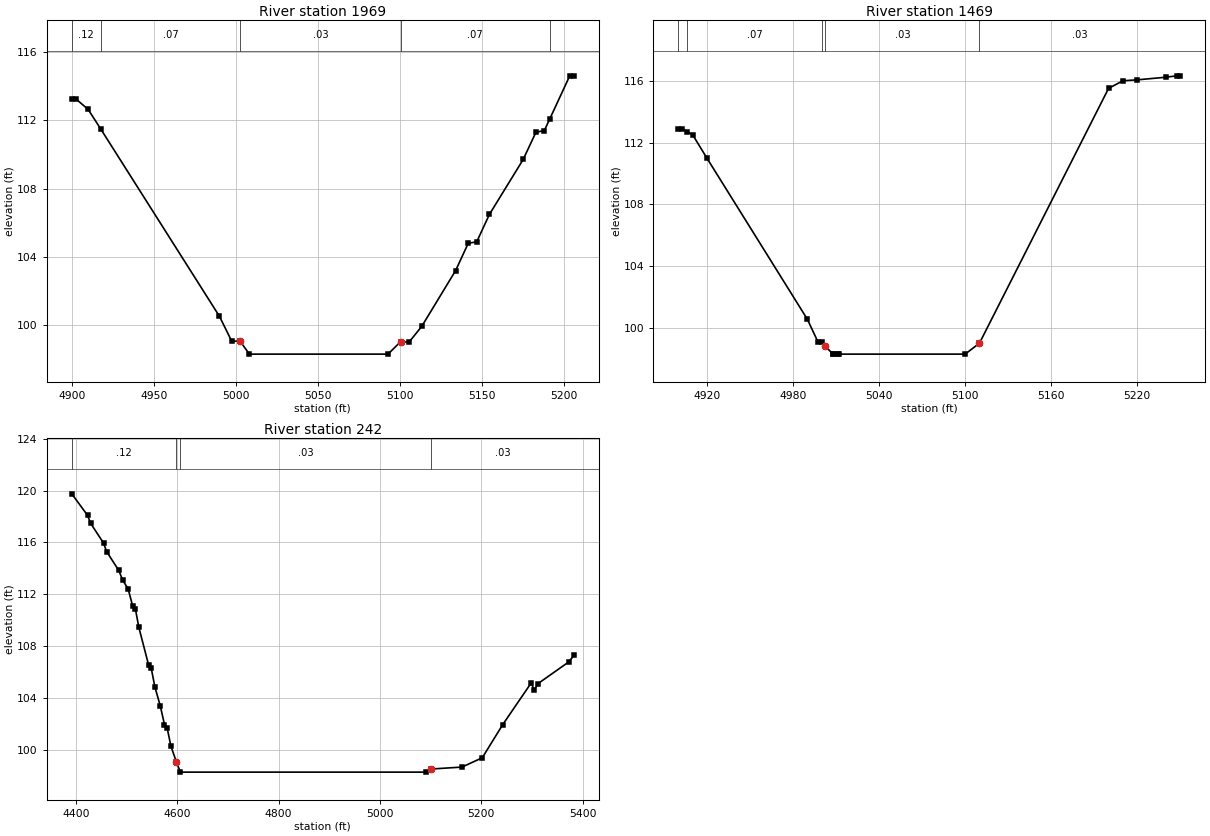
Type RM Length L Ch R = 1 ,1969    ,500,500,500
BEGIN DESCRIPTION:
TRIB 1 TO COLETO CREEK RESERVOIR 3.0
END DESCRIPTION:
XS GIS Cut Line= 3
      2543925.01       13450925.        2544025.       13450925.
      2544224.95     13450974.99
#Sta/Elev= 22
    4900  113.25  4902.5  113.25    4910  112.63  4917.7  111.48    4990  100.52
  4997.5   99.06  5002.6   99.06  5008.3    98.3  5092.8    98.3  5100.5   99.03
  5105.6      99  5113.4   99.93    5134  103.19  5141.7  104.79  5146.9  104.88
  5154.6  106.48  5175.2   109.7    5183   111.3  5188.1  111.39  5191.3  112.05
  5203.6   114.6  5206.1   114.6
#Mann= 5 ,-1 , 0
    4900     .12       0  4917.7     .07       0  5002.6     .03       0
  5100.5     .07       0  5191.3     .07       0
Bank Sta=5002.6,5100.5
XS Rating Curve= 0 ,0
Exp/Cntr=0.3,0.1

Type RM Length L Ch R = 1 ,1469    ,1227,1227,1227
BEGIN DESCRIPTION:
TRIB 1 TO COLETO CREEK RESERVOIR 2.0
END DESCRIPTION:
XS GIS Cut Line= 3
      2543925.01       13451425.        2544025.       13451425.
      2544275.01       13451425.
#Sta/Elev= 21
    4900   112.9  4902.5   112.9  4906.1  112.71    4910  112.51    4920  110.99
    4990  100.56  4997.5   99.07    5000   99.07  5002.5    98.8    5008    98.3
  5008.2    98.3  5011.7    98.3    5012    98.3    5100    98.3    5110   99.01
    5200  115.51    5210     116    5220  116.06    5240  116.23  5247.5  116.32
    5250  116.32
#Mann= 5 ,-1 , 0
    4900    .035       0  4906.1     .07       0    5000     .03       0
  5002.5     .03       0    5110     .03       0
Bank Sta=5002.5,5110
XS Rating Curve= 0 ,0
Exp/Cntr=0.3,0.1

Type RM Length L Ch R = 1 ,242     ,0,0,0
BEGIN DESCRIPTION:
TRIB 1 TO COLETO CREEK RESERVOIR 1.0
END DESCRIPTION:
XS GIS Cut Line= 4
      2543729.73     13452270.22      2544108.21     13452398.69
      2544269.06     13452266.48      2544295.71     13451884.81
#Sta/Elev= 30
  4392.1  119.75  4423.3  118.09  4429.3  117.48  4454.7  115.96    4461  115.29
  4484.7  113.85  4492.7  113.09  4503.3  112.42  4512.2  111.11  4517.5   110.9
  4524.4  109.46  4543.6  106.57  4548.9   106.3  4556.1  104.86  4566.6  103.42
    4575  101.97  4580.3   101.7  4587.7   100.3  4598.3   99.11  4606.4    98.3
  5091.7    98.3  5101.7   98.54    5162   98.69    5202   99.41  5242.1  101.95
  5298.9   105.2  5303.9   104.6  5312.2  105.13  5372.4  106.79  5382.6  107.29
#Mann= 4 ,-1 , 0
  4392.1     .12       0  4598.3     .03       0  4606.4     .03       0
  5101.7     .03       0
Bank Sta=4598.3,5101.7
XS Rating Curve= 0 ,0
Exp/Cntr=0.3,0.1

Chan Stop Cuts=-1
Use User Specified Reach Order=0
Composite Channel Slope=5