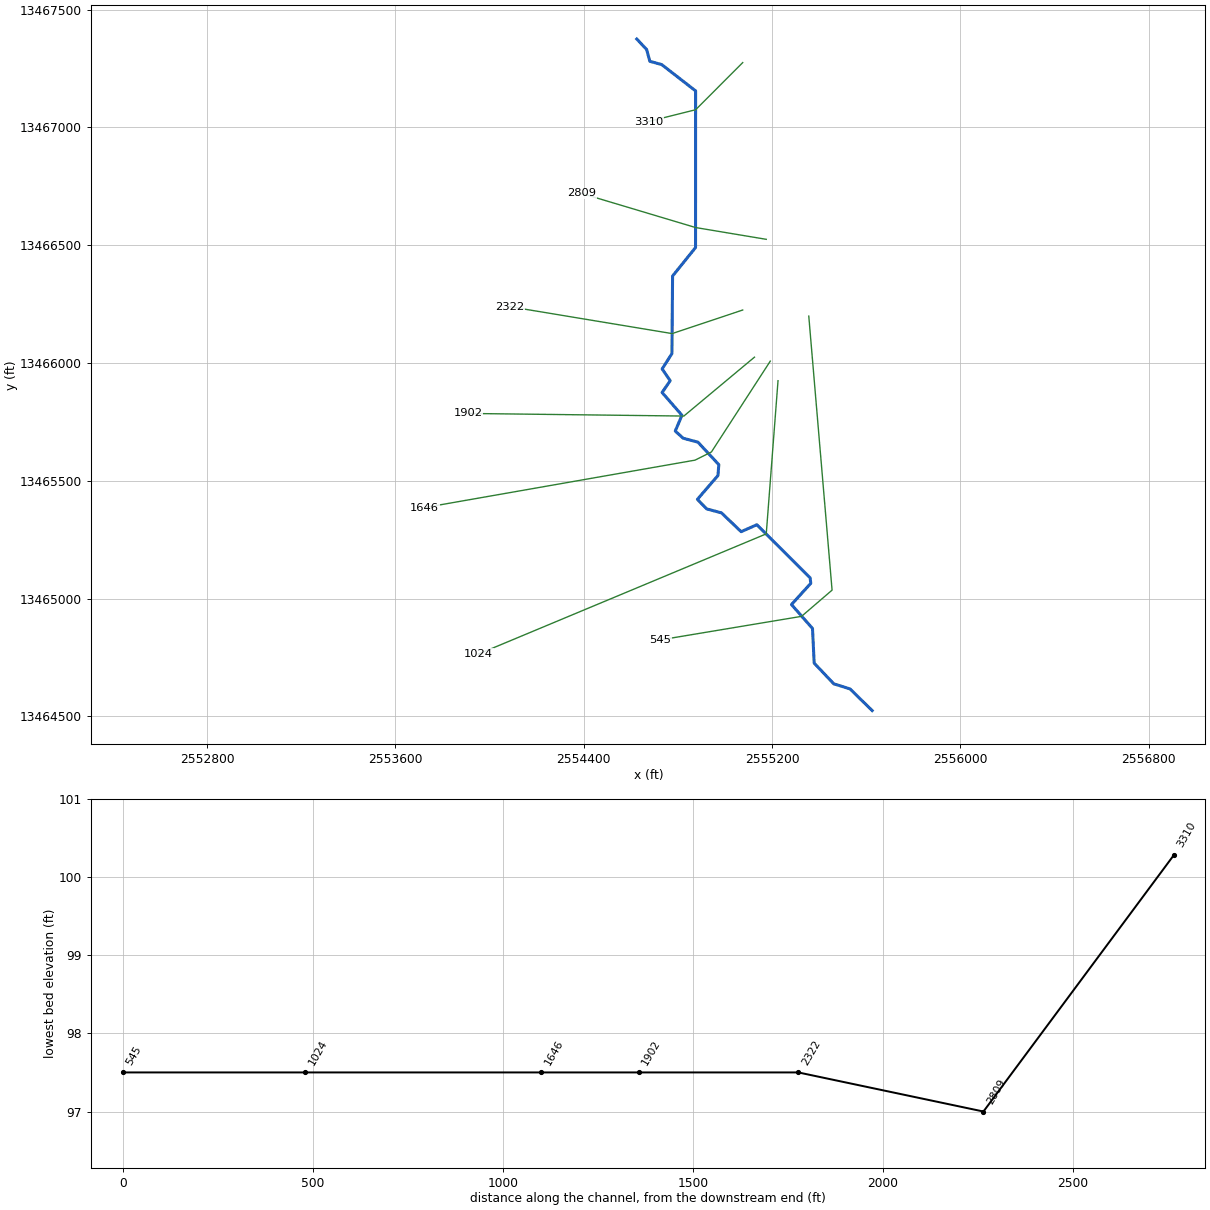
--- TRIB 1 TO COLETO CREEK.prj (project) ---

Proj Title=TRIB 1 TO COLETO CREEK Base Level Engineering
Current Plan=p01
Default Exp/Contr=0.3,0.1
English Units
Geom File=g01
Flow File=f01
Plan File=p01
Y Axis Title=Elevation
X Axis Title(PF)=Main Channel Distance
X Axis Title(XS)=Station
BEGIN DESCRIPTION:
TRIB 1 TO COLETO CREEK
END DESCRIPTION:
DSS Export Rating Curves= 0
DSS Export Rating Curve Sorted= 0
DSS Export Volume Flow Curves= 0
DXF OffsetX= 0
DXF OffsetY= 0
DXF ScaleX= 1
DXF ScaleY= 10

--- TRIB 1 TO COLETO CREEK.p01 (plan) ---

Plan Title=Multiple Run
Short Identifier=Multiple
Geom File=g01
Flow File=f01
Subcritical Flow
K Sum by GR= 0
Std Step Tol= 0.01
Critical Tol= 0.01
Num of Std Step Trials= 20
Max Error Tol= 0.3
Flow Tol Ratio= 0.001
Split Flow NTrial= 30
Split Flow Tol= 0.02
Split Flow Ratio= 0.02
Log Output Level= 0
Friction Slope Method= 1
Unsteady Friction Slope Method= 2
Unsteady Bridges Friction Slope Method= 1
Parabolic Critical Depth
Global Vel Dist=  1 , 1 , 1
Global Log Level= 0
CheckData=True
Encroach Param= -1, 0, 0, 0
BEGIN DESCRIPTION:
Multiple Run
END DESCRIPTION:

--- TRIB 1 TO COLETO CREEK.f01 (steady flow) ---

Flow Title=Multiple
Program Version=4.10
Number of Profiles= 7
Profile Names=10-year,25-year,50-year,1pct_min,100-year,1pct_plu,500-year
River Rch & RM=TRIB 1 TO COLETO,Reach-1         ,3310
     364     555     718     450     898    1791    1386
Boundary for River Rch & Prof#=TRIB 1 TO COLETO,Reach-1         , 1
Up Type= 0
Dn Type= 3
Dn Slope=0.0006
Boundary for River Rch & Prof#=TRIB 1 TO COLETO,Reach-1         , 2
Up Type= 0
Dn Type= 3
Dn Slope=0.0006
Boundary for River Rch & Prof#=TRIB 1 TO COLETO,Reach-1         , 3
Up Type= 0
Dn Type= 3
Dn Slope=0.0006
Boundary for River Rch & Prof#=TRIB 1 TO COLETO,Reach-1         , 4
Up Type= 0
Dn Type= 3
Dn Slope=0.0006
Boundary for River Rch & Prof#=TRIB 1 TO COLETO,Reach-1         , 5
Up Type= 0
Dn Type= 3
Dn Slope=0.0006
Boundary for River Rch & Prof#=TRIB 1 TO COLETO,Reach-1         , 6
Up Type= 0
Dn Type= 3
Dn Slope=0.0006
Boundary for River Rch & Prof#=TRIB 1 TO COLETO,Reach-1         , 7
Up Type= 0
Dn Type= 3
Dn Slope=0.0006
DSS Import GetInterval= 0
DSS Import GetPeak= 0
DSS Import FillOption= 0

--- TRIB 1 TO COLETO CREEK.g01 (geometry) ---

Geom Title=Existing Conditions
Program Version=4.10

River Reach=TRIB 1 TO COLETO,Reach-1
Reach XY= 30
        2554625.       13467375.      2554666.88      13467330.7
      2554680.44     13467280.51      2554730.75     13467266.72
      2554874.96     13467154.81      2554874.61     13466490.16
      2554777.07     13466369.14      2554774.35     13466040.16
      2554732.78      13465974.9      2554766.96     13465924.99
      2554732.56       13465875.      2554816.96     13465778.32
       2554788.5     13465711.32      2554822.17     13465680.86
      2554884.67     13465664.23      2554973.42     13465568.96
      2554969.91     13465522.71      2554882.49     13465421.42
      2554922.14     13465380.85      2554984.64     13465364.17
      2555068.34     13465284.32        2555135.     13465313.76
      2555361.58     13465088.33        2555364.       13465065.
      2555282.11     13464975.01      2555371.43     13464873.53
      2555378.54     13464726.46      2555461.76     13464638.62
      2555531.07     13464616.89        2555625.       13464525.

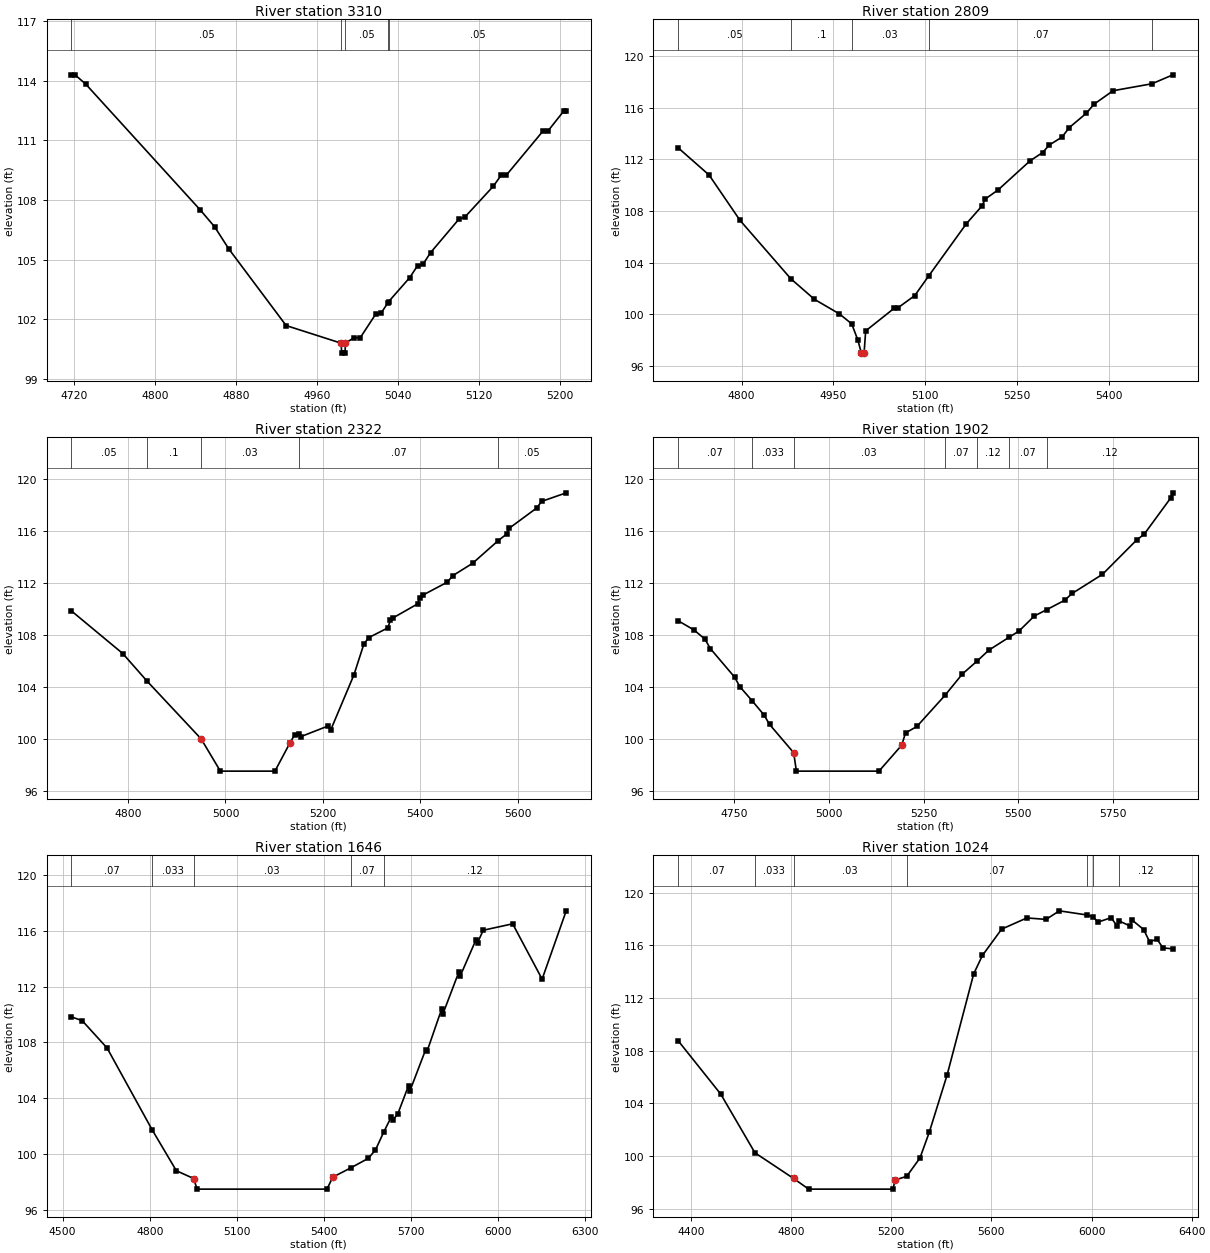
Type RM Length L Ch R = 1 ,3310    ,501,501,501
BEGIN DESCRIPTION:
TRIB 1 TO COLETO CREEK 6.0
END DESCRIPTION:
XS GIS Cut Line= 3
      2555075.02     13467275.02        2554875.       13467075.
      2554675.03     13467025.01
#Sta/Elev= 30
  4717.3  114.31  4720.9  114.31  4731.5  113.84  4844.6   107.5  4858.8  106.65
  4872.9  105.53  4929.5  101.67    4984  100.78  4984.3  100.28  4987.8  100.28
    4988  100.78  4996.6  101.06  5002.8  101.06  5018.2  102.26  5023.4   102.3
  5030.1  102.82  5030.7  102.87  5051.7  104.09  5059.4  104.69  5064.6  104.75
  5072.3  105.35  5100.7  107.06  5105.8  107.12  5134.2  108.69  5141.9  109.24
  5147.1  109.25  5183.1  111.46  5188.3  111.48  5203.8  112.48  5206.3  112.48
#Mann= 5 ,-1 , 0
  4717.3     .05       0    4984     .05       0    4988     .05       0
  5030.1     .07       0  5030.7     .05       0
Bank Sta=4984,4988
XS Rating Curve= 0 ,0
Exp/Cntr=0.3,0.1

Type RM Length L Ch R = 1 ,2809    ,487,487,487
BEGIN DESCRIPTION:
TRIB 1 TO COLETO CREEK 5.0
END DESCRIPTION:
XS GIS Cut Line= 3
      2555174.97     13466525.01        2554875.       13466575.
      2554391.34     13466719.53
#Sta/Elev= 30
    4696  112.89  4746.7  110.78  4797.3  107.27  4880.4  102.75    4919  101.16
  4959.6  100.04  4979.8   99.27    4990      98  4995.6      97  4999.6      97
  5000.1      97  5002.7   98.72  5049.8  100.49    5055  100.49  5082.9  101.45
  5105.7  102.97  5167.1     107  5192.7  108.38  5198.4  108.93  5219.3  109.63
  5271.5  111.88  5292.1  112.52  5302.8   113.1  5323.6  113.71  5335.6  114.45
  5363.5  115.56  5375.8  116.25  5407.1   117.3  5470.8  117.84  5504.9  118.53
#Mann= 5 ,-1 , 0
    4696     .05       0  4880.4      .1       0  4979.8     .03       0
  5105.7     .07       0  5470.8     .05       0
Bank Sta=4995.6,4999.6
XS Rating Curve= 0 ,0
Exp/Cntr=0.3,0.1

Type RM Length L Ch R = 1 ,2322    ,420,420,420
BEGIN DESCRIPTION:
TRIB 1 TO COLETO CREEK 4.0
END DESCRIPTION:
XS GIS Cut Line= 3
      2555074.96     13466224.99        2554775.       13466125.
      2554085.38      13466239.2
#Sta/Elev= 30
  4683.9  109.86  4789.3  106.57  4839.2  104.44    4950   99.99  4989.5    97.5
  5101.5    97.5  5131.9   99.65    5142  100.31  5151.5  100.38  5155.2  100.17
  5211.1  100.99  5216.2   100.7  5263.6  104.93  5283.9   107.3    5294   107.8
  5333.1  108.55  5338.2  109.13  5344.7  109.34  5394.1   110.4  5399.2  110.89
  5405.5  111.09  5455.2  112.08  5466.4  112.58  5506.9  113.53  5559.8  115.29
  5577.2   115.8  5582.3  116.24  5638.2  117.79  5648.8  118.31  5699.1  118.97
#Mann= 5 ,-1 , 0
  4683.9     .05       0  4839.2      .1       0    4950     .03       0
  5151.5     .07       0  5559.8     .05       0
Bank Sta=4950,5131.9
XS Rating Curve= 0 ,0
Exp/Cntr=0.3,0.1

Type RM Length L Ch R = 1 ,1902    ,256,256,256
BEGIN DESCRIPTION:
TRIB 1 TO COLETO CREEK 3.0
END DESCRIPTION:
XS GIS Cut Line= 3
      2555124.99     13466024.99        2554825.       13465775.
      2553909.16     13465786.07
#Sta/Elev= 30
  4601.9  109.09  4644.2  108.37  4672.8  107.67  4687.1  106.94  4750.9  104.75
  4765.2     104  4798.3  102.89    4829  101.82  4843.4   101.1  4907.1   98.92
  4914.3    97.5  5132.4    97.5  5192.4    99.5  5202.4  100.44  5232.4  100.94
  5306.4  103.33  5352.4  104.98  5391.8  105.99  5422.4  106.82  5476.3  107.82
  5502.4   108.3  5542.4  109.45  5574.7  109.93  5622.4  110.66  5642.4  111.19
  5722.4  112.66  5812.5   115.3  5832.5  115.75  5902.5  118.54  5908.3  118.94
#Mann= 7 ,-1 , 0
  4601.9     .07       0  4798.3    .033       0  4907.1     .03       0
  5306.4     .07       0  5391.8     .12       0  5476.3     .07       0
  5574.7     .12       0
Bank Sta=4907.1,5192.4
XS Rating Curve= 0 ,0
Exp/Cntr=0.3,0.1

Type RM Length L Ch R = 1 ,1646    ,622,622,622
BEGIN DESCRIPTION:
Mapping XS 1078803f
END DESCRIPTION:
XS GIS Cut Line= 4
      2555192.13     13466008.11      2554942.11     13465622.65
      2554872.67     13465587.93      2553723.36     13465386.54
#Sta/Elev= 30
  4530.1  109.83  4567.2  109.56    4653   107.6  4808.3  101.74  4891.4   98.82
  4950.8   98.26  4962.9    97.5    5410    97.5  5430.3   98.36  5492.1   99.02
  5552.1    99.7  5577.1   100.3  5605.5  101.58  5631.4  102.66  5636.5  102.45
  5653.6  102.86  5690.9   104.9  5695.9  104.54  5750.1  107.49  5755.4   107.4
  5804.6  110.36  5809.7  110.06  5864.1  113.03  5869.1  112.76  5923.5  115.36
  5928.6  115.13  5948.1  116.03  6049.6  116.49    6151  112.53    6234  117.42
#Mann= 5 ,-1 , 0
  4530.1     .07       0  4808.3    .033       0  4950.8     .03       0
  5492.1     .07       0  5605.5     .12       0
Bank Sta=4950.8,5430.3
XS Rating Curve= 0 ,0
Exp/Cntr=0.3,0.1

Type RM Length L Ch R = 1 ,1024    ,479,479,479
BEGIN DESCRIPTION:
TRIB 1 TO COLETO CREEK 2.0
END DESCRIPTION:
XS GIS Cut Line= 3
        2555225.     13465925.03        2555175.       13465275.
      2553952.56     13464765.03
#Sta/Elev= 30
  4348.5  108.77    4519  104.71  4655.5  100.26  4809.9   98.31  4870.1    97.5
  5206.3    97.5  5216.5    98.2  5261.7   98.47  5314.7   99.86  5351.8  101.81
    5423  106.15  5529.4  113.84  5564.1  115.23    5641  117.23  5741.7  118.08
  5818.6  117.97  5871.6  118.62  5983.7   118.3  6007.7  118.15  6025.4  117.76
  6078.4   118.1  6102.3  117.46  6110.4  117.85  6155.3  117.46  6160.7  117.94
  6208.4   117.2  6232.2  116.26  6261.5  116.47  6285.3  115.81    6325  115.73
#Mann= 7 ,-1 , 0
  4348.5     .07       0  4655.5    .033       0  4809.9     .03       0
  5261.7     .07       0  5983.7     .12       0  6007.7     .07       0
  6110.4     .12       0
Bank Sta=4809.9,5216.5
XS Rating Curve= 0 ,0
Exp/Cntr=0.3,0.1

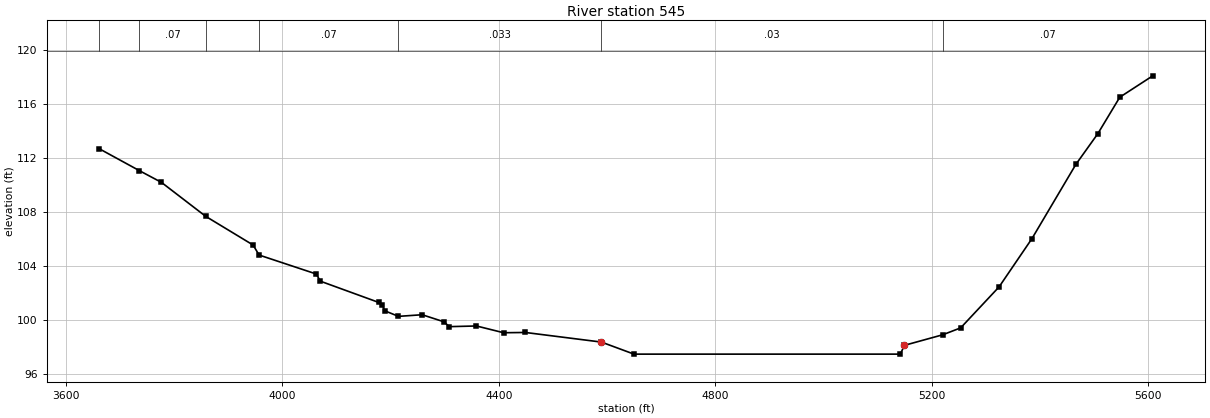
Type RM Length L Ch R = 1 ,545     ,0,0,0
BEGIN DESCRIPTION:
TRIB 1 TO COLETO CREEK 1.0
END DESCRIPTION:
XS GIS Cut Line= 4
      2555355.59     13466199.33      2555454.58     13465036.23
        2555325.       13464925.      2554724.95     13464824.99
#Sta/Elev= 30
  3661.8  112.67    3736  111.05  3776.5  110.19  3858.3  107.68  3945.9  105.56
    3957  104.82  4062.6  103.42  4070.1  102.89    4178  101.32  4184.3  101.16
  4189.3   100.7  4214.5  100.29  4258.3  100.41  4298.4   99.89  4308.5   99.53
  4358.6   99.58  4408.8   99.08    4449    99.1  4589.5   98.39  4649.7    97.5
  5141.8    97.5  5149.4   98.15  5220.2   98.93  5253.3   99.44  5324.3  102.47
  5385.1  106.04  5466.2  111.52  5506.8  113.79  5547.3  116.48  5608.2  118.06
#Mann= 7 ,-1 , 0
  3661.8     .05       0    3736     .07       0  3858.3     .05       0
    3957     .07       0  4214.5    .033       0  4589.5     .03       0
  5220.2     .07       0
Bank Sta=4589.5,5149.4
XS Rating Curve= 0 ,0
Exp/Cntr=0.3,0.1

Chan Stop Cuts=-1
Use User Specified Reach Order=0
Composite Channel Slope=5