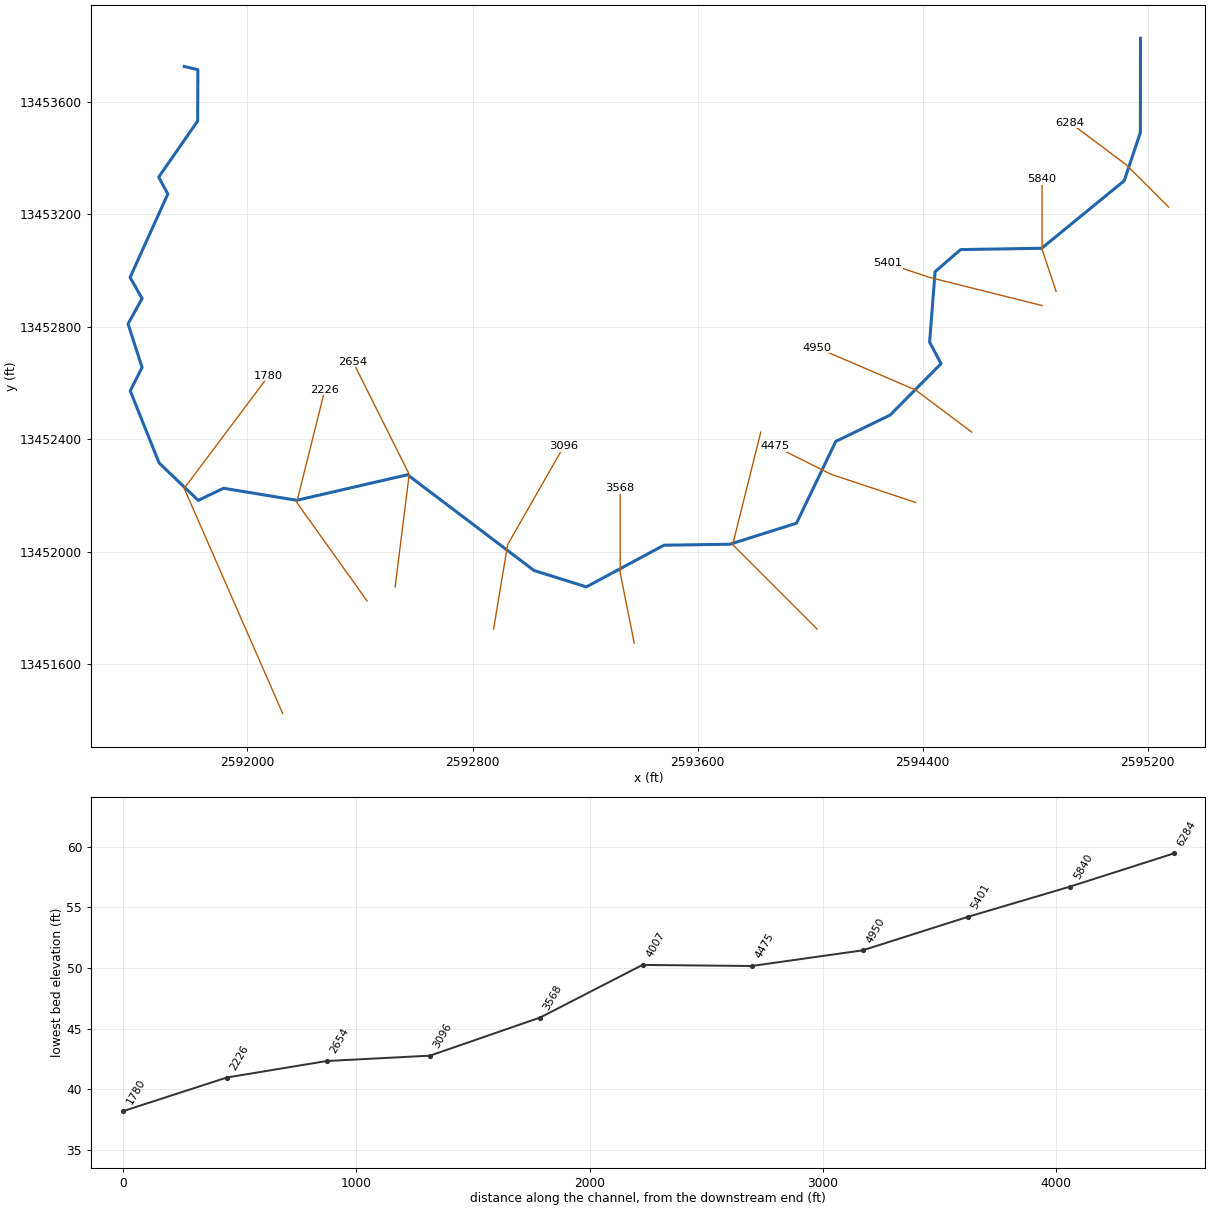
--- TRIB 1 TO COURT BRANCH.prj (project) ---

Proj Title=TRIB 1 TO COURT BRANCH Base Level Engineering
Current Plan=p01
Default Exp/Contr=0.3,0.1
English Units
Geom File=g01
Flow File=f01
Plan File=p01
Y Axis Title=Elevation
X Axis Title(PF)=Main Channel Distance
X Axis Title(XS)=Station
BEGIN DESCRIPTION:
TRIB 1 TO COURT BRANCH
END DESCRIPTION:
DSS Export Rating Curves= 0
DSS Export Rating Curve Sorted= 0
DSS Export Volume Flow Curves= 0
DXF OffsetX= 0
DXF OffsetY= 0
DXF ScaleX= 1
DXF ScaleY= 10

--- TRIB 1 TO COURT BRANCH.p01 (plan) ---

Plan Title=Multiple Run
Short Identifier=Multiple
Geom File=g01
Flow File=f01
Subcritical Flow
K Sum by GR= 0
Std Step Tol= 0.01
Critical Tol= 0.01
Num of Std Step Trials= 20
Max Error Tol= 0.3
Flow Tol Ratio= 0.001
Split Flow NTrial= 30
Split Flow Tol= 0.02
Split Flow Ratio= 0.02
Log Output Level= 0
Friction Slope Method= 1
Unsteady Friction Slope Method= 2
Unsteady Bridges Friction Slope Method= 1
Parabolic Critical Depth
Global Vel Dist=  1 , 1 , 1
Global Log Level= 0
CheckData=True
Encroach Param= -1, 0, 0, 0
BEGIN DESCRIPTION:
Multiple Run
END DESCRIPTION:

--- TRIB 1 TO COURT BRANCH.f01 (steady flow) ---

Flow Title=Multiple
Number of Profiles=7
Profile Names=10-year,25-year,50-year,1pct_min,100-year,1pct_plu,500-year
River Rch & RM= TRIB 1 TO COURT ,Reach-1,6284
     566     872    1136     715    1427    2847    2223
River Rch & RM= TRIB 1 TO COURT ,Reach-1,5840
     697    1088    1429     907    1809    3610    2866
River Rch & RM= TRIB 1 TO COURT ,Reach-1,4007
     803    1265    1672    1068    2130    4250    3414
Boundary for River Rch & Prof#=TRIB 1 TO COURT ,Reach-1,1
Up Type=0
Dn Type=3
Dn Slope=0.005
Boundary for River Rch & Prof#=TRIB 1 TO COURT ,Reach-1,2
Up Type=0
Dn Type=3
Dn Slope=0.005
Boundary for River Rch & Prof#=TRIB 1 TO COURT ,Reach-1,3
Up Type=0
Dn Type=3
Dn Slope=0.005
Boundary for River Rch & Prof#=TRIB 1 TO COURT ,Reach-1,4
Up Type=0
Dn Type=3
Dn Slope=0.005
Boundary for River Rch & Prof#=TRIB 1 TO COURT ,Reach-1,5
Up Type=0
Dn Type=3
Dn Slope=0.005
Boundary for River Rch & Prof#=TRIB 1 TO COURT ,Reach-1,6
Up Type=0
Dn Type=3
Dn Slope=0.005
Boundary for River Rch & Prof#=TRIB 1 TO COURT ,Reach-1,7
Up Type=0
Dn Type=3
Dn Slope=0.005

--- TRIB 1 TO COURT BRANCH.g01 (geometry) ---

Geom Title=Existing Conditions
Program Version=4.10

River Reach=TRIB 1 TO COURT ,Reach-1
Reach XY= 30
        2595175.       13453825.      2595174.48     13453490.22
      2595117.15     13453318.81      2594823.54     13453078.54
      2594535.43     13453073.96      2594444.59     13452995.21
      2594425.19     13452744.98      2594465.87     13452668.26
      2594284.79     13452485.52      2594091.44     13452391.79
      2593951.93     13452101.14       2593714.5     13452026.22
      2593480.86     13452022.93      2593204.82     13451874.72
      2593018.83     13451932.86      2592568.96     13452273.37
        2592175.     13452182.56      2591914.79      13452225.4
       2591824.9     13452182.32      2591685.76     13452315.31
       2591583.1     13452571.71      2591625.21     13452654.79
       2591575.4     13452809.73      2591625.31     13452900.04
      2591582.59     13452974.99      2591716.75     13453271.77
      2591684.31     13453331.66      2591822.77     13453530.93
      2591823.57     13453713.57        2591775.       13453725.

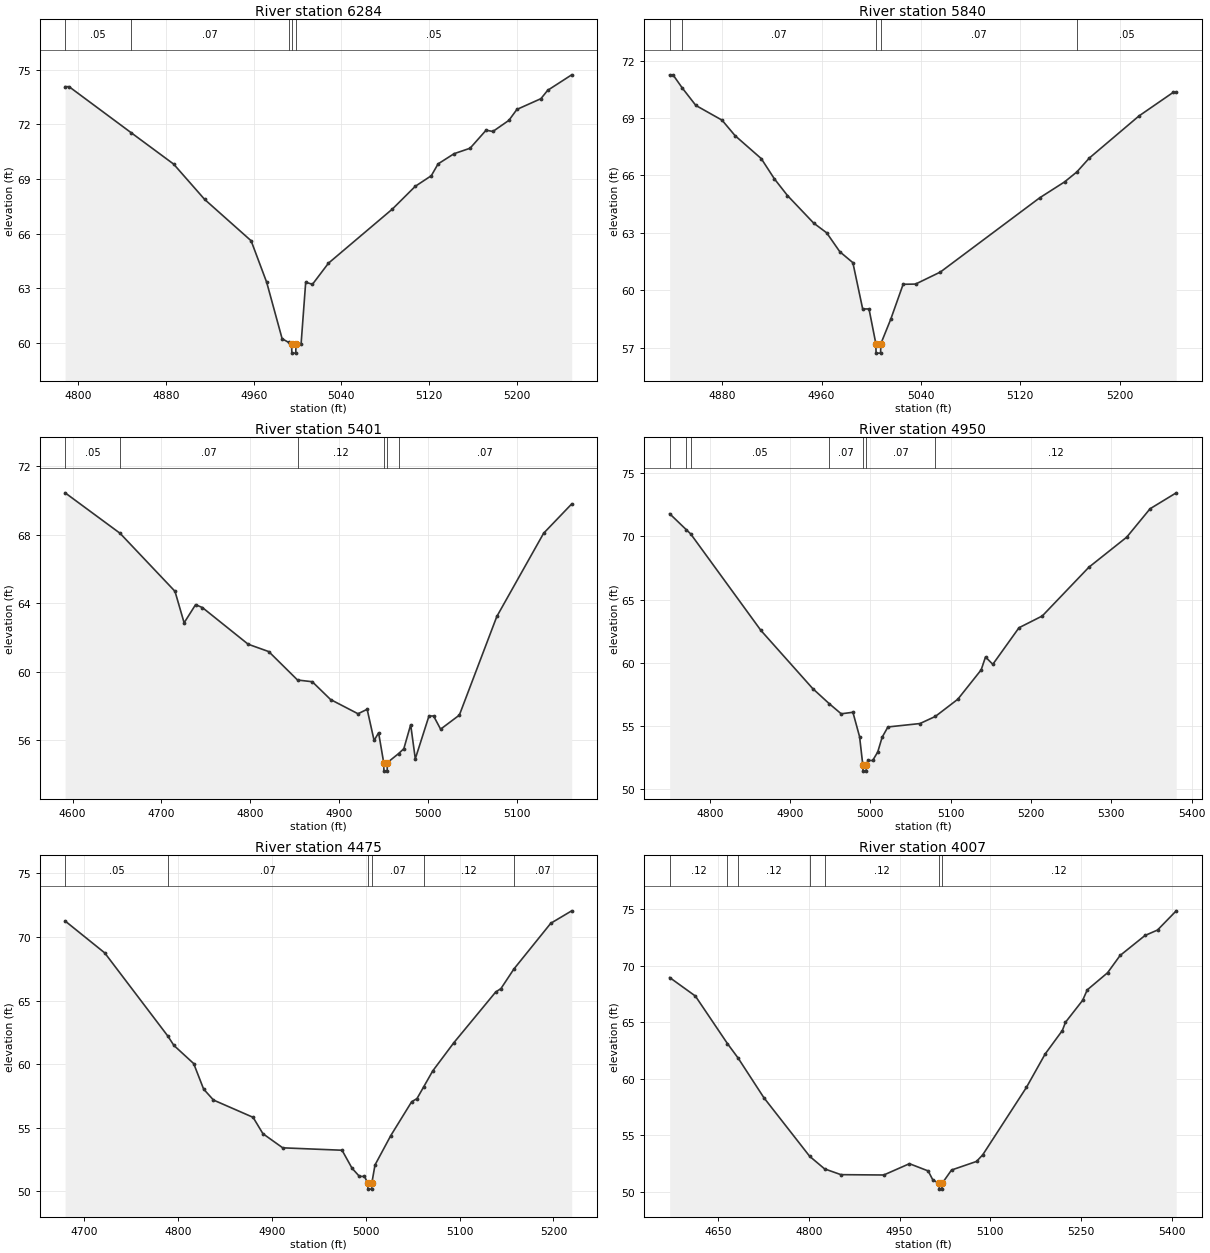
Type RM Length L Ch R = 1 ,6284    ,444,444,444
BEGIN DESCRIPTION:
TRIB 1 TO COURT BRANCH 11.0
END DESCRIPTION:
XS GIS Cut Line= 3
      2595275.03     13453224.97        2595125.       13453375.
      2594924.98     13453525.01
#Sta/Elev= 30
  4787.9   74.07  4791.5   74.07  4848.2   71.54  4886.9   69.82  4915.2   67.88
  4957.6   65.61  4971.8   63.33  4985.9   60.23  4991.8   60.03  4994.5   59.94
  4994.8   59.44  4998.3   59.44  4998.6   59.94  5003.2   59.94  5007.4   63.33
  5013.6   63.22  5028.2   64.38  5086.5   67.35  5107.4    68.6    5122   69.18
  5128.2   69.83  5142.8   70.39  5157.4   70.69    5172   71.68  5178.2   71.61
  5192.8   72.22  5200.1   72.82    5222   73.41  5228.2   73.87  5250.1   74.72
#Mann= 5 ,-1 , 0
  4787.9     .05       0  4848.2     .07       0  4991.8     .05       0
  4994.5     .05       0  4998.6     .05       0
Bank Sta=4994.5,4998.6
XS Rating Curve= 0 ,0
Exp/Cntr=0.3,0.1

Type RM Length L Ch R = 1 ,5840    ,439,439,439
BEGIN DESCRIPTION:
TRIB 1 TO COURT BRANCH 10.0
END DESCRIPTION:
XS GIS Cut Line= 3
      2594875.01     13452924.97        2594825.       13453075.
        2594825.     13453324.96
#Sta/Elev= 30
  4837.6   71.26  4840.3   71.26  4847.9   70.56  4858.7   69.66  4879.8   68.89
  4890.3   68.08  4911.4   66.88    4922   65.82  4932.5   64.95  4953.6   63.51
  4964.1      63  4974.7   62.01  4985.2   61.44  4993.1   59.02  4998.2   59.02
  5003.7   57.21  5003.9   56.71  5007.5   56.71  5007.8   57.21  5015.7   58.48
  5025.7   60.31  5035.7   60.32  5055.7   60.95  5135.7   64.83  5155.7   65.66
  5165.6   66.18  5175.7   66.91  5215.7   69.11  5243.2   70.34  5245.7   70.34
#Mann= 5 ,-1 , 0
  4837.6     .05       0  4847.9     .07       0  5003.7     .05       0
  5007.8     .07       0  5165.6     .05       0
Bank Sta=5003.7,5007.8
XS Rating Curve= 0 ,0
Exp/Cntr=0.3,0.1

Type RM Length L Ch R = 1 ,5401    ,451,451,451
BEGIN DESCRIPTION:
TRIB 1 TO COURT BRANCH 9.0
END DESCRIPTION:
XS GIS Cut Line= 3
      2594824.99       13452875.        2594425.       13452975.
      2594275.01       13453025.
#Sta/Elev= 30
  4591.6   70.46  4653.4    68.1  4715.3   64.71  4725.6   62.87  4738.5   63.93
  4746.2   63.76  4797.7   61.62  4820.9   61.19  4853.3   59.53  4869.9   59.43
  4890.5   58.39  4921.4   57.56  4931.7   57.82  4939.5      56  4944.6   56.45
  4950.3   54.71  4950.6   54.21  4954.2   54.21  4954.5   54.71    4967   55.23
    4973   55.52  4980.7   56.92  4985.9   54.93  5001.3   57.43  5006.5   57.43
  5014.4   56.66  5035.5   57.48  5077.7   63.24  5130.4    68.1    5162   69.81
#Mann= 6 ,-1 , 0
  4591.6     .05       0  4653.4     .07       0  4853.3     .12       0
  4950.3     .05       0  4954.5     .12       0    4967     .07       0
Bank Sta=4950.3,4954.5
XS Rating Curve= 0 ,0
Exp/Cntr=0.3,0.1

Type RM Length L Ch R = 1 ,4950    ,475,475,475
BEGIN DESCRIPTION:
TRIB 1 TO COURT BRANCH 8.0
END DESCRIPTION:
XS GIS Cut Line= 3
      2594575.04     13452424.97        2594375.       13452575.
      2594025.03     13452724.99
#Sta/Elev= 30
    4750   71.79  4770.5   70.54  4776.1    70.2  4863.6   62.57  4928.2   57.97
  4948.7   56.78  4963.6   55.98  4978.2    56.1  4986.5   54.17  4990.5   51.95
  4990.8   51.45  4994.7   51.45    4995   51.95  4996.9   52.29  5002.8   52.29
  5009.1   52.96  5014.6   54.13  5021.8   54.94  5061.7   55.21  5080.8   55.77
  5108.8   57.13  5137.9   59.45  5143.3   60.47  5152.4   59.89    5185   62.78
    5214   63.71    5272   67.56  5319.2   69.94  5348.2   72.18  5380.8   73.44
#Mann= 7 ,-1 , 0
    4750     .05       0  4770.5     .07       0  4776.1     .05       0
  4948.7     .07       0  4990.5     .05       0    4995     .07       0
  5080.8     .12       0
Bank Sta=4990.5,4995
XS Rating Curve= 0 ,0
Exp/Cntr=0.3,0.1

Type RM Length L Ch R = 1 ,4475    ,468,468,468
BEGIN DESCRIPTION:
TRIB 1 TO COURT BRANCH 7.0
END DESCRIPTION:
XS GIS Cut Line= 3
        2594375.       13452175.        2594075.       13452275.
      2593875.03     13452374.98
#Sta/Elev= 30
  4679.6   71.26  4721.8   68.75  4789.1    62.2  4795.5   61.47  4816.6   60.04
  4827.2   58.03  4837.7   57.17  4879.9   55.81  4890.4   54.52  4911.5   53.41
  4974.7   53.22  4985.3   51.81  4993.2   51.16  4998.6   51.16  5001.9   50.66
  5002.3   50.16  5006.2   50.16  5006.5   50.66  5009.8   52.06  5026.6   54.37
  5048.9   57.04  5054.5   57.28  5061.7   58.21  5071.3   59.46  5093.7   61.67
  5138.4   65.67    5144   65.94  5157.8   67.48  5197.1   71.08  5219.4   72.06
#Mann= 6 ,-1 , 0
  4679.6     .05       0  4789.1     .07       0  5001.9     .05       0
  5006.5     .07       0  5061.7     .12       0  5157.8     .07       0
Bank Sta=5001.9,5006.5
XS Rating Curve= 0 ,0
Exp/Cntr=0.3,0.1

Type RM Length L Ch R = 1 ,4007    ,439,439,439
BEGIN DESCRIPTION:
TRIB 1 TO COURT BRANCH 6.0
END DESCRIPTION:
XS GIS Cut Line= 3
      2594025.03     13451724.97        2593725.       13452025.
      2593824.99     13452424.98
#Sta/Elev= 30
  4570.3   68.97  4612.8   67.33  4665.8   63.12  4683.3   61.85  4725.9   58.34
  4801.6   53.15  4826.2   52.04  4853.2   51.53  4923.9    51.5  4966.3    52.5
  4997.2   51.86  5004.9   51.07  5015.5   50.75  5015.8   50.25  5019.8   50.25
  5020.2   50.75  5035.8   51.94  5077.1    52.7  5087.4   53.29  5159.5   59.25
  5190.5   62.21  5218.8   64.28    5224   65.01  5252.3   66.95    5260   67.88
  5293.5   69.39  5314.2   70.92  5355.4   72.69    5376   73.17  5406.9   74.87
#Mann= 7 ,-1 , 0
  4570.3     .12       0  4665.8     .07       0  4683.3     .12       0
  4801.6     .07       0  4826.2     .12       0  5015.5     .05       0
  5020.2     .12       0
Bank Sta=5015.5,5020.2
XS Rating Curve= 0 ,0
Exp/Cntr=0.3,0.1

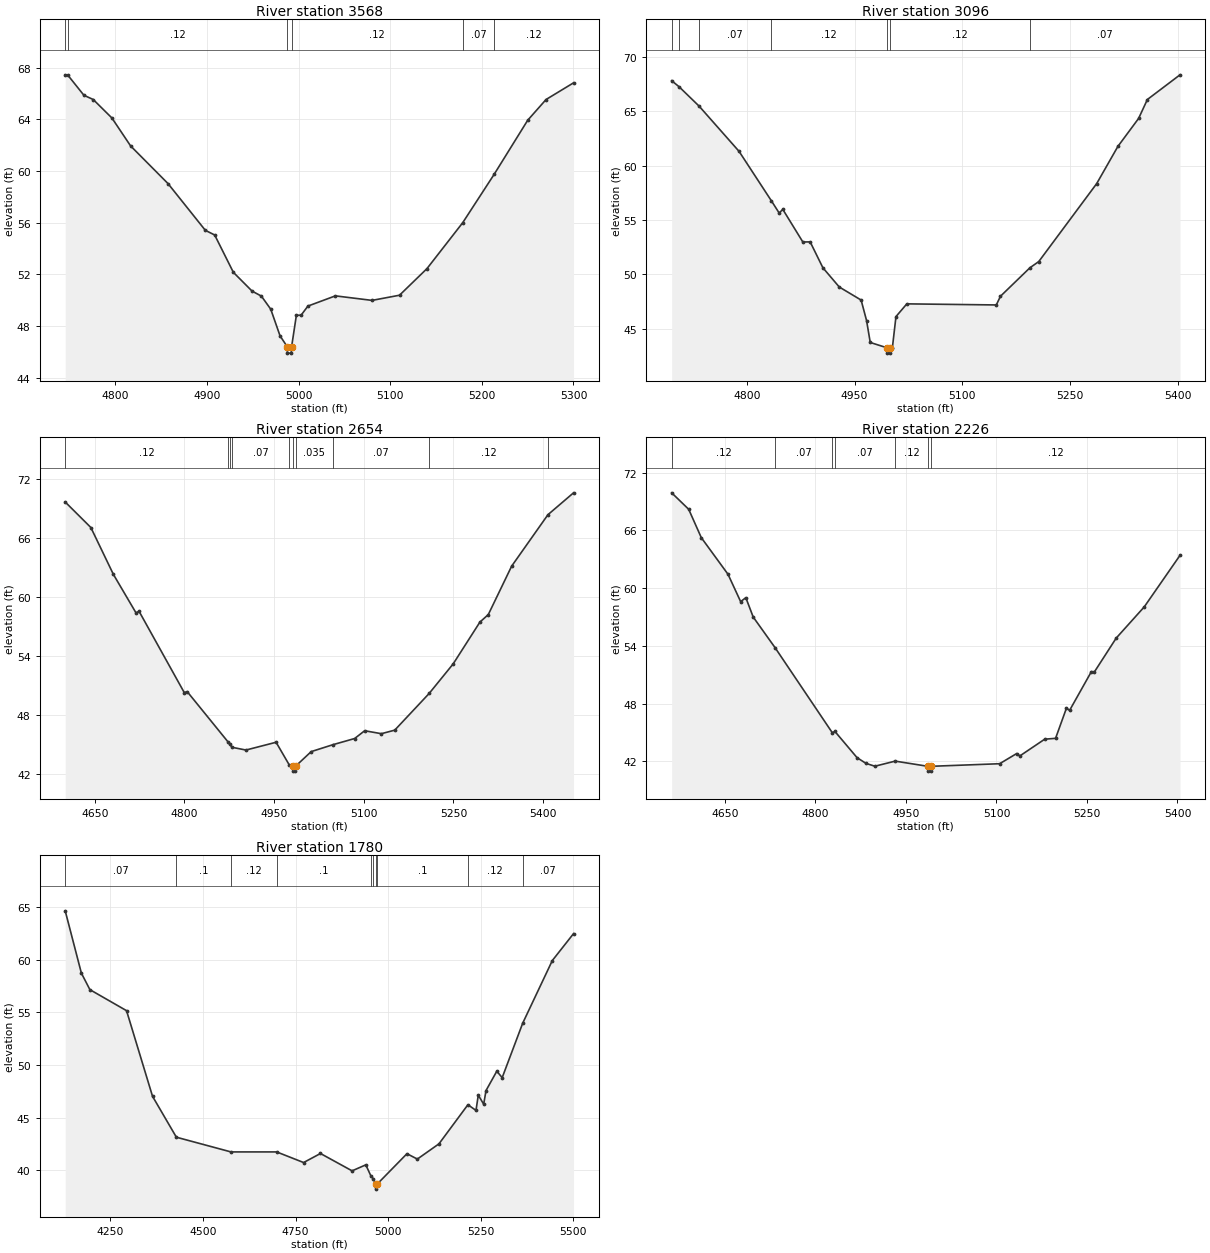
Type RM Length L Ch R = 1 ,3568    ,472,472,472
BEGIN DESCRIPTION:
TRIB 1 TO COURT BRANCH 5.0
END DESCRIPTION:
XS GIS Cut Line= 3
        2593375.       13451675.        2593325.       13451925.
        2593325.     13452225.04
#Sta/Elev= 30
  4745.1   67.44  4747.9   67.42  4765.5   65.86  4775.7   65.53  4796.1    64.1
  4816.5   61.94  4857.3   59.03  4898.1   55.41  4908.3   55.05  4928.7   52.16
  4949.1   50.71  4959.3   50.32  4969.5   49.31  4979.7   47.24  4987.5   46.41
  4987.8   45.91  4991.9   45.91  4992.3   46.41  4997.5   48.84  5002.6   48.84
  5010.1   49.55  5040.1   50.34  5080.1   49.99  5110.1   50.39  5140.1   52.45
  5179.1      56  5213.5   59.75  5250.1   63.93  5270.1   65.53  5300.1   66.82
#Mann= 6 ,-1 , 0
  4745.1     .07       0  4747.9     .12       0  4987.5     .05       0
  4992.3     .12       0  5179.1     .07       0  5213.5     .12       0
Bank Sta=4987.5,4992.3
XS Rating Curve= 0 ,0
Exp/Cntr=0.3,0.1

Type RM Length L Ch R = 1 ,3096    ,442,442,442
BEGIN DESCRIPTION:
TRIB 1 TO COURT BRANCH 4.0
END DESCRIPTION:
XS GIS Cut Line= 3
      2592874.99     13451724.96        2592925.       13452025.
        2593125.     13452375.01
#Sta/Elev= 30
  4695.6   67.82  4705.8   67.27  4733.8   65.48  4789.4   61.32  4834.3   56.78
  4845.2   55.65  4850.2   55.99  4878.1   52.99  4888.3      53    4906   50.62
  4928.8   48.85  4959.2   47.65  4966.8   45.76  4971.9   43.75  4994.8   43.27
  4995.2   42.77  4999.3   42.77  4999.6   43.27  5002.7   43.27  5007.7   46.13
  5022.8    47.3  5147.3    47.2  5153.1      48  5194.1   50.62  5206.4   51.19
    5287   58.36  5316.5   61.78  5345.3   64.35  5357.5   66.09  5402.9   68.36
#Mann= 7 ,-1 , 0
  4695.6     .07       0  4705.8     .12       0  4733.8     .07       0
  4834.3     .12       0  4994.8     .05       0  4999.6     .12       0
  5194.1     .07       0
Bank Sta=4994.8,4999.6
XS Rating Curve= 0 ,0
Exp/Cntr=0.3,0.1

Type RM Length L Ch R = 1 ,2654    ,428,428,428
BEGIN DESCRIPTION:
TRIB 1 TO COURT BRANCH 3.0
END DESCRIPTION:
XS GIS Cut Line= 3
      2592524.99     13451874.96        2592575.       13452275.
      2592374.99     13452675.03
#Sta/Elev= 30
  4600.6   69.65  4643.5   67.06  4681.3   62.29  4719.1   58.39  4724.1   58.56
  4799.7   50.31  4804.7    50.4  4873.6   45.25    4876   45.05  4879.6   44.75
    4903   44.47  4953.4   45.26  4975.7   42.93  4981.2   42.83  4981.5   42.33
  4985.6   42.33    4986   42.83  5012.1   44.31  5048.3   45.01  5084.8   45.64
  5101.6   46.43  5129.5   46.13  5151.9   46.49  5209.4   50.21  5249.7   53.22
  5294.4   57.46  5308.4   58.22  5347.5   63.14  5408.2   68.36    5451   70.58
#Mann= 10 ,-1 , 0
  4600.6     .12       0  4873.6     .07       0    4876    .035       0
  4879.6     .07       0  4975.7    .035       0  4981.2    .035       0
    4986    .035       0  5048.3     .07       0  5209.4     .12       0
  5408.2    .035       0
Bank Sta=4981.2,4986
XS Rating Curve= 0 ,0
Exp/Cntr=0.3,0.1

Type RM Length L Ch R = 1 ,2226    ,446,446,446
BEGIN DESCRIPTION:
TRIB 1 TO COURT BRANCH 2.0
END DESCRIPTION:
XS GIS Cut Line= 3
      2592424.98     13451825.02        2592175.       13452175.
        2592275.       13452575.
#Sta/Elev= 30
  4561.8    69.9    4590   68.19  4610.9   65.24  4655.2   61.43  4676.1   58.59
  4684.7      59  4696.9   56.99  4733.3   53.79  4827.9   44.97  4832.4   45.09
    4869   42.37  4883.7   41.78  4898.5   41.48  4932.2   42.01  4986.4   41.47
  4986.7   40.97  4990.9   40.97  4991.3   41.47  5105.3   41.74  5133.6    42.8
  5138.8   42.55    5180   44.29    5198   44.38  5216.1   47.53  5221.2   47.28
  5257.3   51.31  5262.5    51.3  5298.5    54.8  5344.9   58.04  5404.2    63.4
#Mann= 7 ,-1 , 0
  4561.8     .12       0  4733.3     .07       0  4827.9    .035       0
  4832.4     .07       0  4932.2     .12       0  4986.4     .05       0
  4991.3     .12       0
Bank Sta=4986.4,4991.3
XS Rating Curve= 0 ,0
Exp/Cntr=0.3,0.1

Type RM Length L Ch R = 1 ,1780    ,0,0,0
BEGIN DESCRIPTION:
TRIB 1 TO COURT BRANCH 1.0
END DESCRIPTION:
XS GIS Cut Line= 3
        2592125.     13451424.99        2591775.       13452225.
      2592074.99     13452624.98
#Sta/Elev= 30
  4127.8   64.67  4171.5   58.74  4194.5   57.17  4293.5   55.17  4363.7   47.02
  4428.1   43.13  4575.6   41.73  4699.1   41.73  4771.8   40.72  4817.4   41.58
  4902.8   39.93  4939.8    40.5  4953.7   39.44    4960   39.18  4966.2   38.69
  4966.6   38.19  4971.2   38.69    5051   41.56  5079.1   41.05  5137.5    42.5
  5215.7   46.22  5237.5   45.68  5243.7   47.13  5258.3   46.27  5264.6   47.57
  5293.7   49.41  5308.3    48.8  5363.7   53.98  5443.7   59.94    5501    62.5
#Mann= 10 ,-1 , 0
  4127.8     .07       0  4428.1      .1       0  4575.6     .12       0
  4699.1      .1       0  4953.7     .12       0    4960      .1       0
  4966.2     .05       0  4971.2      .1       0  5215.7     .12       0
  5363.7     .07       0
Bank Sta=4966.2,4971.2
XS Rating Curve= 0 ,0
Exp/Cntr=0.3,0.1

Chan Stop Cuts=-1
Use User Specified Reach Order=0
Composite Channel Slope=5