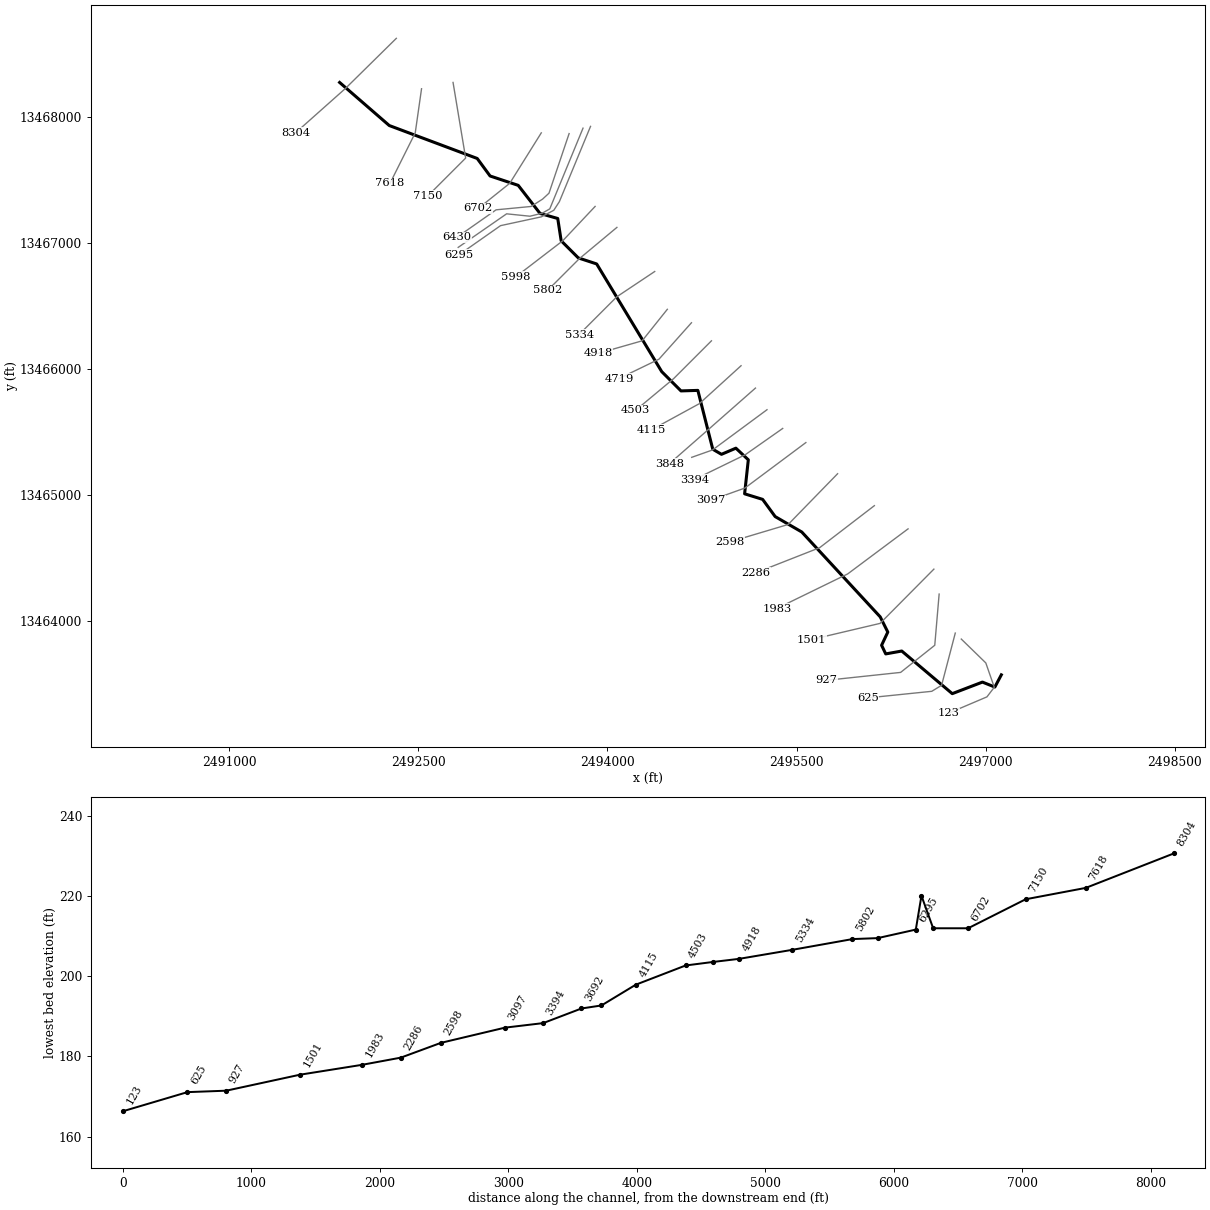
--- TRIB 1 TO FARMER CREEK.prj (project) ---

Proj Title=TRIB 1 TO FARMER CREEK Base Level Engineering
Current Plan=p01
Default Exp/Contr=0.3,0.1
English Units
Geom File=g01
Flow File=f01
Plan File=p01
Y Axis Title=Elevation
X Axis Title(PF)=Main Channel Distance
X Axis Title(XS)=Station
BEGIN DESCRIPTION:
TRIB 1 TO FARMER CREEK
END DESCRIPTION:
DSS Export Rating Curves= 0
DSS Export Rating Curve Sorted= 0
DSS Export Volume Flow Curves= 0
DXF OffsetX= 0
DXF OffsetY= 0
DXF ScaleX= 1
DXF ScaleY= 10

--- TRIB 1 TO FARMER CREEK.p01 (plan) ---

Plan Title=Multiple Run
Short Identifier=Multiple
Geom File=g01
Flow File=f01
Subcritical Flow
K Sum by GR= 0
Std Step Tol= 0.01
Critical Tol= 0.01
Num of Std Step Trials= 20
Max Error Tol= 0.3
Flow Tol Ratio= 0.001
Split Flow NTrial= 30
Split Flow Tol= 0.02
Split Flow Ratio= 0.02
Log Output Level= 0
Friction Slope Method= 1
Unsteady Friction Slope Method= 2
Unsteady Bridges Friction Slope Method= 1
Parabolic Critical Depth
Global Vel Dist=  1 , 1 , 1
Global Log Level= 0
CheckData=True
Encroach Param= -1, 0, 0, 0
BEGIN DESCRIPTION:
Multiple Run
END DESCRIPTION:

--- TRIB 1 TO FARMER CREEK.f01 (steady flow) ---

Flow Title=Multiple
Program Version=4.10
Number of Profiles= 7
Profile Names=10-year,25-year,50-year,1pct_min,100-year,1pct_plu,500-year
River Rch & RM=TRIB 1 TO FARMER,Reach-1         ,8304
     365     567     741     471     940    1875    1490
River Rch & RM=TRIB 1 TO FARMER,Reach-1         ,4503
     551     879    1172     757    1510    3013    2478
Boundary for River Rch & Prof#=TRIB 1 TO FARMER,Reach-1         , 1
Up Type= 0
Dn Type= 3
Dn Slope=0.0066
Boundary for River Rch & Prof#=TRIB 1 TO FARMER,Reach-1         , 2
Up Type= 0
Dn Type= 3
Dn Slope=0.0066
Boundary for River Rch & Prof#=TRIB 1 TO FARMER,Reach-1         , 3
Up Type= 0
Dn Type= 3
Dn Slope=0.0066
Boundary for River Rch & Prof#=TRIB 1 TO FARMER,Reach-1         , 4
Up Type= 0
Dn Type= 3
Dn Slope=0.0066
Boundary for River Rch & Prof#=TRIB 1 TO FARMER,Reach-1         , 5
Up Type= 0
Dn Type= 3
Dn Slope=0.0066
Boundary for River Rch & Prof#=TRIB 1 TO FARMER,Reach-1         , 6
Up Type= 0
Dn Type= 3
Dn Slope=0.0066
Boundary for River Rch & Prof#=TRIB 1 TO FARMER,Reach-1         , 7
Up Type= 0
Dn Type= 3
Dn Slope=0.0066
DSS Import GetInterval= 0
DSS Import GetPeak= 0
DSS Import FillOption= 0

--- TRIB 1 TO FARMER CREEK.g01 (geometry) ---

Geom Title=Existing Conditions
Program Version=4.10

River Reach=TRIB 1 TO FARMER,Reach-1
Reach XY= 30
        2491875.       13468275.      2492268.94     13467933.14
      2492966.66     13467671.83      2493068.81     13467532.86
      2493292.05     13467458.51      2493465.22     13467235.52
      2493605.59     13467195.64      2493632.82     13467018.81
      2493768.83     13466882.86      2493914.39     13466835.06
      2494430.62     13465980.62       2494583.5     13465827.67
      2494717.15     13465831.81      2494835.63     13465364.88
      2494904.73     13465324.62      2495018.98     13465373.38
      2495117.53     13465281.08      2495088.19     13465011.27
      2495231.19     13464967.14      2495330.62     13464830.62
      2495541.67     13464708.35      2496164.24     13464034.68
      2496224.25     13463914.31      2496175.02     13463809.52
      2496207.78     13463741.07      2496335.05     13463763.89
      2496735.68     13463425.75      2496975.01     13463517.41
      2497073.54     13463477.96        2497125.       13463575.

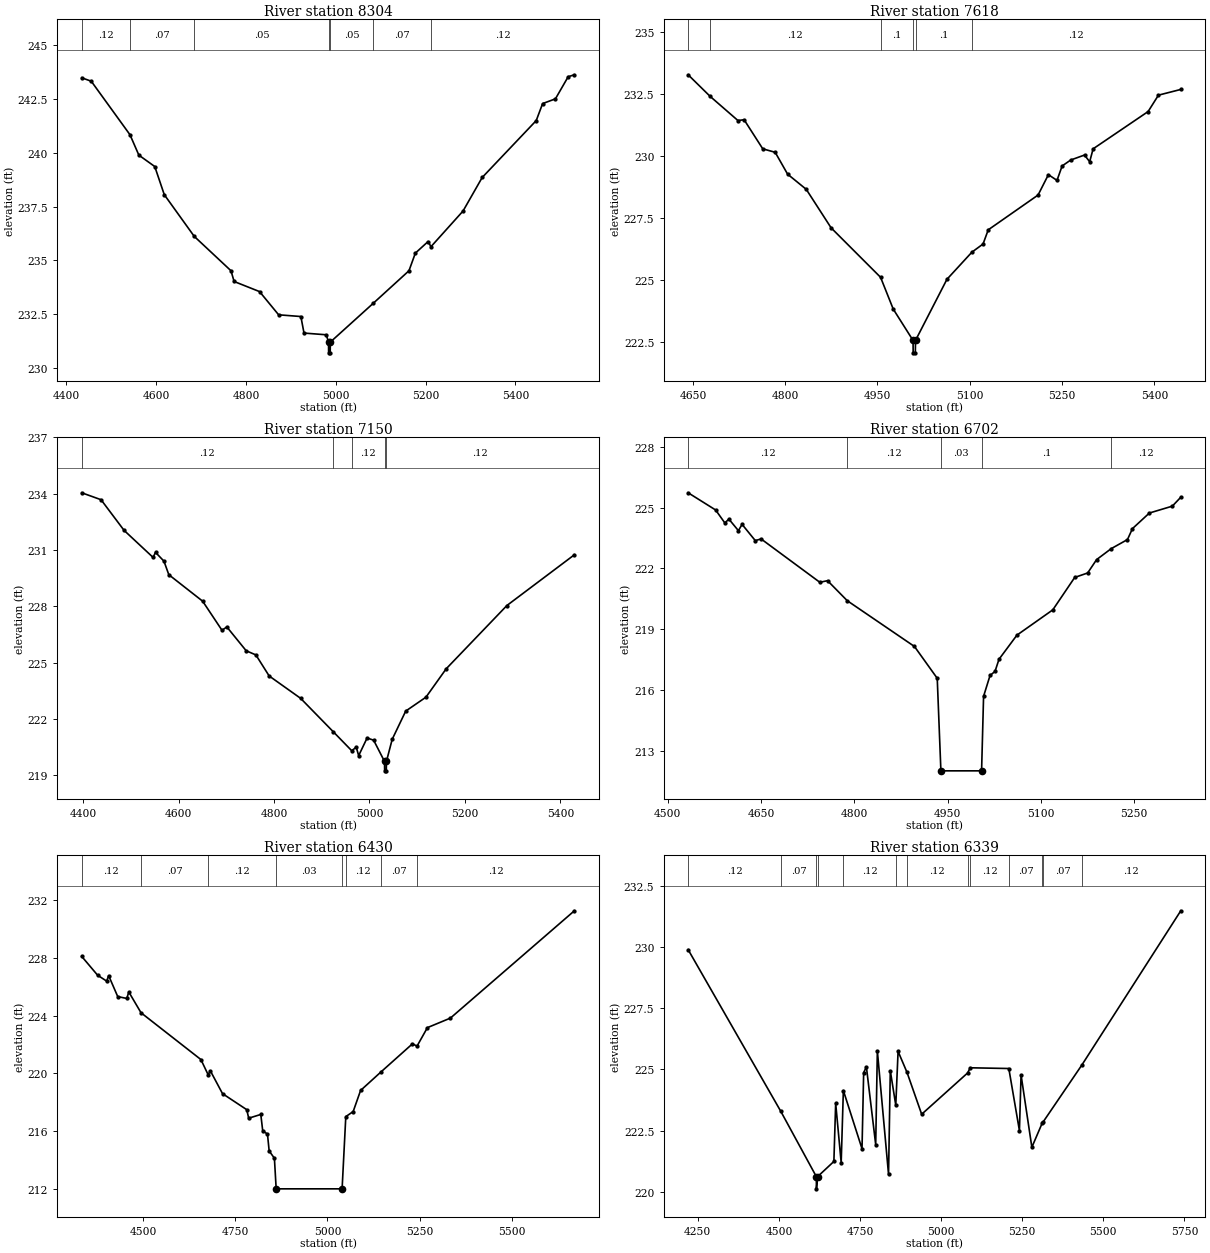
Type RM Length L Ch R = 1 ,8304    ,686,686,686
BEGIN DESCRIPTION:
TRIB 1 TO FARMER CREEK 18.0
END DESCRIPTION:
XS GIS Cut Line= 3
      2492324.97     13468624.97      2491921.91     13468228.03
        2491525.       13467875.
#Sta/Elev= 30
  4434.3  243.49  4455.5  243.33  4541.7  240.84  4561.5  239.89  4596.9  239.36
  4618.1  238.05  4684.8  236.11  4766.6  234.51  4773.6  234.01  4830.2  233.54
  4872.7  232.46  4922.2  232.38  4929.2  231.61  4978.8  231.53  4983.8  231.19
    4984  230.69  4987.5  230.69  4987.8  231.19  5083.6     233  5162.9  234.51
  5177.1  235.33  5205.5  235.87  5211.9  235.63  5283.3  237.29  5325.9  238.85
  5446.3   241.5  5460.5  242.29    5489  242.51  5517.4  243.54  5531.2  243.63
#Mann= 7 ,-1 , 0
  4434.3     .12       0  4541.7     .07       0  4684.8     .05       0
  4983.8     .05       0  4987.8     .05       0  5083.6     .07       0
  5211.9     .12       0
Bank Sta=4983.8,4987.8
XS Rating Curve= 0 ,0
Exp/Cntr=0.3,0.1

Type RM Length L Ch R = 1 ,7618    ,468,468,468
BEGIN DESCRIPTION:
TRIB 1 TO FARMER CREEK 17.0
END DESCRIPTION:
XS GIS Cut Line= 3
      2492525.01     13468225.04        2492475.       13467875.
        2492275.     13467475.01
#Sta/Elev= 30
  4642.2  233.27    4678   232.4  4723.1  231.43  4733.2  231.46  4763.5  230.29
  4783.7  230.15  4803.9  229.27  4834.2  228.66  4874.6  227.11    4955  225.12
  4975.6  223.84  5007.8  222.58    5008  222.08  5011.5  222.08  5011.8  222.58
  5062.9  225.04  5103.4  226.13  5121.6  226.46    5130  227.03    5211  228.43
  5227.8  229.25  5241.8  229.02  5250.1   229.6  5264.1  229.84  5286.5  230.04
  5294.9  229.77  5300.5  230.29  5389.9  231.79  5406.7  232.45    5443  232.68
#Mann= 6 ,-1 , 0
  4642.2     .07       0    4678     .12       0    4955      .1       0
  5007.8     .05       0  5011.8      .1       0  5103.4     .12       0
Bank Sta=5007.8,5011.8
XS Rating Curve= 0 ,0
Exp/Cntr=0.3,0.1

Type RM Length L Ch R = 1 ,7150    ,448,448,448
BEGIN DESCRIPTION:
TRIB 1 TO FARMER CREEK 16.0
END DESCRIPTION:
XS GIS Cut Line= 3
        2492775.     13468274.99        2492875.       13467675.
      2492575.02     13467375.02
#Sta/Elev= 30
  4396.9  234.04  4437.4  233.67  4485.6  232.04  4546.4   230.6  4551.5  230.87
  4569.2   230.4  4579.4  229.68  4650.3  228.27  4690.9  226.72    4701   226.9
  4741.6  225.63  4761.9  225.41  4789.7  224.29  4855.6   223.1  4923.7  221.33
  4962.8  220.31  4972.2   220.5  4977.3  220.05    4995  220.99  5008.7  220.87
  5031.5  219.74  5031.7  219.24  5035.2  219.24  5035.5  219.74  5047.6  220.92
  5075.9  222.42  5118.3  223.16  5160.7  224.67    5288  228.04  5429.4  230.74
#Mann= 5 ,-1 , 0
  4396.9     .12       0  4923.7     .12       0  4962.8     .12       0
  5031.5     .05       0  5035.5     .12       0
Bank Sta=5031.5,5035.5
XS Rating Curve= 0 ,0
Exp/Cntr=0.3,0.1

Type RM Length L Ch R = 1 ,6702    ,272,272,272
BEGIN DESCRIPTION:
TRIB 1 TO FARMER CREEK 15.0
END DESCRIPTION:
XS GIS Cut Line= 3
        2493475.       13467875.        2493225.       13467475.
      2492974.97     13467274.98
#Sta/Elev= 30
    4533  225.73  4577.2  224.88    4592  224.24  4598.5  224.43  4613.8  223.86
  4619.7  224.17  4640.9  223.37  4650.3  223.45  4744.7  221.31  4757.1  221.39
  4788.8   220.4  4896.8  218.14  4933.4  216.57  4939.3     212  5004.7     212
  5007.9  215.68  5018.3  216.71  5026.3  216.91  5032.7  217.51  5061.5   218.7
  5119.2  219.95  5154.4  221.55  5175.2  221.77  5189.6  222.43    5213  222.97
  5239.2  223.42  5247.2  223.96  5274.4  224.73  5311.3  225.07  5324.9  225.51
#Mann= 5 ,-1 , 0
    4533     .12       0  4788.8     .12       0  4939.3     .03       0
  5004.7      .1       0    5213     .12       0
Bank Sta=4939.3,5004.7
XS Rating Curve= 0 ,0
Exp/Cntr=0.3,0.1

Type RM Length L Ch R = 1 ,6430    ,91,91,91
BEGIN DESCRIPTION:
Mapping XS 8f775356
END DESCRIPTION:
XS GIS Cut Line= 6
      2493695.82     13467869.26      2493536.04     13467396.27
      2493485.32     13467349.35      2493394.02     13467291.02
      2493116.32     13467264.39      2492805.62     13467046.27
#Sta/Elev= 30
  4333.7  228.09  4376.7  226.79  4401.3  226.38  4406.7  226.76  4431.3  225.31
  4455.9  225.18  4461.3  225.63  4494.5  224.19  4656.9  220.95  4676.3  219.91
  4682.7  220.16  4715.5  218.59  4781.2  217.48  4786.5  216.89  4819.3  217.15
  4824.5  216.02  4837.4  215.79    4842  214.62  4856.2  214.12    4861     212
  5039.8     212  5049.8     217  5069.8  217.35  5089.9  218.81  5144.2  220.07
  5230.6  222.04    5243  221.88  5271.1  223.16  5333.5  223.82  5669.7  231.25
#Mann= 8 ,-1 , 0
  4333.7     .12       0  4494.5     .07       0  4676.3     .12       0
    4861     .03       0  5039.8     .07       0  5049.8     .12       0
  5144.2     .07       0    5243     .12       0
Bank Sta=4861,5039.8
XS Rating Curve= 0 ,0
Exp/Cntr=0.3,0.1

Type RM Length L Ch R = 1 ,6339    ,44,44,44
BEGIN DESCRIPTION:
Mapping XS 43842b22
END DESCRIPTION:
XS GIS Cut Line= 6
      2493806.13     13467912.36      2493542.38       13467272.
      2493482.78     13467237.76      2493385.14     13467213.67
      2493200.01     13467232.69       2492815.8     13466966.41
#Sta/Elev= 30
  4220.2   229.9  4505.8  223.29  4615.4  220.62  4615.7  220.12  4619.4  220.62
  4669.5  221.24    4675  223.62    4692  221.19  4698.7  224.14  4756.2  221.76
  4761.3  224.87  4769.7  225.11  4798.4  221.93  4803.5  225.76    4838  220.71
  4843.4  224.95  4860.3  223.54  4867.4  225.74    4895  224.88  4940.1  223.17
  5081.9  224.86  5089.7  225.07  5208.8  225.04  5241.5   222.5  5246.5  224.78
  5279.8  221.82  5312.4  222.83  5314.8  222.86  5433.8  225.18  5738.9  231.49
#Mann= 13 ,-1 , 0
  4220.2     .12       0  4505.8     .07       0  4615.4     .05       0
  4619.4     .07       0  4698.7     .12       0  4860.3     .12       0
    4895     .12       0  5081.9     .12       0  5089.7     .12       0
  5208.8     .07       0  5312.4     .12       0  5314.8     .07       0
  5433.8     .12       0
Bank Sta=4615.4,4619.4
XS Rating Curve= 0 ,0
Exp/Cntr=0.3,0.1

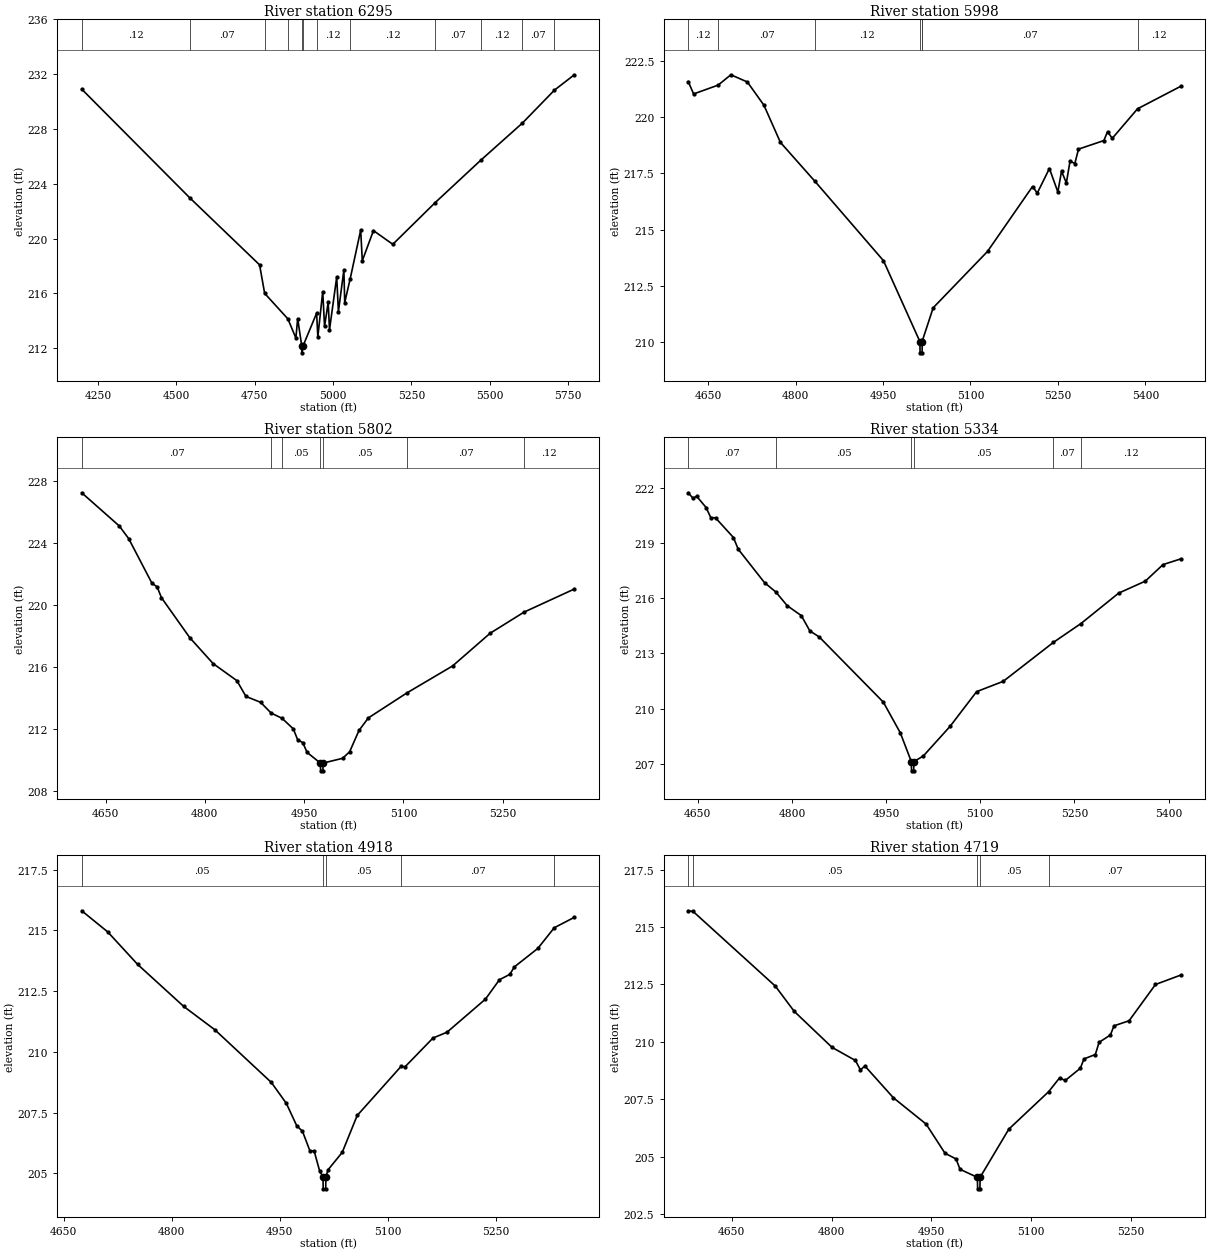
Type RM Length L Ch R = 1 ,6295    ,297,297,297
BEGIN DESCRIPTION:
Mapping XS 111c4d2c
END DESCRIPTION:
XS GIS Cut Line= 6
      2493865.72     13467926.29      2493618.46     13467329.06
      2493574.08     13467260.59      2493475.17      13467208.6
      2493151.82     13467138.85      2492825.15     13466909.68
#Sta/Elev= 30
  4197.5  230.91    4542  222.99  4765.3  218.09  4781.5  216.01  4855.6  214.15
  4881.2  212.75  4886.9  214.17  4899.9  212.17  4900.1  211.67  4903.9  212.17
  4947.3  214.56  4951.3  212.84  4966.9  216.14  4972.7   213.6  4984.3  215.36
  4988.5  213.35  5011.5   217.2    5017  214.68  5034.4  217.72  5037.1  215.34
  5054.7  217.09  5088.1  220.63  5093.2  218.39  5128.8  220.59  5190.6  219.59
  5326.3  222.64  5471.2  225.72  5604.1  228.43  5706.7  230.84  5770.1  231.96
#Mann= 12 ,-1 , 0
  4197.5     .12       0    4542     .07       0  4781.5     .12       0
  4855.6     .12       0  4899.9     .05       0  4903.9     .12       0
  4947.3     .12       0  5054.7     .12       0  5326.3     .07       0
  5471.2     .12       0  5604.1     .07       0  5706.7     .12       0
Bank Sta=4899.9,4903.9
XS Rating Curve= 0 ,0
Exp/Cntr=0.3,0.1

Type RM Length L Ch R = 1 ,5998    ,196,196,196
BEGIN DESCRIPTION:
Mapping XS 5b121c74
END DESCRIPTION:
XS GIS Cut Line= 3
      2493902.11     13467291.28      2493645.17     13467018.71
       2493271.9     13466732.25
#Sta/Elev= 30
  4615.7  221.58    4625  221.03    4667  221.42  4688.9  221.88  4717.2  221.56
  4745.6  220.53  4773.9  218.88  4833.2  217.15  4950.7  213.63  5013.2  210.04
  5013.5  209.54    5017  209.54  5017.2  210.04  5017.6  210.09    5036  211.54
  5129.2  214.04  5206.4  216.92  5214.6  216.63  5235.4  217.72  5249.9  216.68
  5256.2   217.6  5264.5  217.08  5270.8  218.05    5279  217.94  5285.3  218.58
  5328.8  218.96  5335.1  219.35  5343.3  219.06  5386.6  220.37  5460.8  221.37
#Mann= 7 ,-1 , 0
  4615.7     .12       0    4667     .07       0  4833.2     .12       0
  5013.2     .05       0  5017.2     .12       0  5017.6     .07       0
  5386.6     .12       0
Bank Sta=5013.2,5017.2
XS Rating Curve= 0 ,0
Exp/Cntr=0.3,0.1

Type RM Length L Ch R = 1 ,5802    ,468,468,468
BEGIN DESCRIPTION:
TRIB 1 TO FARMER CREEK 13.0
END DESCRIPTION:
XS GIS Cut Line= 3
      2494074.99     13467124.99        2493775.       13466875.
      2493525.03     13466625.03
#Sta/Elev= 30
  4614.1  227.27  4670.7  225.13    4685  224.31  4720.2  221.42    4728  221.19
  4734.5  220.49  4777.4   217.9  4812.6  216.23  4848.4  215.13  4862.1  214.11
  4884.2  213.73  4900.3  213.03  4916.5   212.7  4933.7  212.01  4940.2  211.31
    4948  211.12  4954.5  210.49  4974.6   209.8  4974.9   209.3  4978.4   209.3
  4978.6   209.8  5008.1  210.11  5018.7  210.53  5032.9  211.91    5047  212.72
  5105.4  214.34  5174.3  216.08  5230.9  218.19  5282.3  219.56  5358.1  221.05
#Mann= 7 ,-1 , 0
  4614.1     .07       0  4900.3     .12       0  4916.5     .05       0
  4974.6     .05       0  4978.6     .05       0  5105.4     .07       0
  5282.3     .12       0
Bank Sta=4974.6,4978.6
XS Rating Curve= 0 ,0
Exp/Cntr=0.3,0.1

Type RM Length L Ch R = 1 ,5334    ,416,416,416
BEGIN DESCRIPTION:
TRIB 1 TO FARMER CREEK 12.0
END DESCRIPTION:
XS GIS Cut Line= 3
      2494374.97     13466774.98        2494075.       13466575.
      2493774.99     13466274.99
#Sta/Elev= 30
  4634.7  221.72  4642.2  221.43  4648.2  221.53  4663.2  220.92  4670.7  220.37
  4678.2  220.36  4706.8  219.29  4714.3  218.66  4756.3  216.84  4774.4  216.33
  4792.4  215.59  4814.9  215.05  4828.5  214.22  4843.5  213.89  4945.6  210.35
  4972.7  208.68  4990.2  207.12  4990.5  206.62    4994  206.62  4994.2  207.12
  5009.4  207.43  5051.8  209.03  5094.2  210.92  5136.6  211.48  5216.7   213.6
  5260.5  214.62  5320.5  216.27  5362.9  216.92  5391.2  217.82  5419.5  218.13
#Mann= 6 ,-1 , 0
  4634.7     .07       0  4774.4     .05       0  4990.2     .05       0
  4994.2     .05       0  5216.7     .07       0  5260.5     .12       0
Bank Sta=4990.2,4994.2
XS Rating Curve= 0 ,0
Exp/Cntr=0.3,0.1

Type RM Length L Ch R = 1 ,4918    ,199,199,199
BEGIN DESCRIPTION:
TRIB 1 TO FARMER CREEK 11.0
END DESCRIPTION:
XS GIS Cut Line= 3
      2494475.03     13466475.04        2494275.       13466225.
      2493925.01       13466125.
#Sta/Elev= 30
  4675.2  215.81  4711.3  214.94  4752.9   213.6  4816.9  211.87  4860.1  210.91
  4938.6  208.74  4959.4  207.88  4973.8  206.96  4981.8  206.73  4992.2  205.92
    4998  205.92  5005.8  205.08  5010.3  204.86  5010.6  204.36  5014.1  204.36
  5014.3  204.86  5017.5  205.15    5037  205.86  5057.8  207.38    5119  209.41
  5124.1  209.38  5163.1  210.57  5182.6  210.81  5235.9  212.17  5255.4  212.97
  5269.7  213.19  5276.2   213.5  5308.7  214.26  5331.5  215.11  5359.4  215.54
#Mann= 5 ,-1 , 0
  4675.2     .05       0  5010.3     .05       0  5014.3     .05       0
    5119     .07       0  5331.5     .12       0
Bank Sta=5010.3,5014.3
XS Rating Curve= 0 ,0
Exp/Cntr=0.3,0.1

Type RM Length L Ch R = 1 ,4719    ,216,216,216
BEGIN DESCRIPTION:
Mapping XS 72ee2aa3
END DESCRIPTION:
XS GIS Cut Line= 3
      2494666.49     13466368.44      2494408.67     13466079.37
        2494091.     13465925.75
#Sta/Elev= 30
  4584.4  215.71  4591.8  215.68  4715.3  212.43  4743.7  211.33  4800.6  209.76
  4835.7  209.19  4843.2  208.78  4849.9  208.95  4892.6  207.57  4941.9  206.42
  4970.3  205.15  4986.9   204.9  4992.9  204.45    5019   204.1  5019.3   203.6
  5022.8   203.6    5023   204.1  5066.2   206.2    5126  207.83  5142.4  208.43
    5151  208.32  5173.6  208.85  5179.2  209.26  5196.2  209.45  5201.8  209.98
  5218.8   210.3  5224.3   210.7  5246.9  210.92  5286.6   212.5  5324.6  212.91
#Mann= 5 ,-1 , 0
  4584.4     .07       0  4591.8     .05       0    5019     .05       0
    5023     .05       0    5126     .07       0
Bank Sta=5019,5023
XS Rating Curve= 0 ,0
Exp/Cntr=0.3,0.1

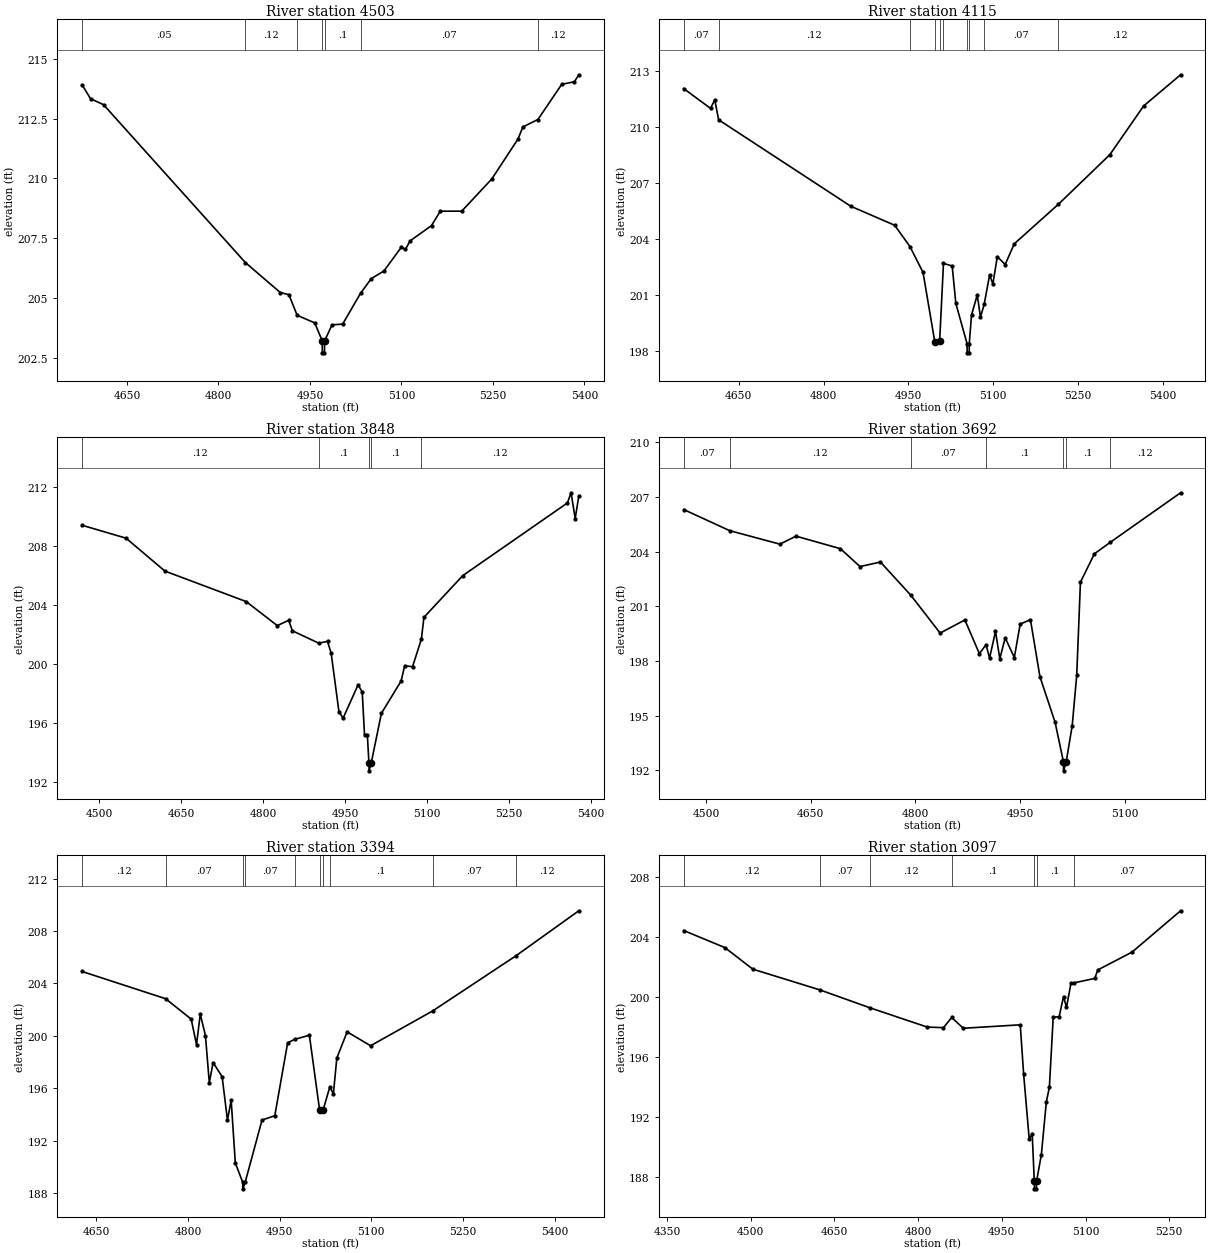
Type RM Length L Ch R = 1 ,4503    ,388,388,388
BEGIN DESCRIPTION:
TRIB 1 TO FARMER CREEK 10.0
END DESCRIPTION:
XS GIS Cut Line= 3
      2494825.01     13466225.01        2494525.       13465925.
      2494224.99     13465674.99
#Sta/Elev= 30
  4576.1  213.92  4590.2  213.33  4611.5  213.08  4844.2  206.48  4901.4  205.23
  4915.5  205.14    4929  204.28  4957.9  203.96  4970.1  203.21  4970.3  202.71
  4973.8  202.71  4974.1  203.21  4986.2  203.88  5003.6  203.91    5033   205.2
  5050.5  205.81  5071.3  206.13    5100  207.13  5106.5  207.03  5114.3  207.39
  5149.4  208.03  5163.7  208.63  5198.9  208.63  5248.3  209.98  5291.3  211.65
  5299.1  212.15  5323.8  212.46  5362.9  213.93  5383.7  214.04  5390.9  214.33
#Mann= 7 ,-1 , 0
  4576.1     .05       0  4844.2     .12       0    4929      .1       0
  4970.1     .05       0  4974.1      .1       0    5033     .07       0
  5323.8     .12       0
Bank Sta=4970.1,4974.1
XS Rating Curve= 0 ,0
Exp/Cntr=0.3,0.1

Type RM Length L Ch R = 1 ,4115    ,267,267,267
BEGIN DESCRIPTION:
TRIB 1 TO FARMER CREEK 9.0
END DESCRIPTION:
XS GIS Cut Line= 3
      2495059.98     13466027.48      2494729.08      13465726.5
      2494350.64     13465519.82
#Sta/Elev= 30
  4552.7  212.06  4600.1     211  4607.6  211.46  4614.4  210.39  4848.1  205.76
  4925.8  204.74  4952.7   203.6  4975.8  202.22  4996.8  198.47  5005.2  198.53
    5012   202.7  5027.4  202.56  5033.8  200.56  5053.6  198.41  5053.9  197.91
  5057.4  197.91  5057.6  198.41  5061.6  199.94  5071.7  201.01  5077.4  199.82
  5083.9   200.5  5093.6  202.09  5099.3   201.6  5107.2  203.06  5121.1  202.64
  5137.2  203.75  5215.3  205.87  5306.1  208.52  5365.9  211.13  5431.2   212.8
#Mann= 10 ,-1 , 0
  4552.7     .07       0  4614.4     .12       0  4952.7      .1       0
  4996.8     .05       0  5005.2     .07       0    5012      .1       0
  5053.6     .07       0  5057.6      .1       0  5083.9     .07       0
  5215.3     .12       0
Bank Sta=4996.8,5005.2
XS Rating Curve= 0 ,0
Exp/Cntr=0.3,0.1

Type RM Length L Ch R = 1 ,3848    ,156,156,156
BEGIN DESCRIPTION:
Mapping XS 5a754789
END DESCRIPTION:
XS GIS Cut Line= 3
      2495174.28      13465850.2      2494783.67     13465506.46
      2494490.49      13465249.6
#Sta/Elev= 30
  4468.2  209.39    4549  208.51  4620.1  206.28  4769.1  204.21    4826  202.58
  4846.9  202.94  4853.6  202.23  4901.9  201.39    4918  201.51  4924.7  200.71
  4938.9  196.75  4946.5   196.3  4974.1  198.57  4981.6  198.07  4985.8  195.17
    4991  195.17  4993.9  193.23  4994.1  192.73  4997.9  193.23  5016.7  196.63
  5052.8  198.82  5059.4  199.86  5073.7  199.79  5089.9  201.65  5094.6  203.14
  5165.7  205.97  5357.4   210.9  5364.1  211.59  5371.7  209.84  5378.3  211.38
#Mann= 5 ,-1 , 0
  4468.2     .12       0  4901.9      .1       0  4993.9     .05       0
  4997.9      .1       0  5089.9     .12       0
Bank Sta=4993.9,4997.9
XS Rating Curve= 0 ,0
Exp/Cntr=0.3,0.1

Type RM Length L Ch R = 1 ,3692    ,298,298,298
BEGIN DESCRIPTION:
Mapping XS d0326a74
END DESCRIPTION:
XS GIS Cut Line= 3
      2495265.82     13465678.43      2494833.67     13465359.16
      2494668.51     13465300.67
#Sta/Elev= 30
  4467.8  206.31  4533.8  205.15  4605.8  204.41  4628.8  204.85  4692.6  204.16
  4720.6  203.18  4749.9  203.43  4793.2  201.62  4835.5  199.53    4871  200.25
  4891.8   198.4  4901.3  198.89  4906.4  198.16  4914.9  199.62  4921.1  198.12
  4928.8  199.27  4941.9  198.19  4950.3  200.02    4965  200.27  4978.6  197.14
  5000.4  194.63  5012.3  192.47  5012.5  191.97  5016.3  192.47  5024.9  194.45
  5031.4  197.22  5036.7  202.32  5056.7  203.88  5079.4  204.51  5180.3  207.23
#Mann= 7 ,-1 , 0
  4467.8     .07       0  4533.8     .12       0  4793.2     .07       0
  4901.3      .1       0  5012.3     .05       0  5016.3      .1       0
  5079.4     .12       0
Bank Sta=5012.3,5016.3
XS Rating Curve= 0 ,0
Exp/Cntr=0.3,0.1

Type RM Length L Ch R = 1 ,3394    ,297,297,297
BEGIN DESCRIPTION:
Mapping XS 8bd4f768
END DESCRIPTION:
XS GIS Cut Line= 3
      2495390.42     13465529.88      2495093.57     13465321.56
      2494688.62     13465124.28
#Sta/Elev= 30
  4626.6  204.91  4763.5  202.83  4805.4  201.27  4814.1  199.32  4820.2  201.65
  4828.7  200.02    4835  196.41  4841.2  197.96    4856  196.88  4864.7  193.57
  4870.8  195.08  4877.6  190.29  4889.7  188.82    4890  188.32  4893.7  188.82
  4921.3  193.57  4942.2   193.9  4963.2  199.46  4974.7  199.73  4998.8  200.04
  5015.6  194.31  5021.1  194.31  5032.2  196.09  5038.1  195.58  5043.7   198.3
  5060.6   200.3  5098.9  199.24  5200.7   201.9  5336.7   206.1  5439.7  209.54
#Mann= 10 ,-1 , 0
  4626.6     .12       0  4763.5     .07       0  4889.7     .07       0
  4893.7     .07       0  4974.7      .1       0  5015.6     .05       0
  5021.1     .07       0  5032.2      .1       0  5200.7     .07       0
  5336.7     .12       0
Bank Sta=5015.6,5021.1
XS Rating Curve= 0 ,0
Exp/Cntr=0.3,0.1

Type RM Length L Ch R = 1 ,3097    ,499,499,499
BEGIN DESCRIPTION:
Mapping XS 37ff1baf
END DESCRIPTION:
XS GIS Cut Line= 3
      2495574.19     13465417.79      2495090.61     13465057.08
      2494820.11     13464959.97
#Sta/Elev= 30
  4379.7  204.45  4453.5  203.31  4503.5  201.87  4624.1  200.48  4713.3  199.29
  4816.2     198  4845.4  197.96  4860.1  198.64  4880.9  197.92    4983  198.15
    4989  194.89  4999.1  190.49  5004.4  190.88  5008.2  187.69  5008.5  187.19
    5012  187.19  5012.2  187.69  5020.8  189.46  5029.8  193.01  5035.2  193.97
  5042.1  198.66  5052.7  198.69  5060.6  200.04  5065.9  199.31    5074  200.95
    5079  200.95  5116.5  201.25  5122.1  201.82  5183.5  203.01  5270.4  205.77
#Mann= 7 ,-1 , 0
  4379.7     .12       0  4624.1     .07       0  4713.3     .12       0
  4860.1      .1       0  5008.2     .05       0  5012.2      .1       0
    5079     .07       0
Bank Sta=5008.2,5012.2
XS Rating Curve= 0 ,0
Exp/Cntr=0.3,0.1

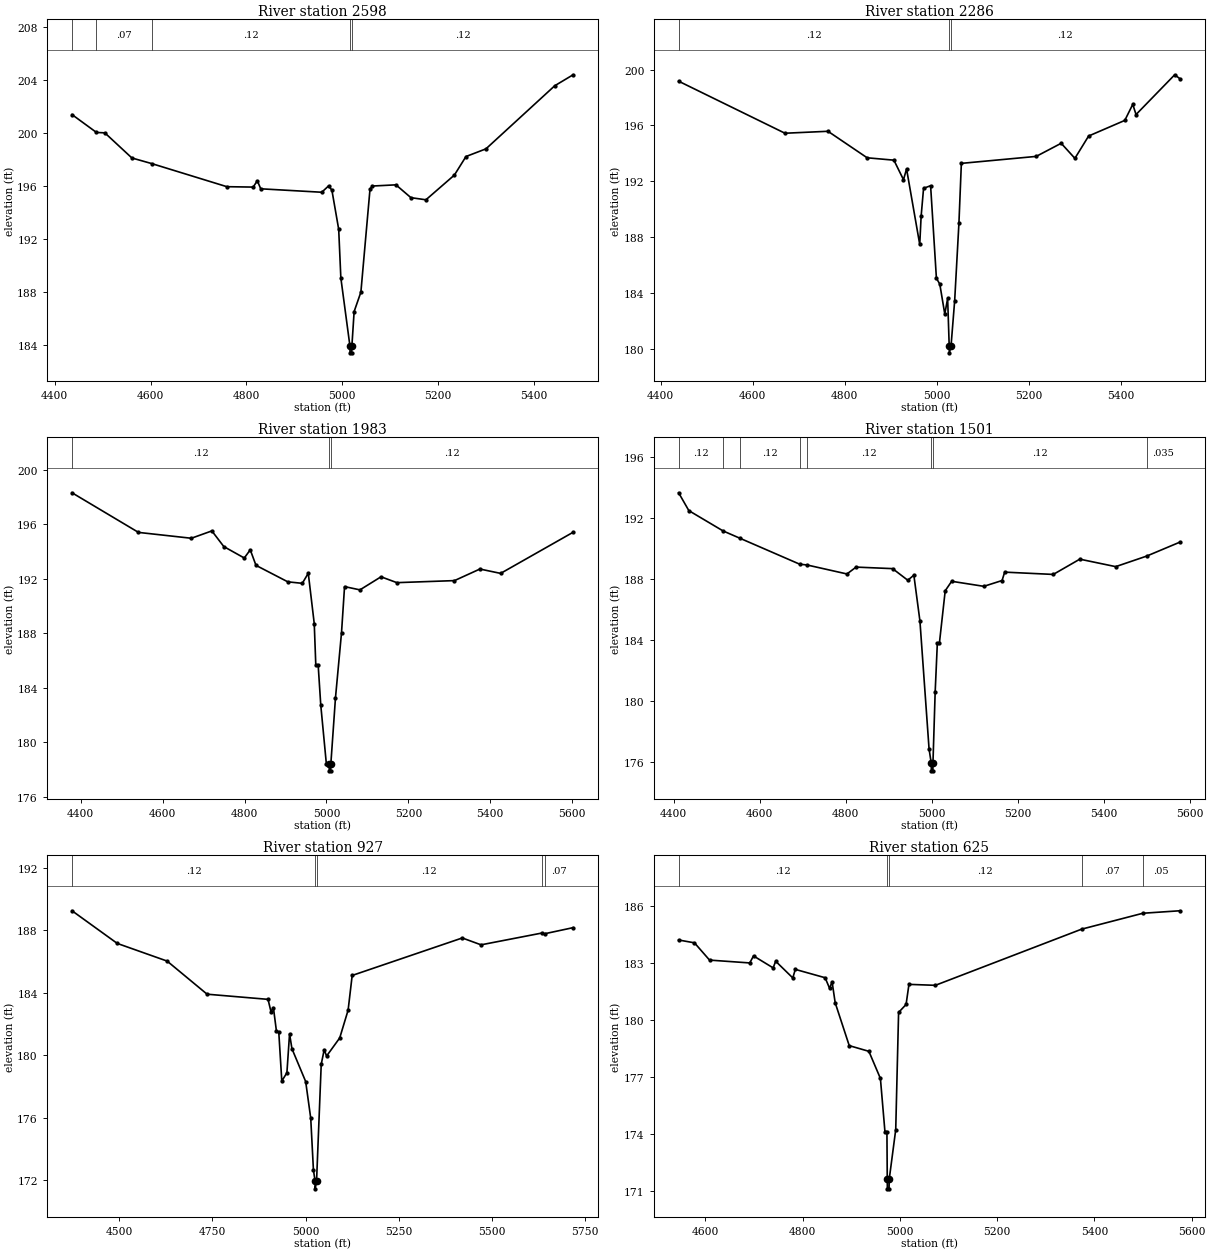
Type RM Length L Ch R = 1 ,2598    ,312,312,312
BEGIN DESCRIPTION:
Mapping XS ac367ae5
END DESCRIPTION:
XS GIS Cut Line= 3
      2495826.01     13465170.69      2495433.64     13464767.91
      2494970.82     13464629.76
#Sta/Elev= 30
  4436.3   201.4  4487.3  200.05  4504.7  200.02  4561.2  198.12  4602.2   197.7
  4759.3  195.95  4814.2  195.92  4822.8   196.4    4830  195.79  4957.3  195.53
  4971.5  196.01  4978.4  195.69  4992.6  192.73  4997.1  189.05  5016.1  183.89
  5016.3  183.39  5019.8  183.39  5020.1  183.89  5024.8  186.51  5038.9  187.98
  5057.9  195.76  5063.1     196    5112  196.09  5143.3  195.12  5174.6  194.96
    5234  196.83  5258.1  198.23  5299.8  198.81  5443.3  203.58  5481.6  204.41
#Mann= 5 ,-1 , 0
  4436.3     .12       0  4487.3     .07       0  4602.2     .12       0
  5016.1     .05       0  5020.1     .12       0
Bank Sta=5016.1,5020.1
XS Rating Curve= 0 ,0
Exp/Cntr=0.3,0.1

Type RM Length L Ch R = 1 ,2286    ,303,303,303
BEGIN DESCRIPTION:
Mapping XS 157f5030
END DESCRIPTION:
XS GIS Cut Line= 3
       2496117.7     13464917.24      2495683.64     13464583.89
      2495180.14     13464385.96
#Sta/Elev= 30
  4439.2  199.17  4670.2  195.44  4763.6  195.58  4848.7  193.68  4906.8  193.51
  4927.6  192.11  4934.3  192.88  4962.9  187.47  4965.9  189.48  4971.2  191.49
  4986.5  191.68  4999.1  185.05  5006.5  184.62  5017.3  182.48  5023.5   183.6
  5026.9   180.2  5027.2   179.7  5030.9   180.2  5038.8  183.45    5048  188.98
  5053.3  193.28  5215.9  193.78  5270.1  194.72  5299.9  193.64  5329.7  195.24
  5408.3  196.36  5425.6  197.51  5432.7  196.78  5516.7  199.63  5527.5  199.36
#Mann= 3 ,-1 , 0
  4439.2     .12       0  5026.9     .05       0  5030.9     .12       0
Bank Sta=5026.9,5030.9
XS Rating Curve= 0 ,0
Exp/Cntr=0.3,0.1

Type RM Length L Ch R = 1 ,1983    ,482,482,482
BEGIN DESCRIPTION:
Mapping XS 607b70df
END DESCRIPTION:
XS GIS Cut Line= 3
      2496385.04      13464733.2      2495905.86     13464375.55
      2495343.32     13464101.23
#Sta/Elev= 30
  4378.6  198.32  4540.9  195.41    4670  194.98  4720.1  195.52  4749.3  194.37
  4799.3  193.53  4813.9  194.13  4827.9  192.99  4905.6  191.78    4941  191.67
  4955.6  192.41  4970.2  188.71    4974  185.65  4979.8  185.65  4986.1  182.73
  4999.7  178.43  5006.7   178.4  5006.9   177.9  5010.4   177.9  5010.7   178.4
    5022  183.25  5036.8  188.05  5044.2  191.43  5081.8  191.19  5133.3  192.15
    5172  191.72  5312.7  191.87  5374.8  192.72  5425.4   192.4  5602.4  195.42
#Mann= 3 ,-1 , 0
  4378.6     .12       0  5006.7     .05       0  5010.7     .12       0
Bank Sta=5006.7,5010.7
XS Rating Curve= 0 ,0
Exp/Cntr=0.3,0.1

Type RM Length L Ch R = 1 ,1501    ,574,574,574
BEGIN DESCRIPTION:
Mapping XS ef8d0058
END DESCRIPTION:
XS GIS Cut Line= 3
       2496589.9     13464413.75      2496162.81     13463983.19
      2495618.87       13463855.
#Sta/Elev= 30
  4411.5  193.66  4435.3  192.49  4514.9  191.16  4553.3  190.69  4693.1  188.98
    4710  188.93    4803  188.34  4824.2  188.79  4909.1  188.69  4944.4  187.93
  4958.6  188.26  4972.7  185.26  4993.9  176.89    4999  175.94  4999.3  175.44
  5002.8  175.44    5003  175.94  5008.1  180.58  5013.2  183.81    5018  183.81
  5031.5  187.24  5046.5  187.86  5121.3  187.53  5163.7  187.91  5169.8  188.46
  5282.8  188.31  5344.5  189.31    5428  188.82  5499.9  189.51  5576.8  190.42
#Mann= 8 ,-1 , 0
  4411.5     .12       0  4514.9    .035       0  4553.3     .12       0
  4693.1    .035       0    4710     .12       0    4999     .05       0
    5003     .12       0  5499.9    .035       0
Bank Sta=4999,5003
XS Rating Curve= 0 ,0
Exp/Cntr=0.3,0.1

Type RM Length L Ch R = 1 ,927     ,302,302,302
BEGIN DESCRIPTION:
Mapping XS a737caf2
END DESCRIPTION:
XS GIS Cut Line= 4
      2496631.56     13464215.81      2496596.84     13463809.58
        2496326.      13463594.3      2495739.61     13463531.85
#Sta/Elev= 30
    4374  189.25  4495.3  187.16  4628.9  186.03  4736.1  183.91  4899.5  183.58
  4907.5  182.78  4913.9  183.05  4921.9  181.57  4928.3  181.49  4936.4  178.35
  4950.1  178.88  4957.2  181.37  4963.6  180.42  5000.4  178.32    5014  175.97
  5021.2  172.66  5025.6  171.95  5025.9  171.45  5029.6  171.95  5042.1  179.42
  5050.1  180.36  5056.5  179.95  5091.7  181.11  5114.2  182.89  5125.1  185.11
  5420.3  187.51  5470.6  187.07  5632.7  187.82  5641.3  187.78  5717.4  188.17
#Mann= 5 ,-1 , 0
    4374     .12       0  5025.6     .05       0  5029.6     .12       0
  5632.7     .05       0  5641.3     .07       0
Bank Sta=5025.6,5029.6
XS Rating Curve= 0 ,0
Exp/Cntr=0.3,0.1

Type RM Length L Ch R = 1 ,625     ,502,502,502
BEGIN DESCRIPTION:
Mapping XS f3734141
END DESCRIPTION:
XS GIS Cut Line= 4
      2496759.63     13463906.52      2496651.13     13463492.04
        2496573.      13463444.3      2496065.17     13463392.21
#Sta/Elev= 30
    4545  184.21  4577.6  184.06  4608.6  183.15  4691.3     183    4699  183.37
  4739.4  182.74  4744.6  183.09  4779.8  182.21    4785  182.66  4846.3  182.22
  4855.5  181.66  4860.6  182.01    4867   180.9  4895.9  178.64  4936.3  178.34
    4960  176.91  4969.3  174.11  4973.4  174.11  4974.1  171.59  4974.3  171.09
  4977.8  171.09  4978.1  171.59  4991.5  174.21  4997.4  180.39  5012.8  180.81
  5018.7  181.87    5073  181.82  5373.7  184.78  5499.9  185.62  5575.5  185.75
#Mann= 5 ,-1 , 0
    4545     .12       0  4974.1     .05       0  4978.1     .12       0
  5373.7     .07       0  5499.9     .05       0
Bank Sta=4974.1,4978.1
XS Rating Curve= 0 ,0
Exp/Cntr=0.3,0.1

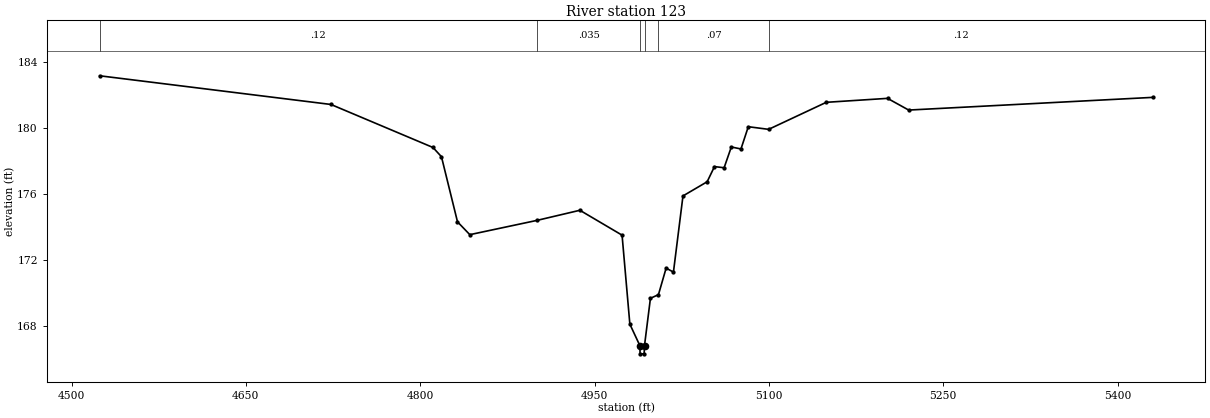
Type RM Length L Ch R = 1 ,123     ,0,0,0
BEGIN DESCRIPTION:
TRIB 1 TO FARMER CREEK 1.0
END DESCRIPTION:
XS GIS Cut Line= 5
      2496807.36     13463858.81      2497001.82     13463669.56
       2497069.1     13463476.49      2497010.84     13463400.23
      2496703.23     13463269.26
#Sta/Elev= 30
  4524.2  183.19  4723.2  181.45    4811  178.84  4818.3  178.28  4832.1  174.33
  4842.7  173.55  4900.7  174.42  4937.4  175.03  4973.7  173.52  4980.4  168.12
    4989  166.82  4989.2  166.32  4992.7  166.32    4993  166.82  4998.1  169.69
    5005  169.91  5011.6  171.52  5017.9  171.28  5026.1   175.9  5046.9  176.76
  5053.2  177.68  5061.5  177.61  5067.7  178.87    5076  178.75  5082.3   180.1
  5099.8  179.94  5149.4  181.58  5202.1  181.82  5220.3  181.11  5430.3  181.88
#Mann= 6 ,-1 , 0
  4524.2     .12       0  4900.7    .035       0    4989    .035       0
    4993    .035       0    5005     .07       0  5099.8     .12       0
Bank Sta=4989,4993
XS Rating Curve= 0 ,0
Exp/Cntr=0.3,0.1

Chan Stop Cuts=-1
Use User Specified Reach Order=0
Composite Channel Slope=5