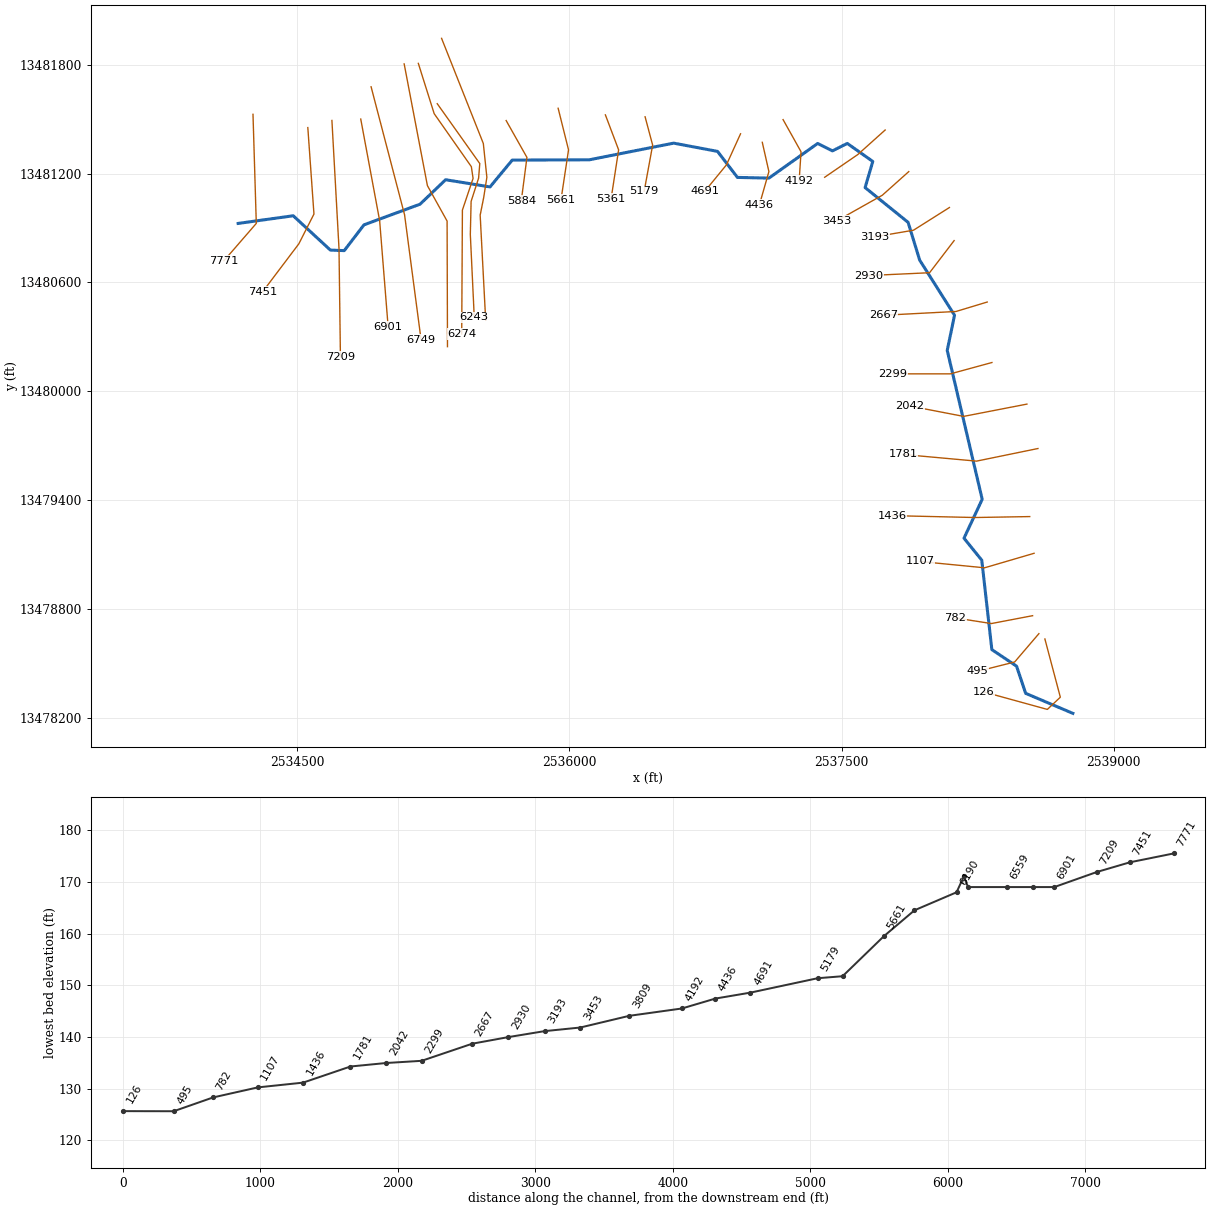
--- TRIB 1 TO GOBBLER CREEK.prj (project) ---

Proj Title=TRIB 1 TO GOBBLER CREEK Base Level Engineering
Current Plan=p01
Default Exp/Contr=0.3,0.1
English Units
Geom File=g01
Flow File=f01
Plan File=p01
Y Axis Title=Elevation
X Axis Title(PF)=Main Channel Distance
X Axis Title(XS)=Station
BEGIN DESCRIPTION:
TRIB 1 TO GOBBLER CREEK
END DESCRIPTION:
DSS Export Rating Curves= 0
DSS Export Rating Curve Sorted= 0
DSS Export Volume Flow Curves= 0
DXF OffsetX= 0
DXF OffsetY= 0
DXF ScaleX= 1
DXF ScaleY= 10

--- TRIB 1 TO GOBBLER CREEK.p01 (plan) ---

Plan Title=Multiple Run
Short Identifier=Multiple
Geom File=g01
Flow File=f01
Subcritical Flow
K Sum by GR= 0
Std Step Tol= 0.01
Critical Tol= 0.01
Num of Std Step Trials= 20
Max Error Tol= 0.3
Flow Tol Ratio= 0.001
Split Flow NTrial= 30
Split Flow Tol= 0.02
Split Flow Ratio= 0.02
Log Output Level= 0
Friction Slope Method= 1
Unsteady Friction Slope Method= 2
Unsteady Bridges Friction Slope Method= 1
Parabolic Critical Depth
Global Vel Dist=  1 , 1 , 1
Global Log Level= 0
CheckData=True
Encroach Param= -1, 0, 0, 0
BEGIN DESCRIPTION:
Multiple Run
END DESCRIPTION:

--- TRIB 1 TO GOBBLER CREEK.f01 (steady flow) ---

Flow Title=Multiple
Number of Profiles=7
Profile Names=10-year,25-year,50-year,1pct_min,100-year,1pct_plu,500-year
River Rch & RM= TRIB 1 TO GOBBLE,Reach-1,7771
     404     622     810     511    1019    2034    1595
River Rch & RM= TRIB 1 TO GOBBLE,Reach-1,3193
     625     989    1312     842    1681    3354    2725
Boundary for River Rch & Prof#=TRIB 1 TO GOBBLE,Reach-1,1
Up Type=0
Dn Type=3
Dn Slope=0.005
Boundary for River Rch & Prof#=TRIB 1 TO GOBBLE,Reach-1,2
Up Type=0
Dn Type=3
Dn Slope=0.005
Boundary for River Rch & Prof#=TRIB 1 TO GOBBLE,Reach-1,3
Up Type=0
Dn Type=3
Dn Slope=0.005
Boundary for River Rch & Prof#=TRIB 1 TO GOBBLE,Reach-1,4
Up Type=0
Dn Type=3
Dn Slope=0.005
Boundary for River Rch & Prof#=TRIB 1 TO GOBBLE,Reach-1,5
Up Type=0
Dn Type=3
Dn Slope=0.005
Boundary for River Rch & Prof#=TRIB 1 TO GOBBLE,Reach-1,6
Up Type=0
Dn Type=3
Dn Slope=0.005
Boundary for River Rch & Prof#=TRIB 1 TO GOBBLE,Reach-1,7
Up Type=0
Dn Type=3
Dn Slope=0.005

--- TRIB 1 TO GOBBLER CREEK.g01 (geometry) ---

Geom Title=Existing Conditions
Program Version=4.10

River Reach=TRIB 1 TO GOBBLE,Reach-1
Reach XY= 30
        2534175.       13480925.      2534478.41     13480967.19
      2534683.35     13480777.99      2534759.78     13480775.13
      2534868.55     13480917.25       2535177.3     13481030.83
      2535318.33      13481165.7      2535562.99     13481126.18
      2535685.43     13481273.95      2536109.78     13481275.52
        2536575.     13481367.44       2536816.7     13481321.93
      2536926.45     13481178.53      2537100.12      13481174.7
      2537368.39     13481365.57        2537450.     13481324.78
      2537531.73     13481365.84      2537672.36     13481266.52
      2537629.99     13481122.46      2537866.86     13480931.06
      2537930.77     13480722.68      2538122.77     13480419.07
      2538082.56       13480225.      2538275.29     13479404.82
      2538174.95     13479190.34      2538272.93     13479069.14
      2538328.45     13478576.25      2538464.61      13478485.1
      2538514.84     13478335.36        2538775.       13478225.

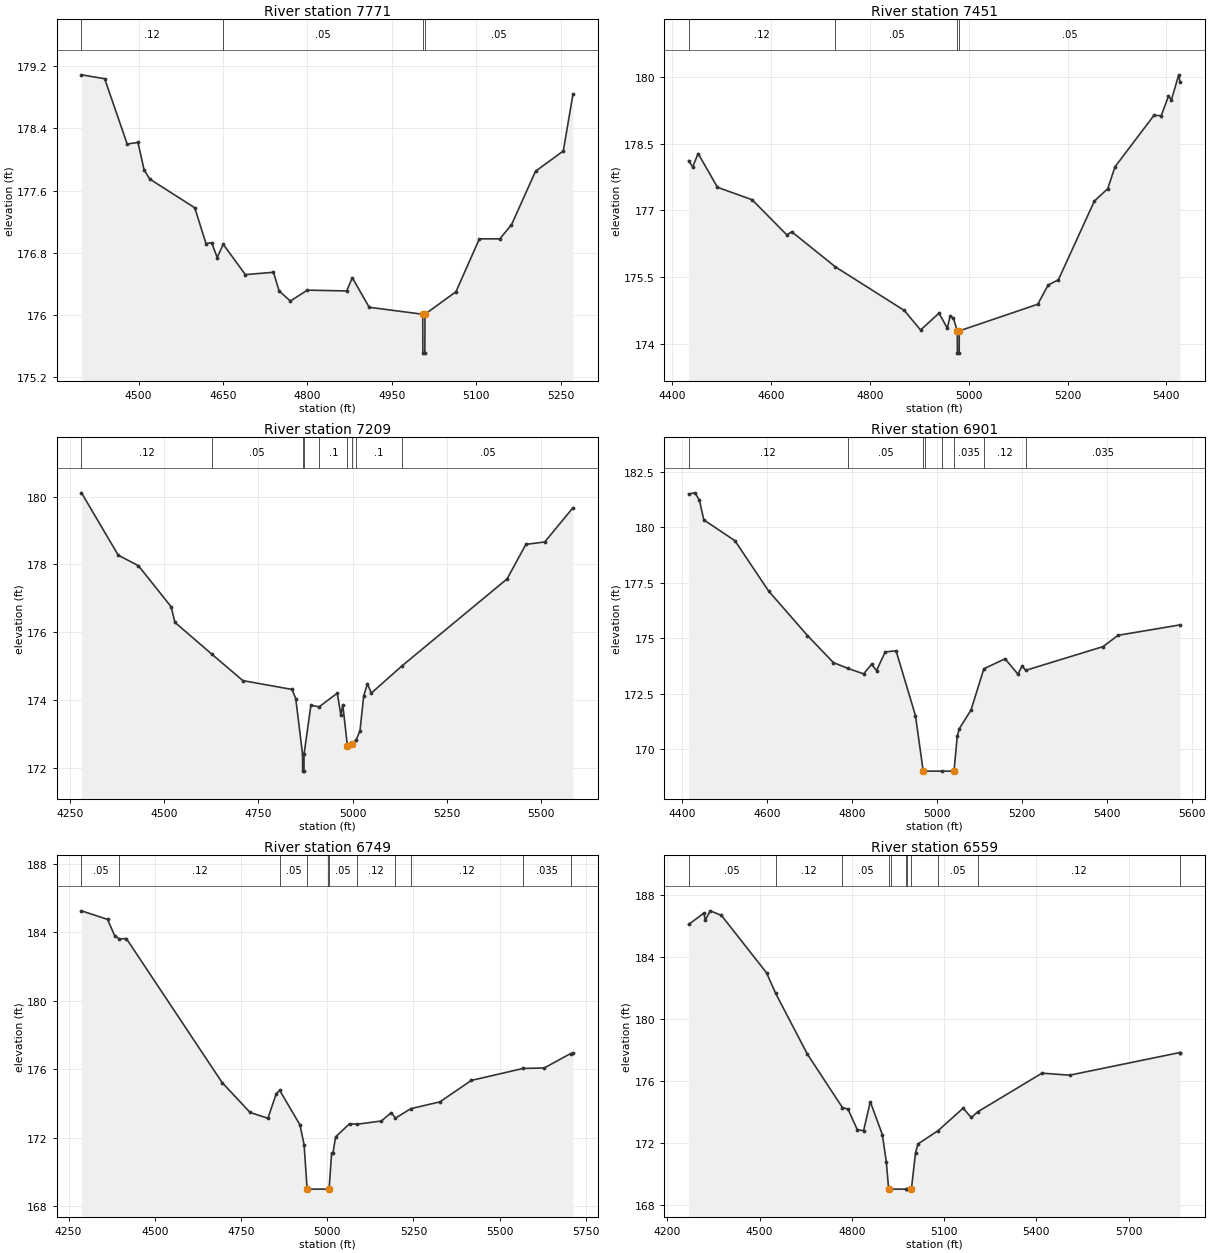
Type RM Length L Ch R = 1 ,7771    ,320,320,320
BEGIN DESCRIPTION:
TRIB 1 TO GOBBLER CREEK 17.0
END DESCRIPTION:
XS GIS Cut Line= 3
      2534256.84     13481526.18        2534275.       13480925.
      2534096.76     13480719.34
#Sta/Elev= 30
  4398.5  179.09  4439.7  179.04  4479.7   178.2  4498.9  178.22  4509.7  177.87
  4519.7  177.75  4599.8  177.38  4619.8  176.92  4629.8  176.93  4639.8  176.74
  4650.4  176.91  4689.8  176.52  4739.8  176.55  4749.8  176.31  4769.8  176.18
  4799.9  176.32  4869.9  176.31  4879.9  176.48  4909.9   176.1  5005.1  176.01
  5005.3  175.51  5008.8  175.51  5009.1  176.01  5064.1   176.3  5105.8  176.98
    5142  176.98  5162.8  177.16  5205.6  177.85  5254.9  178.11  5272.1  178.84
#Mann= 4 ,-1 , 0
  4398.5     .12       0  4650.4     .05       0  5005.1     .05       0
  5009.1     .05       0
Bank Sta=5005.1,5009.1
XS Rating Curve= 0 ,0
Exp/Cntr=0.3,0.1

Type RM Length L Ch R = 1 ,7451    ,242,242,242
BEGIN DESCRIPTION:
Mapping XS 8932d6d2
END DESCRIPTION:
XS GIS Cut Line= 4
      2534558.93     13481453.21      2534592.78     13480976.68
      2534509.45     13480812.62       2534308.9     13480546.96
#Sta/Elev= 30
  4433.2  178.12  4441.4  177.98  4452.4  178.28  4491.6  177.52  4561.7  177.24
  4631.9  176.45  4641.9  176.52  4730.3  175.73  4869.6  174.75  4902.6  174.31
    4940  174.69  4956.7  174.35  4962.3  174.62  4968.9  174.58  4976.9  174.29
  4977.2  173.79  4980.7  173.79  4980.9  174.29  5139.8  174.89  5160.6  175.32
  5181.5  175.44  5254.3  177.21  5281.4  177.49    5296  177.98    5375  179.14
  5389.6  179.13  5404.2  179.57  5410.4  179.49    5425  180.05  5427.8  179.88
#Mann= 4 ,-1 , 0
  4433.2     .12       0  4730.3     .05       0  4976.9     .05       0
  4980.9     .05       0
Bank Sta=4976.9,4980.9
XS Rating Curve= 0 ,0
Exp/Cntr=0.3,0.1

Type RM Length L Ch R = 1 ,7209    ,308,308,308
BEGIN DESCRIPTION:
Mapping XS 7bde6838
END DESCRIPTION:
XS GIS Cut Line= 3
      2534691.74     13481492.35       2534730.8     13480786.58
      2534738.62     13480190.18
#Sta/Elev= 30
  4280.6  180.11  4378.1  178.27  4431.6  177.96  4518.3  176.75  4528.3  176.29
  4626.3  175.35  4708.6  174.57  4838.8  174.31  4848.8  174.04  4866.8   172.4
  4867.1   171.9  4870.6   171.9  4870.8   172.4  4888.9  173.84  4911.1   173.8
    4959   174.2  4968.5  173.55  4973.5  173.86  4985.7  172.65    4999   172.7
    5009  172.83    5019  173.08    5029  174.12    5039  174.48    5049   174.2
  5131.1  175.01  5409.1  177.57  5459.1  178.59  5509.1  178.66  5583.9  179.67
#Mann= 9 ,-1 , 0
  4280.6     .12       0  4626.3     .05       0  4866.8     .07       0
  4870.8     .05       0  4911.1      .1       0  4985.7     .05       0
    4999     .07       0    5009      .1       0  5131.1     .05       0
Bank Sta=4985.7,4999
XS Rating Curve= 0 ,0
Exp/Cntr=0.3,0.1

Type RM Length L Ch R = 1 ,6901    ,152,152,152
BEGIN DESCRIPTION:
Mapping XS 1d20eafb
END DESCRIPTION:
XS GIS Cut Line= 3
       2534850.6     13481500.08      2534954.76     13480940.22
      2535001.64     13480354.25
#Sta/Elev= 30
  4415.6  181.51  4430.9  181.56  4441.1  181.22  4451.3  180.34  4524.6   179.4
  4603.9  177.13  4695.4  175.12  4756.4   173.9  4790.2  173.64  4827.6  173.39
  4846.3  173.82  4858.1  173.54  4878.5  174.38  4904.1  174.43  4949.7  171.51
    4968     169    4972     169  5012.1     169  5040.5     169  5048.1  170.57
  5053.1  170.92  5080.6  171.76  5110.8  173.62  5160.8  174.07  5190.9  173.38
    5201  173.74  5209.5  173.55  5391.6  174.62  5426.8  175.13  5572.9   175.6
#Mann= 8 ,-1 , 0
  4415.6     .12       0  4790.2     .05       0    4968     .05       0
    4972     .05       0  5012.1    .035       0  5040.5    .035       0
  5110.8     .12       0  5209.5    .035       0
Bank Sta=4968,5040.5
XS Rating Curve= 0 ,0
Exp/Cntr=0.3,0.1

Type RM Length L Ch R = 1 ,6749    ,190,190,190
BEGIN DESCRIPTION:
Mapping XS a3a0c93e
END DESCRIPTION:
XS GIS Cut Line= 3
      2534907.61     13481678.02      2535092.07     13480972.76
      2535183.22     13480282.64
#Sta/Elev= 30
  4287.6  185.26  4363.1  184.76  4383.8  183.81  4397.8  183.62  4417.8  183.64
  4695.6  175.22  4776.5  173.48  4828.2  173.14  4852.2  174.57  4862.4  174.77
  4921.2  172.75  4933.1  171.59  4941.9     169  5001.6     169  5005.6     169
  5012.8  171.09  5016.6  171.09  5024.4  172.05  5064.8  172.82  5086.3  172.79
  5157.1  172.98  5185.8  173.47  5198.1  173.15  5242.4   173.7    5327   174.1
  5417.8  175.35    5568  176.05  5629.6  176.08  5705.7  176.92  5712.7  176.95
#Mann= 11 ,-1 , 0
  4287.6     .05       0  4397.8     .12       0  4862.4     .05       0
  4941.9     .05       0  5001.6     .05       0  5005.6     .05       0
  5086.3     .12       0  5198.1    .035       0  5242.4     .12       0
    5568    .035       0  5705.7     .05       0
Bank Sta=4941.9,5005.6
XS Rating Curve= 0 ,0
Exp/Cntr=0.3,0.1

Type RM Length L Ch R = 1 ,6559    ,285,285,285
BEGIN DESCRIPTION:
Mapping XS 007748ff
END DESCRIPTION:
XS GIS Cut Line= 4
      2535089.89     13481803.97      2535217.94     13481133.35
      2535326.44     13480938.04      2535328.61      13480245.8
#Sta/Elev= 30
  4269.1  186.07  4318.4   186.8  4323.5  186.36  4339.3  186.95  4375.6  186.66
  4522.6  182.95  4551.8  181.64  4654.9  177.72  4769.3  174.26  4787.3  174.16
  4817.8  172.83  4838.2  172.77  4859.9  174.64  4899.2  172.51    4912  170.76
  4919.6     169  4928.6     169  4975.6     169  4979.6     169  4993.6     169
  5007.1  171.36  5015.4  171.92  5080.3  172.77  5161.8  174.22  5188.3  173.62
  5209.7  173.99  5418.3  176.48  5508.3  176.35  5866.6  177.81  5867.5  177.81
#Mann= 11 ,-1 , 0
  4269.1     .05       0  4551.8     .12       0  4769.3     .05       0
  4919.6     .05       0  4928.6     .05       0  4975.6     .05       0
  4979.6     .05       0  4993.6     .07       0  5080.3     .05       0
  5209.7     .12       0  5866.6     .05       0
Bank Sta=4919.6,4993.6
XS Rating Curve= 0 ,0
Exp/Cntr=0.3,0.1

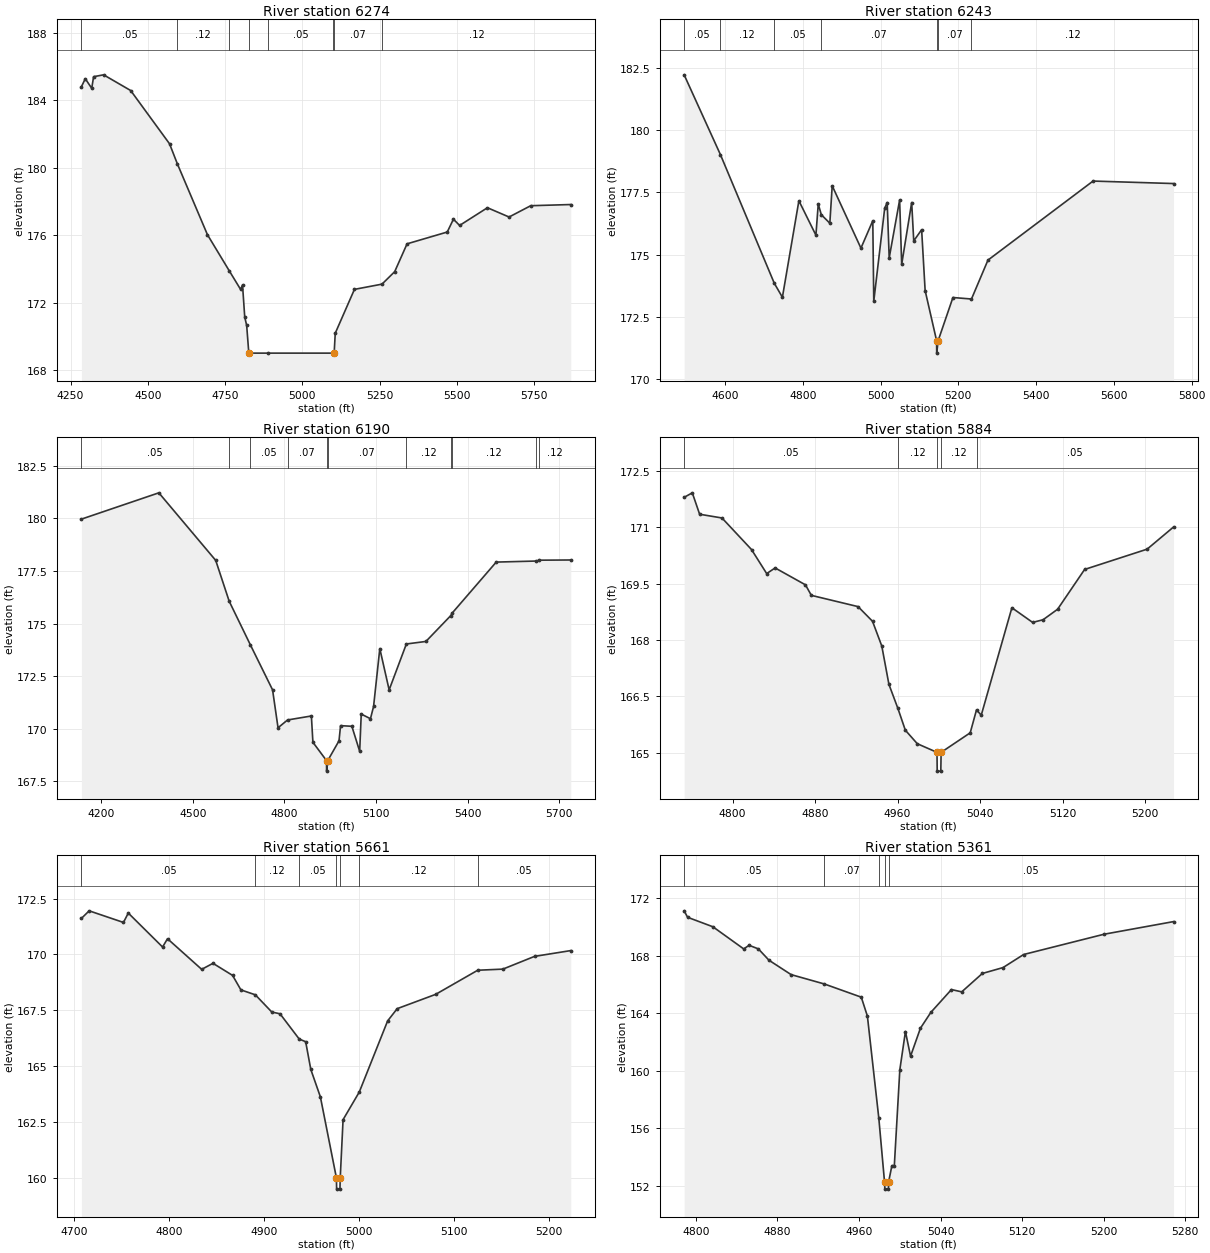
Type RM Length L Ch R = 1 ,6274    ,31,31,31
BEGIN DESCRIPTION:
Mapping XS c489cebb
END DESCRIPTION:
XS GIS Cut Line= 6
       2535167.9       13481807.       2535255.2     13481529.93
      2535460.16     13481237.67      2535469.64     13481173.15
      2535410.81     13480998.55      2535407.02     13480315.41
#Sta/Elev= 30
  4285.2  184.79  4297.8  185.27  4318.7   184.7  4324.7  185.39  4357.1   185.5
  4444.6  184.57  4570.4  181.41  4595.5  180.23    4693  176.02  4763.9  173.87
  4800.1  172.78  4806.5  173.04  4813.6  171.14  4819.9  170.64  4826.8     169
  4889.8     169  5098.9     169  5102.9     169  5106.4  170.18  5168.5  172.78
  5257.6  173.09  5298.7  173.83  5338.7  175.48  5468.7  176.18  5488.7  176.94
  5508.7  176.57  5598.7  177.62  5668.7  177.07  5738.7  177.74  5868.3  177.81
#Mann= 8 ,-1 , 0
  4285.2     .05       0  4595.5     .12       0  4763.9     .05       0
  4826.8     .05       0  4889.8     .05       0  5098.9     .05       0
  5102.9     .07       0  5257.6     .12       0
Bank Sta=4826.8,5102.9
XS Rating Curve= 0 ,0
Exp/Cntr=0.3,0.1

Type RM Length L Ch R = 1 ,6243    ,53,53,53
BEGIN DESCRIPTION:
Mapping XS 5e324a82
END DESCRIPTION:
XS GIS Cut Line= 6
      2535272.21     13481584.71      2535506.56     13481254.88
      2535500.05     13481174.58      2535458.82     13481046.54
      2535454.48     13480864.25       2535476.1     13480408.19
#Sta/Elev= 30
  4494.7  182.21    4588  179.01  4726.6  173.85  4747.4  173.29  4789.8  177.16
  4833.6  175.78  4839.6  177.03  4847.5   176.6  4869.4  176.26  4875.5  177.76
  4949.4  175.26  4979.9  176.36  4982.4  173.13  5010.5  176.86  5016.9  177.09
  5022.1  174.87  5048.9  177.19  5054.2  174.61  5079.9  177.09  5085.2  175.55
  5105.5     176  5114.5  173.56    5144  171.55  5144.3  171.05    5148  171.55
    5186  173.28  5233.7  173.22  5276.1  174.78  5546.4  177.95  5753.4  177.85
#Mann= 7 ,-1 , 0
  4494.7     .05       0    4588     .12       0  4726.6     .05       0
  4847.5     .07       0    5144     .05       0    5148     .07       0
  5233.7     .12       0
Bank Sta=5144,5148
XS Rating Curve= 0 ,0
Exp/Cntr=0.3,0.1

Type RM Length L Ch R = 1 ,6190    ,306,306,306
BEGIN DESCRIPTION:
Mapping XS 8b4f0cc8
END DESCRIPTION:
XS GIS Cut Line= 6
      2535296.07     13481944.95       2535526.1     13481365.55
      2535545.63     13481178.92      2535528.27     13481068.25
      2535508.73     13480970.59      2535539.12     13480391.14
#Sta/Elev= 30
  4134.8  179.96  4388.5  181.21  4574.8     178  4618.9  176.06  4687.9     174
    4761  171.85  4778.9  170.05  4810.1  170.42  4888.1  170.61  4893.1  169.36
  4937.7  168.49    4938  167.99  4941.7  168.49  4978.6  169.43  4983.7  170.15
  5020.7  170.12  5046.3  168.93  5051.4   170.7  5081.6  170.48  5091.8  171.06
  5112.2  173.81  5142.8  171.85  5199.2  174.03  5263.2  174.15  5344.8  175.38
  5349.4   175.5  5493.5  177.92    5625  177.97  5634.9  178.01  5737.7  178.02
#Mann= 11 ,-1 , 0
  4134.8     .05       0  4618.9     .12       0  4687.9     .05       0
  4810.1     .07       0  4937.7     .05       0  4941.7     .07       0
  5199.2     .12       0  5344.8     .07       0  5349.4     .12       0
    5625     .07       0  5634.9     .12       0
Bank Sta=4937.7,4941.7
XS Rating Curve= 0 ,0
Exp/Cntr=0.3,0.1

Type RM Length L Ch R = 1 ,5884    ,223,223,223
BEGIN DESCRIPTION:
Mapping XS 24437ad0
END DESCRIPTION:
XS GIS Cut Line= 3
       2535651.9     13481491.85      2535766.51     13481288.68
      2535735.32     13481049.57
#Sta/Elev= 30
  4753.1   171.8    4761  171.92  4768.1  171.35  4789.8  171.25  4818.4  170.41
  4833.1  169.77  4841.3  169.92  4870.7  169.47  4876.4  169.19  4921.7  168.89
  4935.7   168.5  4944.7  167.84  4951.6  166.82  4960.3  166.18  4967.5   165.6
  4979.1  165.24  4998.2  165.01  4998.4  164.51  5001.9  164.51  5002.2  165.01
  5030.4  165.53  5036.5  166.14  5041.1     166  5070.8  168.86  5090.9  168.47
    5101  168.54  5115.1  168.82  5141.3  169.88  5201.9  170.42  5227.5  171.01
#Mann= 5 ,-1 , 0
  4753.1     .05       0  4960.3     .12       0  4998.2     .05       0
  5002.2     .12       0  5036.5     .05       0
Bank Sta=4998.2,5002.2
XS Rating Curve= 0 ,0
Exp/Cntr=0.3,0.1

Type RM Length L Ch R = 1 ,5661    ,300,300,300
BEGIN DESCRIPTION:
Mapping XS 1fd942b7
END DESCRIPTION:
XS GIS Cut Line= 3
      2535938.39     13481559.49      2535995.67     13481330.35
        2535954.     13481054.27
#Sta/Elev= 30
  4707.8  171.61    4716  171.95  4752.1  171.43  4757.2  171.85  4793.3  170.33
  4798.5   170.7  4834.5  169.33  4846.4   169.6    4867  169.06  4875.8  168.41
    4891  168.19  4908.3  167.42    4917  167.34  4937.2  166.21    4944  166.09
  4949.4  164.85  4959.5  163.62  4976.4  159.99  4976.6  159.49  4980.1  159.49
  4980.4  159.99  4983.4   162.6  5000.5  163.84  5030.3  167.02  5040.4  167.57
  5080.9  168.21  5125.2  169.29  5151.7  169.34    5185  169.91  5223.2  170.17
#Mann= 7 ,-1 , 0
  4707.8     .05       0    4891     .12       0  4937.2     .05       0
  4976.4     .05       0  4980.4     .05       0  5000.5     .12       0
  5125.2     .05       0
Bank Sta=4976.4,4980.4
XS Rating Curve= 0 ,0
Exp/Cntr=0.3,0.1

Type RM Length L Ch R = 1 ,5361    ,182,182,182
BEGIN DESCRIPTION:
Mapping XS 3562f3b6
END DESCRIPTION:
XS GIS Cut Line= 3
      2536198.78      13481523.1      2536271.72     13481330.35
      2536230.08     13481059.72
#Sta/Elev= 30
  4788.6  171.13    4792  170.68  4816.8  170.02    4847  168.48  4852.3  168.73
  4861.4  168.48  4871.8  167.69  4893.5  166.69    4926  166.04  4962.3  165.12
  4968.3   163.8  4979.5  156.69  4985.1  152.26  4985.4  151.76  4988.9  151.76
  4989.1  152.26  4992.3  153.39  4994.7  153.39  5000.1  160.07  5005.6  162.73
  5010.6  161.01  5020.3  162.96  5030.5  164.06  5050.7  165.65  5060.8  165.49
    5081  166.77  5101.3  167.18  5121.5  168.09  5200.3   169.5  5268.5  170.38
#Mann= 5 ,-1 , 0
  4788.6     .05       0    4926     .07       0  4979.5     .05       0
  4985.1     .05       0  4989.1     .05       0
Bank Sta=4985.1,4989.1
XS Rating Curve= 0 ,0
Exp/Cntr=0.3,0.1

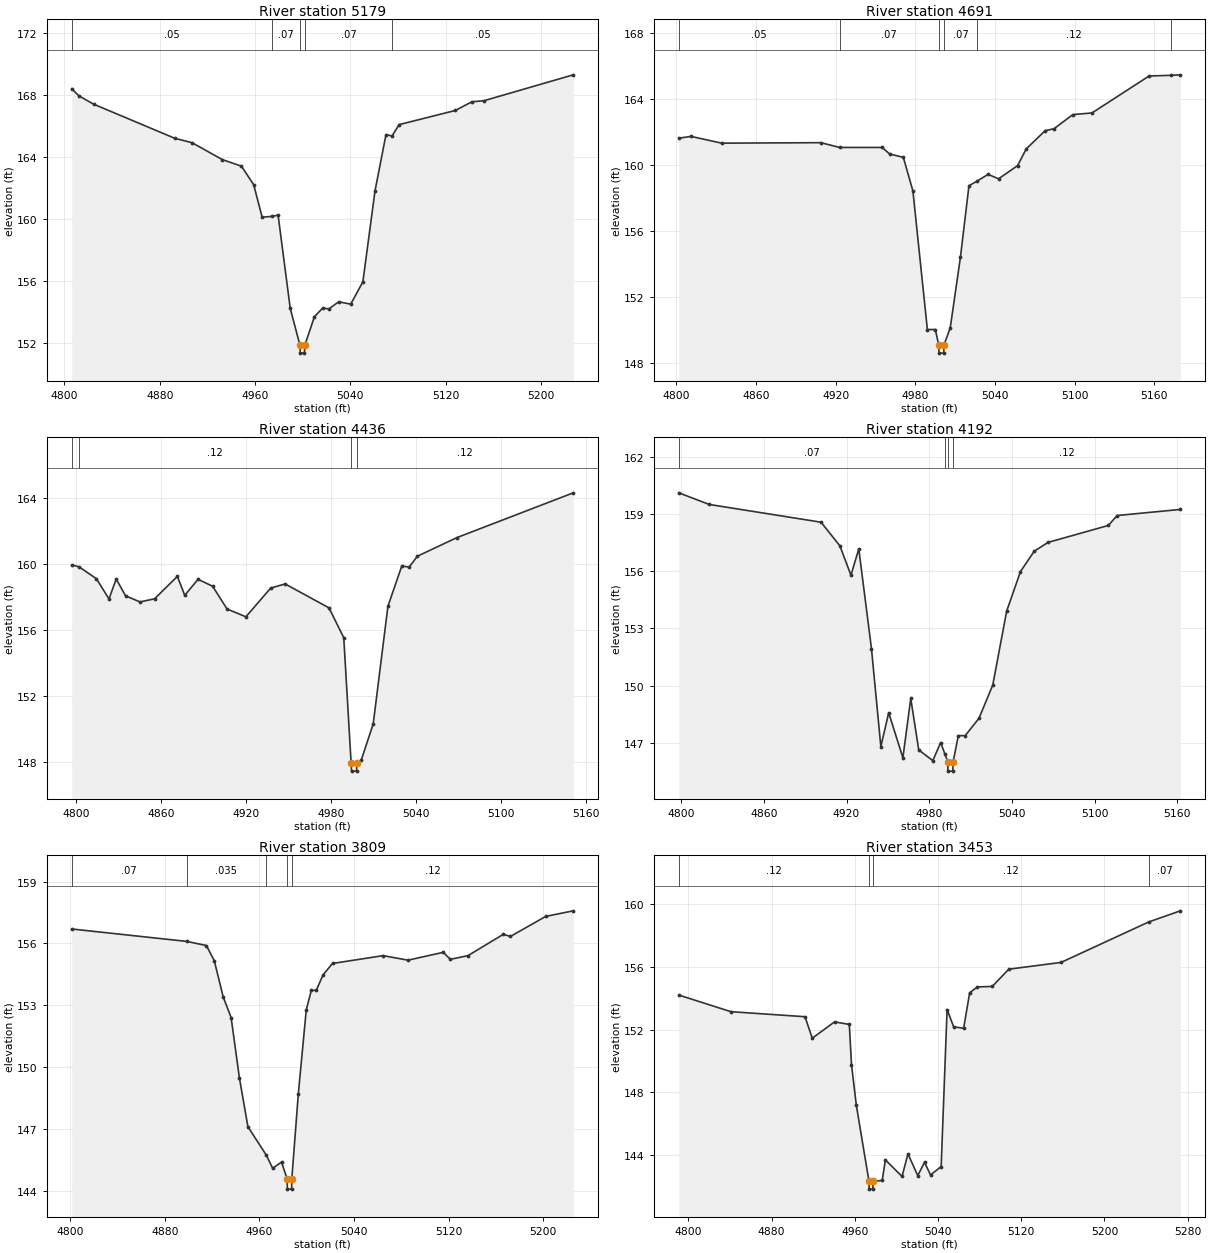
Type RM Length L Ch R = 1 ,5179    ,488,488,488
BEGIN DESCRIPTION:
Mapping XS d6405e10
END DESCRIPTION:
XS GIS Cut Line= 3
      2536417.54     13481512.67      2536459.22     13481356.39
      2536412.34      13481101.2
#Sta/Elev= 30
  4806.1  168.42  4812.2  167.96  4824.4  167.43  4892.5  165.23  4907.2  164.94
  4932.6  163.85  4948.6  163.43  4958.9  162.23    4966  160.14  4974.4  160.19
  4979.4  160.27  4989.6  154.25  4997.8  151.87    4998  151.37  5001.5  151.37
  5001.8  151.87  5009.9  153.72  5016.9  154.28    5022  154.22  5030.3  154.68
  5040.4  154.53  5050.6  155.97  5060.8  161.84    5070  165.46  5075.1  165.38
  5081.1  166.11  5128.2  167.02  5142.1  167.58  5152.3  167.65  5227.3  169.32
#Mann= 5 ,-1 , 0
  4806.1     .05       0  4974.4     .07       0  4997.8     .05       0
  5001.8     .07       0  5075.1     .05       0
Bank Sta=4997.8,5001.8
XS Rating Curve= 0 ,0
Exp/Cntr=0.3,0.1

Type RM Length L Ch R = 1 ,4691    ,255,255,255
BEGIN DESCRIPTION:
Mapping XS 5a7d6314
END DESCRIPTION:
XS GIS Cut Line= 3
      2536943.58     13481418.87      2536865.47     13481247.02
      2536745.67     13481101.18
#Sta/Elev= 30
    4802  161.61  4811.2  161.72  4834.3  161.31    4909  161.34    4923  161.05
  4955.1  161.05  4960.6  160.66    4971  160.45  4978.2  158.42  4989.1  150.02
  4995.1  150.02  4997.6  149.09  4997.9  148.59  5001.4  148.59  5001.6  149.09
  5006.3  150.11    5014  154.41  5020.4  158.73  5026.5  159.01  5034.8  159.42
  5042.7  159.15    5057  159.95  5063.5  160.96  5077.8  162.07  5084.3  162.18
  5098.6  163.04    5113  163.14    5156  165.38  5172.6  165.42  5179.5  165.45
#Mann= 6 ,-1 , 0
    4802     .05       0    4923     .07       0  4997.6     .05       0
  5001.6     .07       0  5026.5     .12       0  5172.6     .05       0
Bank Sta=4997.6,5001.6
XS Rating Curve= 0 ,0
Exp/Cntr=0.3,0.1

Type RM Length L Ch R = 1 ,4436    ,244,244,244
BEGIN DESCRIPTION:
Mapping XS c04e8ffe
END DESCRIPTION:
XS GIS Cut Line= 3
      2537063.38     13481372.02      2537099.84     13481210.56
      2537048.01     13481029.14
#Sta/Elev= 30
    4797  159.93  4802.1  159.82  4814.4   159.1  4823.3  157.87  4828.4  159.08
    4835  158.06  4845.2  157.69  4855.5  157.88  4871.6  159.24  4876.8  158.09
  4886.2  159.06  4896.5  158.64  4906.7  157.26    4920  156.79  4937.5  158.53
  4947.7  158.78  4978.7  157.33  4989.1  155.52  4994.3  147.94  4994.6  147.44
  4998.1  147.44  4998.3  147.94  5001.5  148.12  5009.9   150.3  5020.3  157.43
  5030.1  159.87  5035.3   159.8  5041.1  160.46  5069.1  161.59  5151.2   164.3
#Mann= 4 ,-1 , 0
    4797     .05       0  4802.1     .12       0  4994.3     .05       0
  4998.3     .12       0
Bank Sta=4994.3,4998.3
XS Rating Curve= 0 ,0
Exp/Cntr=0.3,0.1

Type RM Length L Ch R = 1 ,4192    ,383,383,383
BEGIN DESCRIPTION:
Mapping XS 848a28cb
END DESCRIPTION:
XS GIS Cut Line= 3
      2537177.96     13481497.02      2537276.92     13481319.93
      2537266.56     13481159.23
#Sta/Elev= 30
  4798.3  160.11  4820.4   159.5  4901.5  158.57  4915.2  157.33  4923.2  155.79
  4928.9  157.17  4938.1  151.94  4944.9  146.81  4950.6  148.58  4960.9  146.22
  4966.6  149.33  4972.4  146.63  4982.6  146.07  4988.3  147.02  4991.3  146.43
  4993.4  146.02  4993.6  145.52  4997.1  145.52  4997.4  146.02  5001.1  147.38
  5006.1  147.38  5016.1  148.29  5026.1  150.03  5036.2  153.91  5046.2  155.98
  5056.2  157.05  5066.2  157.51    5110   158.4  5116.3  158.92  5162.2  159.24
#Mann= 4 ,-1 , 0
  4798.3     .07       0  4991.3     .12       0  4993.4     .05       0
  4997.4     .12       0
Bank Sta=4993.4,4997.4
XS Rating Curve= 0 ,0
Exp/Cntr=0.3,0.1

Type RM Length L Ch R = 1 ,3809    ,356,356,356
BEGIN DESCRIPTION:
Mapping XS 471afc4d
END DESCRIPTION:
XS GIS Cut Line= 3
       2537740.5     13481439.75      2537589.42     13481304.31
      2537407.16     13481179.33
#Sta/Elev= 30
  4801.4   156.7  4898.4   156.1  4915.2   155.9  4921.9  155.16  4929.4  153.41
  4936.1  152.41  4943.1  149.49  4950.3  147.12  4965.8  145.75  4971.2  145.11
  4978.7  145.41  4983.4   144.6  4983.7   144.1  4987.2   144.1  4987.4   144.6
  4992.9  148.71  4999.6  152.78  5003.9  153.73  5008.1  153.73  5013.8  154.48
  5021.8  155.03  5064.6  155.41  5085.6  155.19  5115.4  155.57  5121.4  155.23
  5136.3  155.41  5166.1  156.44  5172.2  156.34    5202  157.31  5225.3  157.58
#Mann= 5 ,-1 , 0
  4801.4     .07       0  4898.4    .035       0  4965.8     .12       0
  4983.4     .05       0  4987.4     .12       0
Bank Sta=4983.4,4987.4
XS Rating Curve= 0 ,0
Exp/Cntr=0.3,0.1

Type RM Length L Ch R = 1 ,3453    ,260,260,260
BEGIN DESCRIPTION:
Mapping XS e12f9129
END DESCRIPTION:
XS GIS Cut Line= 3
      2537870.67     13481210.55      2537724.84     13481080.35
      2537475.04     13480939.84
#Sta/Elev= 30
  4790.8  154.21    4841  153.15  4912.1  152.83  4919.1  151.46  4940.5   152.5
  4954.7  152.34  4956.8  149.78  4961.4  147.21  4973.6  142.34  4973.8  141.84
  4977.3  141.84  4977.6  142.34  4986.3  142.39  4989.4   143.7  5005.4  142.65
  5011.1  144.09  5020.5   142.7    5027  143.55  5032.8  142.74    5043  143.28
  5048.7  153.29    5055  152.19  5064.6  152.09  5070.4  154.36  5077.9  154.73
  5092.1  154.76    5108  155.86  5158.2  156.29  5242.5  158.87  5272.9  159.58
#Mann= 4 ,-1 , 0
  4790.8     .12       0  4973.6     .05       0  4977.6     .12       0
  5242.5     .07       0
Bank Sta=4973.6,4977.6
XS Rating Curve= 0 ,0
Exp/Cntr=0.3,0.1

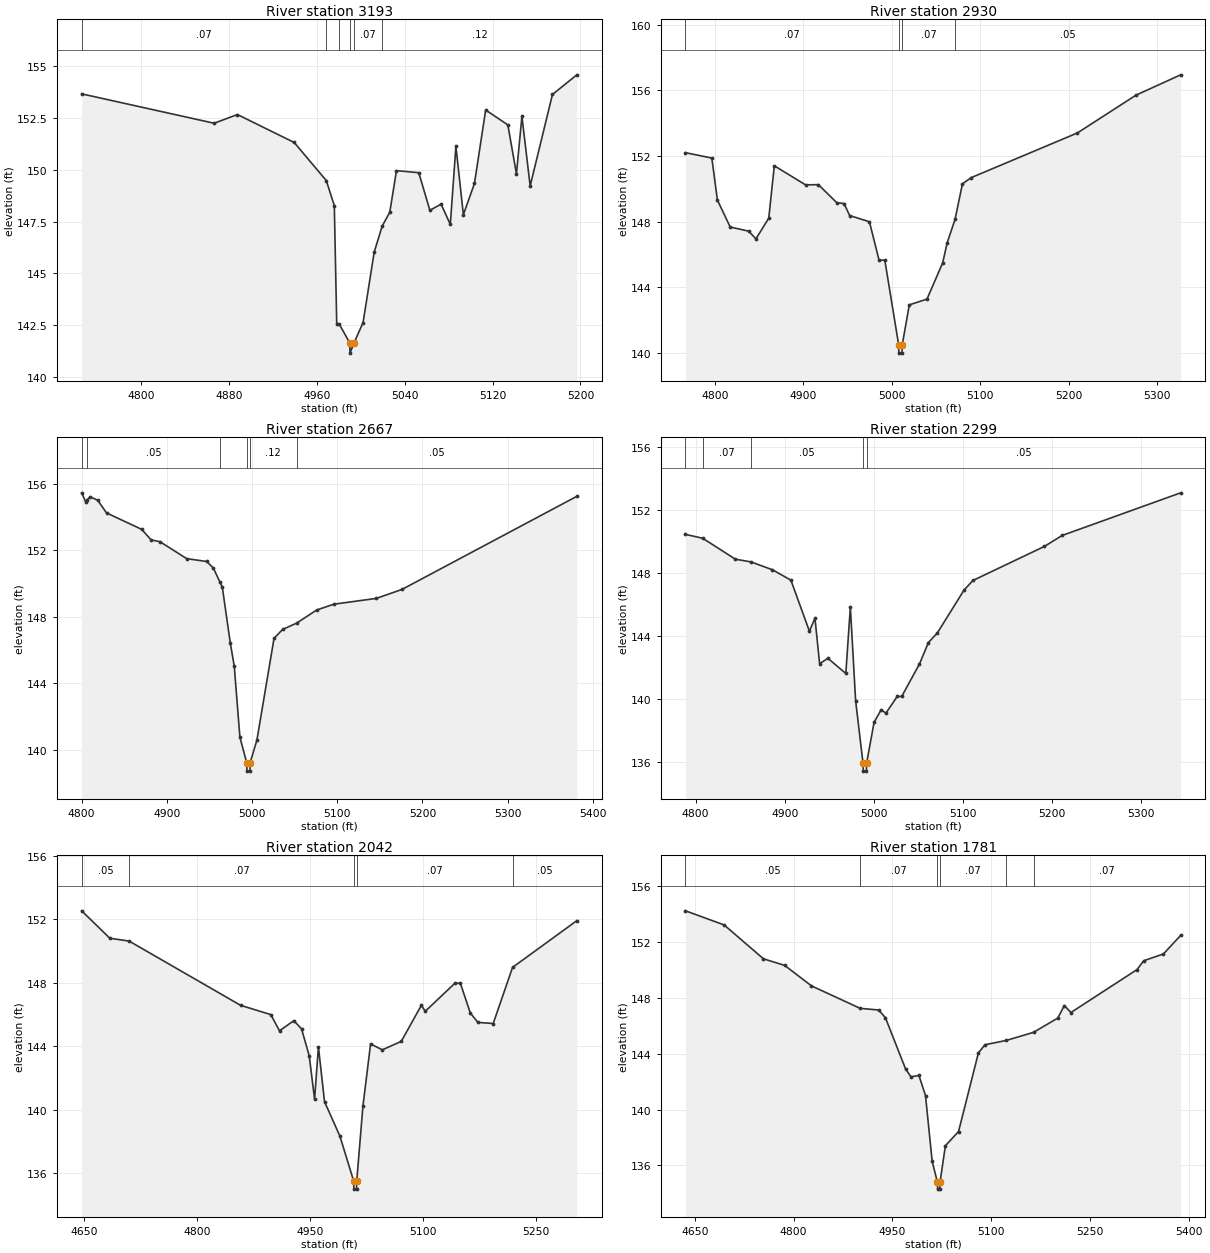
Type RM Length L Ch R = 1 ,3193    ,263,263,263
BEGIN DESCRIPTION:
Mapping XS afbeeafc
END DESCRIPTION:
XS GIS Cut Line= 3
      2538094.67     13481012.67      2537896.72     13480887.64
      2537683.14     13480851.18
#Sta/Elev= 30
  4745.9  153.67  4866.5  152.25  4887.7  152.67  4939.4  151.32  4968.6  149.48
  4975.9  148.27  4978.1  142.56  4980.2  142.56  4989.9  141.64  4990.2  141.14
  4993.9  141.64  5002.1  142.62  5012.2  146.02  5019.5  147.28  5026.4  147.95
  5032.5  149.96  5052.8  149.86  5062.9  148.04  5073.1  148.34  5081.5  147.36
  5086.6  151.13  5093.4  147.83  5103.5  149.34  5113.7  152.89  5133.9  152.17
  5141.7   149.8  5146.7  152.58  5154.2  149.22  5174.5  153.64  5196.7  154.59
#Mann= 6 ,-1 , 0
  4745.9     .07       0  4968.6     .12       0  4980.2     .07       0
  4989.9     .05       0  4993.9     .07       0  5019.5     .12       0
Bank Sta=4989.9,4993.9
XS Rating Curve= 0 ,0
Exp/Cntr=0.3,0.1

Type RM Length L Ch R = 1 ,2930    ,263,263,263
BEGIN DESCRIPTION:
Mapping XS 1c39a2a4
END DESCRIPTION:
XS GIS Cut Line= 3
      2538120.66     13480830.33      2537985.26     13480653.27
      2537648.32     13480637.72
#Sta/Elev= 30
  4766.5   152.2  4796.3  151.87  4802.6  149.31  4817.1  147.67  4837.9  147.42
  4846.2  146.95  4860.7  148.21    4867   151.4  4902.3  150.24  4916.9  150.25
  4937.7  149.15  4945.9   149.1  4952.2  148.37  4974.6  147.99  4985.5  145.65
    4992  145.65  5007.7  140.49  5007.9  139.99  5011.4  139.99  5011.7  140.49
  5019.7  142.93  5039.7  143.28  5057.5  145.49  5062.5   146.7  5071.5  148.14
  5079.8   150.3  5089.8  150.68  5209.9   153.4  5276.1   155.7  5326.7  156.94
#Mann= 4 ,-1 , 0
  4766.5     .07       0  5007.7     .05       0  5011.7     .07       0
  5071.5     .05       0
Bank Sta=5007.7,5011.7
XS Rating Curve= 0 ,0
Exp/Cntr=0.3,0.1

Type RM Length L Ch R = 1 ,2667    ,368,368,368
BEGIN DESCRIPTION:
Mapping XS e655fc8a
END DESCRIPTION:
XS GIS Cut Line= 3
      2538302.99     13480491.82      2538131.09     13480439.73
      2537730.04     13480418.89
#Sta/Elev= 30
  4800.1  155.45  4804.8  154.91  4806.6  155.02    4810  155.22  4818.9     155
  4829.3  154.24  4870.6  153.25  4881.6  152.62    4892  152.51  4923.4  151.49
  4946.9  151.32  4954.7  150.92  4962.1  150.11  4965.2  149.77  4974.6   146.4
  4979.2  145.02  4985.8  140.76  4993.8  139.21  4994.1  138.71  4997.6  138.71
  4997.8  139.21  5005.8  140.58  5025.9   146.7  5035.9  147.23  5052.3  147.61
  5075.9   148.4    5096  148.75    5146   149.1  5176.1  149.64  5381.3  155.24
#Mann= 6 ,-1 , 0
  4800.1     .07       0  4806.6     .05       0  4962.1     .12       0
  4993.8     .05       0  4997.8     .12       0  5052.3     .05       0
Bank Sta=4993.8,4997.8
XS Rating Curve= 0 ,0
Exp/Cntr=0.3,0.1

Type RM Length L Ch R = 1 ,2299    ,257,257,257
BEGIN DESCRIPTION:
Mapping XS 0f4eaed9
END DESCRIPTION:
XS GIS Cut Line= 3
      2538329.05     13480158.49      2538099.84     13480095.98
      2537782.13     13480095.98
#Sta/Elev= 30
  4788.7  150.45  4808.1   150.2  4844.7  148.87  4862.1   148.7  4886.2   148.2
  4906.9  147.54  4927.7  144.29  4933.9  145.12  4939.1  142.23  4948.4  142.57
  4968.5  141.61  4973.6  145.83  4979.5  139.87  4987.8   135.9  4988.1   135.4
  4991.6   135.4  4991.8   135.9  5000.2   138.5  5008.2  139.31  5013.4  139.08
  5026.2  140.15  5031.2  140.15  5051.1  142.21  5061.1  143.57  5071.1  144.18
  5101.1  146.91  5111.1  147.52  5191.1  149.68  5211.1  150.38    5344  153.09
#Mann= 5 ,-1 , 0
  4788.7     .12       0  4808.1     .07       0  4862.1     .05       0
  4987.8     .05       0  4991.8     .05       0
Bank Sta=4987.8,4991.8
XS Rating Curve= 0 ,0
Exp/Cntr=0.3,0.1

Type RM Length L Ch R = 1 ,2042    ,261,261,261
BEGIN DESCRIPTION:
Mapping XS d1860811
END DESCRIPTION:
XS GIS Cut Line= 3
      2538521.74     13479929.31      2538172.76      13479861.6
      2537875.92     13479918.89
#Sta/Elev= 30
  4647.1  152.54  4684.5  150.81  4710.2  150.63  4858.1  146.58  4898.4  145.99
  4909.9  144.97    4929  145.61  4939.2  145.09  4949.4  143.39  4956.5  140.65
  4961.6  143.96  4969.7   140.5  4990.1  138.33  5008.5  135.48  5008.7  134.98
  5012.2  134.98  5012.5  135.48  5020.7  140.21  5030.9  144.14  5046.5  143.77
  5071.6   144.3  5098.4  146.58  5103.5   146.2  5142.9  147.97  5150.2  147.97
  5163.3   146.1  5173.4   145.5  5193.8  145.43  5219.5  148.97  5304.9  151.92
#Mann= 5 ,-1 , 0
  4647.1     .05       0  4710.2     .07       0  5008.5     .05       0
  5012.5     .07       0  5219.5     .05       0
Bank Sta=5008.5,5012.5
XS Rating Curve= 0 ,0
Exp/Cntr=0.3,0.1

Type RM Length L Ch R = 1 ,1781    ,345,345,345
BEGIN DESCRIPTION:
Mapping XS 8bccec23
END DESCRIPTION:
XS GIS Cut Line= 3
      2538582.51     13479684.52      2538243.94     13479615.07
      2537839.03     13479651.88
#Sta/Elev= 30
  4635.7  154.25  4694.4  153.24  4754.1  150.81  4786.3  150.34  4827.1  148.87
    4901  147.26  4929.2  147.14  4939.4  146.59    4970  142.92  4978.2  142.35
  4990.3  142.45  5000.3  141.01  5010.4   136.3  5018.4   134.8  5018.7   134.3
  5022.2   134.3  5022.4   134.8  5030.5  137.41  5050.5  138.43  5080.7  144.07
  5090.7  144.65  5123.1  144.96  5164.4  145.54  5201.2  146.56  5211.2  147.46
  5221.2  146.96  5321.7  150.04  5331.7  150.67  5361.8  151.16  5387.9  152.49
#Mann= 6 ,-1 , 0
  4635.7     .05       0    4901     .07       0  5018.4     .05       0
  5022.4     .07       0  5123.1     .05       0  5164.4     .07       0
Bank Sta=5018.4,5022.4
XS Rating Curve= 0 ,0
Exp/Cntr=0.3,0.1

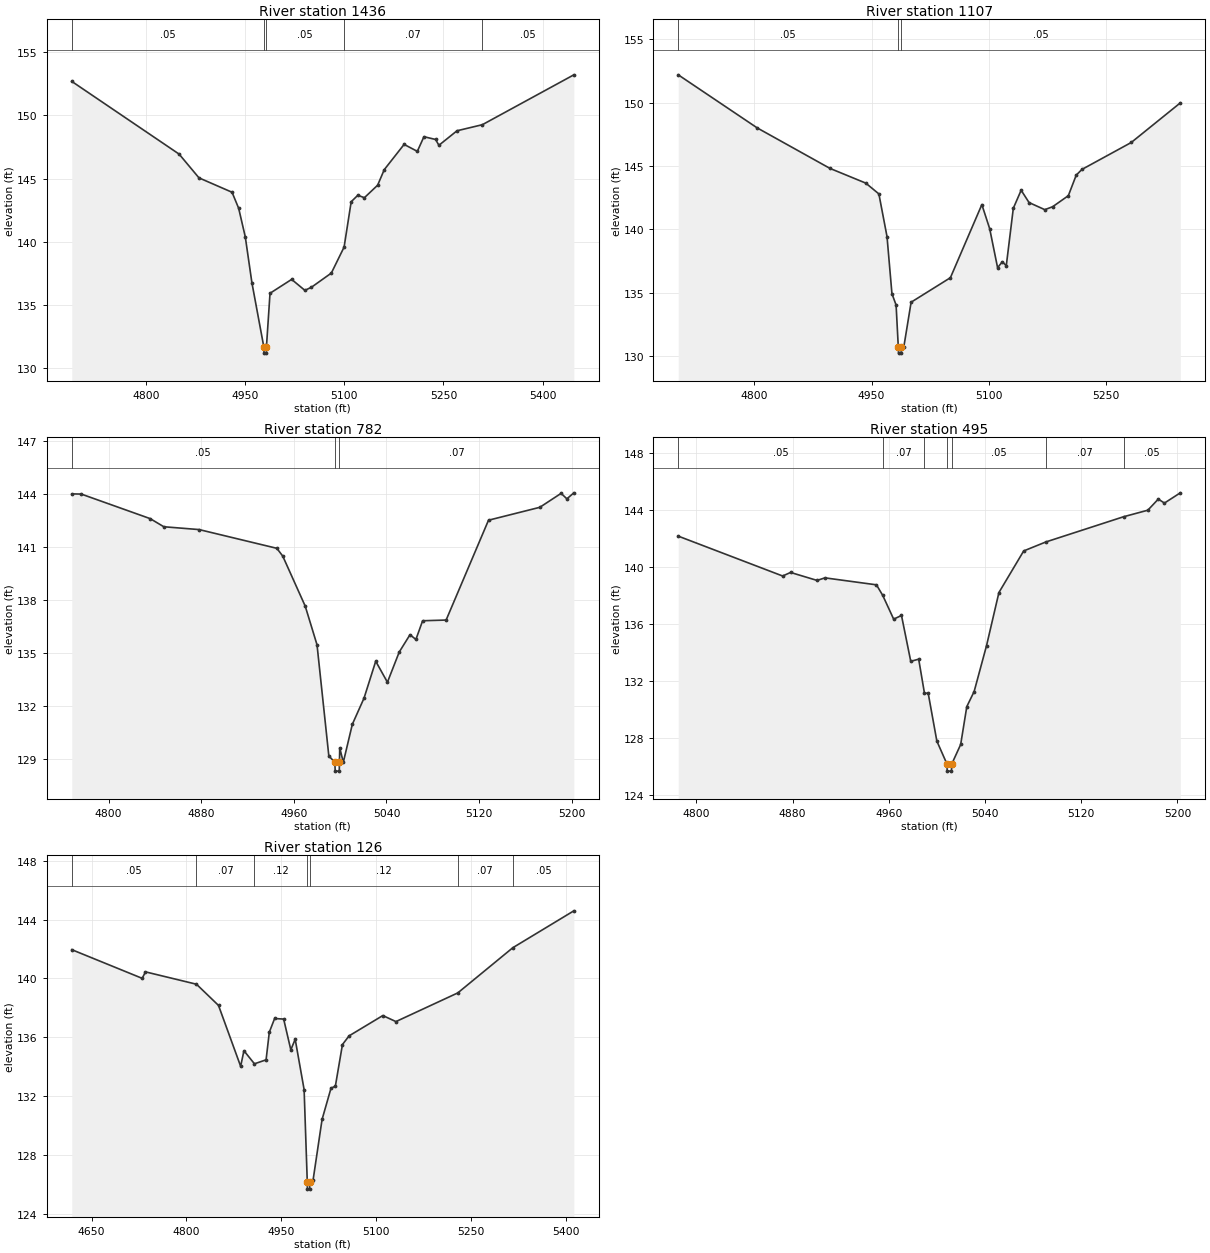
Type RM Length L Ch R = 1 ,1436    ,329,329,329
BEGIN DESCRIPTION:
Mapping XS 037aed0f
END DESCRIPTION:
XS GIS Cut Line= 3
      2538537.31     13479309.52      2538235.26     13479304.31
      2537778.47     13479314.69
#Sta/Elev= 30
  4688.1   152.7  4850.4  146.94  4880.4  145.06  4930.4  143.92  4940.4  142.65
  4950.4  140.39  4960.4  136.76  4978.4  131.68  4978.7  131.18  4982.2  131.18
  4982.4  131.68  4987.8  135.92  5020.5  137.02  5040.5  136.15  5050.5   136.4
  5080.5  137.52  5099.8  139.58  5110.5  143.17  5120.5  143.68  5130.5  143.49
  5150.5  144.48  5160.5  145.71  5190.5  147.71  5210.5  147.16  5220.5  148.32
  5238.1   148.1  5243.1  147.64  5270.5  148.79  5308.8  149.27  5447.1  153.22
#Mann= 5 ,-1 , 0
  4688.1     .05       0  4978.4     .05       0  4982.4     .05       0
  5099.8     .07       0  5308.8     .05       0
Bank Sta=4978.4,4982.4
XS Rating Curve= 0 ,0
Exp/Cntr=0.3,0.1

Type RM Length L Ch R = 1 ,1107    ,325,325,325
BEGIN DESCRIPTION:
Mapping XS 2fad9608
END DESCRIPTION:
XS GIS Cut Line= 3
      2538561.04     13479107.12      2538288.47     13479027.26
      2537932.59     13479061.98
#Sta/Elev= 30
  4702.9  152.18  4803.8     148  4896.8  144.81  4942.6  143.65  4959.3   142.8
  4969.7  139.44    4976  134.94  4981.3  134.05  4984.1  130.76  4984.4  130.26
  4987.9  130.26  4988.1  130.76  4991.2  130.76  5000.5  134.27  5050.7   136.2
  5090.9  141.96  5100.9  140.06    5111  136.99  5117.1  137.46  5122.1  137.14
  5131.1  141.67  5141.1  143.09  5151.2  142.12  5171.3  141.56  5181.3  141.79
  5201.4  142.66  5211.5  144.28  5218.8  144.73  5281.8  146.85  5344.5  149.97
#Mann= 3 ,-1 , 0
  4702.9     .05       0  4984.1     .05       0  4988.1     .05       0
Bank Sta=4984.1,4988.1
XS Rating Curve= 0 ,0
Exp/Cntr=0.3,0.1

Type RM Length L Ch R = 1 ,782     ,287,287,287
BEGIN DESCRIPTION:
Mapping XS 8149fede
END DESCRIPTION:
XS GIS Cut Line= 3
      2538553.05     13478763.37      2538325.62     13478719.96
      2538125.98     13478751.21
#Sta/Elev= 30
  4768.2  144.01  4776.4     144  4835.9  142.61  4847.7  142.15  4878.2  141.99
  4945.3  140.93  4950.4  140.49  4969.8  137.66    4980  135.47  4990.2  129.18
  4995.4  128.82  4995.7  128.32  4999.2  128.32  4999.4  128.82  4999.6  129.64
  5002.7  128.82  5010.5  130.97  5020.6  132.45  5030.7  134.54  5040.8  133.35
    5051  135.06  5060.3  136.04  5065.4  135.77  5071.2  136.83  5091.5  136.87
  5128.1  142.52  5172.4  143.25  5190.8  144.04  5195.8  143.73  5201.8  144.07
#Mann= 3 ,-1 , 0
  4768.2     .05       0  4995.4     .05       0  4999.4     .07       0
Bank Sta=4995.4,4999.4
XS Rating Curve= 0 ,0
Exp/Cntr=0.3,0.1

Type RM Length L Ch R = 1 ,495     ,369,369,369
BEGIN DESCRIPTION:
Mapping XS 4f5b2c36
END DESCRIPTION:
XS GIS Cut Line= 3
      2538587.79     13478664.43      2538454.09     13478508.16
      2538248.78      13478456.4
#Sta/Elev= 30
    4785  142.15  4871.8  139.35  4878.4   139.6  4900.4  139.04    4907  139.22
  4949.8  138.73    4955  137.99  4964.1  136.32  4970.6  136.58  4978.3  133.36
  4984.9  133.51  4989.7  131.12  4992.8  131.12    5000  127.76  5008.4  126.15
  5008.6  125.65  5012.1  125.65  5012.4  126.15  5019.8  127.52  5024.9  130.18
    5031  131.24  5041.3  134.46  5051.6  138.19  5072.2  141.11  5090.6  141.74
  5155.2  143.51  5175.4  143.97  5184.1  144.75  5189.2  144.47  5202.4  145.19
#Mann= 7 ,-1 , 0
    4785     .05       0    4955     .07       0  4989.7     .05       0
  5008.4     .05       0  5012.4     .05       0  5090.6     .07       0
  5155.2     .05       0
Bank Sta=5008.4,5012.4
XS Rating Curve= 0 ,0
Exp/Cntr=0.3,0.1

Type RM Length L Ch R = 1 ,126     ,0,0,0
BEGIN DESCRIPTION:
TRIB 1 TO GOBBLER CREEK 1.0
END DESCRIPTION:
XS GIS Cut Line= 4
      2538620.76     13478634.91      2538705.86     13478314.12
      2538634.24     13478246.84      2538283.91     13478343.24
#Sta/Elev= 30
  4618.8  141.95  4730.1     140  4735.3  140.44  4815.9   139.6  4850.7  138.16
  4885.7  134.02  4890.9  135.08  4907.5  134.19  4925.9  134.46    4931  136.34
  4939.4  137.27  4953.7  137.23    4965  135.14  4971.9  135.86    4986  132.44
    4991  126.17  4991.3  125.67  4994.8  125.67    4995  126.17  5000.2  126.29
  5014.4  130.41  5028.5  132.53  5035.4  132.67  5046.6   135.5  5057.1  136.09
  5110.4  137.47  5131.1  137.06  5228.9  139.01  5315.8  142.08  5412.3  144.59
#Mann= 7 ,-1 , 0
  4618.8     .05       0  4815.9     .07       0  4907.5     .12       0
    4991     .05       0    4995     .12       0  5228.9     .07       0
  5315.8     .05       0
Bank Sta=4991,4995
XS Rating Curve= 0 ,0
Exp/Cntr=0.3,0.1

Chan Stop Cuts=-1
Use User Specified Reach Order=0
Composite Channel Slope=5