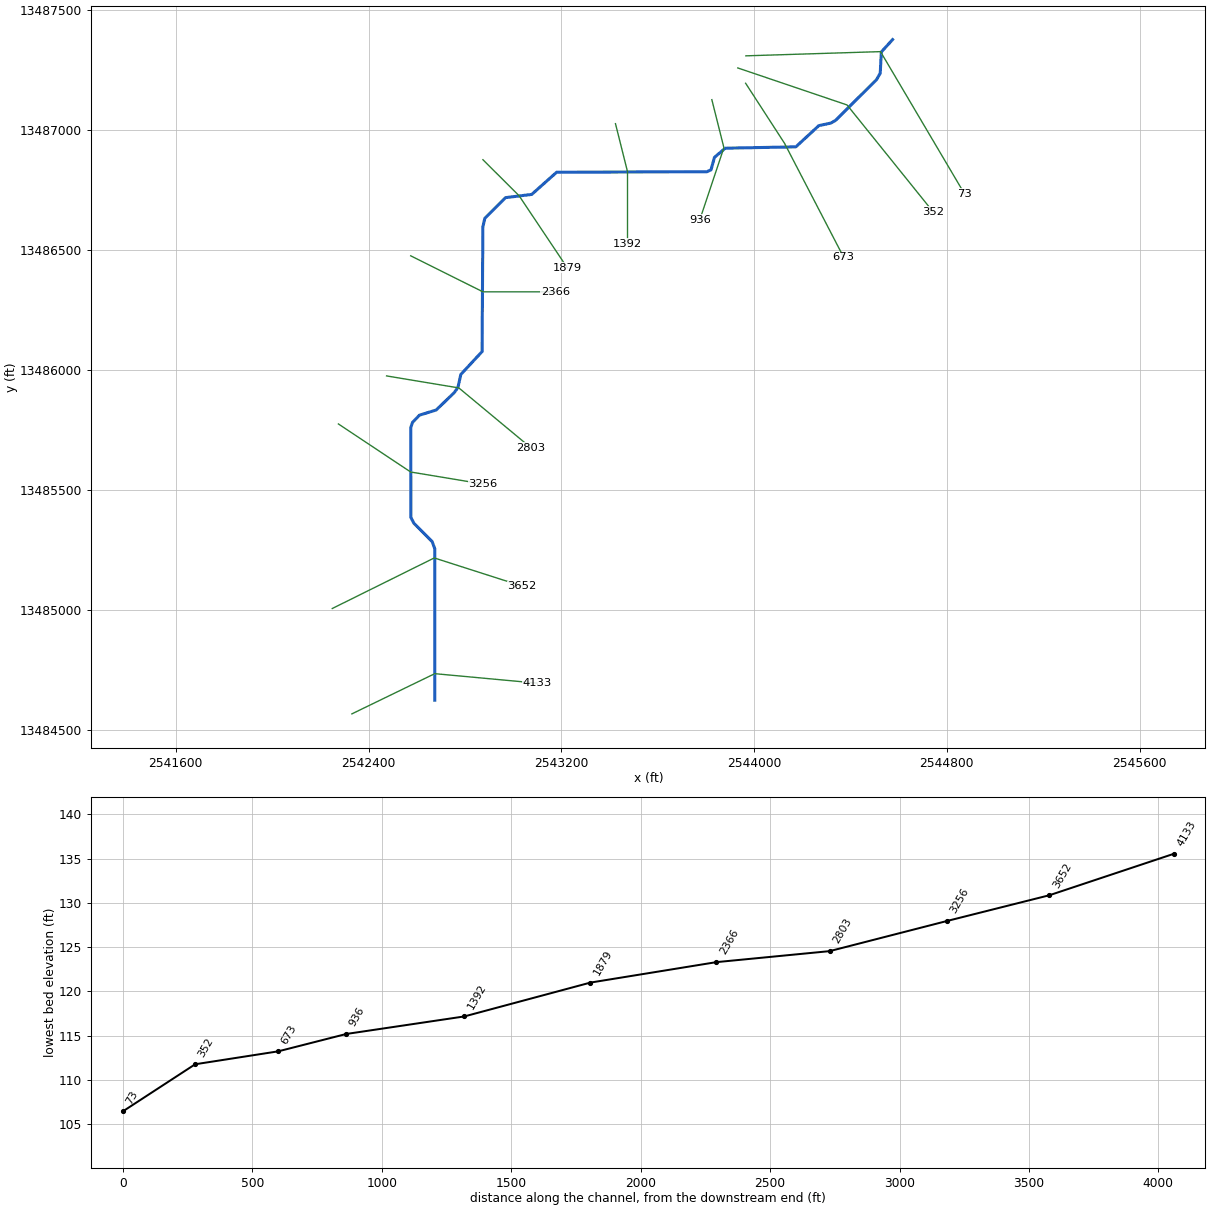
--- TRIB 1 TO HOG THIEF CREEK.prj (project) ---

Proj Title=TRIB 1 TO HOG THIEF CREEK Base Level Engineering
Current Plan=p01
Default Exp/Contr=0.3,0.1
English Units
Geom File=g01
Flow File=f01
Plan File=p01
Y Axis Title=Elevation
X Axis Title(PF)=Main Channel Distance
X Axis Title(XS)=Station
BEGIN DESCRIPTION:
TRIB 1 TO HOG THIEF CREEK
END DESCRIPTION:
DSS Export Rating Curves= 0
DSS Export Rating Curve Sorted= 0
DSS Export Volume Flow Curves= 0
DXF OffsetX= 0
DXF OffsetY= 0
DXF ScaleX= 1
DXF ScaleY= 10

--- TRIB 1 TO HOG THIEF CREEK.p01 (plan) ---

Plan Title=Multiple Run
Short Identifier=Multiple
Geom File=g01
Flow File=f01
Subcritical Flow
K Sum by GR= 0
Std Step Tol= 0.01
Critical Tol= 0.01
Num of Std Step Trials= 20
Max Error Tol= 0.3
Flow Tol Ratio= 0.001
Split Flow NTrial= 30
Split Flow Tol= 0.02
Split Flow Ratio= 0.02
Log Output Level= 0
Friction Slope Method= 1
Unsteady Friction Slope Method= 2
Unsteady Bridges Friction Slope Method= 1
Parabolic Critical Depth
Global Vel Dist=  1 , 1 , 1
Global Log Level= 0
CheckData=True
Encroach Param= -1, 0, 0, 0
BEGIN DESCRIPTION:
Multiple Run
END DESCRIPTION:

--- TRIB 1 TO HOG THIEF CREEK.f01 (steady flow) ---

Flow Title=Multiple
Number of Profiles=7
Profile Names=10-year,25-year,50-year,1pct_min,100-year,1pct_plu,500-year
River Rch & RM= TRIB 1 TO HOG TH,Reach-1,4133
     395     608     792     500     999    1992    1566
River Rch & RM= TRIB 1 TO HOG TH,Reach-1,3256
     720    1153    1542     998    1991    3973    3281
Boundary for River Rch & Prof#=TRIB 1 TO HOG TH,Reach-1,1
Up Type=0
Dn Type=3
Dn Slope=0.005
Boundary for River Rch & Prof#=TRIB 1 TO HOG TH,Reach-1,2
Up Type=0
Dn Type=3
Dn Slope=0.005
Boundary for River Rch & Prof#=TRIB 1 TO HOG TH,Reach-1,3
Up Type=0
Dn Type=3
Dn Slope=0.005
Boundary for River Rch & Prof#=TRIB 1 TO HOG TH,Reach-1,4
Up Type=0
Dn Type=3
Dn Slope=0.005
Boundary for River Rch & Prof#=TRIB 1 TO HOG TH,Reach-1,5
Up Type=0
Dn Type=3
Dn Slope=0.005
Boundary for River Rch & Prof#=TRIB 1 TO HOG TH,Reach-1,6
Up Type=0
Dn Type=3
Dn Slope=0.005
Boundary for River Rch & Prof#=TRIB 1 TO HOG TH,Reach-1,7
Up Type=0
Dn Type=3
Dn Slope=0.005

--- TRIB 1 TO HOG THIEF CREEK.g01 (geometry) ---

Geom Title=Existing Conditions
Program Version=4.10

River Reach=TRIB 1 TO HOG TH,Reach-1
Reach XY= 30
        2542675.       13484625.      2542675.04     13485255.02
       2542664.5     13485284.79       2542588.4     13485361.69
      2542576.06     13485385.44      2542575.33     13485759.97
      2542582.69     13485781.48      2542611.37     13485811.54
      2542681.04     13485833.16      2542755.23     13485904.87
      2542771.03     13485926.64      2542783.18     13485981.04
      2542871.45     13486076.47      2542874.57     13486595.18
       2542882.8     13486631.21      2542968.81     13486717.14
      2543077.42     13486730.54      2543180.86     13486822.93
       2543804.8     13486825.06       2543821.6     13486833.15
      2543835.75     13486884.75      2543880.68     13486922.99
      2544173.53     13486928.55      2544268.96     13487016.82
      2544318.95     13487027.53      2544338.21     13487038.63
      2544508.55     13487208.24      2544523.88     13487235.46
      2544528.39     13487323.59        2544575.       13487375.

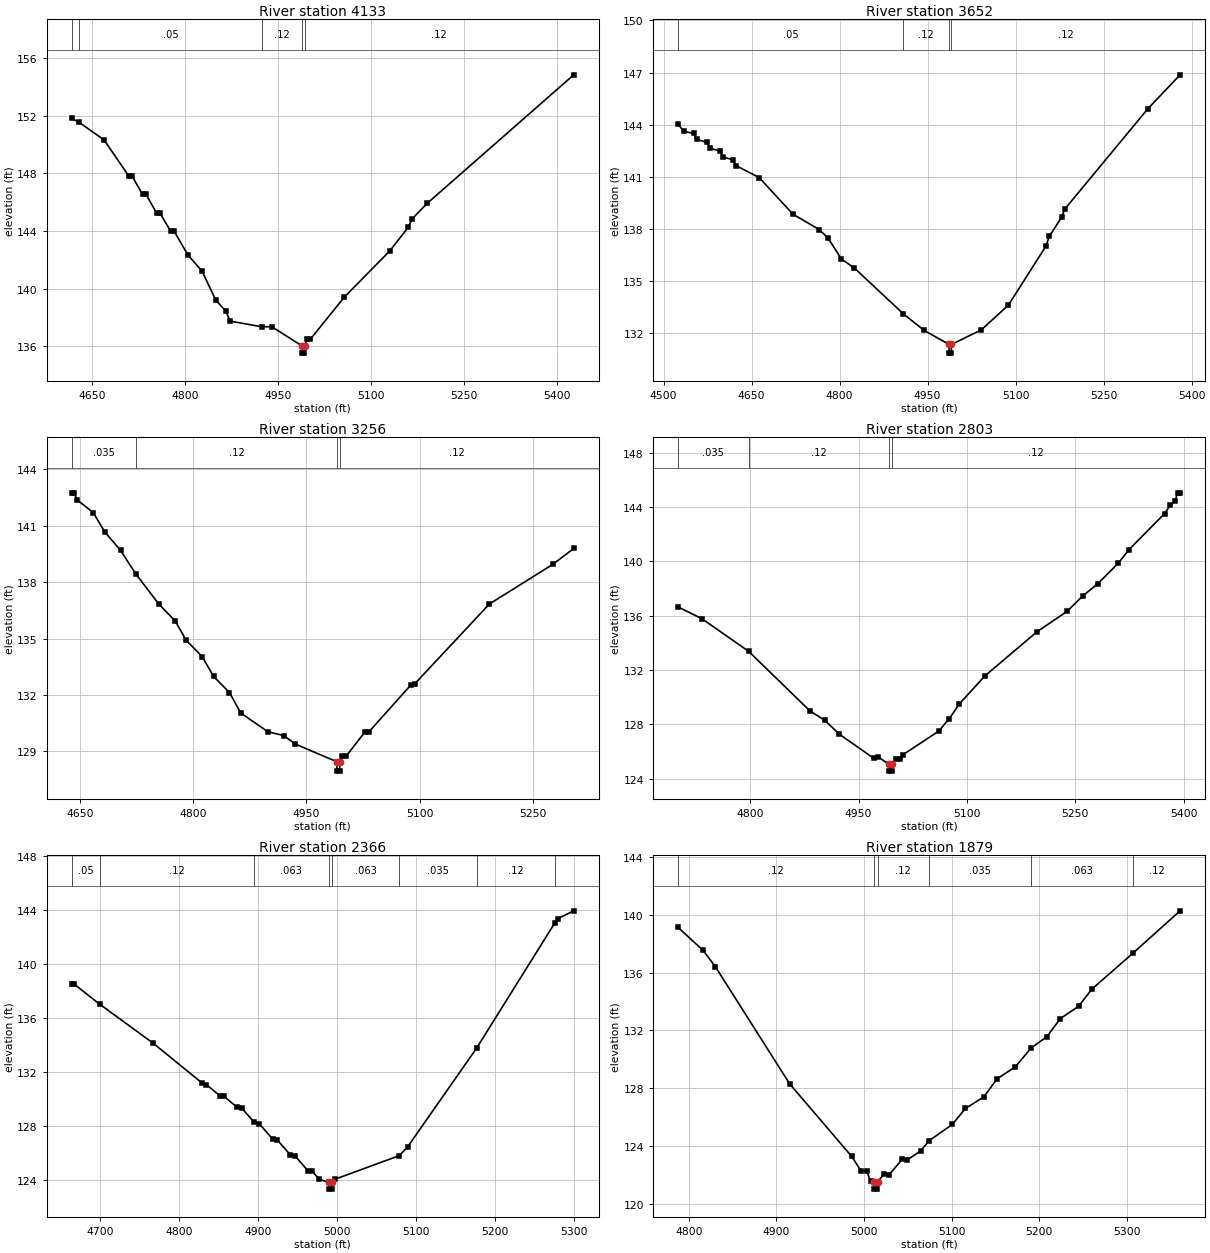
Type RM Length L Ch R = 1 ,4133    ,481,481,481
BEGIN DESCRIPTION:
TRIB 1 TO HOG THIEF CREEK 8.0
END DESCRIPTION:
XS GIS Cut Line= 3
      2542331.14     13484568.17        2542675.     13484735.47
      2543100.37     13484695.93
#Sta/Elev= 30
  4617.6  151.81  4629.7  151.53  4669.7  150.32  4709.3  147.83  4714.8  147.81
  4731.8  146.54  4737.4  146.54  4754.4  145.25  4759.9  145.25  4776.9     144
  4782.5     144    4805  142.34  4827.6  141.23  4850.1   139.2  4866.5  138.43
  4872.7  137.76  4923.7  137.37  4940.3  137.37    4989  136.04  4989.2  135.54
  4992.7  135.54    4993  136.04  4997.2  136.51  5002.5  136.51  5057.2  139.42
  5130.6  142.63  5160.7  144.28  5166.4  144.84  5190.8  145.92  5427.2  154.83
#Mann= 5 ,-1 , 0
  4617.6     .12       0  4629.7     .05       0  4923.7     .12       0
    4989     .05       0    4993     .12       0
Bank Sta=4989,4993
XS Rating Curve= 0 ,0
Exp/Cntr=0.3,0.1

Type RM Length L Ch R = 1 ,3652    ,396,396,396
BEGIN DESCRIPTION:
Mapping XS dfb14eb2
END DESCRIPTION:
XS GIS Cut Line= 3
      2542249.65     13485006.73      2542672.85     13485217.24
      2543037.41     13485100.06
#Sta/Elev= 30
  4524.7  144.03  4534.2  143.62    4551   143.5  4556.6  143.16  4573.4  142.99
  4578.9  142.65  4595.8  142.49  4601.3  142.14  4618.2  141.98  4623.7  141.64
  4662.9  140.96  4720.5  138.85  4765.2  137.97  4780.5  137.47  4802.9  136.28
  4825.3  135.75  4908.3  133.13  4943.9  132.17  4986.6  131.36  4986.8  130.86
  4990.3  130.86  4990.6  131.36  5041.6   132.2  5087.6  133.62  5151.8  137.02
  5157.2  137.57  5178.2  138.67  5183.9  139.15  5325.2  144.91  5380.3  146.87
#Mann= 4 ,-1 , 0
  4524.7     .05       0  4908.3     .12       0  4986.6     .05       0
  4990.6     .12       0
Bank Sta=4986.6,4990.6
XS Rating Curve= 0 ,0
Exp/Cntr=0.3,0.1

Type RM Length L Ch R = 1 ,3256    ,453,453,453
BEGIN DESCRIPTION:
TRIB 1 TO HOG THIEF CREEK 7.0
END DESCRIPTION:
XS GIS Cut Line= 3
      2542275.03     13485774.98        2542575.       13485575.
      2542875.05     13485524.99
#Sta/Elev= 30
  4639.5  142.75  4642.5  142.75    4647  142.36    4668   141.7    4683  140.68
  4704.1  139.69  4724.6  138.42  4755.1  136.82  4776.2  135.95  4791.2   134.9
  4812.2  134.04  4827.2  132.99  4848.3  132.13  4863.3  131.04  4899.4  130.04
  4920.4  129.84  4935.4  129.39  4990.5  128.45  4990.8  127.95  4994.3  127.95
  4994.5  128.45    4997  128.73  5002.5  128.73  5027.9  130.04    5033  130.04
  5088.7  132.54  5093.8   132.6  5192.6  136.84  5276.3  138.94  5304.2  139.79
#Mann= 4 ,-1 , 0
  4639.5    .035       0  4724.6     .12       0  4990.5     .05       0
  4994.5     .12       0
Bank Sta=4990.5,4994.5
XS Rating Curve= 0 ,0
Exp/Cntr=0.3,0.1

Type RM Length L Ch R = 1 ,2803    ,437,437,437
BEGIN DESCRIPTION:
TRIB 1 TO HOG THIEF CREEK 6.0
END DESCRIPTION:
XS GIS Cut Line= 3
      2542474.98       13485975.        2542775.       13485925.
      2543075.02     13485674.98
#Sta/Elev= 30
  4700.3  136.64  4733.3  135.77  4797.9  133.37  4882.8  128.98  4903.1   128.3
  4923.4  127.27  4971.5  125.48  4976.6  125.61  4992.3  125.05  4992.6  124.55
  4996.1  124.55  4996.3  125.05  5001.9  125.41  5007.7  125.41  5011.6  125.76
  5061.1   127.5  5075.4   128.4  5089.7  129.51  5124.9  131.56  5196.5  134.79
  5238.8  136.32  5260.2  137.44  5281.1  138.35  5309.7  139.87    5324  140.84
  5373.5  143.51  5381.3  144.11  5387.8  144.42  5391.7  145.04    5395  145.04
#Mann= 4 ,-1 , 0
  4700.3    .035       0  4797.9     .12       0  4992.3     .05       0
  4996.3     .12       0
Bank Sta=4992.3,4996.3
XS Rating Curve= 0 ,0
Exp/Cntr=0.3,0.1

Type RM Length L Ch R = 1 ,2366    ,487,487,487
BEGIN DESCRIPTION:
TRIB 1 TO HOG THIEF CREEK 5.0
END DESCRIPTION:
XS GIS Cut Line= 3
      2542575.02     13486474.99        2542875.       13486325.
      2543175.01       13486325.
#Sta/Elev= 30
  4664.6   138.5  4667.4   138.5  4700.3  136.99    4768   134.1  4829.5  131.17
  4835.1  131.05  4851.8  130.23  4857.4  130.17  4874.2  129.36  4879.8   129.3
    4895   128.3  4902.2  128.13  4918.9  127.02  4924.5  126.96  4941.3  125.85
  4946.9  125.79  4963.7  124.66  4969.2  124.62  4977.6  124.05  4989.6  123.81
  4989.9  123.31  4993.4  123.31  4993.6  123.81  4997.2  124.03  5079.2  125.79
    5090  126.46  5177.5  133.79  5275.8     143    5280  143.35    5300  143.92
#Mann= 8 ,-1 , 0
  4664.6     .05       0  4700.3     .12       0    4895    .063       0
  4989.6     .05       0  4993.6    .063       0  5079.2    .035       0
  5177.5     .12       0  5275.8    .035       0
Bank Sta=4989.6,4993.6
XS Rating Curve= 0 ,0
Exp/Cntr=0.3,0.1

Type RM Length L Ch R = 1 ,1879    ,487,487,487
BEGIN DESCRIPTION:
TRIB 1 TO HOG THIEF CREEK 4.0
END DESCRIPTION:
XS GIS Cut Line= 3
      2542875.01     13486874.99        2543025.       13486725.
      2543225.01     13486424.98
#Sta/Elev= 30
  4787.9  139.13  4816.2  137.55  4830.3  136.42  4915.2  128.29  4985.9  123.27
  4996.5  122.27    5003  122.27  5007.5  121.54  5011.5   121.5  5011.8     121
  5015.3     121  5015.5   121.5  5022.6  122.03  5028.6  121.99  5043.6  123.07
  5049.6  123.03  5064.6  123.65  5074.2  124.35  5100.7  125.48  5115.7  126.59
  5136.7  127.39  5151.8  128.64  5172.8  129.48  5190.5  130.77  5208.8  131.57
  5223.9  132.81  5244.9  133.67  5259.9  134.85  5306.9  137.35  5360.6  140.28
#Mann= 6 ,-1 , 0
  4787.9     .12       0  5011.5     .05       0  5015.5     .12       0
  5074.2    .035       0  5190.5    .063       0  5306.9     .12       0
Bank Sta=5011.5,5015.5
XS Rating Curve= 0 ,0
Exp/Cntr=0.3,0.1

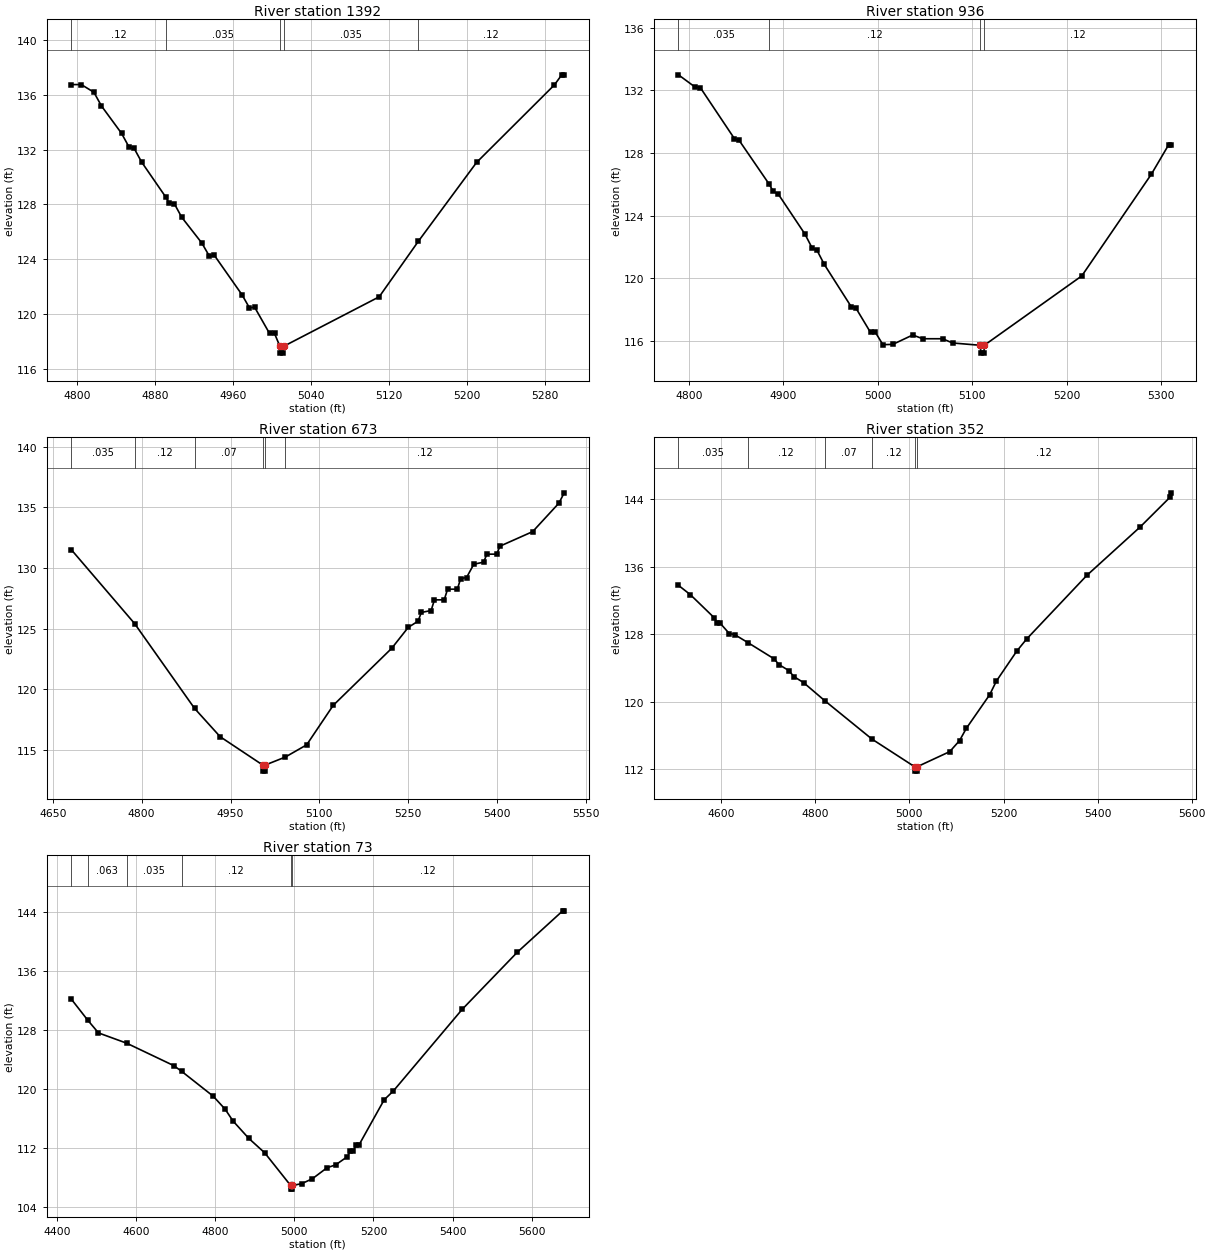
Type RM Length L Ch R = 1 ,1392    ,456,456,456
BEGIN DESCRIPTION:
TRIB 1 TO HOG THIEF CREEK 3.0
END DESCRIPTION:
XS GIS Cut Line= 3
      2543424.99     13487025.04        2543475.       13486825.
        2543475.       13486525.
#Sta/Elev= 30
  4793.8  136.73  4804.1  136.73    4817  136.17  4824.8  135.17  4845.4  133.18
  4853.1  132.18  4858.3  132.09    4866  131.09  4891.1  128.51  4894.3   128.1
  4899.5  128.07  4907.2  127.07  4927.8   125.2  4935.6  124.24  4940.7   124.3
  4969.1  121.43  4976.8  120.47    4982  120.53  4997.4  118.61  5002.5  118.61
    5008  117.68  5008.2  117.18  5011.7  117.18    5012  117.68    5110  121.28
  5150.2  125.32    5210  131.06    5290  136.71  5297.5  137.44    5300  137.44
#Mann= 5 ,-1 , 0
  4793.8     .12       0  4891.1    .035       0    5008    .035       0
    5012    .035       0  5150.2     .12       0
Bank Sta=5008,5012
XS Rating Curve= 0 ,0
Exp/Cntr=0.3,0.1

Type RM Length L Ch R = 1 ,936     ,263,263,263
BEGIN DESCRIPTION:
TRIB 1 TO HOG THIEF CREEK 2.0
END DESCRIPTION:
XS GIS Cut Line= 3
        2543825.       13487125.        2543875.       13486925.
      2543774.99     13486624.98
#Sta/Elev= 30
  4788.7     133  4806.7   132.2  4811.9  132.18    4848  128.92  4853.1   128.8
  4884.7  126.02  4889.2  125.54  4894.4  125.38  4922.7  122.82  4930.4  121.92
  4935.6  121.77  4943.3  120.87  4971.7  118.18  4976.8  118.08  4992.3  116.52
  4997.5  116.52  5005.4  115.74  5015.9  115.76    5037  116.36  5047.6  116.12
  5068.6  116.12  5079.2  115.85  5108.8   115.7  5109.1   115.2  5112.6   115.2
  5112.8   115.7  5216.2  120.14    5290  126.65  5308.4  128.54  5311.1  128.54
#Mann= 4 ,-1 , 0
  4788.7    .035       0  4884.7     .12       0  5108.8     .05       0
  5112.8     .12       0
Bank Sta=5108.8,5112.8
XS Rating Curve= 0 ,0
Exp/Cntr=0.3,0.1

Type RM Length L Ch R = 1 ,673     ,321,321,321
BEGIN DESCRIPTION:
Mapping XS 064f0699
END DESCRIPTION:
XS GIS Cut Line= 3
      2543965.15     13487193.37      2544126.61     13486943.37
      2544372.29     13486468.57
#Sta/Elev= 30
  4681.2  131.51  4788.1  125.41  4889.2  118.42  4932.5  116.08  5004.5  113.74
  5004.8  113.24  5008.3  113.24  5008.5  113.74  5042.5   114.4  5078.6  115.41
  5123.3  118.66  5222.3  123.38  5250.1   125.1  5266.6  125.61  5272.2  126.33
  5288.7  126.49  5294.3  127.37  5310.8  127.37  5316.5  128.25    5333  128.25
  5338.6  129.13  5348.5  129.21  5360.8  130.31  5377.3  130.48  5382.9  131.14
  5399.4  131.14    5405   131.8  5460.2     133  5504.5  135.35  5513.4   136.2
#Mann= 6 ,-1 , 0
  4681.2    .035       0  4788.1     .12       0  4889.2     .07       0
  5004.5     .05       0  5008.5     .07       0  5042.5     .12       0
Bank Sta=5004.5,5008.5
XS Rating Curve= 0 ,0
Exp/Cntr=0.3,0.1

Type RM Length L Ch R = 1 ,352     ,279,279,279
BEGIN DESCRIPTION:
Mapping XS 082b8fff
END DESCRIPTION:
XS GIS Cut Line= 3
      2543932.68     13487257.06      2544386.18     13487102.97
      2544742.26     13486659.37
#Sta/Elev= 30
    4509  133.79  4534.4  132.68  4585.4  129.93  4591.9  129.27  4597.2  129.33
  4617.1  128.08  4628.6  127.95  4656.5  127.01  4712.1  125.09  4722.7   124.4
  4743.5   123.7  4754.4  122.98  4774.9  122.27  4820.3  120.11  4920.5  115.57
  5011.7  112.28    5012  111.78  5015.5  111.78  5015.7  112.28  5085.7  114.09
  5106.5  115.39  5120.9  116.84  5170.5  120.82  5184.9  122.45  5228.1  125.99
    5249  127.42    5377  134.96  5490.6  140.71  5554.6  144.26  5556.8  144.75
#Mann= 6 ,-1 , 0
    4509    .035       0  4656.5     .12       0  4820.3     .07       0
  4920.5     .12       0  5011.7     .05       0  5015.7     .12       0
Bank Sta=5011.7,5015.7
XS Rating Curve= 0 ,0
Exp/Cntr=0.3,0.1

Type RM Length L Ch R = 1 ,73      ,0,0,0
BEGIN DESCRIPTION:
TRIB 1 TO HOG THIEF CREEK 1.0
END DESCRIPTION:
XS GIS Cut Line= 3
      2543966.32     13487307.47        2544525.       13487325.
       2544873.8     13486732.74
#Sta/Elev= 30
  4436.1  132.18  4477.7  129.33  4504.8  127.61    4576  126.22  4694.9  123.19
  4715.1  122.41    4795  119.04    4825  117.29    4845  115.69    4885  113.33
    4925  111.39  4990.6  106.97  4990.8  106.47  4994.3  106.47  4994.6  106.97
  5018.3   107.2  5045.8  107.88  5082.9  109.37  5104.4  109.75  5134.3  110.87
  5141.5  111.61  5147.3  111.62  5157.1  112.38  5162.9  112.39  5227.3  118.57
  5250.4  119.75  5424.5   130.8  5563.7  138.52  5678.7  144.13  5682.4  144.13
#Mann= 6 ,-1 , 0
  4436.1    .035       0  4477.7    .063       0    4576    .035       0
  4715.1     .12       0  4990.6     .05       0  4994.6     .12       0
Bank Sta=4990.6,4994.6
XS Rating Curve= 0 ,0
Exp/Cntr=0.3,0.1

Chan Stop Cuts=-1
Use User Specified Reach Order=0
Composite Channel Slope=5