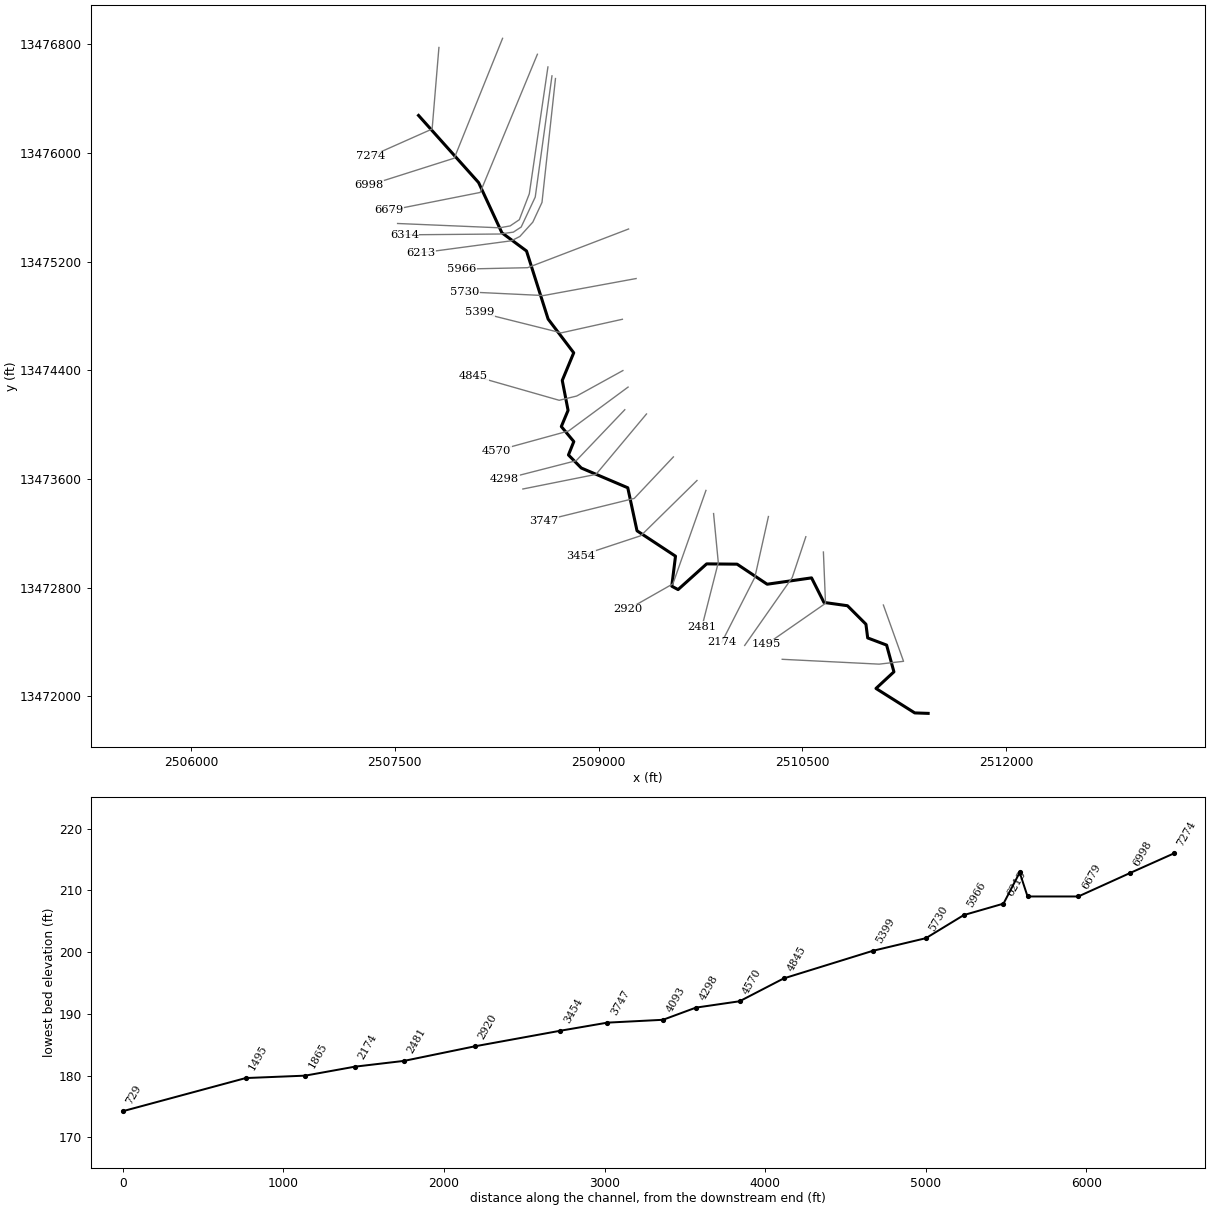
--- TRIB 1 TO KILGORE CREEK.prj (project) ---

Proj Title=TRIB 1 TO KILGORE CREEK Base Level Engineering
Current Plan=p01
Default Exp/Contr=0.3,0.1
English Units
Geom File=g01
Flow File=f01
Plan File=p01
Y Axis Title=Elevation
X Axis Title(PF)=Main Channel Distance
X Axis Title(XS)=Station
BEGIN DESCRIPTION:
TRIB 1 TO KILGORE CREEK
END DESCRIPTION:
DSS Export Rating Curves= 0
DSS Export Rating Curve Sorted= 0
DSS Export Volume Flow Curves= 0
DXF OffsetX= 0
DXF OffsetY= 0
DXF ScaleX= 1
DXF ScaleY= 10

--- TRIB 1 TO KILGORE CREEK.p01 (plan) ---

Plan Title=Multiple Run
Short Identifier=Multiple
Geom File=g01
Flow File=f01
Subcritical Flow
K Sum by GR= 0
Std Step Tol= 0.01
Critical Tol= 0.01
Num of Std Step Trials= 20
Max Error Tol= 0.3
Flow Tol Ratio= 0.001
Split Flow NTrial= 30
Split Flow Tol= 0.02
Split Flow Ratio= 0.02
Log Output Level= 0
Friction Slope Method= 1
Unsteady Friction Slope Method= 2
Unsteady Bridges Friction Slope Method= 1
Parabolic Critical Depth
Global Vel Dist=  1 , 1 , 1
Global Log Level= 0
CheckData=True
Encroach Param= -1, 0, 0, 0
BEGIN DESCRIPTION:
Multiple Run
END DESCRIPTION:

--- TRIB 1 TO KILGORE CREEK.f01 (steady flow) ---

Flow Title=Multiple
Number of Profiles=7
Profile Names=10-year,25-year,50-year,1pct_min,100-year,1pct_plu,500-year
River Rch & RM= TRIB 1 TO KILGOR,Reach-1,7274
     298     452     583     365     729    1454    1123
River Rch & RM= TRIB 1 TO KILGOR,Reach-1,4570
     783    1265    1700    1105    2204    4398    3667
Boundary for River Rch & Prof#=TRIB 1 TO KILGOR,Reach-1,1
Up Type=0
Dn Type=3
Dn Slope=0.005
Boundary for River Rch & Prof#=TRIB 1 TO KILGOR,Reach-1,2
Up Type=0
Dn Type=3
Dn Slope=0.005
Boundary for River Rch & Prof#=TRIB 1 TO KILGOR,Reach-1,3
Up Type=0
Dn Type=3
Dn Slope=0.005
Boundary for River Rch & Prof#=TRIB 1 TO KILGOR,Reach-1,4
Up Type=0
Dn Type=3
Dn Slope=0.005
Boundary for River Rch & Prof#=TRIB 1 TO KILGOR,Reach-1,5
Up Type=0
Dn Type=3
Dn Slope=0.005
Boundary for River Rch & Prof#=TRIB 1 TO KILGOR,Reach-1,6
Up Type=0
Dn Type=3
Dn Slope=0.005
Boundary for River Rch & Prof#=TRIB 1 TO KILGOR,Reach-1,7
Up Type=0
Dn Type=3
Dn Slope=0.005

--- TRIB 1 TO KILGORE CREEK.g01 (geometry) ---

Geom Title=Existing Conditions
Program Version=4.10

River Reach=TRIB 1 TO KILGOR,Reach-1
Reach XY= 30
        2507675.       13476275.      2508116.86     13475781.06
      2508288.47     13475411.43      2508469.54     13475277.46
      2508628.61      13474776.5      2508816.96     13474528.32
      2508732.56       13474325.      2508775.35     13474104.85
      2508725.61     13473985.62      2508817.64     13473875.08
      2508778.15     13473776.63      2508872.56     13473680.52
      2509214.62     13473535.11       2509282.7     13473218.52
      2509565.88     13473031.76      2509538.37     13472810.84
      2509584.85     13472785.89      2509794.98     13472975.04
      2510019.14     13472972.94      2510240.27     13472825.37
      2510567.03     13472872.07       2510658.2     13472691.42
      2510831.19     13472667.18      2510967.12     13472531.12
      2510980.11     13472430.11      2511119.28     13472377.58
      2511173.11     13472180.71      2511041.14     13472058.39
      2511326.41     13471878.39        2511425.       13471875.

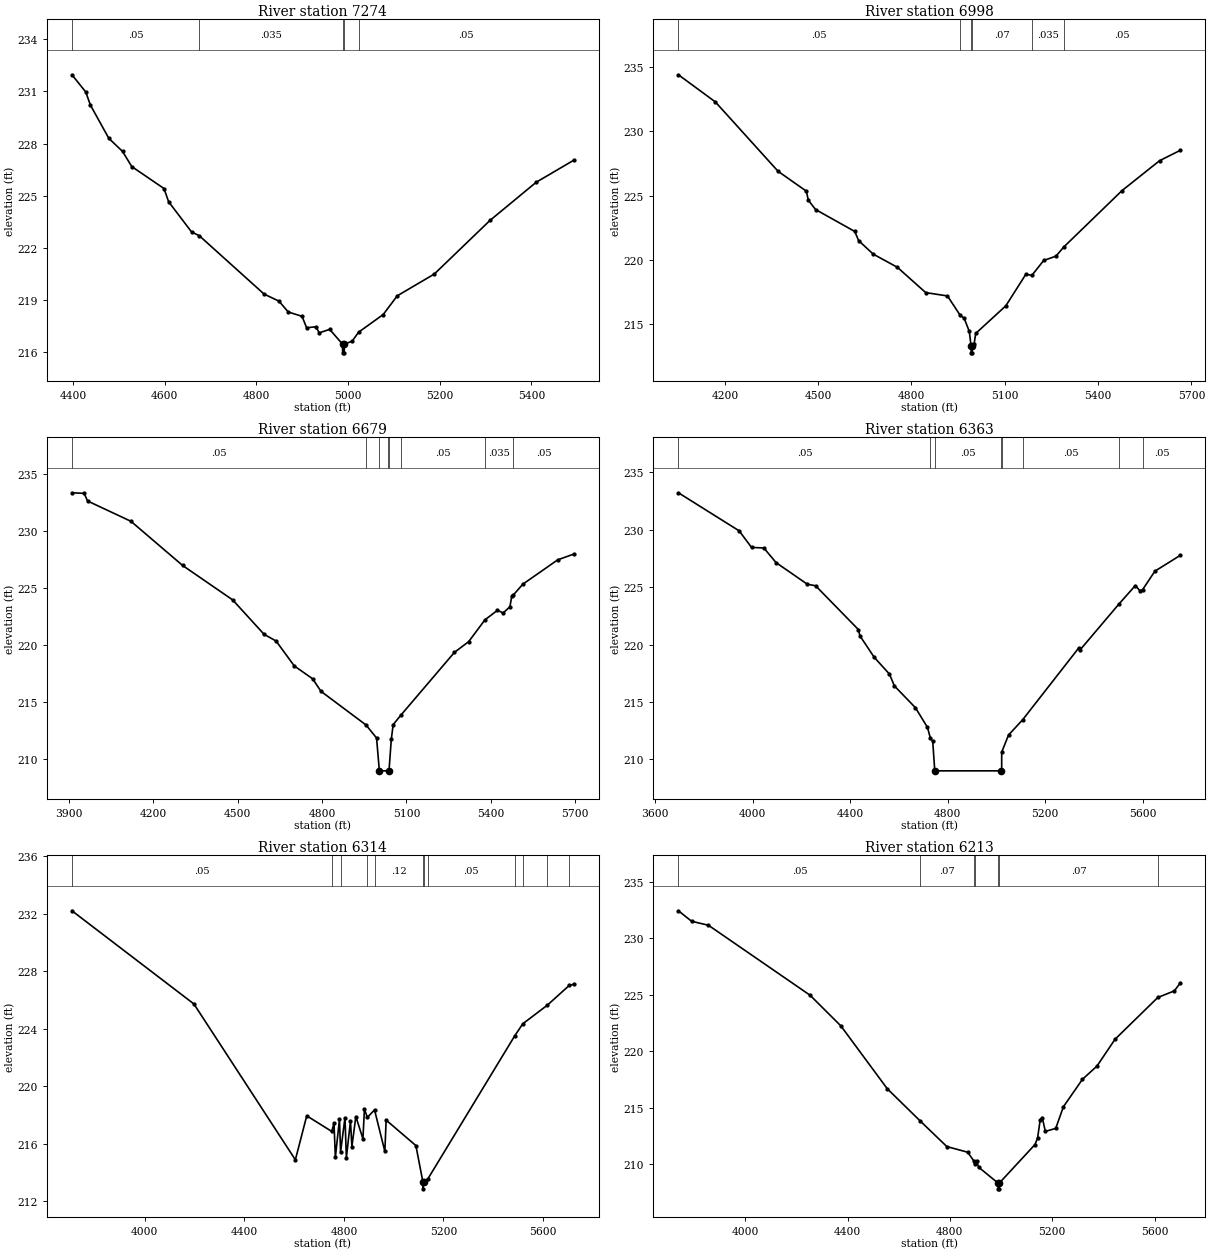
Type RM Length L Ch R = 1 ,7274    ,276,276,276
BEGIN DESCRIPTION:
TRIB 1 TO KILGORE CREEK 14.0
END DESCRIPTION:
XS GIS Cut Line= 3
        2507825.     13476775.04        2507775.       13476175.
      2507324.97     13475974.99
#Sta/Elev= 30
  4397.9  231.96    4428  230.97  4438.1  230.22  4478.2  228.31  4508.3  227.55
  4528.4  226.68  4598.6  225.42  4608.7  224.66  4658.8  222.92  4675.4  222.71
  4816.9  219.35  4849.5  218.94  4869.6  218.32  4899.7  218.07  4909.7  217.41
  4929.8  217.47  4937.3  217.12  4959.9  217.32    4988  216.47  4988.2  215.97
  4991.7  215.97    4992  216.47  5008.9  216.64  5023.2  217.16  5076.6  218.17
  5107.4  219.25  5188.1   220.5  5309.8  223.59  5410.4  225.78  5492.5  227.05
#Mann= 5 ,-1 , 0
  4397.9     .05       0  4675.4    .035       0    4988    .035       0
    4992    .035       0  5023.2     .05       0
Bank Sta=4988,4992
XS Rating Curve= 0 ,0
Exp/Cntr=0.3,0.1

Type RM Length L Ch R = 1 ,6998    ,319,319,319
BEGIN DESCRIPTION:
Mapping XS fa688f58
END DESCRIPTION:
XS GIS Cut Line= 3
      2508293.41     13476842.31      2507937.89     13475960.48
      2507306.28     13475759.88
#Sta/Elev= 30
  4050.8  234.41  4169.4   232.3  4371.4  226.89    4462  225.35  4468.4  224.65
  4491.6  223.92  4617.8  222.21  4630.1   221.5  4676.8  220.45  4754.7  219.42
  4845.8  217.45  4915.8  217.19  4956.7  215.68  4969.5  215.45  4985.9  214.43
  4991.7  213.26  4991.9  212.76  4995.4  212.76  4995.7  213.26  5001.6  213.48
  5006.5  214.27  5103.3  216.42  5167.8  218.88    5187  218.79    5225  219.95
  5264.6  220.29  5289.2  220.99  5476.8  225.39  5597.6  227.72  5664.3  228.53
#Mann= 6 ,-1 , 0
  4050.8     .05       0  4956.7     .07       0  4991.7     .05       0
  4995.7     .07       0    5187    .035       0  5289.2     .05       0
Bank Sta=4991.7,4995.7
XS Rating Curve= 0 ,0
Exp/Cntr=0.3,0.1

Type RM Length L Ch R = 1 ,6679    ,316,316,316
BEGIN DESCRIPTION:
Mapping XS 3aeb9bb4
END DESCRIPTION:
XS GIS Cut Line= 3
      2508549.63     13476725.14      2508128.57     13475708.24
      2507458.63     13475575.44
#Sta/Elev= 30
  3911.5  233.37  3954.9  233.32    3967  232.65  4121.2  230.87  4304.7     227
  4482.7  223.98  4594.5  220.96  4636.8  220.38  4701.8  218.19  4766.7  217.07
  4796.5  215.97  4956.5  213.02    4994  211.88  5003.9     209  5034.2     209
  5038.2     209  5046.4  211.77    5053  213.05  5079.7  213.86  5270.6  219.38
  5321.6  220.33    5379  222.23  5423.6  223.07  5443.9  222.84  5467.7  223.37
  5474.5  224.29  5478.6  224.37  5513.8  225.36  5637.6  227.49  5695.1     228
#Mann= 8 ,-1 , 0
  3911.5     .05       0  4956.5     .07       0  5003.9     .05       0
  5034.2     .05       0  5038.2     .07       0  5079.7     .05       0
    5379    .035       0  5478.6     .05       0
Bank Sta=5003.9,5038.2
XS Rating Curve= 0 ,0
Exp/Cntr=0.3,0.1

Type RM Length L Ch R = 1 ,6363    ,49,49,49
BEGIN DESCRIPTION:
Mapping XS 9cc74018
END DESCRIPTION:
XS GIS Cut Line= 6
      2508627.09     13476631.79      2508490.05     13475698.31
      2508416.56     13475507.64      2508349.03     13475461.95
      2508271.57     13475448.05      2507520.84     13475479.83
#Sta/Elev= 30
  3695.4  233.23  3944.8  229.91  3995.4  228.47  4045.9  228.42  4096.4  227.14
  4224.5  225.26  4258.2  225.13  4433.9  221.31  4440.1  220.77  4498.6   218.9
  4561.4  217.43  4581.6   216.4    4668   214.5  4717.3  212.79  4729.5  211.84
  4738.9  211.58  4747.3     209    5018     209  5021.8     209    5022  210.63
    5050  212.12  5107.9  213.45  5337.4  219.69  5342.4  219.51    5502  223.51
  5570.5  225.15  5590.6  224.65  5600.5   224.8  5650.6   226.4  5754.9  227.78
#Mann= 8 ,-1 , 0
  3695.4     .05       0  4729.5     .07       0  4747.3     .05       0
    5018     .07       0    5022     .12       0  5107.9     .05       0
    5502    .035       0  5600.5     .05       0
Bank Sta=4747.3,5018
XS Rating Curve= 0 ,0
Exp/Cntr=0.3,0.1

Type RM Length L Ch R = 1 ,6314    ,101,101,101
BEGIN DESCRIPTION:
Mapping XS d949c827
END DESCRIPTION:
XS GIS Cut Line= 6
      2508656.89     13476566.26      2508533.75     13475674.47
      2508430.47     13475454.01      2508372.87     13475416.27
      2508273.56     13475402.37      2507570.42     13475396.41
#Sta/Elev= 30
  3707.6  232.22  4197.5  225.74  4605.1   214.9  4650.8  217.96  4751.5  216.87
  4760.2  217.46  4765.8  215.08  4782.3  217.71  4786.7  215.45  4804.4  217.83
    4810  215.05  4826.5   217.6  4832.1  215.82  4848.1  217.91  4876.5  216.36
  4882.5  218.42  4894.4  217.85  4923.1  218.37  4964.6  215.48  4969.7  217.66
  5089.2  215.89  5117.2  213.38  5117.5  212.88  5121.2  213.38  5137.6  213.58
  5486.6  223.53  5518.7  224.36    5617  225.65  5705.4  227.03  5723.8  227.11
#Mann= 12 ,-1 , 0
  3707.6     .05       0  4751.5     .07       0  4786.7     .12       0
  4894.4     .07       0  4923.1     .12       0  5117.2     .05       0
  5121.2     .12       0  5137.6     .05       0  5486.6     .12       0
  5518.7    .035       0    5617     .12       0  5705.4     .05       0
Bank Sta=5117.2,5121.2
XS Rating Curve= 0 ,0
Exp/Cntr=0.3,0.1

Type RM Length L Ch R = 1 ,6213    ,247,247,247
BEGIN DESCRIPTION:
Mapping XS 18b42dab
END DESCRIPTION:
XS GIS Cut Line= 6
      2508682.71     13476546.44       2508583.4     13475634.75
      2508515.87     13475489.76      2508420.53     13475384.49
      2508358.96     13475352.71      2507691.59     13475263.33
#Sta/Elev= 30
    3739  232.44  3790.7  231.51  3856.3  231.16  4253.5  224.97  4374.2  222.25
  4555.2   216.7  4684.7  213.83  4788.2  211.58  4869.6  211.08    4894   210.3
  4896.8  210.03  4904.7  210.34  4912.1  209.76    4989  208.34  4989.3  207.84
  4992.8  207.84    4993  208.34  5132.8  211.76  5142.9  212.34  5153.1  213.95
    5161  214.15  5173.3  212.92  5213.8  213.19    5244  215.11  5318.3  217.53
    5375   218.7  5445.5  221.07  5612.8  224.77  5677.2  225.35  5700.8  226.06
#Mann= 7 ,-1 , 0
    3739     .05       0  4684.7     .07       0    4894     .12       0
  4896.8     .07       0    4989     .05       0    4993     .07       0
  5612.8    .035       0
Bank Sta=4989,4993
XS Rating Curve= 0 ,0
Exp/Cntr=0.3,0.1

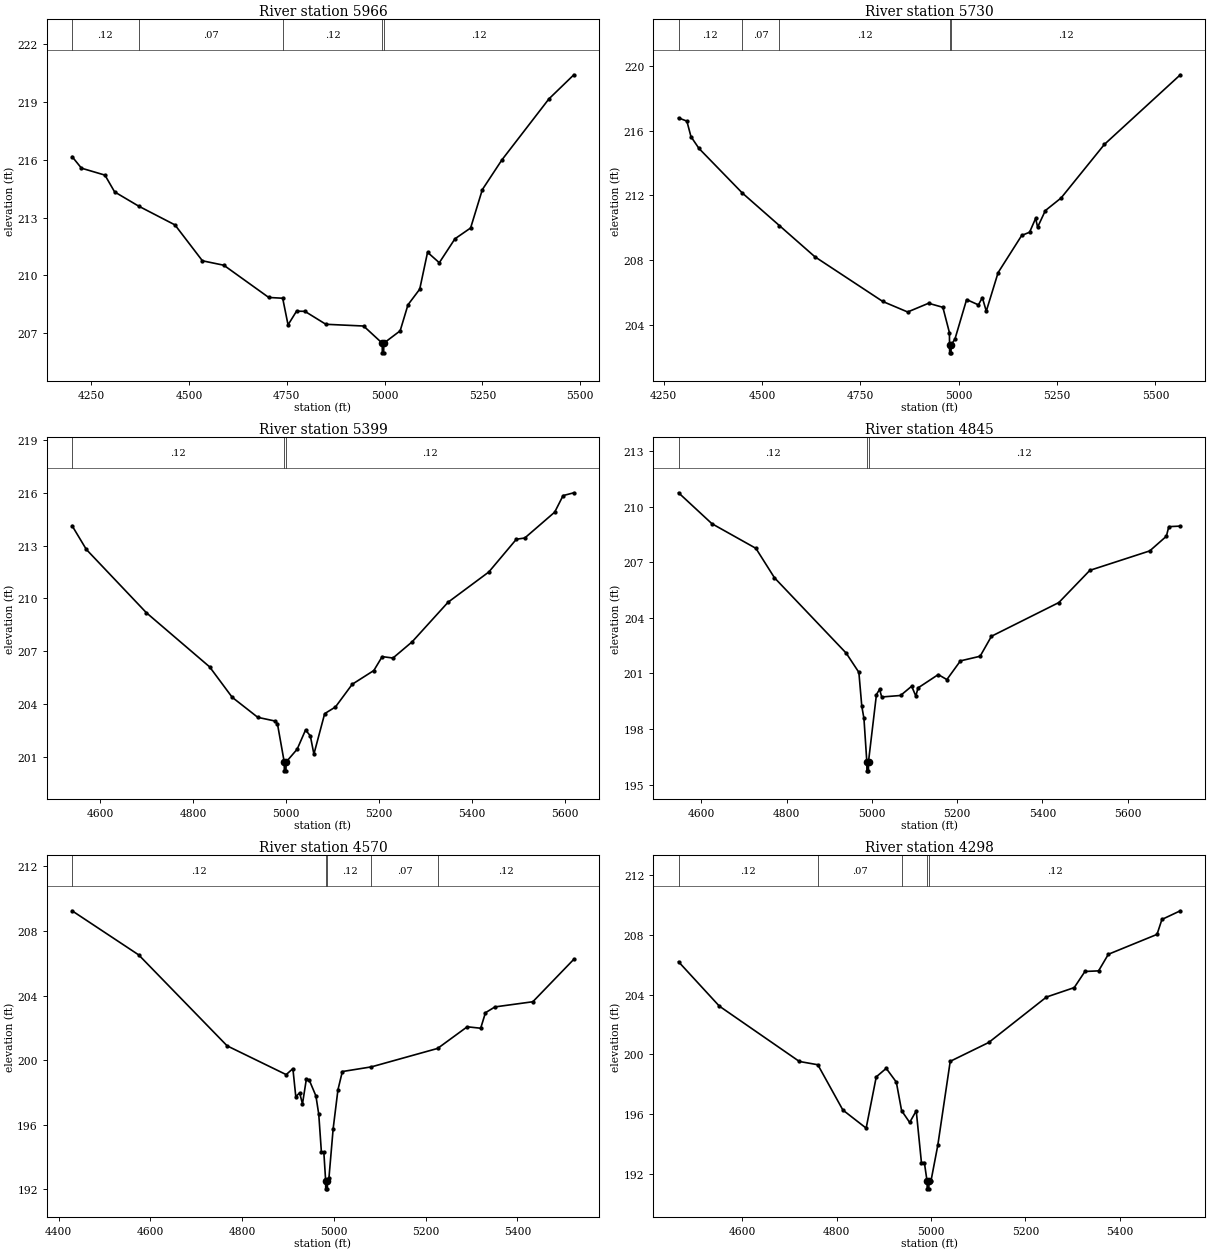
Type RM Length L Ch R = 1 ,5966    ,236,236,236
BEGIN DESCRIPTION:
Mapping XS 3a7fd4cb
END DESCRIPTION:
XS GIS Cut Line= 3
       2509220.5      13475439.3      2508477.41     13475154.56
      2507991.29     13475144.15
#Sta/Elev= 30
  4201.5  216.16  4225.5  215.56  4285.5   215.2  4310.2  214.33  4371.9  213.59
  4464.4  212.62  4534.5  210.76  4589.2  210.53    4704  208.86  4739.6  208.82
  4753.3  207.44    4775  208.15  4796.4  208.14  4849.9  207.47  4946.3  207.38
  4993.9  206.49  4994.1  205.99  4997.6  205.99  4997.9  206.49  5039.7  207.13
  5059.7  208.48  5089.7  209.29  5109.7   211.2  5139.7  210.66  5179.7   211.9
  5219.7  212.46  5249.7  214.45  5299.7  215.99  5419.8  219.15  5483.5   220.4
#Mann= 5 ,-1 , 0
  4201.5     .12       0  4371.9     .07       0  4739.6     .12       0
  4993.9     .05       0  4997.9     .12       0
Bank Sta=4993.9,4997.9
XS Rating Curve= 0 ,0
Exp/Cntr=0.3,0.1

Type RM Length L Ch R = 1 ,5730    ,331,331,331
BEGIN DESCRIPTION:
Mapping XS 26df53a1
END DESCRIPTION:
XS GIS Cut Line= 3
      2509276.04     13475074.71      2508595.47      13474949.7
      2508012.18     13474977.48
#Sta/Elev= 30
  4287.5   216.8  4308.7   216.6  4319.1  215.64  4339.4  214.91  4449.6  212.15
    4544  210.13  4634.2   208.2  4806.9  205.43  4870.1  204.78  4923.2  205.32
  4959.6  205.07  4976.3   203.5  4976.6  202.75  4976.9  202.25  4980.4  202.25
  4980.6  202.75  4990.3   203.1    5020  205.55    5050  205.22    5060  205.67
    5070  204.83  5100.1  207.22  5160.1  209.52  5180.1  209.72  5195.5  210.58
  5200.5  210.03  5220.2  211.06  5260.2  211.84  5370.4  215.16  5563.4  219.47
#Mann= 5 ,-1 , 0
  4287.5     .12       0  4449.6     .07       0    4544     .12       0
  4976.6     .05       0  4980.6     .12       0
Bank Sta=4976.6,4980.6
XS Rating Curve= 0 ,0
Exp/Cntr=0.3,0.1

Type RM Length L Ch R = 1 ,5399    ,554,554,554
BEGIN DESCRIPTION:
TRIB 1 TO KILGORE CREEK 10.0
END DESCRIPTION:
XS GIS Cut Line= 3
      2509174.98       13474775.        2508725.       13474675.
      2508125.02     13474824.99
#Sta/Elev= 30
  4539.3  214.13    4570  212.78  4699.3  209.18  4835.1  206.11  4883.7  204.38
  4938.8  203.24  4975.9  203.03  4981.1  202.87  4995.7   200.7  4995.9   200.2
  4999.4   200.2  4999.7   200.7  5023.5  201.43  5041.5  202.52  5051.8  202.19
  5059.5  201.15  5082.7  203.45  5105.9  203.83    5142  205.12  5188.4   205.9
  5206.4  206.69  5229.6  206.61  5270.8  207.53  5348.1  209.78  5435.8   211.5
    5495  213.36  5513.1  213.43  5577.5   214.9  5595.5  215.84  5618.7     216
#Mann= 3 ,-1 , 0
  4539.3     .12       0  4995.7     .05       0  4999.7     .12       0
Bank Sta=4995.7,4999.7
XS Rating Curve= 0 ,0
Exp/Cntr=0.3,0.1

Type RM Length L Ch R = 1 ,4845    ,275,275,275
BEGIN DESCRIPTION:
Mapping XS 6a86519a
END DESCRIPTION:
XS GIS Cut Line= 4
      2509178.81     13474397.62      2508838.53     13474210.12
      2508710.05     13474178.87      2508079.04     13474359.16
#Sta/Elev= 30
  4546.3  210.76  4624.6  209.09  4727.7  207.76  4771.3  206.17  4939.5   202.1
  4969.3  201.06  4976.1  199.24  4981.2  198.57  4987.9  196.24  4988.2  195.74
  4991.7  195.74  4991.9  196.24  5010.5  199.86  5017.8  200.14  5022.9  199.73
    5067  199.81  5093.1  200.31  5102.9  199.78  5108.1  200.22  5155.5  200.94
  5175.7  200.67  5207.5  201.68  5253.7  201.93  5280.3  203.01  5438.3  204.83
  5511.1  206.57  5651.5  207.62  5690.5  208.41  5696.3  208.93  5723.3  208.96
#Mann= 3 ,-1 , 0
  4546.3     .12       0  4987.9     .05       0  4991.9     .12       0
Bank Sta=4987.9,4991.9
XS Rating Curve= 0 ,0
Exp/Cntr=0.3,0.1

Type RM Length L Ch R = 1 ,4570    ,272,272,272
BEGIN DESCRIPTION:
Mapping XS ffdcf5fb
END DESCRIPTION:
XS GIS Cut Line= 3
      2509216.97     13474276.07       2508779.5     13473953.18
      2508249.15     13473807.59
#Sta/Elev= 30
  4429.2  209.25  4574.4  206.52  4767.2  200.89  4895.9  199.11  4910.5  199.48
  4916.8  197.75  4925.2  197.98  4931.4   197.3  4939.8  198.82    4946  198.78
  4960.7  197.79  4966.9  196.65  4972.6  194.33  4977.9  194.33  4981.9  192.54
  4982.1  192.04  4985.6  192.04  4985.9  192.54    4989  192.68  4998.3  195.77
  5008.7  198.17  5018.3   199.3  5081.8  199.59  5225.9  200.73  5290.5  202.07
  5319.8  201.98  5330.2  202.94  5350.9   203.3  5433.5  203.62  5522.9  206.25
#Mann= 5 ,-1 , 0
  4429.2     .12       0  4981.9     .05       0  4985.9     .12       0
  5081.8     .07       0  5225.9     .12       0
Bank Sta=4981.9,4985.9
XS Rating Curve= 0 ,0
Exp/Cntr=0.3,0.1

Type RM Length L Ch R = 1 ,4298    ,205,205,205
BEGIN DESCRIPTION:
Mapping XS 3fa9fedc
END DESCRIPTION:
XS GIS Cut Line= 3
      2509192.69     13474109.42      2508835.05     13473734.43
      2508307.24       13473599.
#Sta/Elev= 30
  4465.2   206.2  4551.7  203.23  4721.2  199.53  4760.3  199.31  4813.4  196.28
  4862.7  195.07  4884.1   198.5  4905.2  199.07  4926.6  198.15  4937.8  196.24
  4954.9  195.45  4968.8  196.23  4979.8  192.77    4986  192.77  4991.8  191.51
    4992  191.01  4995.5  191.01  4995.8  191.51  5000.1  191.55  5014.4  193.91
  5040.8  199.54  5122.4   200.8  5244.7  203.84  5303.5  204.47  5326.2  205.55
  5355.1  205.59  5375.8   206.7  5478.9  208.03  5489.3  209.03  5528.3  209.61
#Mann= 5 ,-1 , 0
  4465.2     .12       0  4760.3     .07       0  4937.8     .12       0
  4991.8     .05       0  4995.8     .12       0
Bank Sta=4991.8,4995.8
XS Rating Curve= 0 ,0
Exp/Cntr=0.3,0.1

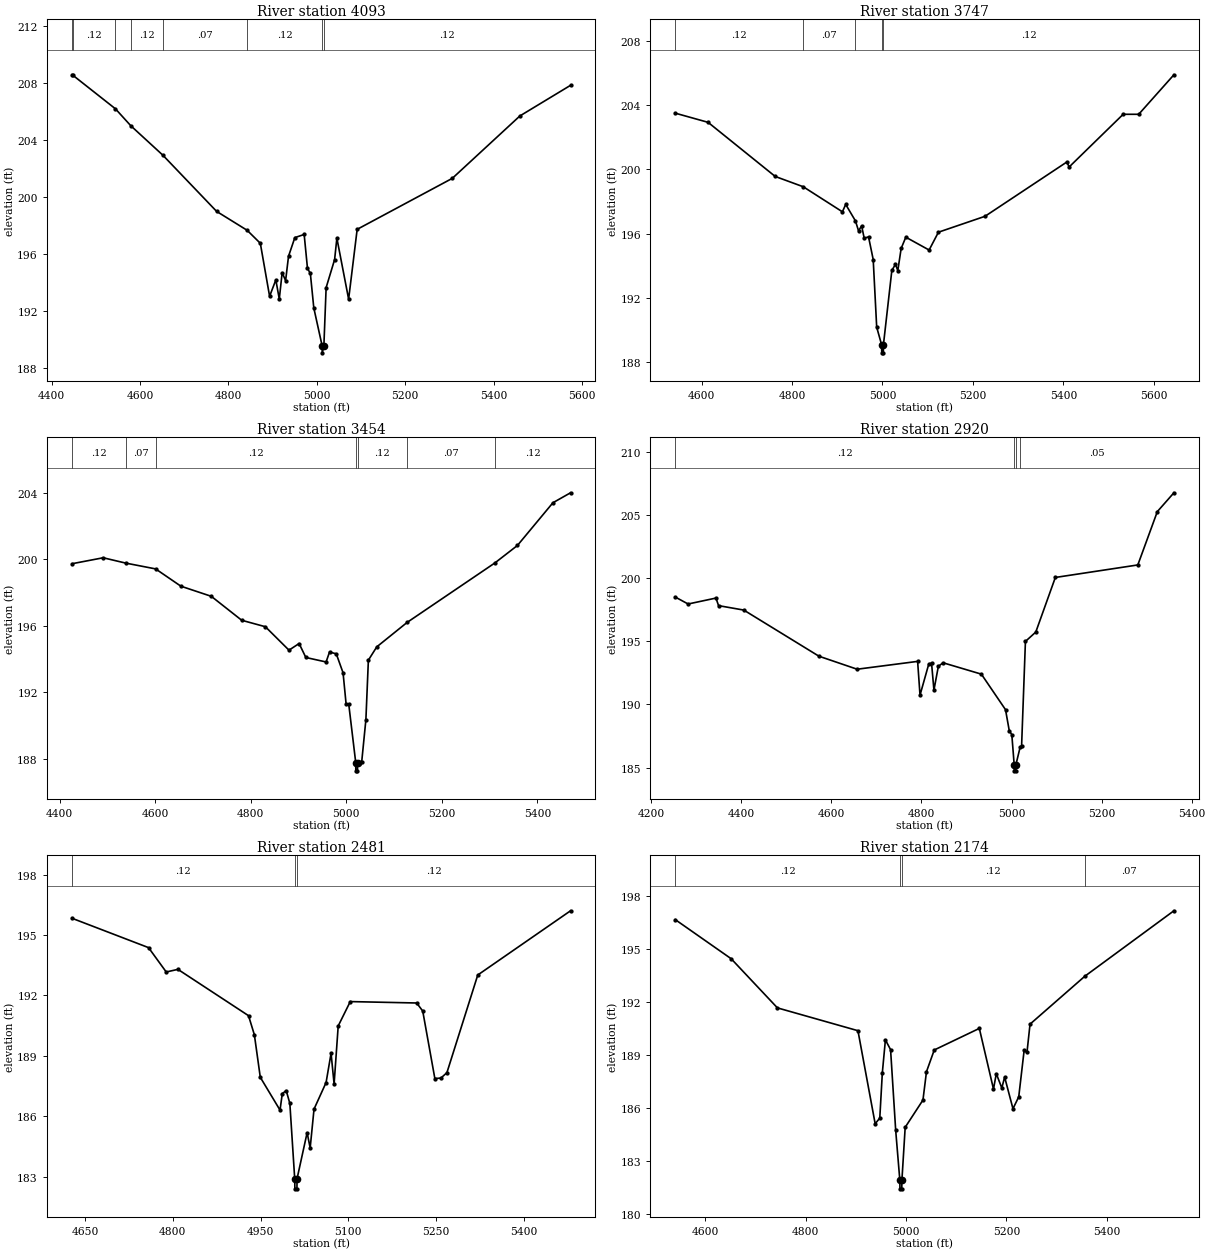
Type RM Length L Ch R = 1 ,4093    ,346,346,346
BEGIN DESCRIPTION:
Mapping XS f756f2b8
END DESCRIPTION:
XS GIS Cut Line= 3
      2509352.44     13474078.21      2508980.89     13473633.73
      2508442.67     13473526.09
#Sta/Elev= 30
  4445.8  208.56  4447.4  208.54  4544.3  206.17  4579.1  204.98  4651.4  202.92
  4773.2  198.97  4842.4  197.64  4872.1  196.73  4893.1  193.01  4907.2  194.16
    4915  192.82  4921.5  194.67  4929.3  194.11  4935.9  195.82  4950.2  197.13
  4971.3  197.35  4978.8  194.97  4985.3  194.61  4993.1  192.19  5011.9  189.54
  5012.2  189.04  5015.9  189.54    5021  193.62  5040.2  195.59  5045.3  197.09
  5071.9  192.81  5091.2  197.71  5306.5  201.29  5459.4  205.67    5574  207.82
#Mann= 8 ,-1 , 0
  4445.8    .035       0  4447.4     .12       0  4544.3     .07       0
  4579.1     .12       0  4651.4     .07       0  4842.4     .12       0
  5011.9     .05       0  5015.9     .12       0
Bank Sta=5011.9,5015.9
XS Rating Curve= 0 ,0
Exp/Cntr=0.3,0.1

Type RM Length L Ch R = 1 ,3747    ,293,293,293
BEGIN DESCRIPTION:
Mapping XS 8e6c8688
END DESCRIPTION:
XS GIS Cut Line= 3
      2509550.31     13473762.18      2509262.14     13473456.65
       2508599.5     13473293.59
#Sta/Elev= 30
  4541.9   203.5  4614.4  202.93  4762.9  199.56  4824.8  198.92  4911.4  197.36
  4918.7  197.82  4940.3  196.79    4947  196.18  4953.9  196.48  4959.6  195.72
  4969.2   195.8  4979.5  194.39  4987.2  190.18  4998.1  189.08  4998.4  188.58
  5001.9  188.58  5002.1  189.08  5020.7  193.71  5028.7  194.09  5033.9   193.7
  5041.3  195.08  5051.6  195.78  5103.1  194.98  5123.7  196.09  5226.7  197.08
  5407.6  200.46  5412.7  200.15  5532.1  203.43  5566.5  203.43  5644.3  205.89
#Mann= 5 ,-1 , 0
  4541.9     .12       0  4824.8     .07       0  4940.3     .12       0
  4998.1     .05       0  5002.1     .12       0
Bank Sta=4998.1,5002.1
XS Rating Curve= 0 ,0
Exp/Cntr=0.3,0.1

Type RM Length L Ch R = 1 ,3454    ,534,534,534
BEGIN DESCRIPTION:
Mapping XS f521d471
END DESCRIPTION:
XS GIS Cut Line= 3
      2509723.98     13473588.63      2509310.75     13473182.34
      2508869.93     13473036.56
#Sta/Elev= 30
  4425.7  199.73  4491.2  200.09  4538.2  199.77  4600.9  199.42  4653.8  198.38
  4717.5  197.77  4781.1  196.33  4830.7  195.94  4880.1  194.53  4901.3  194.93
  4915.4  194.09  4957.8  193.82    4965  194.42  4979.1  194.31  4993.3  193.17
  4999.7  191.28  5005.2  191.28  5019.8  187.77    5020  187.27  5023.5  187.27
  5023.8  187.77  5032.3   187.8  5041.1  190.35  5046.3  193.93  5063.9  194.73
  5127.4   196.2  5311.2  199.78  5358.3  200.83  5432.6   203.4  5469.5     204
#Mann= 7 ,-1 , 0
  4425.7     .12       0  4538.2     .07       0  4600.9     .12       0
  5019.8     .05       0  5023.8     .12       0  5127.4     .07       0
  5311.2     .12       0
Bank Sta=5019.8,5023.8
XS Rating Curve= 0 ,0
Exp/Cntr=0.3,0.1

Type RM Length L Ch R = 1 ,2920    ,439,439,439
BEGIN DESCRIPTION:
Mapping XS f2c8ddb7
END DESCRIPTION:
XS GIS Cut Line= 3
       2509789.9     13473515.64      2509546.86     13472828.18
      2509218.47     13472641.51
#Sta/Elev= 30
  4253.6  198.49  4282.1  197.94  4343.9  198.41  4349.7  197.81  4405.7  197.46
  4572.5  193.81  4657.3  192.78  4791.6   193.4  4796.9  190.73  4816.4   193.2
  4822.5  193.26  4827.8  191.13  4837.6  193.01  4848.1  193.29  4933.1  192.39
  4986.7  189.58    4995  187.92  5000.7   187.6  5005.9  185.24  5006.2  184.74
  5009.7  184.74  5009.9  185.24  5019.2  186.62  5022.4  186.71  5030.9  194.98
  5053.9  195.72  5097.3  200.04  5280.4  201.03  5323.7  205.25  5360.5  206.74
#Mann= 4 ,-1 , 0
  4253.6     .12       0  5005.9     .05       0  5009.9     .12       0
  5019.2     .05       0
Bank Sta=5005.9,5009.9
XS Rating Curve= 0 ,0
Exp/Cntr=0.3,0.1

Type RM Length L Ch R = 1 ,2481    ,307,307,307
BEGIN DESCRIPTION:
Mapping XS 64d6924f
END DESCRIPTION:
XS GIS Cut Line= 3
      2509846.04     13473345.31      2509880.76     13472985.08
      2509759.91     13472510.32
#Sta/Elev= 30
  4627.8  195.83  4758.7  194.37  4788.9  193.16  4808.9  193.29  4929.5  190.99
  4939.5  190.04  4949.6  187.93  4983.3   186.3  4987.2  187.12  4993.9  187.27
  5000.1  186.63  5008.4  182.89  5008.7  182.39  5012.2  182.39  5012.4  182.89
  5029.6  185.18  5034.8  184.42  5041.4  186.35    5062  187.67  5070.5  189.12
  5075.7   187.6  5082.7  190.48  5103.3  191.69  5216.8  191.62  5227.1  191.22
  5247.8  187.87  5258.1  187.89  5268.4  188.16  5321.1  193.01  5479.6   196.2
#Mann= 3 ,-1 , 0
  4627.8     .12       0  5008.4     .05       0  5012.4     .12       0
Bank Sta=5008.4,5012.4
XS Rating Curve= 0 ,0
Exp/Cntr=0.3,0.1

Type RM Length L Ch R = 1 ,2174    ,309,309,309
BEGIN DESCRIPTION:
Mapping XS dbf8e9fe
END DESCRIPTION:
XS GIS Cut Line= 3
      2510249.67     13473323.58      2510149.86     13472876.58
      2509907.01     13472399.55
#Sta/Elev= 30
  4540.2  196.67  4651.5  194.46  4743.7  191.68  4904.1  190.39  4938.4  185.13
  4947.6  185.45  4952.7  188.02  4958.8  189.87  4969.1  189.32  4979.3  184.75
  4987.5  181.95  4987.8  181.45  4991.4  181.45  4991.7  181.95  4998.2  184.93
  5033.6  186.47  5040.6  188.07  5056.1   189.3  5145.9  190.52  5174.1  187.09
  5179.7  187.96  5190.7  187.15  5196.3  187.77  5212.9  185.98  5224.4  186.65
  5235.2  189.29  5240.8  189.16  5246.9  190.76  5356.1  193.47  5533.5  197.17
#Mann= 4 ,-1 , 0
  4540.2     .12       0  4987.5     .05       0  4991.7     .12       0
  5356.1     .07       0
Bank Sta=4987.5,4991.7
XS Rating Curve= 0 ,0
Exp/Cntr=0.3,0.1

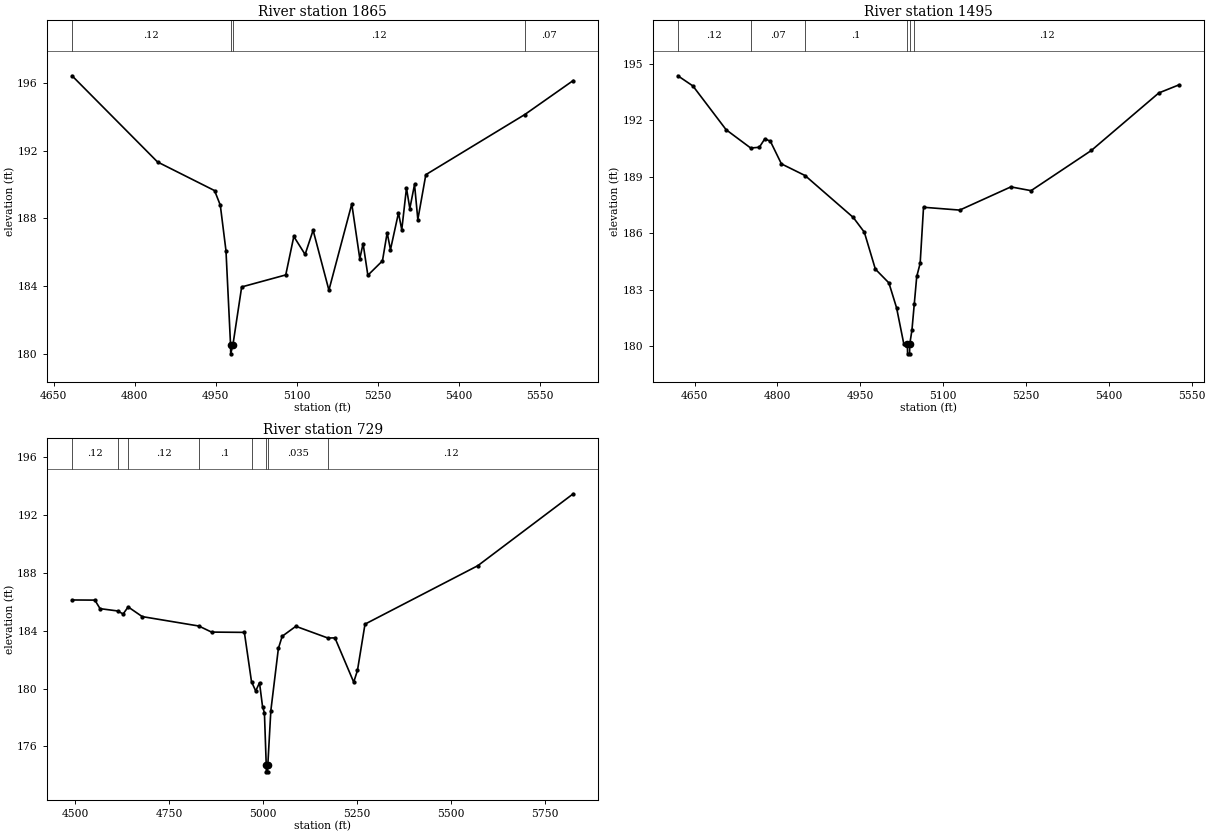
Type RM Length L Ch R = 1 ,1865    ,370,370,370
BEGIN DESCRIPTION:
TRIB 1 TO KILGORE CREEK 2.0
END DESCRIPTION:
XS GIS Cut Line= 3
        2510525.     13473175.01        2510425.       13472875.
      2510074.98     13472374.97
#Sta/Elev= 30
  4684.2  196.42  4842.3  191.33  4947.7  189.64  4958.3  188.78  4968.8  186.09
  4977.3   180.5  4977.5     180  4981.5   180.5  4997.8  183.95  5079.3  184.66
  5094.2  186.93  5115.1  185.87  5129.9   187.3  5159.1  183.76  5201.4  188.85
  5216.2  185.62  5222.3  186.51  5231.1  184.64  5258.1  185.49  5266.8  187.15
  5272.9  186.15  5287.7  188.32  5293.8  187.33  5302.5  189.79  5308.7  188.58
  5317.4     190  5323.5  187.93  5338.3  190.58  5521.2  194.13  5610.8  196.14
#Mann= 4 ,-1 , 0
  4684.2     .12       0  4977.3     .05       0  4981.5     .12       0
  5521.2     .07       0
Bank Sta=4977.3,4981.5
XS Rating Curve= 0 ,0
Exp/Cntr=0.3,0.1

Type RM Length L Ch R = 1 ,1495    ,766,766,766
BEGIN DESCRIPTION:
Mapping XS eb60ac6c
END DESCRIPTION:
XS GIS Cut Line= 3
       2510654.2     13473062.33      2510669.82     13472684.74
      2510234.95     13472382.67
#Sta/Elev= 30
  4619.8  194.35  4647.1  193.81  4707.2  191.49  4751.7  190.52  4767.3  190.56
  4777.3  191.01  4787.3  190.88  4807.3  189.68  4850.2  189.06  4937.4  186.84
  4957.4  186.06  4977.4   184.1  5001.9  183.37  5015.8  182.05  5028.8  180.15
  5035.4  180.11  5035.7  179.61  5039.4  179.61  5039.6  180.11  5043.6  180.86
  5047.9  182.27  5052.3  183.71  5058.5  184.41  5064.6  187.38  5130.1  187.23
  5222.7  188.46  5259.3  188.26  5368.4  190.39  5490.6  193.44  5527.2  193.87
#Mann= 6 ,-1 , 0
  4619.8     .12       0  4751.7     .07       0  4850.2      .1       0
  5035.4     .05       0  5039.6      .1       0  5047.9     .12       0
Bank Sta=5035.4,5039.6
XS Rating Curve= 0 ,0
Exp/Cntr=0.3,0.1

Type RM Length L Ch R = 1 ,729     ,0,0,0
BEGIN DESCRIPTION:
TRIB 1 TO KILGORE CREEK 1.0
END DESCRIPTION:
XS GIS Cut Line= 4
      2511095.53     13472672.21      2511243.97     13472258.13
      2511064.29     13472237.29      2510351.05     13472272.92
#Sta/Elev= 30
  4491.1  186.12  4551.9  186.11  4565.7  185.52  4612.7  185.36  4627.2  185.15
  4640.5  185.64  4678.1  184.97  4828.7  184.32  4862.6   183.9  4950.1  183.88
  4969.1  180.47  4980.3  179.83  4990.4   180.4  4998.5  178.75  5003.5  178.32
  5008.3  174.74  5008.6  174.24  5012.3  174.24  5012.6  174.74  5020.6  178.47
  5040.7  182.77  5050.8  183.61  5087.2   184.3  5172.5  183.49  5191.3   183.5
  5241.3  180.44  5251.3  181.25  5271.4  184.45  5571.9  188.49    5826  193.46
#Mann= 8 ,-1 , 0
  4491.1     .12       0  4612.7     .07       0  4640.5     .12       0
  4828.7      .1       0  4969.1    .035       0  5008.3    .035       0
  5012.6    .035       0  5172.5     .12       0
Bank Sta=5008.3,5012.6
XS Rating Curve= 0 ,0
Exp/Cntr=0.3,0.1

Chan Stop Cuts=-1
Use User Specified Reach Order=0
Composite Channel Slope=5