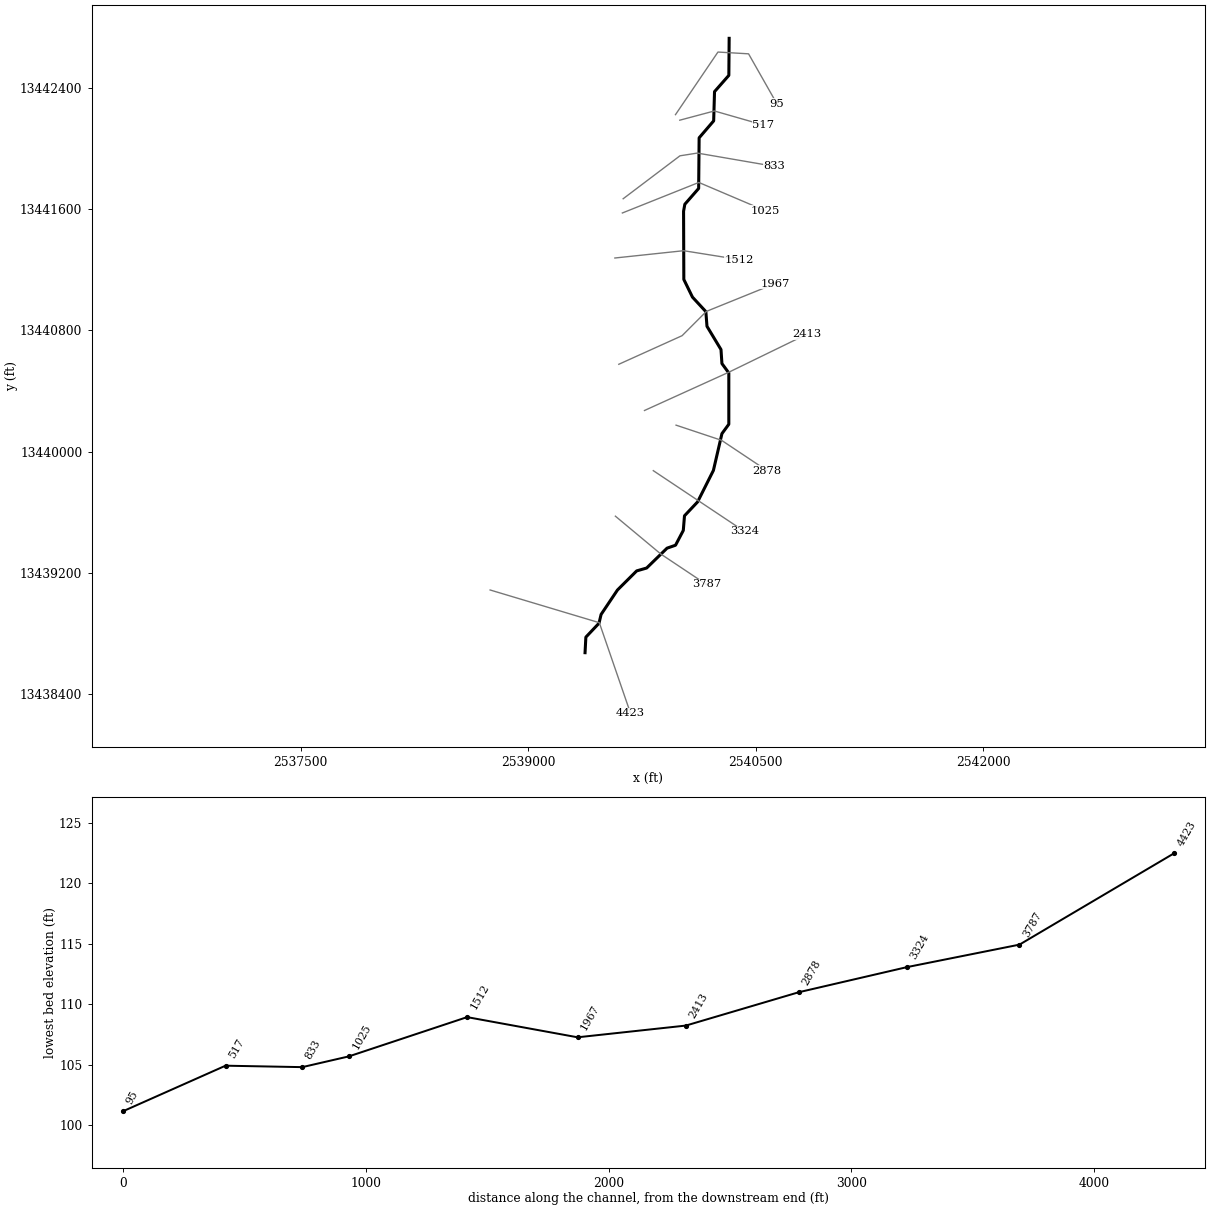
--- TRIB 1 TO PAYTON BRANCH.prj (project) ---

Proj Title=TRIB 1 TO PAYTON BRANCH Base Level Engineering
Current Plan=p01
Default Exp/Contr=0.3,0.1
English Units
Geom File=g01
Flow File=f01
Plan File=p01
Y Axis Title=Elevation
X Axis Title(PF)=Main Channel Distance
X Axis Title(XS)=Station
BEGIN DESCRIPTION:
TRIB 1 TO PAYTON BRANCH
END DESCRIPTION:
DSS Export Rating Curves= 0
DSS Export Rating Curve Sorted= 0
DSS Export Volume Flow Curves= 0
DXF OffsetX= 0
DXF OffsetY= 0
DXF ScaleX= 1
DXF ScaleY= 10

--- TRIB 1 TO PAYTON BRANCH.p01 (plan) ---

Plan Title=Multiple Run
Short Identifier=Multiple
Geom File=g01
Flow File=f01
Subcritical Flow
K Sum by GR= 0
Std Step Tol= 0.01
Critical Tol= 0.01
Num of Std Step Trials= 20
Max Error Tol= 0.3
Flow Tol Ratio= 0.001
Split Flow NTrial= 30
Split Flow Tol= 0.02
Split Flow Ratio= 0.02
Log Output Level= 0
Friction Slope Method= 1
Unsteady Friction Slope Method= 2
Unsteady Bridges Friction Slope Method= 1
Parabolic Critical Depth
Global Vel Dist=  1 , 1 , 1
Global Log Level= 0
CheckData=True
Encroach Param= -1, 0, 0, 0
BEGIN DESCRIPTION:
Multiple Run
END DESCRIPTION:

--- TRIB 1 TO PAYTON BRANCH.f01 (steady flow) ---

Flow Title=Multiple
Number of Profiles=7
Profile Names=10-year,25-year,50-year,1pct_min,100-year,1pct_plu,500-year
River Rch & RM= TRIB 1 TO PAYTON,Reach-1,4423
     257     386     494     307     612    1221     928
River Rch & RM= TRIB 1 TO PAYTON,Reach-1,2413
     442     684     893     565    1128    2250    1776
Boundary for River Rch & Prof#=TRIB 1 TO PAYTON,Reach-1,1
Up Type=0
Dn Type=3
Dn Slope=0.005
Boundary for River Rch & Prof#=TRIB 1 TO PAYTON,Reach-1,2
Up Type=0
Dn Type=3
Dn Slope=0.005
Boundary for River Rch & Prof#=TRIB 1 TO PAYTON,Reach-1,3
Up Type=0
Dn Type=3
Dn Slope=0.005
Boundary for River Rch & Prof#=TRIB 1 TO PAYTON,Reach-1,4
Up Type=0
Dn Type=3
Dn Slope=0.005
Boundary for River Rch & Prof#=TRIB 1 TO PAYTON,Reach-1,5
Up Type=0
Dn Type=3
Dn Slope=0.005
Boundary for River Rch & Prof#=TRIB 1 TO PAYTON,Reach-1,6
Up Type=0
Dn Type=3
Dn Slope=0.005
Boundary for River Rch & Prof#=TRIB 1 TO PAYTON,Reach-1,7
Up Type=0
Dn Type=3
Dn Slope=0.005

--- TRIB 1 TO PAYTON BRANCH.g01 (geometry) ---

Geom Title=Existing Conditions
Program Version=4.10

River Reach=TRIB 1 TO PAYTON,Reach-1
Reach XY= 30
        2539375.       13438675.      2539380.36     13438777.49
      2539466.82     13438868.96      2539480.87     13438927.28
      2539588.63     13439088.21      2539715.32     13439214.22
      2539781.05     13439233.16      2539915.59     13439364.11
      2539971.49     13439383.48      2540022.68     13439480.94
      2540030.54     13439577.42      2540116.84     13439668.95
      2540221.17     13439876.58      2540277.36     13440119.02
      2540322.74     13440180.94      2540322.74     13440519.06
      2540277.36     13440580.98      2540271.17     13440673.42
      2540178.83     13440826.59      2540171.38      13440923.5
      2540083.16     13441018.95       2540026.2      13441135.5
       2540024.5     13441585.21      2540032.83     13441631.19
      2540123.94     13441735.44      2540127.07     13442069.14
      2540222.93     13442180.86      2540228.55     13442373.53
      2540322.94     13442480.86        2540325.       13442725.

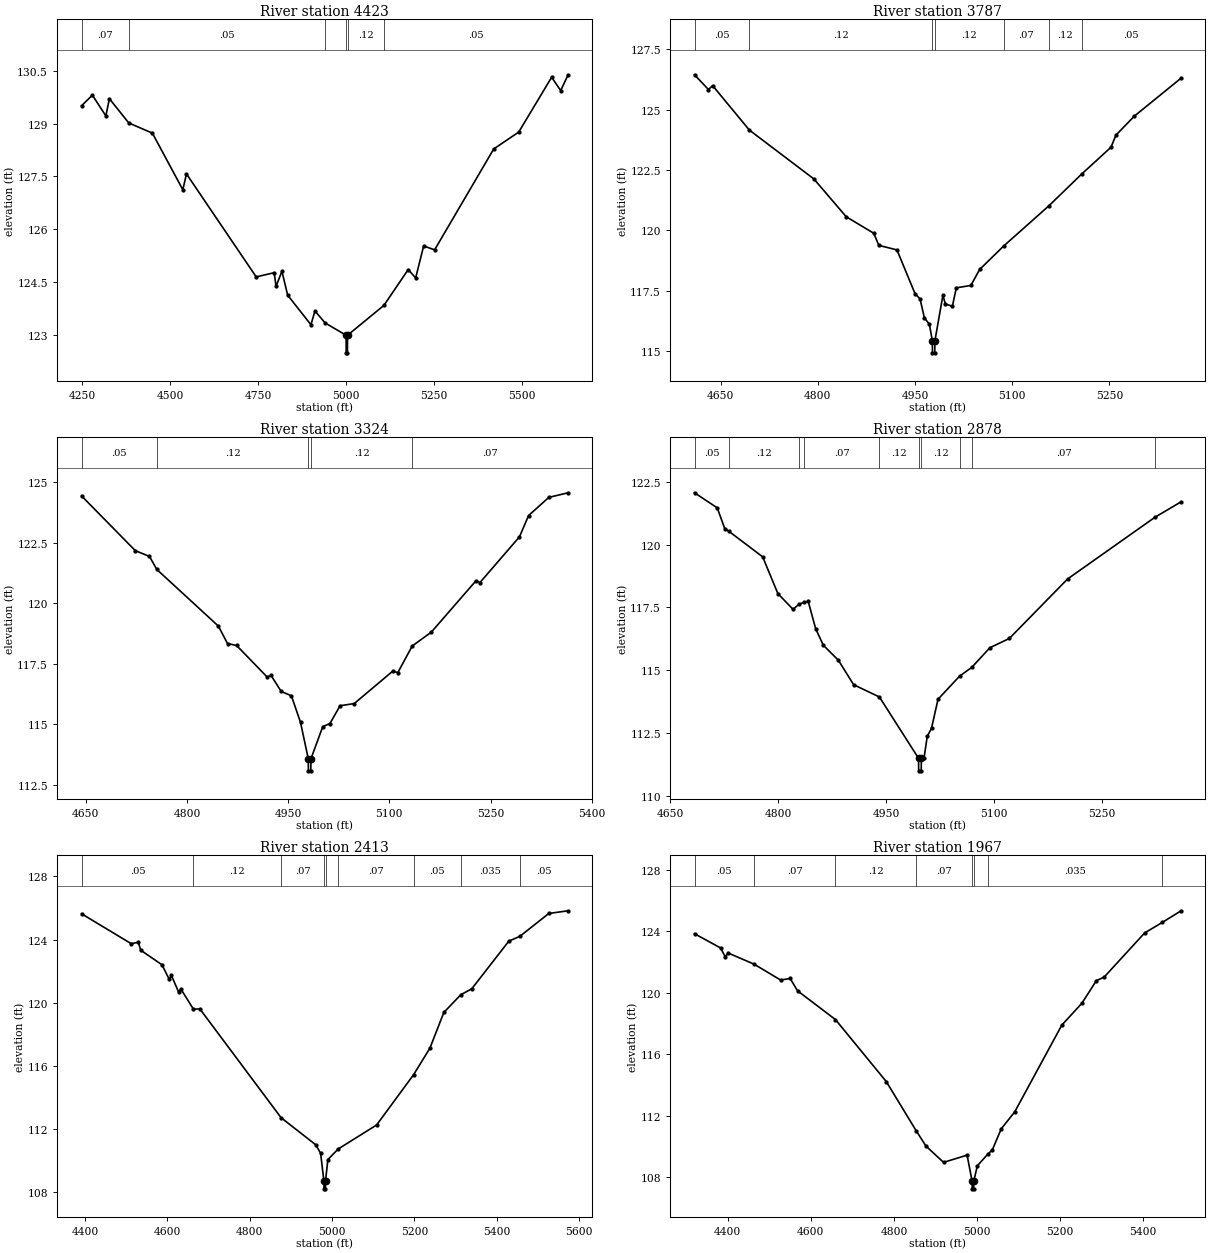
Type RM Length L Ch R = 1 ,4423    ,636,636,636
BEGIN DESCRIPTION:
TRIB 1 TO PAYTON BRANCH 9.0
END DESCRIPTION:
XS GIS Cut Line= 3
      2538749.15     13439088.41      2539469.13     13438872.72
      2539675.01     13438274.98
#Sta/Elev= 30
  4248.4  129.51  4279.2  129.81  4317.5  129.22  4327.6  129.71  4382.6  129.02
  4449.8  128.73  4536.4  127.12  4546.8  127.57  4745.1  124.64  4796.3  124.76
  4801.5  124.37  4818.2   124.8  4834.6  124.12  4900.7  123.28  4912.2  123.67
  4941.2  123.33  5000.8  122.98    5001  122.48  5004.5  122.48  5004.8  122.98
  5108.3  123.83  5177.4  124.85  5198.5  124.61  5221.3  125.52  5252.5  125.41
  5420.6  128.28  5491.7  128.76  5585.3  130.32    5611  129.94  5632.2  130.39
#Mann= 6 ,-1 , 0
  4248.4     .07       0  4382.6     .05       0  4941.2     .12       0
  5000.8     .05       0  5004.8     .12       0  5108.3     .05       0
Bank Sta=5000.8,5004.8
XS Rating Curve= 0 ,0
Exp/Cntr=0.3,0.1

Type RM Length L Ch R = 1 ,3787    ,463,463,463
BEGIN DESCRIPTION:
TRIB 1 TO PAYTON BRANCH 8.0
END DESCRIPTION:
XS GIS Cut Line= 3
      2539574.97     13439575.03        2539875.       13439325.
      2540174.99     13439125.01
#Sta/Elev= 30
  4609.6  126.44  4631.1  125.83  4637.6  125.99  4694.3  124.15  4793.8  122.13
  4843.9  120.56  4886.3  119.88  4894.1  119.38  4922.1  119.19    4950  117.38
  4957.8  117.16  4964.4  116.38  4972.2  116.11  4976.7  115.43  4976.9  114.93
  4980.4  114.93  4980.7  115.43    4993  117.31  4996.9  116.95  5007.7  116.86
  5013.7  117.62  5036.2  117.72  5049.7  118.38  5086.8  119.35  5156.8  121.02
  5207.2  122.33  5252.5  123.44  5260.1  123.94  5288.6  124.73  5360.7   126.3
#Mann= 7 ,-1 , 0
  4609.6     .05       0  4694.3     .12       0  4976.7     .05       0
  4980.7     .12       0  5086.8     .07       0  5156.8     .12       0
  5207.2     .05       0
Bank Sta=4976.7,4980.7
XS Rating Curve= 0 ,0
Exp/Cntr=0.3,0.1

Type RM Length L Ch R = 1 ,3324    ,446,446,446
BEGIN DESCRIPTION:
TRIB 1 TO PAYTON BRANCH 7.0
END DESCRIPTION:
XS GIS Cut Line= 3
      2539825.02     13439874.99        2540125.       13439675.
      2540425.01     13439474.99
#Sta/Elev= 30
  4643.9  124.43  4723.5  122.17  4744.5  121.93  4755.5  121.39  4846.7  119.05
  4860.2  118.33  4873.7  118.25  4918.8  116.95  4924.8  117.01  4939.8  116.35
  4954.9  116.17  4968.4  115.07  4979.9  113.57  4980.1  113.07  4983.6  113.07
  4983.9  113.57  5001.4   114.9  5011.9  115.02    5027  115.76    5048  115.85
  5105.1  117.19  5112.6  117.13    5134  118.23  5162.2   118.8  5228.3  120.92
  5234.3  120.85  5292.9  122.74  5306.4  123.62  5336.4  124.37    5365  124.56
#Mann= 5 ,-1 , 0
  4643.9     .05       0  4755.5     .12       0  4979.9     .05       0
  4983.9     .12       0    5134     .07       0
Bank Sta=4979.9,4983.9
XS Rating Curve= 0 ,0
Exp/Cntr=0.3,0.1

Type RM Length L Ch R = 1 ,2878    ,465,465,465
BEGIN DESCRIPTION:
TRIB 1 TO PAYTON BRANCH 6.0
END DESCRIPTION:
XS GIS Cut Line= 3
      2539975.03     13440174.99        2540275.       13440075.
      2540575.04     13439874.97
#Sta/Elev= 30
  4683.8  122.06  4715.4  121.46  4725.9  120.63  4731.9  120.52  4778.6  119.51
  4799.7  118.05  4820.8  117.42  4829.5  117.63  4836.5   117.7  4841.9  117.74
  4852.4  116.64    4863  115.99    4884  115.39  4905.1  114.42    4941  113.93
  4995.4  111.49  4995.6  110.99  4999.1  110.99  4999.4  111.49    5003  111.49
  5007.5  112.36  5013.5  112.69  5022.5  113.84  5052.5  114.76  5069.5  115.11
  5094.6  115.89  5121.7  116.26  5202.8  118.63  5324.5  121.09  5360.6   121.7
#Mann= 10 ,-1 , 0
  4683.8     .05       0  4731.9     .12       0  4829.5     .05       0
  4836.5     .07       0    4941     .12       0  4995.4     .05       0
  4999.4     .12       0  5052.5      .1       0  5069.5     .07       0
  5324.5     .05       0
Bank Sta=4995.4,4999.4
XS Rating Curve= 0 ,0
Exp/Cntr=0.3,0.1

Type RM Length L Ch R = 1 ,2413    ,446,446,446
BEGIN DESCRIPTION:
TRIB 1 TO PAYTON BRANCH 5.0
END DESCRIPTION:
XS GIS Cut Line= 3
       2539766.9     13440271.68        2540325.       13440525.
      2540837.17     13440774.26
#Sta/Elev= 30
  4391.2  125.63  4511.8  123.74  4529.3  123.83  4534.8  123.33  4586.8   122.4
  4604.1  121.49  4609.6  121.73  4627.2  120.67  4632.6  120.87    4663   119.6
  4678.8  119.61  4876.1  112.73  4960.2  111.02  4972.2  110.48  4980.1  108.73
  4980.4  108.23  4983.9  108.23  4984.1  108.73  4989.8  110.08  5014.8  110.75
  5108.3  112.27  5198.1  115.45  5237.6  117.12  5271.7  119.39  5312.9  120.51
  5339.4  120.88  5429.6   123.9  5456.2   124.2  5526.8  125.65  5573.7  125.82
#Mann= 9 ,-1 , 0
  4391.2     .05       0    4663     .12       0  4876.1     .07       0
  4980.1     .05       0  4984.1     .07       0  5014.8     .07       0
  5198.1     .05       0  5312.9    .035       0  5456.2     .05       0
Bank Sta=4980.1,4984.1
XS Rating Curve= 0 ,0
Exp/Cntr=0.3,0.1

Type RM Length L Ch R = 1 ,1967    ,455,455,455
BEGIN DESCRIPTION:
TRIB 1 TO PAYTON BRANCH 4.0
END DESCRIPTION:
XS GIS Cut Line= 4
      2539597.56     13440576.34      2540014.89     13440764.89
        2540175.       13440925.      2540626.28     13441107.62
#Sta/Elev= 30
    4320  123.84    4383  122.91    4394  122.33  4400.6  122.59  4463.5  121.86
  4527.2  120.83  4550.3  120.93  4567.9  120.13  4659.3  118.26  4781.6  114.23
  4853.2  111.05  4877.1  110.04  4919.5  108.98  4976.1  109.45  4988.2  107.76
  4988.5  107.26    4992  107.26  4992.2  107.76  5000.8  108.76  5026.5  109.53
  5036.7  109.78  5058.3  111.16  5090.7  112.26  5204.1   117.9  5252.4  119.32
  5287.3  120.79    5306  121.02  5403.5  123.89  5445.8  124.57  5491.2  125.33
#Mann= 8 ,-1 , 0
    4320     .05       0  4463.5     .07       0  4659.3     .12       0
  4853.2     .07       0  4988.2     .05       0  4992.2     .07       0
  5026.5    .035       0  5445.8     .05       0
Bank Sta=4988.2,4992.2
XS Rating Curve= 0 ,0
Exp/Cntr=0.3,0.1

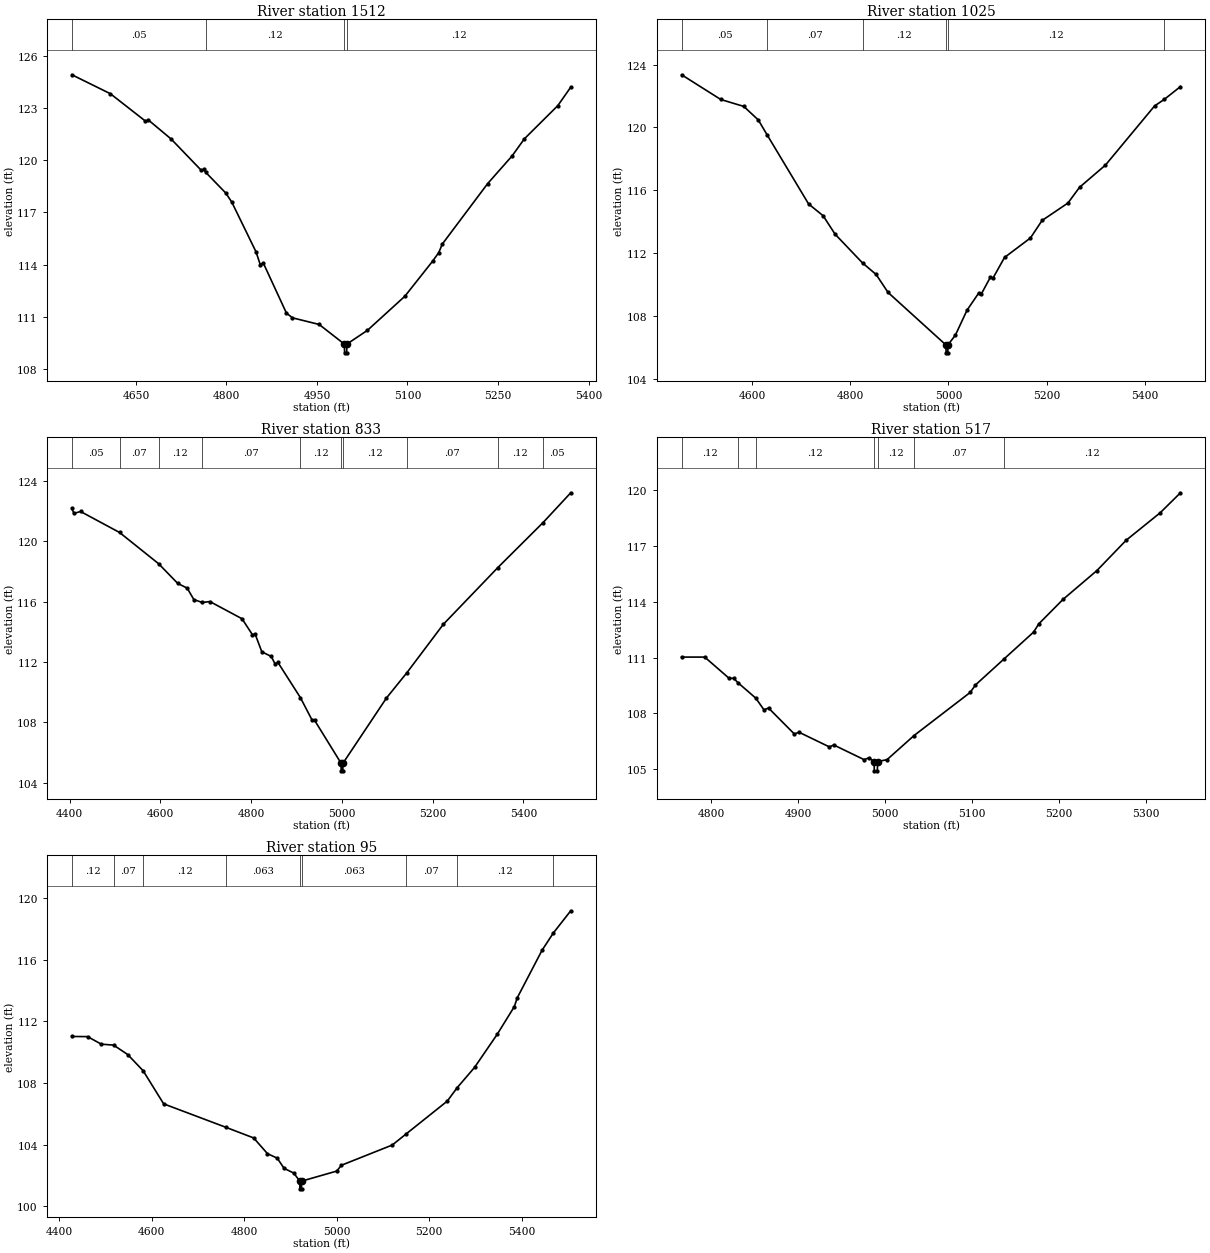
Type RM Length L Ch R = 1 ,1512    ,487,487,487
BEGIN DESCRIPTION:
TRIB 1 TO PAYTON BRANCH 3.0
END DESCRIPTION:
XS GIS Cut Line= 3
      2539571.52     13441276.87        2540025.       13441325.
      2540390.95     13441266.61
#Sta/Elev= 30
    4544   124.9  4607.8  123.81  4665.8  122.24  4670.8   122.3  4708.4  121.21
  4758.4  119.41  4763.4  119.46  4765.9  119.29  4798.9  118.11    4809  117.58
  4849.2  114.72    4856     114  4861.1  114.09  4899.5  111.21  4909.5  110.94
  4953.7  110.56  4995.5  109.43  4995.8  108.93  4999.3  108.93  4999.5  109.43
  5033.6  110.22  5095.7  112.18  5141.8   114.2  5151.9  114.69  5157.8  115.18
  5232.9  118.65  5273.4  120.24  5293.7  121.22  5349.2  123.13  5370.6  124.19
#Mann= 4 ,-1 , 0
    4544     .05       0  4765.9     .12       0  4995.5     .05       0
  4999.5     .12       0
Bank Sta=4995.5,4999.5
XS Rating Curve= 0 ,0
Exp/Cntr=0.3,0.1

Type RM Length L Ch R = 1 ,1025    ,192,192,192
BEGIN DESCRIPTION:
TRIB 1 TO PAYTON BRANCH 2.0
END DESCRIPTION:
XS GIS Cut Line= 3
      2539621.06     13441573.76        2540125.       13441775.
      2540559.82     13441589.94
#Sta/Elev= 30
  4456.9  123.35  4536.5  121.78  4583.3  121.34  4612.9  120.48  4630.9  119.53
  4715.3  115.14  4744.9  114.39  4769.2  113.22  4825.1  111.39  4852.7  110.66
  4876.9  109.52  4994.8  106.18  4995.1  105.68  4998.6  105.68  4998.8  106.18
  5014.1  106.81  5037.7  108.39  5061.3  109.47  5066.8  109.42    5085  110.47
  5090.4  110.42    5114  111.74  5166.8  112.98  5190.4  114.09  5243.1   115.2
  5266.7   116.2  5319.4  117.61  5419.4  121.37  5439.3  121.79  5472.1   122.6
#Mann= 6 ,-1 , 0
  4456.9     .05       0  4630.9     .07       0  4825.1     .12       0
  4994.8     .05       0  4998.8     .12       0  5439.3     .07       0
Bank Sta=4994.8,4998.8
XS Rating Curve= 0 ,0
Exp/Cntr=0.3,0.1

Type RM Length L Ch R = 1 ,833     ,316,316,316
BEGIN DESCRIPTION:
Mapping XS 4f8b8ab5
END DESCRIPTION:
XS GIS Cut Line= 4
      2539626.26     13441667.51      2540000.56     13441950.52
      2540115.13     13441968.61      2540621.83     13441881.36
#Sta/Elev= 30
  4404.8  122.18  4409.2  121.85  4423.8  121.98  4509.7  120.59  4595.8  118.52
  4638.1  117.21  4658.9   116.9  4673.5  116.14  4692.1  115.95  4708.9  116.01
  4779.7  114.87  4802.5  113.82  4808.8  113.84  4823.3  112.68  4844.2  112.37
  4852.4  111.88  4858.7  111.98  4908.4  109.64  4934.5  108.13  4939.6  108.14
  4998.1  105.29  4998.3  104.79  5001.8  104.79  5002.1  105.29  5098.1  109.62
  5142.7  111.28  5223.3   114.5  5343.1  118.25  5443.3  121.25  5504.2  123.22
#Mann= 10 ,-1 , 0
  4404.8     .05       0  4509.7     .07       0  4595.8     .12       0
  4692.1     .07       0  4908.4     .12       0  4998.1     .05       0
  5002.1     .12       0  5142.7     .07       0  5343.1     .12       0
  5443.3     .05       0
Bank Sta=4998.1,5002.1
XS Rating Curve= 0 ,0
Exp/Cntr=0.3,0.1

Type RM Length L Ch R = 1 ,517     ,422,422,422
BEGIN DESCRIPTION:
Mapping XS 4f360eae
END DESCRIPTION:
XS GIS Cut Line= 3
      2539999.44      13442185.4      2540227.33     13442246.17
      2540551.42     13442153.27
#Sta/Elev= 30
  4766.3  111.03  4792.8  111.03  4820.8  109.89    4826  109.89  4830.8  109.66
  4851.5  108.82  4860.9  108.19  4866.1  108.29  4895.8  106.89    4901  106.99
  4935.9   106.2  4941.1   106.3    4976  105.51  4981.2  105.61  4987.4  105.41
  4987.6  104.91  4991.1  104.91  4991.4  105.41  5002.2  105.51  5033.3  106.81
  5097.8  109.13  5103.8  109.53  5136.4  110.92  5170.5  112.37  5176.6  112.82
  5204.3  114.13  5243.2  115.68    5277  117.32  5315.9  118.79  5339.3  119.87
#Mann= 7 ,-1 , 0
  4766.3     .12       0  4830.8     .07       0  4851.5     .12       0
  4987.4     .05       0  4991.4     .12       0  5033.3     .07       0
  5136.4     .12       0
Bank Sta=4987.4,4991.4
XS Rating Curve= 0 ,0
Exp/Cntr=0.3,0.1

Type RM Length L Ch R = 1 ,95      ,0,0,0
BEGIN DESCRIPTION:
TRIB 1 TO PAYTON BRANCH 1.0
END DESCRIPTION:
XS GIS Cut Line= 4
      2539971.16     13442221.86      2540251.11     13442634.62
      2540452.93      13442622.9      2540639.66     13442293.91
#Sta/Elev= 30
  4427.2  111.02    4461  111.01  4490.9  110.52  4517.3  110.46  4547.8  109.85
  4581.2   108.8  4625.7  106.65  4760.3  105.13  4820.4  104.44  4850.3  103.42
  4871.3  103.13  4886.2  102.47  4907.2  102.16  4920.2  101.64  4920.4  101.14
  4923.9  101.14  4924.2  101.64    5000  102.29  5010.3  102.67  5120.2  103.98
    5149  104.67  5239.3  106.83  5260.7   107.7  5298.2  109.01  5347.5  111.17
  5384.4  112.96  5390.7  113.53  5444.1   116.6  5468.7  117.73  5506.4  119.17
#Mann= 9 ,-1 , 0
  4427.2     .12       0  4517.3     .07       0  4581.2     .12       0
  4760.3    .063       0  4920.2     .05       0  4924.2    .063       0
    5149     .07       0  5260.7     .12       0  5468.7     .07       0
Bank Sta=4920.2,4924.2
XS Rating Curve= 0 ,0
Exp/Cntr=0.3,0.1

Chan Stop Cuts=-1
Use User Specified Reach Order=0
Composite Channel Slope=5