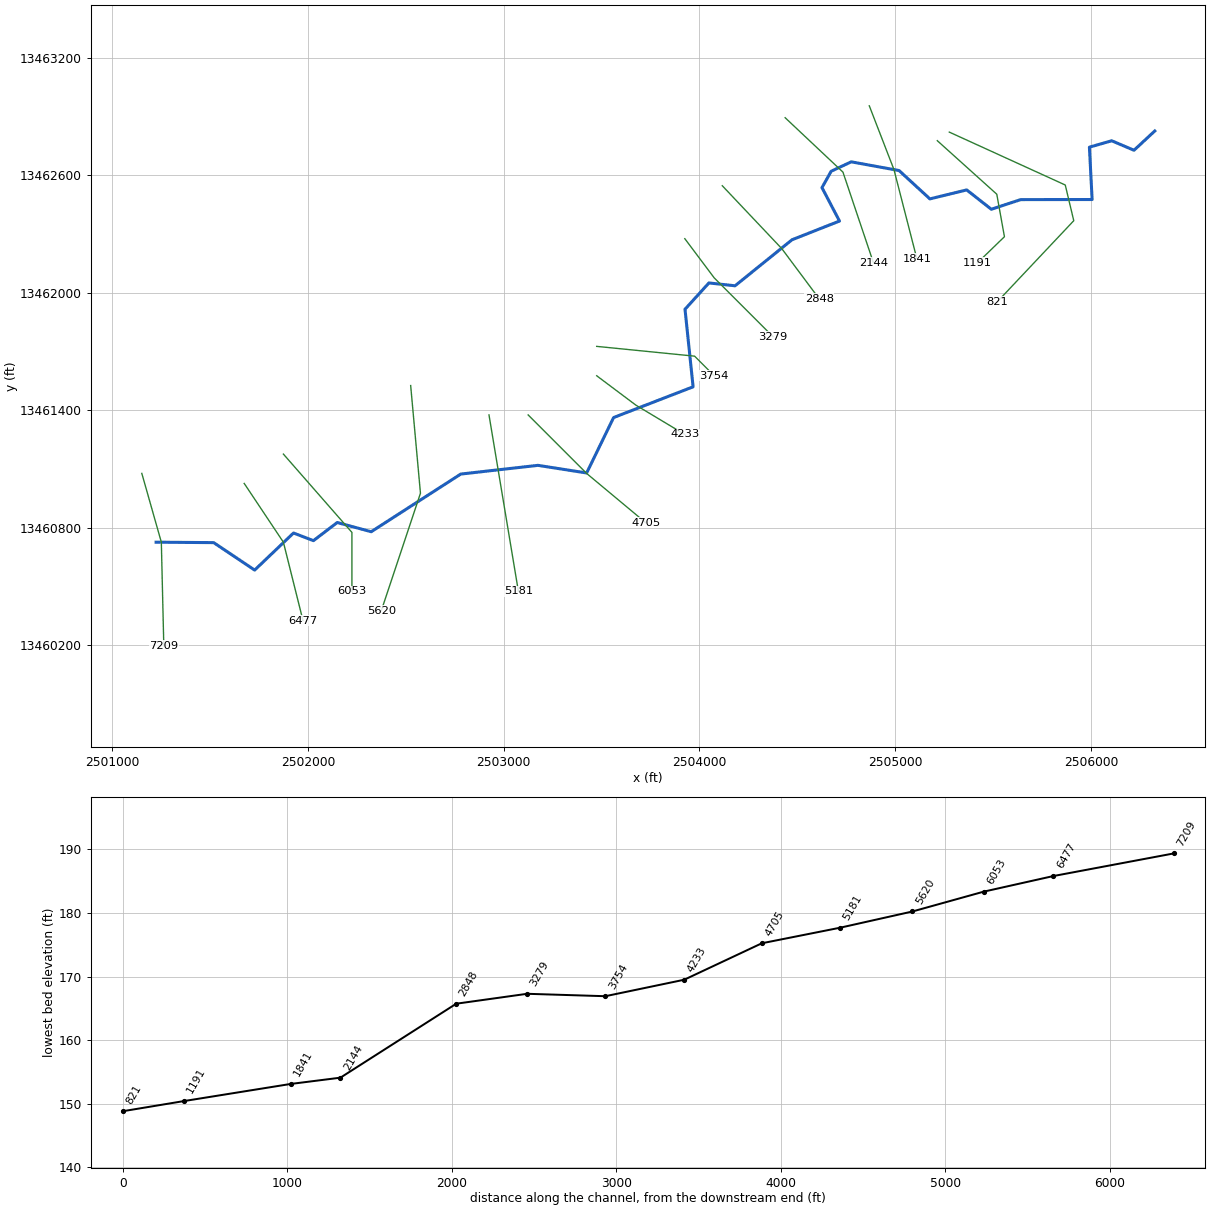
--- TRIB 1 TO PERDIDO CREEK.prj (project) ---

Proj Title=TRIB 1 TO PERDIDO CREEK Base Level Engineering
Current Plan=p01
Default Exp/Contr=0.3,0.1
English Units
Geom File=g01
Flow File=f01
Plan File=p01
Y Axis Title=Elevation
X Axis Title(PF)=Main Channel Distance
X Axis Title(XS)=Station
BEGIN DESCRIPTION:
TRIB 1 TO PERDIDO CREEK
END DESCRIPTION:
DSS Export Rating Curves= 0
DSS Export Rating Curve Sorted= 0
DSS Export Volume Flow Curves= 0
DXF OffsetX= 0
DXF OffsetY= 0
DXF ScaleX= 1
DXF ScaleY= 10

--- TRIB 1 TO PERDIDO CREEK.p01 (plan) ---

Plan Title=Multiple Run
Short Identifier=Multiple
Geom File=g01
Flow File=f01
Subcritical Flow
K Sum by GR= 0
Std Step Tol= 0.01
Critical Tol= 0.01
Num of Std Step Trials= 20
Max Error Tol= 0.3
Flow Tol Ratio= 0.001
Split Flow NTrial= 30
Split Flow Tol= 0.02
Split Flow Ratio= 0.02
Log Output Level= 0
Friction Slope Method= 1
Unsteady Friction Slope Method= 2
Unsteady Bridges Friction Slope Method= 1
Parabolic Critical Depth
Global Vel Dist=  1 , 1 , 1
Global Log Level= 0
CheckData=True
Encroach Param= -1, 0, 0, 0
BEGIN DESCRIPTION:
Multiple Run
END DESCRIPTION:

--- TRIB 1 TO PERDIDO CREEK.f01 (steady flow) ---

Flow Title=Multiple
Number of Profiles=7
Profile Names=10-year,25-year,50-year,1pct_min,100-year,1pct_plu,500-year
River Rch & RM= TRIB 1 TO PERDID,Reach-1,7209
     396     620     817     522    1042    2079    1675
River Rch & RM= TRIB 1 TO PERDID,Reach-1,4705
     609     979    1311     851    1698    3388    2814
Boundary for River Rch & Prof#=TRIB 1 TO PERDID,Reach-1,1
Up Type=0
Dn Type=3
Dn Slope=0.005
Boundary for River Rch & Prof#=TRIB 1 TO PERDID,Reach-1,2
Up Type=0
Dn Type=3
Dn Slope=0.005
Boundary for River Rch & Prof#=TRIB 1 TO PERDID,Reach-1,3
Up Type=0
Dn Type=3
Dn Slope=0.005
Boundary for River Rch & Prof#=TRIB 1 TO PERDID,Reach-1,4
Up Type=0
Dn Type=3
Dn Slope=0.005
Boundary for River Rch & Prof#=TRIB 1 TO PERDID,Reach-1,5
Up Type=0
Dn Type=3
Dn Slope=0.005
Boundary for River Rch & Prof#=TRIB 1 TO PERDID,Reach-1,6
Up Type=0
Dn Type=3
Dn Slope=0.005
Boundary for River Rch & Prof#=TRIB 1 TO PERDID,Reach-1,7
Up Type=0
Dn Type=3
Dn Slope=0.005

--- TRIB 1 TO PERDIDO CREEK.g01 (geometry) ---

Geom Title=Existing Conditions
Program Version=4.10

River Reach=TRIB 1 TO PERDID,Reach-1
Reach XY= 30
        2501225.       13460725.      2501519.07     13460722.76
      2501728.34      13460582.6      2501926.65     13460771.84
       2502028.4     13460732.84      2502149.96     13460825.49
       2502323.5     13460778.47      2502780.86     13461072.93
        2503175.     13461117.44      2503423.75     13461078.45
      2503561.37     13461361.55      2503967.33     13461518.48
      2503926.05     13461914.57      2504048.18     13462048.96
      2504181.61     13462034.43      2504472.57     13462269.48
      2504714.96       13462365.      2504625.54     13462535.69
      2504672.39      13462619.3      2504774.99     13462667.47
      2505019.15     13462622.94      2505176.63     13462478.13
      2505364.52     13462524.06      2505490.22     13462425.25
      2505640.22     13462474.48      2506005.09     13462474.95
      2505991.21     13462742.23      2506104.89     13462775.09
      2506218.97     13462726.56        2506325.       13462825.

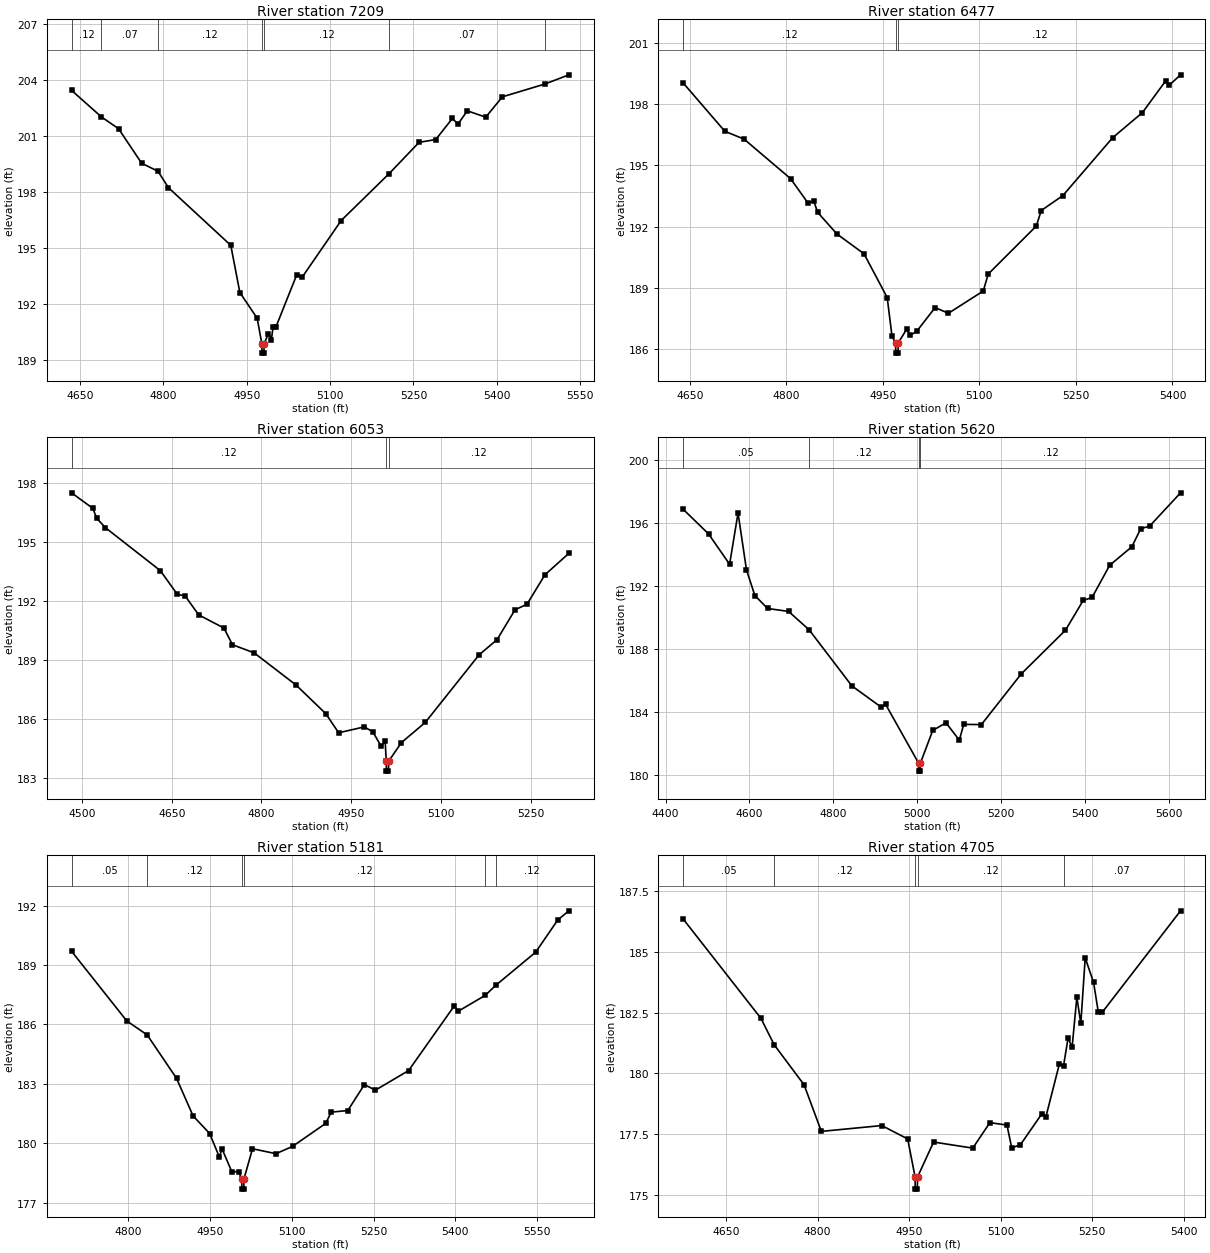
Type RM Length L Ch R = 1 ,7209    ,732,732,732
BEGIN DESCRIPTION:
TRIB 1 TO PERDIDO CREEK 14.0
END DESCRIPTION:
XS GIS Cut Line= 3
      2501152.02     13461076.45      2501251.69     13460725.01
      2501264.31     13460195.46
#Sta/Elev= 30
  4634.7  203.46  4688.6  202.03  4719.4   201.4  4760.9  199.55  4790.3  199.12
  4809.1  198.24  4921.3  195.15  4937.6  192.62  4968.8  191.24  4977.2  189.87
  4977.5  189.37    4981  189.37  4981.2  189.87  4989.1  190.42  4994.3  190.09
  4997.4  190.77  5002.5  190.77    5040  193.57    5050  193.45    5120  196.48
  5206.5     199  5260.1  200.67  5290.1  200.82  5320.1  201.95  5330.1  201.65
    5347  202.36  5380.1  202.02  5410.1  203.11  5486.9   203.8  5529.7  204.29
#Mann= 7 ,-1 , 0
  4634.7     .12       0  4688.6     .07       0  4790.3     .12       0
  4977.2     .05       0  4981.2     .12       0  5206.5     .07       0
  5486.9     .12       0
Bank Sta=4977.2,4981.2
XS Rating Curve= 0 ,0
Exp/Cntr=0.3,0.1

Type RM Length L Ch R = 1 ,6477    ,424,424,424
BEGIN DESCRIPTION:
TRIB 1 TO PERDIDO CREEK 13.0
END DESCRIPTION:
XS GIS Cut Line= 3
      2501674.97     13461025.04        2501875.       13460725.
        2501975.     13460325.01
#Sta/Elev= 30
  4639.7  199.03  4704.3  196.67  4734.4  196.28  4806.5  194.35  4833.5  193.16
  4842.6  193.25  4848.6   192.7  4878.6  191.64  4920.7  190.67  4956.7  188.53
  4964.2  186.63  4969.8  186.31    4970  185.81  4973.5  185.81  4973.8  186.31
  4986.8  186.97  4992.8  186.68  5002.9  186.89  5031.2  188.04  5051.8  187.76
    5106  188.85  5113.7  189.68  5188.4  192.03  5196.1  192.79  5229.7  193.52
    5307  196.35  5353.3  197.58  5389.4  199.13  5394.6  198.91  5412.6  199.43
#Mann= 3 ,-1 , 0
  4639.7     .12       0  4969.8     .05       0  4973.8     .12       0
Bank Sta=4969.8,4973.8
XS Rating Curve= 0 ,0
Exp/Cntr=0.3,0.1

Type RM Length L Ch R = 1 ,6053    ,433,433,433
BEGIN DESCRIPTION:
TRIB 1 TO PERDIDO CREEK 12.0
END DESCRIPTION:
XS GIS Cut Line= 3
      2501874.99     13461175.01        2502225.       13460775.
        2502225.     13460475.02
#Sta/Elev= 30
  4482.5  197.51  4518.1  196.72  4524.7  196.21    4539  195.74    4631  193.55
  4659.5  192.34  4672.3  192.27  4695.1   191.3  4737.3  190.63  4751.6  189.78
  4787.7  189.37  4857.9  187.73  4907.7  186.27  4929.1   185.3  4971.8   185.6
    4986  185.36  5000.3  184.61  5006.9  184.86  5008.7  183.85  5008.9  183.35
  5012.4  183.35  5012.7  183.85    5034   184.8    5074  185.83    5164  189.27
    5194  190.04    5224  191.56    5244  191.84    5274  193.34    5314  194.43
#Mann= 3 ,-1 , 0
  4482.5     .12       0  5008.7     .05       0  5012.7     .12       0
Bank Sta=5008.7,5012.7
XS Rating Curve= 0 ,0
Exp/Cntr=0.3,0.1

Type RM Length L Ch R = 1 ,5620    ,439,439,439
BEGIN DESCRIPTION:
TRIB 1 TO PERDIDO CREEK 11.0
END DESCRIPTION:
XS GIS Cut Line= 3
        2502525.     13461525.05        2502575.       13460975.
      2502374.99     13460374.97
#Sta/Elev= 30
  4442.2  196.87  4502.5  195.31  4552.7  193.38  4572.8  196.64  4592.9  193.02
  4612.9  191.39  4643.1  190.57  4693.3  190.38  4742.2  189.21  4843.9  185.65
  4914.2  184.29  4924.2  184.48  5003.1  180.73  5003.3  180.23  5006.8  180.23
  5007.1  180.73  5036.7  182.82  5068.3   183.3  5099.9   182.2  5110.5   183.2
  5152.6  183.19  5247.5  186.41  5352.9  189.19  5395.1  191.08  5416.2  191.27
  5458.3  193.32    5511  194.49  5532.1  195.64  5553.2   195.8    5627  197.92
#Mann= 4 ,-1 , 0
  4442.2     .05       0  4742.2     .12       0  5003.1     .05       0
  5007.1     .12       0
Bank Sta=5003.1,5007.1
XS Rating Curve= 0 ,0
Exp/Cntr=0.3,0.1

Type RM Length L Ch R = 1 ,5181    ,476,476,476
BEGIN DESCRIPTION:
TRIB 1 TO PERDIDO CREEK 10.0
END DESCRIPTION:
XS GIS Cut Line= 3
      2502925.01     13461374.95        2502975.       13461075.
      2503075.01     13460474.97
#Sta/Elev= 30
  4695.9   189.7  4797.2  186.18  4834.7  185.47  4888.5  183.28  4918.9  181.38
  4949.3  180.49    4967  179.31  4972.1  179.71  4989.9  178.56  5002.5  178.56
  5008.1  178.18  5008.4  177.68  5011.9  177.68  5012.1  178.18  5027.9  179.72
    5071  179.47  5101.4  179.84  5162.2     181  5172.3  181.57  5202.7  181.65
  5233.2  182.96  5253.4  182.68  5314.3  183.67  5397.9  186.93  5405.5  186.67
  5454.9  187.47  5473.9  187.97  5547.4  189.65    5588  191.28  5608.3  191.74
#Mann= 6 ,-1 , 0
  4695.9     .05       0  4834.7     .12       0  5008.1     .05       0
  5012.1     .12       0  5454.9     .07       0  5473.9     .12       0
Bank Sta=5008.1,5012.1
XS Rating Curve= 0 ,0
Exp/Cntr=0.3,0.1

Type RM Length L Ch R = 1 ,4705    ,472,472,472
BEGIN DESCRIPTION:
TRIB 1 TO PERDIDO CREEK 9.0
END DESCRIPTION:
XS GIS Cut Line= 3
      2503124.97     13461375.03        2503425.       13461075.
      2503724.99     13460825.01
#Sta/Elev= 30
  4579.8  186.36  4707.1  182.27  4728.8  181.18  4777.8  179.53  4806.1  177.61
  4905.1  177.85  4947.5   177.3  4959.7  175.73  4959.9  175.23  4963.4  175.23
  4963.7  175.73    4990  177.17  5054.2  176.92  5082.2  177.97  5110.2  177.87
    5118  176.93  5132.3  177.06  5167.5  178.34    5174  178.21  5196.1  180.39
  5202.9  180.31  5210.4  181.47  5216.9  181.07  5224.7  183.14  5231.2  182.06
  5238.4  184.76  5252.1  183.75  5259.9  182.52  5266.4  182.52  5394.6   186.7
#Mann= 5 ,-1 , 0
  4579.8     .05       0  4728.8     .12       0  4959.7     .05       0
  4963.7     .12       0  5202.9     .07       0
Bank Sta=4959.7,4963.7
XS Rating Curve= 0 ,0
Exp/Cntr=0.3,0.1

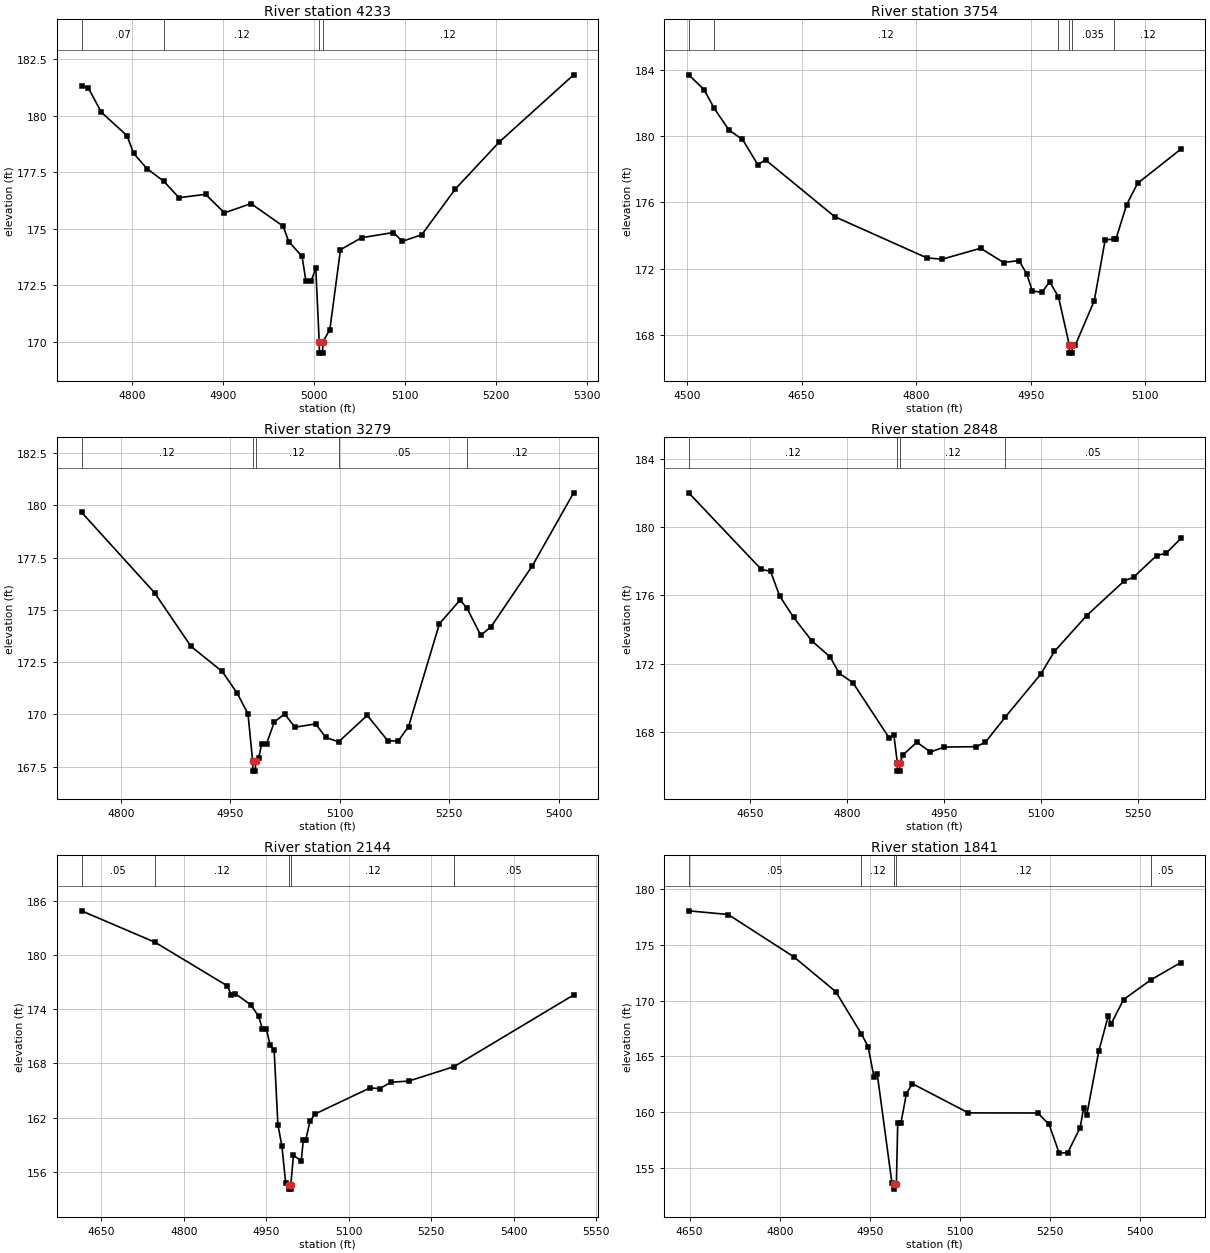
Type RM Length L Ch R = 1 ,4233    ,479,479,479
BEGIN DESCRIPTION:
TRIB 1 TO PERDIDO CREEK 8.0
END DESCRIPTION:
XS GIS Cut Line= 3
      2503474.99       13461575.        2503675.       13461425.
      2503925.04     13461274.98
#Sta/Elev= 30
  4744.1   181.3  4751.4  181.24    4766  180.15  4794.1  179.12  4801.4  178.34
    4816  177.66  4834.6   177.1  4851.4  176.37  4880.6  176.52  4901.4   175.7
  4930.6  176.11    4966  175.11  4972.2  174.43  4986.8  173.77    4991   172.7
    4997   172.7  5001.9  173.25  5005.7  169.99    5006  169.49  5009.5  169.49
  5009.7  169.99  5017.4  170.53  5029.1  174.07  5052.4   174.6  5087.4  174.83
  5097.1  174.44  5118.5  174.73  5155.4  176.75    5204  178.84  5285.7  181.81
#Mann= 4 ,-1 , 0
  4744.1     .07       0  4834.6     .12       0  5005.7     .05       0
  5009.7     .12       0
Bank Sta=5005.7,5009.7
XS Rating Curve= 0 ,0
Exp/Cntr=0.3,0.1

Type RM Length L Ch R = 1 ,3754    ,475,475,475
BEGIN DESCRIPTION:
TRIB 1 TO PERDIDO CREEK 7.0
END DESCRIPTION:
XS GIS Cut Line= 3
      2503474.96       13461725.        2503975.       13461675.
      2504075.03     13461574.97
#Sta/Elev= 30
  4502.3   183.7  4522.4  182.81  4535.5  181.69  4555.1  180.36  4572.7   179.8
  4592.8  178.27  4602.8  178.57  4693.3  175.14  4813.9  172.65    4834  172.57
  4884.2  173.23  4914.4  172.37  4934.5  172.49  4944.5   171.7  4952.1  170.64
  4964.6  170.58  4974.7   171.2  4986.2   170.3  5000.3   167.4  5000.6   166.9
  5004.1   166.9  5004.3   167.4  5008.4   167.4  5033.1  170.07  5047.3  173.74
  5058.9  173.78  5061.4  173.79  5075.5  175.87  5089.7  177.15  5146.3  179.21
#Mann= 6 ,-1 , 0
  4502.3     .05       0  4535.5     .12       0  4986.2    .035       0
  5000.3    .035       0  5004.3    .035       0  5058.9     .12       0
Bank Sta=5000.3,5004.3
XS Rating Curve= 0 ,0
Exp/Cntr=0.3,0.1

Type RM Length L Ch R = 1 ,3279    ,431,431,431
BEGIN DESCRIPTION:
TRIB 1 TO PERDIDO CREEK 6.0
END DESCRIPTION:
XS GIS Cut Line= 3
      2503925.01     13462274.98        2504075.       13462075.
      2504374.97     13461775.03
#Sta/Elev= 30
  4746.1  179.67  4846.1  175.82  4896.1  173.25  4938.8  172.05  4959.6     171
  4974.2  170.01  4980.5  167.78  4980.8  167.28  4984.3  167.28  4984.5  167.78
  4988.8  167.91    4993  168.59  4999.6  168.59  5010.2  169.63  5024.4  170.02
  5038.5  169.38  5066.8  169.54  5080.9  168.89  5098.3  168.68  5137.5  169.95
  5165.8  168.73  5179.9  168.72  5194.1  169.41  5236.5  174.34  5264.8  175.47
    5274  175.09  5293.1  173.78  5307.2  174.19  5363.8  177.11  5420.3   180.6
#Mann= 5 ,-1 , 0
  4746.1     .12       0  4980.5     .05       0  4984.5     .12       0
  5098.3     .05       0    5274     .12       0
Bank Sta=4980.5,4984.5
XS Rating Curve= 0 ,0
Exp/Cntr=0.3,0.1

Type RM Length L Ch R = 1 ,2848    ,704,704,704
BEGIN DESCRIPTION:
Mapping XS a45a292d
END DESCRIPTION:
XS GIS Cut Line= 3
      2504116.32     13462545.42      2504420.13     13462224.25
      2504611.07     13461968.21
#Sta/Elev= 30
  4555.2     182  4667.6  177.52  4681.8  177.41  4695.9  175.97  4717.4  174.72
  4745.7  173.34    4774   172.4  4788.1  171.44  4809.2   170.9  4865.8  167.64
  4872.7  167.83    4878  166.22  4878.2  165.72  4881.7  165.72    4882  166.22
  4886.9  166.68  4908.3  167.41  4929.3  166.84  4950.8  167.13  4999.9  167.15
  5014.4  167.41  5044.8  168.87  5099.9  171.39  5121.1  172.72    5171  174.82
  5229.2  176.85  5243.8  177.07  5279.2  178.33  5293.8  178.46  5316.7  179.33
#Mann= 4 ,-1 , 0
  4555.2     .12       0    4878     .05       0    4882     .12       0
  5044.8     .05       0
Bank Sta=4878,4882
XS Rating Curve= 0 ,0
Exp/Cntr=0.3,0.1

Type RM Length L Ch R = 1 ,2144    ,303,303,303
BEGIN DESCRIPTION:
Mapping XS 28b35d87
END DESCRIPTION:
XS GIS Cut Line= 3
      2504437.47     13462892.68      2504732.63     13462614.88
      2504888.87     13462150.49
#Sta/Elev= 30
  4613.7  184.87  4747.5  181.39  4879.2  176.56    4886  175.55  4893.3  175.71
  4921.7  174.47  4935.8  173.21  4942.7  171.83    4950   171.8  4956.8     170
  4964.1  169.48    4971  161.22  4978.3  158.81  4985.2  154.71  4990.5  154.58
  4990.7  154.08  4994.2  154.08  4994.5  154.58  4999.3  157.81  5013.5  157.22
  5017.2  159.52  5021.6  159.52  5029.5  161.62  5038.4  162.39  5138.2  165.27
  5156.1  165.21  5177.2  165.91  5208.8  166.03  5291.3  167.63    5509  175.56
#Mann= 5 ,-1 , 0
  4613.7     .05       0  4747.5     .12       0  4990.5     .05       0
  4994.5     .12       0  5291.3     .05       0
Bank Sta=4990.5,4994.5
XS Rating Curve= 0 ,0
Exp/Cntr=0.3,0.1

Type RM Length L Ch R = 1 ,1841    ,650,650,650
BEGIN DESCRIPTION:
Mapping XS ced0305c
END DESCRIPTION:
XS GIS Cut Line= 3
      2504867.16     13462953.46      2504993.04      13462627.9
       2505110.1     13462172.66
#Sta/Elev= 30
  4648.4  178.06  4714.1  177.73  4823.2  173.94  4893.3   170.8  4935.5  167.05
    4947  165.88  4956.8  163.14  4962.2  163.43  4986.7  153.62  4990.1  153.59
  4990.4  153.09  4994.1  153.59  4996.3  158.98  5001.5  158.98  5010.8  161.67
  5020.7  162.55    5114  159.93  5229.5  159.92  5248.3  158.89    5265  156.32
  5279.2  156.36  5299.9  158.59  5305.8  160.39  5310.9  159.72  5330.9  165.45
  5346.5  168.59  5351.6  167.92  5372.2   170.1  5417.8  171.87  5467.5  173.42
#Mann= 5 ,-1 , 0
  4648.4     .05       0  4935.5     .12       0  4990.1     .05       0
  4994.1     .12       0  5417.8     .05       0
Bank Sta=4990.1,4994.1
XS Rating Curve= 0 ,0
Exp/Cntr=0.3,0.1

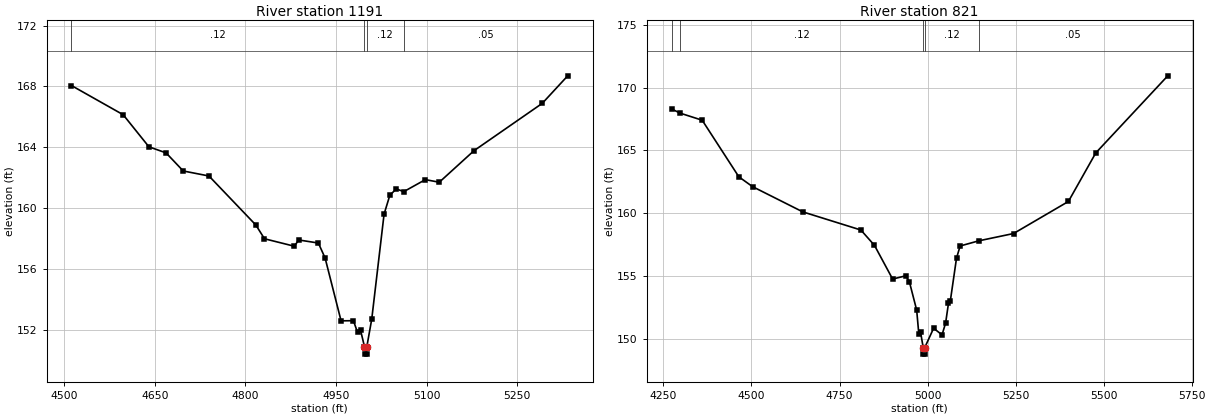
Type RM Length L Ch R = 1 ,1191    ,370,370,370
BEGIN DESCRIPTION:
Mapping XS c0e7f71a
END DESCRIPTION:
XS GIS Cut Line= 4
      2505214.42     13462775.45      2505518.22     13462502.03
      2505557.28     13462285.02      2505419.18     13462151.23
#Sta/Elev= 30
  4512.2  168.06  4597.8  166.14  4640.4  164.03  4668.8  163.63  4697.2  162.44
  4739.8  162.11  4817.5  158.88  4831.7  157.98    4881  157.49  4888.5   157.9
  4920.9   157.7  4932.1  156.71  4958.5  152.58  4978.9  152.59  4985.7  151.83
  4990.8  151.95  4997.2  150.89  4997.4  150.39  5000.9  150.39  5001.2  150.89
  5009.3   152.7  5029.7   159.6  5039.3  160.85    5050  161.26  5062.3  161.08
    5098  161.87  5121.1   161.7  5178.4  163.77  5291.6  166.89  5333.7   168.7
#Mann= 4 ,-1 , 0
  4512.2     .12       0  4997.2     .05       0  5001.2     .12       0
  5062.3     .05       0
Bank Sta=4997.2,5001.2
XS Rating Curve= 0 ,0
Exp/Cntr=0.3,0.1

Type RM Length L Ch R = 1 ,821     ,0,0,0
BEGIN DESCRIPTION:
Mapping XS 0ed2433a
END DESCRIPTION:
XS GIS Cut Line= 4
      2505275.76     13462819.24      2505867.91     13462549.11
      2505911.31     13462366.82      2505519.62      13461951.4
#Sta/Elev= 30
  4272.9   168.3  4297.6  167.96    4360   167.4  4464.1   162.9  4502.9  162.12
  4645.8  160.11  4810.6  158.67  4849.2  157.45  4900.8  154.77  4938.3  155.03
  4948.5  154.54  4969.1   152.3  4975.1  150.42  4980.2  150.54  4987.7   149.3
  4987.9   148.8  4991.4   148.8  4991.7   149.3  5017.2  150.86  5041.1  150.33
  5051.3  151.28  5059.4  152.84  5064.5     153  5082.2  156.43  5092.5   157.4
  5145.5  157.81  5244.2  158.39    5400  160.94  5477.7   164.8  5682.1  170.93
#Mann= 5 ,-1 , 0
  4272.9     .05       0  4297.6     .12       0  4987.7     .05       0
  4991.7     .12       0  5145.5     .05       0
Bank Sta=4987.7,4991.7
XS Rating Curve= 0 ,0
Exp/Cntr=0.3,0.1

Chan Stop Cuts=-1
Use User Specified Reach Order=0
Composite Channel Slope=5