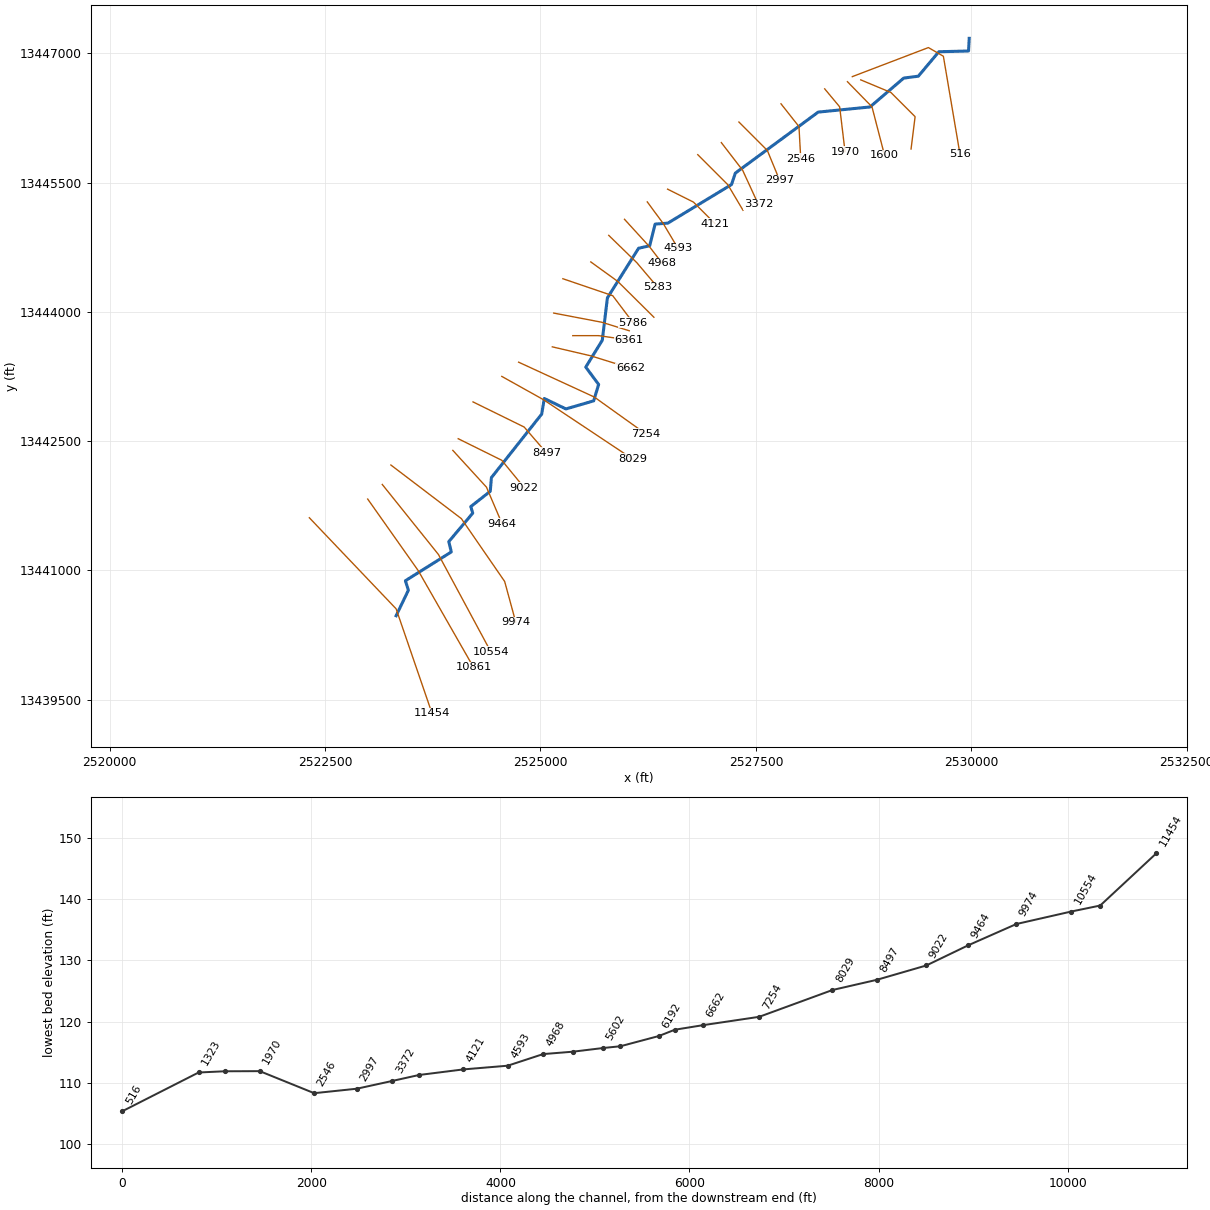
--- TRIB 1 TO ROAD CREEK.prj (project) ---

Proj Title=TRIB 1 TO ROAD CREEK Base Level Engineering
Current Plan=p01
Default Exp/Contr=0.3,0.1
English Units
Geom File=g01
Flow File=f01
Plan File=p01
Y Axis Title=Elevation
X Axis Title(PF)=Main Channel Distance
X Axis Title(XS)=Station
BEGIN DESCRIPTION:
TRIB 1 TO ROAD CREEK
END DESCRIPTION:
DSS Export Rating Curves= 0
DSS Export Rating Curve Sorted= 0
DSS Export Volume Flow Curves= 0
DXF OffsetX= 0
DXF OffsetY= 0
DXF ScaleX= 1
DXF ScaleY= 10

--- TRIB 1 TO ROAD CREEK.p01 (plan) ---

Plan Title=Multiple Run
Program Version=4.10
Short Identifier=Multiple
Geom File=g01
Flow File=f01
Subcritical Flow
K Sum by GR= 0
Std Step Tol= 0.01
Critical Tol= 0.01
Num of Std Step Trials= 20
Max Error Tol= 0.3
Flow Tol Ratio= 0.001
Split Flow NTrial= 30
Split Flow Tol= 0.02
Split Flow Ratio= 0.02
Log Output Level= 0
Friction Slope Method= 1
Unsteady Friction Slope Method= 2
Unsteady Bridges Friction Slope Method= 1
Parabolic Critical Depth
Global Vel Dist= 1 , 1 , 1
Global Log Level= 0
CheckData=True
Encroach Param=-1 ,0,0, 0
BEGIN DESCRIPTION:
Multiple Run
END DESCRIPTION:
Computation Interval=1HOUR
Output Interval=1HOUR
Run HTab= 0
Run UNet= 0
Run PostProcess= 0
Run WQNet= 0
UNET Theta= 1
UNET Theta Warmup= 1
UNET ZTol= 0.02
UNET ZSATol= 0.05
UNET MxIter= 20
UNET MaxInSteps= 0
UNET DtIC= 0
UNET DtMin= 0
UNET MaxCRTS= 20
UNET WFStab= 2
UNET SFStab= 1
UNET WFX= 1
UNET SFX= 1
UNET DSS MLevel= 4
UNET DZMax Abort= 100
UNET Convert EG Bridges= 0
UNET Use Existing IB Tables=-1
UNET Froude Reduction=False
UNET Froude Limit= 1
UNET Froude Power= 10
UNET Time Slicing=0,0, 5
UNET Junction Losses=0
Instantaneous Interval=1HOUR
Write IC File= 0
Write IC File at Sim End=0
Echo Input=False
Echo Parameters=False
Echo Output=False
Write Detailed= 0
WQ AD Non Conservative
WQ ULTIMATE=-1
WQ Max Comp Step=1HOUR
WQ Output Interval=15MIN
WQ Output Selected Increments= 0
WQ Output face flow=0
WQ Output face velocity=0
WQ Output face area=0
WQ Output face dispersion=0
WQ Output cell volume=0
WQ Output cell surface area=0
WQ Output cell continuity=0
WQ Output cumulative cell continuity=0
WQ Output face conc=0
WQ Output face dconc_dx=0
WQ Output face courant=0
WQ Output face peclet=0
WQ Output face adv mass=0
WQ Output face disp mass=0
WQ Output cell mass=0
WQ Output cell source sink temp=0
WQ Output cell source sink nsm=0
WQ Output MaxMinRange=-1
WQ Daily Max Min Mean=-1
WQ Daily Range=0
WQ Daily Time=0
WQ Create Restart=0
WQ Fixed Restart=0
WQ System Summary=0
WQ Use Fixed Temperature=0
Sorting and Armoring Iterations= 10
XS Update Threshold= 0.02
Hydraulics Update Threshold= 0.02
Energy Slope Method= 1
Volume Change Method= 0
XS Weighting Method= 0
Number of US Weighted Cross Sections= 1
Number of DS Weighted Cross Sections= 1
Upstream XS Weight=0.25
Main XS Weight=0.5
Downstream XS Weight=0.25
Number of DS XS's Weighted with US Boundary= 1
Upstream Boundary Weight= 1
Weight of XSs Associated with US Boundary= 0
Number of US XS's Weighted with DS Boundary= 1
Downstream Boundary Weight= 0.5
Weight of XSs Associated with DS Boundary= 0.5
Sediment Output Level= 4
Mass or Volume Output= 0
Output Increment Type= 1
Profile and TS Output Increment= 10
XS Output Flag= 0
XS Output Increment= 10
Disregard all LS=0
Disregard all Conn=0
Disregard all Breaches=0
Disregard all Pumps=0

--- TRIB 1 TO ROAD CREEK.f01 (steady flow) ---

Flow Title=Multiple
Number of Profiles=7
Profile Names=10-year,25-year,50-year,1pct_min,100-year,1pct_plu,500-year
River Rch & RM= TRIB 1 TO ROAD C,Reach-1,11454
     694    1097    1452     929    1854    3698    2987
River Rch & RM= TRIB 1 TO ROAD C,Reach-1,6662
     819    1307    1741    1119    2233    4456    3637
River Rch & RM= TRIB 1 TO ROAD C,Reach-1,2997
    1047    1693    2275    1474    2942    5870    4870
Boundary for River Rch & Prof#=TRIB 1 TO ROAD C,Reach-1,1
Up Type=0
Dn Type=3
Dn Slope=0.005
Boundary for River Rch & Prof#=TRIB 1 TO ROAD C,Reach-1,2
Up Type=0
Dn Type=3
Dn Slope=0.005
Boundary for River Rch & Prof#=TRIB 1 TO ROAD C,Reach-1,3
Up Type=0
Dn Type=3
Dn Slope=0.005
Boundary for River Rch & Prof#=TRIB 1 TO ROAD C,Reach-1,4
Up Type=0
Dn Type=3
Dn Slope=0.005
Boundary for River Rch & Prof#=TRIB 1 TO ROAD C,Reach-1,5
Up Type=0
Dn Type=3
Dn Slope=0.005
Boundary for River Rch & Prof#=TRIB 1 TO ROAD C,Reach-1,6
Up Type=0
Dn Type=3
Dn Slope=0.005
Boundary for River Rch & Prof#=TRIB 1 TO ROAD C,Reach-1,7
Up Type=0
Dn Type=3
Dn Slope=0.005

--- TRIB 1 TO ROAD CREEK.g01 (geometry) ---

Geom Title=Existing Conditions
Program Version=4.10

River Reach=TRIB 1 TO ROAD C,Reach-1
Reach XY= 30
        2523325.       13440475.      2523467.17      13440771.6
      2523432.49     13440881.07      2523964.93       13441215.
      2523936.11     13441335.05      2524213.76       13441665.
      2524191.38      13441741.7      2524417.19     13441918.79
       2524430.4     13442077.68      2525013.89     13442814.68
      2525044.62     13442995.69      2525295.16     13442874.53
      2525617.26     13442968.45      2525674.77     13443158.99
      2525525.38     13443359.72      2525717.18     13443671.59
      2525776.53     13444163.12      2526138.41     13444739.09
      2526267.18     13444768.18      2526330.41     13445019.82
      2526477.69     13445030.37      2527216.84     13445478.38
      2527261.37     13445611.55       2528222.7     13446319.17
      2528823.54     13446378.54        2529215.     13446713.76
       2529384.7     13446735.74      2529622.55     13447019.53
      2529967.13     13447027.87        2529975.       13447175.

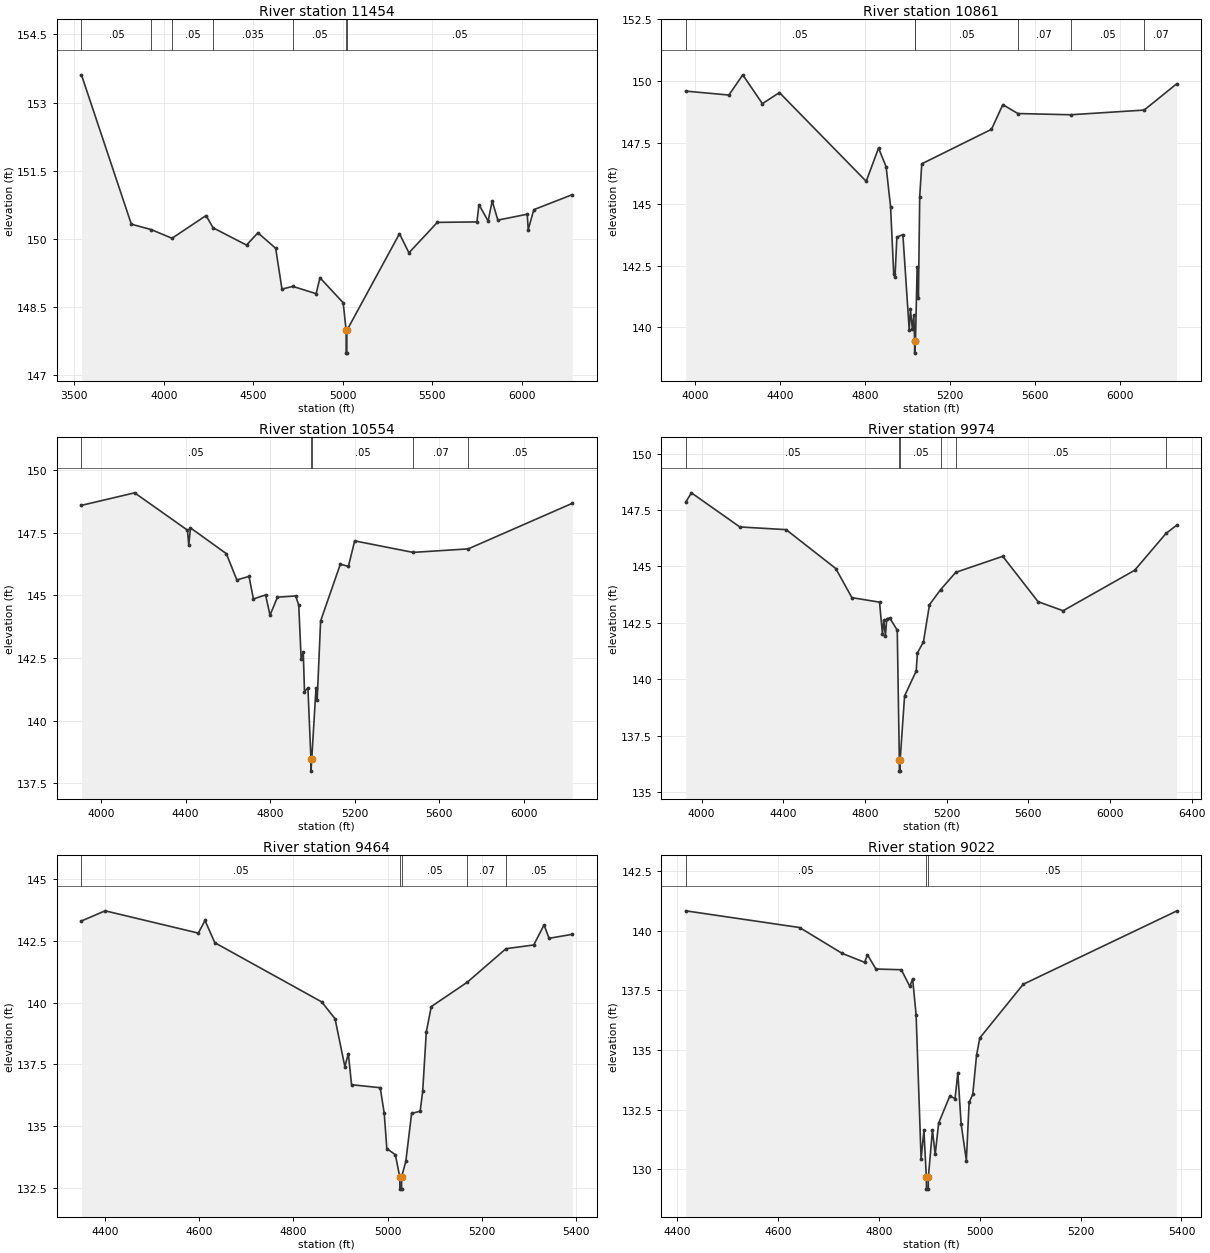
Type RM Length L Ch R = 1 ,11454   ,593,593,593
BEGIN DESCRIPTION:
TRIB 1 TO ROAD CREEK 20.0
END DESCRIPTION:
XS GIS Cut Line= 3
      2522317.82     13441611.97       2523324.8     13440555.08
      2523741.47     13439341.94
#Sta/Elev= 30
  3540.2  153.61    3819  150.32  3930.9   150.2  4046.3  150.01  4236.4  150.51
  4275.9  150.24  4462.5  149.86  4526.4  150.13  4625.4  149.79  4660.7  148.89
  4721.3  148.95  4851.6  148.79    4873  149.14  5002.7  148.59  5019.3  147.98
  5019.5  147.48    5023  147.48  5023.3  147.98  5317.3  150.11  5370.2  149.69
  5528.8  150.36  5750.2  150.37  5761.4  150.75  5812.7  150.39  5835.4  150.83
  5867.1  150.41  6031.4  150.54  6036.7   150.2    6068  150.64  6282.7  150.97
#Mann= 7 ,-1 , 0
  3540.2     .05       0  3930.9     .07       0  4046.3     .05       0
  4275.9    .035       0  4721.3     .05       0  5019.3     .05       0
  5023.3     .05       0
Bank Sta=5019.3,5023.3
XS Rating Curve= 0 ,0
Exp/Cntr=0.3,0.1

Type RM Length L Ch R = 1 ,10861   ,307,307,307
BEGIN DESCRIPTION:
Mapping XS 909b01c1
END DESCRIPTION:
XS GIS Cut Line= 3
      2522994.96     13441828.91      2523581.73     13440997.81
      2524223.24     13439875.82
#Sta/Elev= 30
  3956.2  149.59  4159.3  149.43  4224.6  150.25  4316.9  149.08    4397  149.53
  4805.6  145.93  4863.6  147.28  4899.3  146.52  4920.2   144.9    4935  142.18
  4941.1  142.05  4949.8  143.66  4978.1  143.77    5008   139.9  5013.7  140.73
  5022.9  139.95  5029.6   140.5  5033.3  139.46  5033.6  138.96  5037.3  139.46
  5045.4  142.44  5051.2  141.18  5057.4   145.3    5067  146.64  5395.2  148.04
  5448.5  149.04  5519.3  148.68  5767.6  148.63  6113.6  148.82    6266  149.88
#Mann= 6 ,-1 , 0
  3956.2     .05       0  5033.3     .05       0  5037.3     .05       0
  5519.3     .07       0  5767.6     .05       0  6113.6     .07       0
Bank Sta=5033.3,5037.3
XS Rating Curve= 0 ,0
Exp/Cntr=0.3,0.1

Type RM Length L Ch R = 1 ,10554   ,580,580,580
BEGIN DESCRIPTION:
Mapping XS fcc479b7
END DESCRIPTION:
XS GIS Cut Line= 3
      2523164.21     13441998.21       2523816.1     13441185.31
      2524422.39     13440059.03
#Sta/Elev= 30
  3907.4   148.6  4158.9   149.1  4408.6  147.61    4415     147    4423   147.7
  4592.6  146.67  4642.3  145.62  4699.9  145.76  4720.7  144.86  4778.3  145.02
  4799.1  144.21  4834.4  144.93  4920.7  144.98  4935.1  144.61  4946.4  142.47
  4956.5  142.73  4962.2  141.16  4978.4  141.31  4992.7  138.48  4992.9  137.98
  4996.7  138.48  5016.6   141.3  5022.2  140.83  5038.5  143.98  5131.8  146.25
  5169.9  146.16  5199.6  147.18  5475.7  146.72  5736.4  146.86  6228.5  148.68
#Mann= 5 ,-1 , 0
  3907.4     .05       0  4992.7     .05       0  4996.7     .05       0
  5475.7     .07       0  5736.4     .05       0
Bank Sta=4992.7,4996.7
XS Rating Curve= 0 ,0
Exp/Cntr=0.3,0.1

Type RM Length L Ch R = 1 ,9974    ,510,510,510
BEGIN DESCRIPTION:
Mapping XS 7a9c3ef3
END DESCRIPTION:
XS GIS Cut Line= 4
      2523264.04      13442223.9      2524081.73     13441601.98
      2524584.36     13440872.64      2524713.29     13440399.58
#Sta/Elev= 30
  3922.5  147.85  3950.3  148.26  4187.3  146.75    4414  146.63  4657.2  144.91
  4736.2  143.62  4871.4  143.42  4885.9  142.01  4892.2  142.63  4900.5  141.94
  4906.8  142.68  4921.3  142.72  4958.3  142.18  4968.5  136.44  4968.7  135.94
  4972.2  135.94  4972.5  136.44  4994.2  139.27    5051  140.37    5057  141.17
  5086.8  141.67  5116.2  143.31  5171.1  143.98  5244.8  144.74    5475  145.45
  5648.1  143.44  5770.5  143.04  6120.7  144.83  6274.1  146.46  6325.9  146.82
#Mann= 6 ,-1 , 0
  3922.5     .05       0  4968.5     .05       0  4972.5     .05       0
  5171.1     .07       0  5244.8     .05       0  6274.1    .035       0
Bank Sta=4968.5,4972.5
XS Rating Curve= 0 ,0
Exp/Cntr=0.3,0.1

Type RM Length L Ch R = 1 ,9464    ,442,442,442
BEGIN DESCRIPTION:
Mapping XS 96fec4e2
END DESCRIPTION:
XS GIS Cut Line= 3
      2523982.79     13442393.63      2524373.39     13441966.56
      2524555.56     13441539.77
#Sta/Elev= 30
  4349.7   143.3  4400.1  143.71    4598  142.81  4612.2  143.32  4633.1  142.42
  4860.1  140.03  4888.5  139.35  4909.4  137.41  4916.8  137.94  4923.6  136.68
  4984.5  136.56  4993.1  135.52  4998.5   134.1  5016.7  133.85    5026  132.96
  5026.3  132.46  5029.8  132.46    5030  132.96  5038.9  133.58  5051.2  135.52
  5069.4  135.61  5074.8  136.42  5082.4  138.81    5093  139.84  5169.2  140.82
  5251.8  142.18  5310.7  142.33  5332.6  143.14  5343.3   142.6  5392.5  142.76
#Mann= 5 ,-1 , 0
  4349.7     .05       0    5026     .05       0    5030     .05       0
  5169.2     .07       0  5251.8     .05       0
Bank Sta=5026,5030
XS Rating Curve= 0 ,0
Exp/Cntr=0.3,0.1

Type RM Length L Ch R = 1 ,9022    ,525,525,525
BEGIN DESCRIPTION:
Mapping XS abebaa50
END DESCRIPTION:
XS GIS Cut Line= 3
      2524045.29     13442529.05      2524550.48     13442279.06
      2524810.48     13441961.86
#Sta/Elev= 30
  4416.4  140.84  4642.3  140.14  4726.4  139.06  4771.3  138.68  4776.9     139
  4793.7   138.4  4844.2  138.37    4861  137.67  4866.6  137.99  4873.5  136.48
  4883.4  130.44    4889  131.63  4893.8  129.67  4894.1  129.17  4897.6  129.17
  4897.8  129.67  4905.9  131.64  4911.4  130.63  4918.2  131.94  4940.5  133.08
  4950.7  132.96  4956.3  134.05  4962.8  131.91  4973.2  130.37  4978.7  132.81
  4985.9  133.14  4993.4  134.78  4999.9  135.51    5086  137.76  5390.2  140.83
#Mann= 3 ,-1 , 0
  4416.4     .05       0  4893.8     .05       0  4897.8     .05       0
Bank Sta=4893.8,4897.8
XS Rating Curve= 0 ,0
Exp/Cntr=0.3,0.1

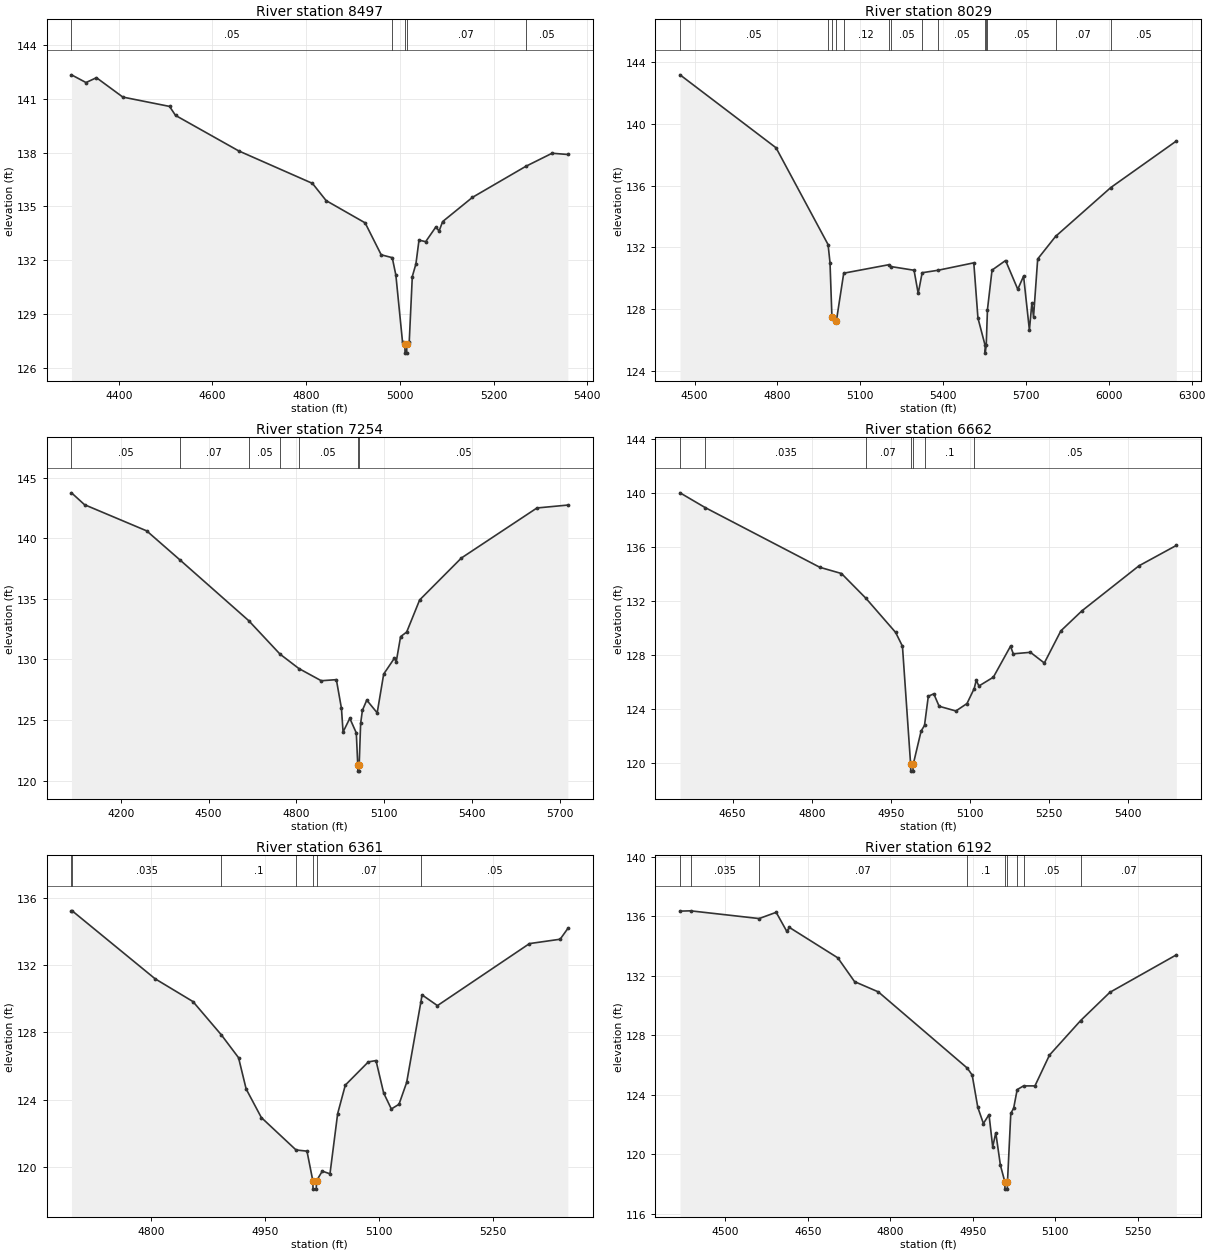
Type RM Length L Ch R = 1 ,8497    ,468,468,468
BEGIN DESCRIPTION:
Mapping XS 02a3243f
END DESCRIPTION:
XS GIS Cut Line= 3
      2524217.16     13442956.14      2524810.89     13442664.48
      2525070.63     13442363.19
#Sta/Elev= 30
  4299.2  142.33  4330.2   141.9  4352.5  142.17  4408.8  141.09  4508.5  140.57
  4521.2  140.07  4656.1  138.09  4813.5  136.28  4842.7  135.32  4925.9  134.08
  4960.2   132.3  4983.8  132.14  4991.5  131.17  5005.8  127.42  5010.8  127.32
  5011.1  126.82  5014.6  126.82  5014.8  127.32    5020  127.42  5026.6  131.09
  5034.3  131.79  5040.9  133.12  5055.1  133.03  5077.1  133.86  5083.7  133.62
  5091.3  134.15  5154.9   135.5  5268.8  137.23    5325  137.96  5358.5  137.89
#Mann= 5 ,-1 , 0
  4299.2     .05       0  4983.8     .07       0  5010.8     .05       0
  5014.8     .07       0  5268.8     .05       0
Bank Sta=5010.8,5014.8
XS Rating Curve= 0 ,0
Exp/Cntr=0.3,0.1

Type RM Length L Ch R = 1 ,8029    ,775,775,775
BEGIN DESCRIPTION:
Mapping XS 447e51e6
END DESCRIPTION:
XS GIS Cut Line= 3
        2524551.     13443252.23      2525032.73     13442983.15
      2526070.07     13442293.04
#Sta/Elev= 30
    4447  143.16  4794.8  138.44  4983.2  132.18  4990.2  131.01  4997.2  127.47
  5013.5  127.27  5039.9  130.33  5203.7  130.88  5210.7  130.76  5294.6  130.52
  5309.6  129.02    5324  130.36  5381.6  130.52    5511     131    5526  127.43
    5552  125.66  5552.3  125.16    5556  125.66  5560.5  127.98  5577.1  130.53
  5626.1  131.15  5670.3  129.29  5691.3  130.14  5712.4  126.65  5721.4  128.41
  5727.4  127.51  5742.4  131.25  5807.2  132.71  6007.2  135.87  6244.7  138.88
#Mann= 14 ,-1 , 0
    4447     .05       0  4983.2     .07       0  4997.2     .05       0
  5013.5     .07       0  5039.9     .12       0  5203.7      .1       0
  5210.7     .05       0    5324      .1       0  5381.6     .05       0
    5552     .07       0    5556     .05       0  5560.5     .05       0
  5807.2     .07       0  6007.2     .05       0
Bank Sta=4997.2,5013.5
XS Rating Curve= 0 ,0
Exp/Cntr=0.3,0.1

Type RM Length L Ch R = 1 ,7254    ,592,592,592
BEGIN DESCRIPTION:
Mapping XS 953e3b07
END DESCRIPTION:
XS GIS Cut Line= 3
      2524746.27     13443417.18      2525623.01     13443013.53
      2526216.34     13442589.11
#Sta/Elev= 30
  4032.1  143.75  4076.7  142.77  4288.9  140.61  4402.1  138.22  4637.2   133.2
    4744  130.44  4808.4  129.25    4885  128.24  4936.5  128.33  4953.9  125.96
  4959.4  124.01  4982.4  125.14  5004.6  123.93  5009.6  121.28    5010  120.78
  5014.1  120.78  5014.4  121.28  5019.4  124.72  5025.5   125.8  5040.3  126.64
  5075.9  125.59  5098.1  128.79  5134.9  130.11    5141  129.82  5155.8  131.88
  5176.6  132.26  5220.9  134.91  5363.4  138.37  5621.4   142.5  5726.8  142.74
#Mann= 7 ,-1 , 0
  4032.1     .05       0  4402.1     .07       0  4637.2     .05       0
    4744     .07       0  4808.4     .05       0  5009.6     .05       0
  5014.4     .05       0
Bank Sta=5009.6,5014.4
XS Rating Curve= 0 ,0
Exp/Cntr=0.3,0.1

Type RM Length L Ch R = 1 ,6662    ,301,301,301
BEGIN DESCRIPTION:
Mapping XS 99619a90
END DESCRIPTION:
XS GIS Cut Line= 3
      2525136.94     13443595.12      2525583.95     13443490.96
      2526043.99     13443347.74
#Sta/Elev= 30
  4550.4  140.01    4598  138.92  4815.4   134.5  4856.4  134.04  4902.7  132.21
  4959.1  129.68    4972  128.66  4987.5  119.92  4987.8  119.42    4992  119.42
  4992.4  119.92  5007.4  122.39  5013.8   122.8    5021  124.96  5031.4  125.14
  5041.5  124.22  5073.3  123.87  5094.3  124.42    5108  125.53  5111.8  126.13
    5117  125.72  5144.3  126.37  5176.8  128.66  5182.1   128.1  5214.6  128.21
  5240.9  127.42  5272.3   129.8  5312.2  131.28  5420.3  134.61  5491.2  136.12
#Mann= 7 ,-1 , 0
  4550.4     .05       0    4598    .035       0  4902.7     .07       0
  4987.5     .05       0  4992.4     .07       0  5013.8      .1       0
    5108     .05       0
Bank Sta=4987.5,4992.4
XS Rating Curve= 0 ,0
Exp/Cntr=0.3,0.1

Type RM Length L Ch R = 1 ,6361    ,169,169,169
BEGIN DESCRIPTION:
TRIB 1 TO ROAD CREEK 10.0
END DESCRIPTION:
XS GIS Cut Line= 3
      2525374.97       13443725.        2525675.       13443725.
      2526025.02       13443675.
#Sta/Elev= 30
  4695.1  135.23    4696  135.23  4805.1  131.19  4855.1  129.83  4892.6  127.84
  4915.1  126.49  4925.1  124.63  4945.1  122.93  4990.8     121  5005.2  120.93
  5012.9  119.17  5013.2  118.67  5017.4  118.67  5017.8  119.17  5025.4  119.74
  5035.5  119.58  5045.6  123.16  5055.7  124.86    5086  126.24  5096.1  126.32
  5106.2  124.39  5116.3  123.44  5126.4  123.72  5136.5  125.02  5155.3  129.83
  5156.7  130.23    5177  129.59  5298.2  133.28  5338.6  133.54  5348.7  134.18
#Mann= 7 ,-1 , 0
  4695.1     .07       0    4696    .035       0  4892.6      .1       0
  4990.8     .07       0  5012.9     .05       0  5017.8     .07       0
  5155.3     .05       0
Bank Sta=5012.9,5017.8
XS Rating Curve= 0 ,0
Exp/Cntr=0.3,0.1

Type RM Length L Ch R = 1 ,6192    ,406,406,406
BEGIN DESCRIPTION:
Mapping XS 2118a162
END DESCRIPTION:
XS GIS Cut Line= 3
      2525153.28     13443987.03      2525713.14     13443880.26
      2526030.45     13443781.43
#Sta/Elev= 30
  4417.7  136.33  4436.8  136.35  4561.5  135.83  4592.5  136.25  4611.6  134.98
  4616.7  135.23  4704.5  133.19    4735  131.59  4778.2   130.9  4939.8  125.78
  4948.8  125.31    4959  123.14  4969.2  122.05  4979.4  122.65  4986.1  120.48
  4991.7  121.43  5000.1  119.25  5008.1  118.14  5008.4  117.64  5012.6  117.64
    5013  118.14    5019  122.73  5024.2  123.08  5030.6  124.33  5042.1  124.58
  5062.9  124.58  5089.3  126.65  5145.9  128.97  5199.1  130.87    5320  133.39
#Mann= 9 ,-1 , 0
  4417.7     .07       0  4436.8    .035       0  4561.5     .07       0
  4939.8      .1       0  5008.1     .05       0    5013      .1       0
  5030.6     .07       0  5042.1     .05       0  5145.9     .07       0
Bank Sta=5008.1,5013
XS Rating Curve= 0 ,0
Exp/Cntr=0.3,0.1

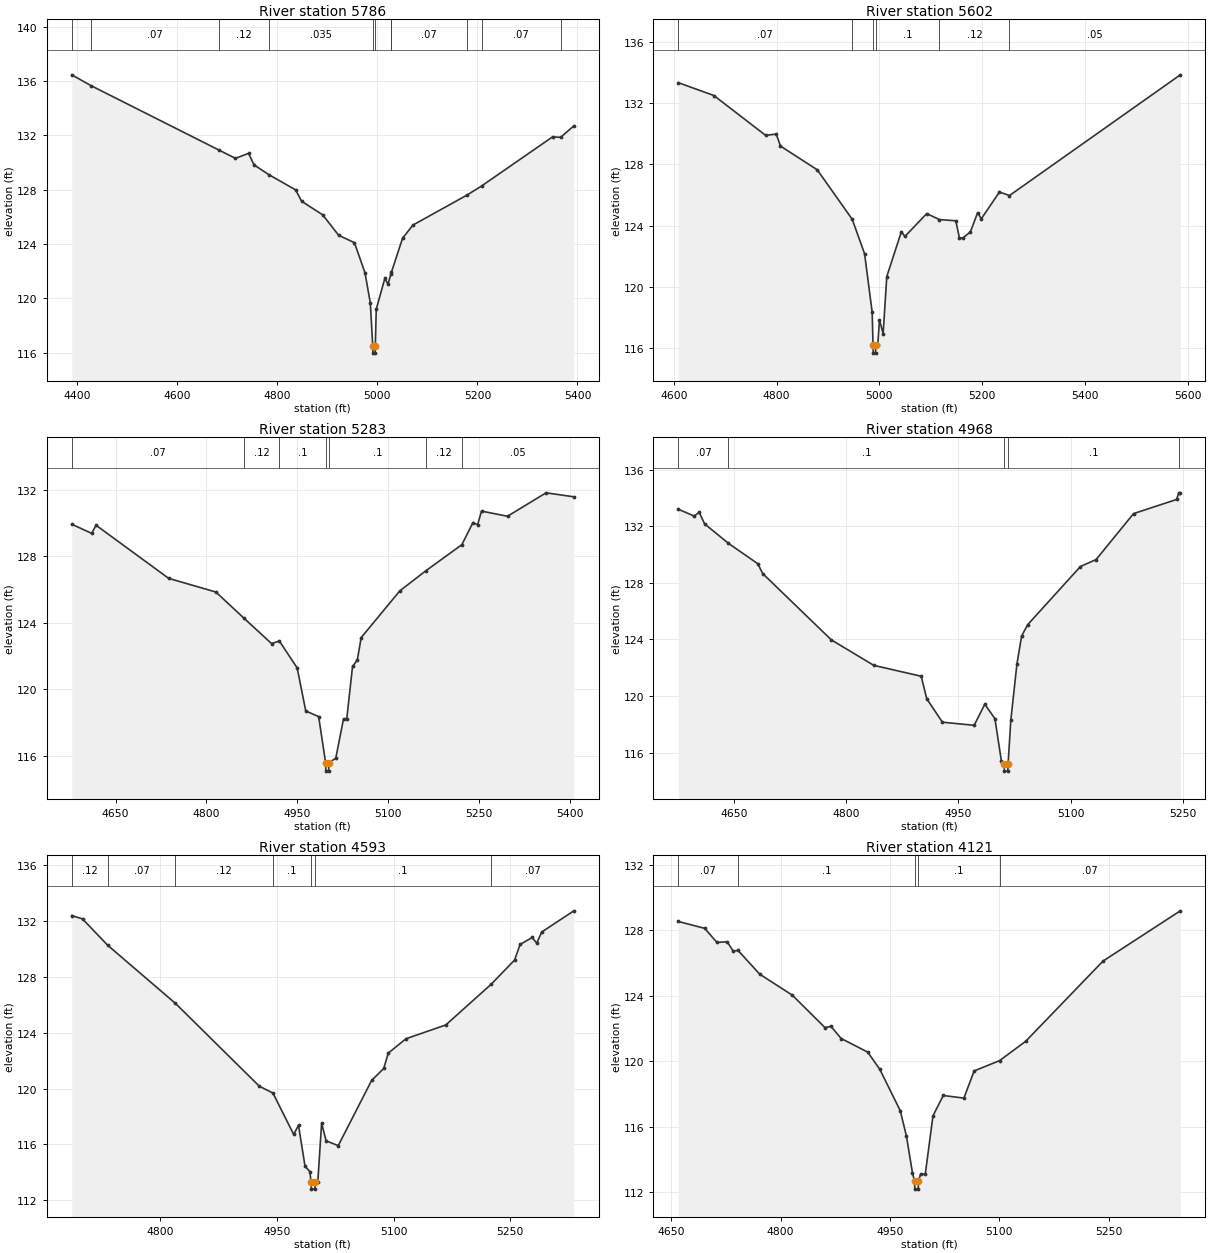
Type RM Length L Ch R = 1 ,5786    ,184,184,184
BEGIN DESCRIPTION:
TRIB 1 TO ROAD CREEK 9.0
END DESCRIPTION:
XS GIS Cut Line= 3
      2525260.06     13444385.46      2525838.36     13444188.57
      2526074.98     13443875.03
#Sta/Elev= 30
  4389.1  136.46  4427.3  135.67  4684.4   130.9  4716.4  130.31  4742.5  130.68
  4753.5  129.83  4782.7  129.12  4836.6  127.99  4848.6  127.15  4890.8  126.15
  4922.5  124.65  4954.2   124.1  4975.3  121.88  4985.9  119.67  4990.8  116.47
  4991.2  115.97  4995.5  115.97  4995.9  116.47  4997.8   119.2    5015  121.48
  5021.3  121.05  5027.4  121.83    5028  121.91  5050.4  124.43  5071.2   125.4
  5179.4  127.61  5208.5  128.28  5350.2  131.89  5366.3  131.86  5392.8   132.7
#Mann= 11 ,-1 , 0
  4389.1     .05       0  4427.3     .07       0  4684.4     .12       0
  4782.7    .035       0  4990.8    .035       0  4995.9    .035       0
  5027.4     .12       0    5028     .07       0  5179.4      .1       0
  5208.5     .07       0  5366.3     .05       0
Bank Sta=4990.8,4995.9
XS Rating Curve= 0 ,0
Exp/Cntr=0.3,0.1

Type RM Length L Ch R = 1 ,5602    ,319,319,319
BEGIN DESCRIPTION:
Mapping XS 13a54087
END DESCRIPTION:
XS GIS Cut Line= 3
      2525583.79     13444580.54      2525896.27     13444354.86
      2526316.21     13443938.66
#Sta/Elev= 30
  4608.6  133.34  4677.9   132.5  4778.5   129.9  4799.3  129.98  4807.5   129.2
    4879  127.65    4947  124.42  4971.1  122.17  4985.8  118.37  4987.6  116.18
    4988  115.68  4992.4  115.68  4992.7  116.18  4996.7  116.18  5000.1  117.85
  5007.2  116.95  5014.3  120.68  5042.6   123.6  5049.6   123.3    5092  124.79
  5116.7   124.4  5148.6  124.32  5155.7  123.18  5162.7  123.21  5176.9  123.59
    5191  124.85  5198.1  124.45  5233.5   126.2    5253  125.97  5585.3  133.85
#Mann= 6 ,-1 , 0
  4608.6     .07       0    4947      .1       0  4987.6     .05       0
  4992.7      .1       0  5116.7     .12       0    5253     .05       0
Bank Sta=4987.6,4992.7
XS Rating Curve= 0 ,0
Exp/Cntr=0.3,0.1

Type RM Length L Ch R = 1 ,5283    ,315,315,315
BEGIN DESCRIPTION:
Mapping XS 55be64ee
END DESCRIPTION:
XS GIS Cut Line= 3
      2525792.07     13444888.75      2526117.62     13444571.87
      2526360.36     13444285.78
#Sta/Elev= 30
  4577.6  129.94  4610.5  129.39  4617.7  129.88  4737.8  126.68  4815.7  125.86
  4861.6   124.3  4907.6  122.76  4920.6  122.91    4950  121.29  4964.2   118.7
  4985.5  118.36    4997  115.58  4997.4  115.08  5001.9  115.08  5002.3  115.58
  5013.8  115.86  5026.6  118.23  5031.9  118.23  5041.5  121.38  5049.3  121.76
  5055.8  123.12  5119.6  125.93    5163  127.15  5222.1  128.71  5240.4  130.04
  5248.1  129.91  5254.6  130.73  5297.5  130.42  5361.2  131.83  5407.1  131.59
#Mann= 7 ,-1 , 0
  4577.6     .07       0  4861.6     .12       0  4920.6      .1       0
    4997     .05       0  5002.3      .1       0    5163     .12       0
  5222.1     .05       0
Bank Sta=4997,5002.3
XS Rating Curve= 0 ,0
Exp/Cntr=0.3,0.1

Type RM Length L Ch R = 1 ,4968    ,375,375,375
BEGIN DESCRIPTION:
TRIB 1 TO ROAD CREEK 7.0
END DESCRIPTION:
XS GIS Cut Line= 3
      2525975.02     13445074.98      2526261.63      13444760.9
      2526412.65     13444565.45
#Sta/Elev= 30
  4574.8  133.21  4596.1  132.73  4602.8  132.99  4610.2  132.17    4642   130.8
  4681.2  129.36  4687.9  128.66  4779.8  123.97  4836.6  122.17  4900.1   121.4
  4907.5  119.81  4928.5  118.15    4971  117.93  4985.2  119.42  4998.8   118.4
  5007.4  115.42  5011.1  115.19  5011.5  114.69    5016  114.69  5016.4  115.19
  5020.1   118.3  5028.2  122.24  5034.5  124.24  5042.7  125.05  5113.3  129.16
  5134.2  129.65  5184.4   132.9    5242   133.9    5245  134.37    5247  134.37
#Mann= 5 ,-1 , 0
  4574.8     .07       0    4642      .1       0  5011.1     .05       0
  5016.4      .1       0    5245     .07       0
Bank Sta=5011.1,5016.4
XS Rating Curve= 0 ,0
Exp/Cntr=0.3,0.1

Type RM Length L Ch R = 1 ,4593    ,472,472,472
BEGIN DESCRIPTION:
TRIB 1 TO ROAD CREEK 6.0
END DESCRIPTION:
XS GIS Cut Line= 3
      2526239.02     13445277.28        2526425.       13445025.
      2526594.66     13444739.53
#Sta/Elev= 30
  4686.2   132.4    4700  132.16  4732.4  130.27  4819.4  126.11  4927.5  120.16
  4944.8  119.68  4971.5  116.71  4977.7  117.37  4986.1  114.43  4992.3  114.05
  4993.9  113.29  4994.3  112.79  4998.8  112.79  4999.2  113.29  5002.5  113.29
  5007.4  117.52  5013.2  116.25  5028.8  115.91  5071.7  120.58  5087.3  121.44
  5093.1  122.54  5115.9  123.57  5167.1  124.56  5225.1  127.46  5255.5  129.21
  5262.6  130.33  5278.2  130.83    5284  130.42  5290.4  131.22  5331.7  132.74
#Mann= 7 ,-1 , 0
  4686.2     .12       0  4732.4     .07       0  4819.4     .12       0
  4944.8      .1       0  4993.9     .05       0  4999.2      .1       0
  5225.1     .07       0
Bank Sta=4993.9,4999.2
XS Rating Curve= 0 ,0
Exp/Cntr=0.3,0.1

Type RM Length L Ch R = 1 ,4121    ,467,467,467
BEGIN DESCRIPTION:
TRIB 1 TO ROAD CREEK 5.0
END DESCRIPTION:
XS GIS Cut Line= 3
      2526474.99       13445425.        2526775.       13445275.
      2527025.02     13445024.98
#Sta/Elev= 30
  4659.5  128.53  4695.8  128.11  4712.6  127.25  4726.6  127.29    4735  126.72
  4741.6  126.76  4771.3  125.31    4816  124.03  4860.8  122.05  4869.1  122.12
  4883.1  121.38  4919.5  120.55  4936.2  119.49  4964.2  116.97  4972.6  115.43
  4980.9  113.18  4983.8  112.68  4984.2  112.18  4988.8  112.18  4989.2  112.68
  4992.1  113.09  4998.5  113.09  5009.1  116.66  5023.2   117.9  5051.5  117.74
  5065.6   119.4  5100.5  120.03  5136.3  121.21  5242.4  126.11  5348.5  129.18
#Mann= 5 ,-1 , 0
  4659.5     .07       0  4741.6      .1       0  4983.8     .05       0
  4989.2      .1       0  5100.5     .07       0
Bank Sta=4983.8,4989.2
XS Rating Curve= 0 ,0
Exp/Cntr=0.3,0.1

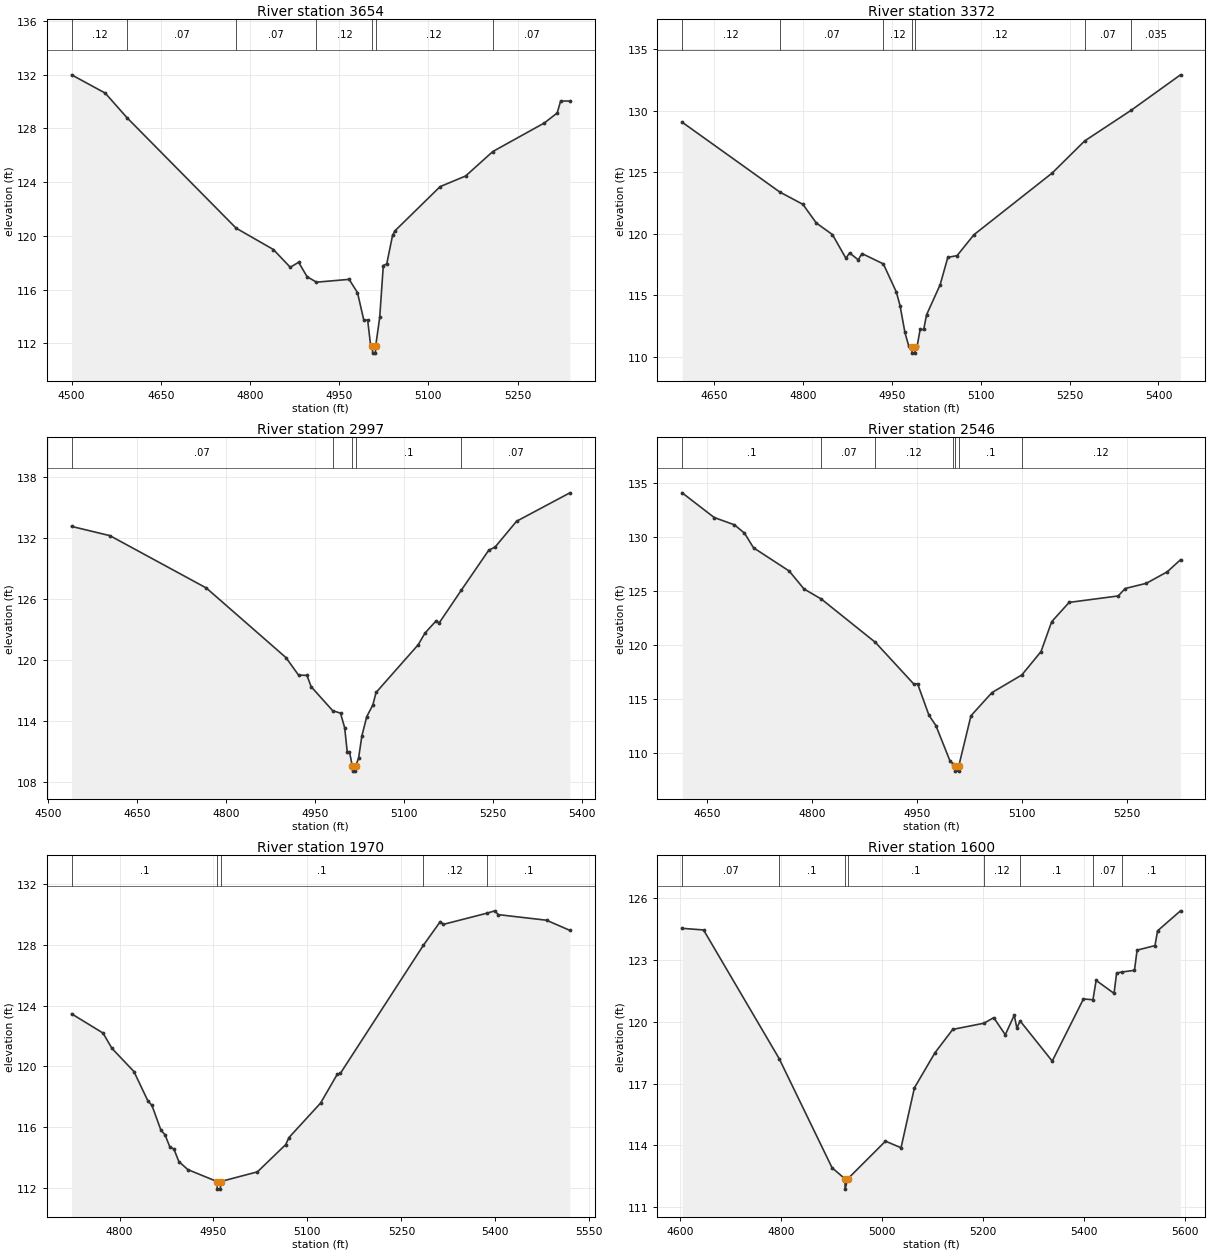
Type RM Length L Ch R = 1 ,3654    ,282,282,282
BEGIN DESCRIPTION:
TRIB 1 TO ROAD CREEK 4.0
END DESCRIPTION:
XS GIS Cut Line= 3
      2526825.01     13445824.99        2527175.       13445475.
      2527349.99     13445179.94
#Sta/Elev= 30
  4500.1  131.98  4556.7  130.62  4593.7  128.77  4776.8  120.57  4839.5  118.98
  4867.8  117.66  4881.9  118.03  4896.1  116.96  4911.9  116.55  4966.8  116.76
  4980.9  115.77  4991.5  113.73    4998  113.73  5002.9  111.87  5005.9  111.77
  5006.4  111.27    5011  111.27  5011.4  111.77  5018.3  113.94  5024.3  117.79
  5030.1  117.91  5039.9  120.04  5044.1  120.38  5119.8  123.66  5162.7  124.45
  5208.4  126.27  5295.2   128.4  5316.7  129.14  5322.5  130.03  5338.1  130.03
#Mann= 7 ,-1 , 0
  4500.1     .12       0  4593.7     .07       0  4776.8     .07       0
  4911.9     .12       0  5005.9     .05       0  5011.4     .12       0
  5208.4     .07       0
Bank Sta=5005.9,5011.4
XS Rating Curve= 0 ,0
Exp/Cntr=0.3,0.1

Type RM Length L Ch R = 1 ,3372    ,375,375,375
BEGIN DESCRIPTION:
Mapping XS eb6a240b
END DESCRIPTION:
XS GIS Cut Line= 3
      2527098.53      13445965.1      2527345.92     13445643.92
        2527528.     13445248.21
#Sta/Elev= 30
  4596.2  129.06  4760.9  123.39  4799.9  122.39  4822.6  120.87  4849.8  119.93
  4872.5  118.01  4878.8  118.44  4893.3  117.88  4899.6  118.39  4935.7  117.55
  4957.6  115.27  4963.9  114.16  4972.1  111.98  4978.4  110.91  4983.9   110.8
  4984.3   110.3    4989   110.3  4989.4   110.8  4992.9  110.91  4997.8  112.22
  5003.8  112.22  5008.6  113.41  5031.6  115.86  5044.5  118.08  5060.1  118.22
  5088.6  119.92  5220.6  124.93  5275.5  127.54  5353.6  130.02  5437.2  132.91
#Mann= 7 ,-1 , 0
  4596.2     .12       0  4760.9     .07       0  4935.7     .12       0
  4983.9     .05       0  4989.4     .12       0  5275.5     .07       0
  5353.6    .035       0
Bank Sta=4983.9,4989.4
XS Rating Curve= 0 ,0
Exp/Cntr=0.3,0.1

Type RM Length L Ch R = 1 ,2997    ,451,451,451
BEGIN DESCRIPTION:
Mapping XS 5a486de2
END DESCRIPTION:
XS GIS Cut Line= 3
      2527302.51     13446203.82      2527632.38     13445873.96
      2527774.92      13445528.4
#Sta/Elev= 30
  4539.7  133.15  4604.3  132.24  4766.9  127.08  4901.2  120.22  4922.5  118.49
  4936.6  118.47  4943.7  117.35  4979.8     115  4993.2  114.74  5000.2  113.31
  5004.5  110.93  5008.3  110.93  5013.1  109.53  5013.5  109.03  5018.2  109.03
  5018.7  109.53  5023.7  110.32  5029.2   112.5  5037.5  114.41  5047.7  115.55
  5053.1  116.78  5124.1  121.48  5135.7  122.64  5154.2  123.83  5159.6  123.64
  5196.6  126.84  5243.1   130.8  5253.9  131.12  5290.1  133.66    5380  136.46
#Mann= 5 ,-1 , 0
  4539.7     .07       0  4979.8      .1       0  5013.1     .05       0
  5018.7      .1       0  5196.6     .07       0
Bank Sta=5013.1,5018.7
XS Rating Curve= 0 ,0
Exp/Cntr=0.3,0.1

Type RM Length L Ch R = 1 ,2546    ,576,576,576
BEGIN DESCRIPTION:
Mapping XS 61fe5805
END DESCRIPTION:
XS GIS Cut Line= 3
      2527791.01     13446415.02      2527999.37     13446151.09
       2528020.2     13445776.13
#Sta/Elev= 30
  4614.6  134.13  4660.3  131.84  4689.2  131.16  4703.6  130.39  4716.5  129.03
  4767.5  126.87  4788.6  125.21  4813.6  124.26  4890.6  120.25  4945.2   116.4
  4950.9   116.4  4967.1  113.49    4977  112.53    4997  109.27  5001.2     109
  5004.2   108.8  5004.7   108.3  5009.4   108.3  5009.8   108.8  5027.1  113.44
  5057.1  115.59  5099.8  117.23  5127.2   119.4  5142.4  122.17  5167.3  123.96
  5237.4  124.56  5247.4  125.25  5277.5  125.73  5307.5   126.8  5326.4  127.92
#Mann= 7 ,-1 , 0
  4614.6      .1       0  4813.6     .07       0  4890.6     .12       0
  5001.2      .1       0  5004.2     .05       0  5009.8      .1       0
  5099.8     .12       0
Bank Sta=5004.2,5009.8
XS Rating Curve= 0 ,0
Exp/Cntr=0.3,0.1

Type RM Length L Ch R = 1 ,1970    ,370,370,370
BEGIN DESCRIPTION:
Mapping XS 43633515
END DESCRIPTION:
XS GIS Cut Line= 3
      2528297.96     13446588.62      2528471.59     13446380.26
      2528534.06     13445859.72
#Sta/Elev= 30
  4723.5  123.46  4773.7  122.19    4788  121.18  4823.1  119.65  4845.3  117.72
  4851.8  117.42  4866.1  115.79  4872.6  115.49  4880.4  114.68  4886.9  114.54
  4894.7  113.72    4909  113.19  4955.7   112.4  4956.1   111.9  4960.9   111.9
  4961.4   112.4  5020.2  113.04  5065.4  114.84  5070.5   115.3  5120.9  117.57
  5147.6  119.47  5152.7  119.54  5285.1  127.98  5312.1  129.54  5317.2  129.36
  5386.2  130.09  5399.4  130.25  5404.5     130  5481.7  129.63    5519  128.96
#Mann= 5 ,-1 , 0
  4723.5      .1       0  4955.7     .05       0  4961.4      .1       0
  5285.1     .12       0  5386.2      .1       0
Bank Sta=4955.7,4961.4
XS Rating Curve= 0 ,0
Exp/Cntr=0.3,0.1

Type RM Length L Ch R = 1 ,1600    ,277,277,277
BEGIN DESCRIPTION:
Mapping XS 9be03a42
END DESCRIPTION:
XS GIS Cut Line= 3
      2528561.89     13446671.91      2528846.59     13446380.26
      2528992.13     13445818.89
#Sta/Elev= 30
    4604  124.55  4646.4  124.47  4796.2  118.22    4901  112.92  4926.5  112.38
  4926.9  111.88  4932.2  112.38  5006.9  114.21  5037.7  113.89  5064.2   116.8
  5104.8   118.5  5140.2  119.64    5202  119.94  5221.4  120.21  5244.3  119.38
    5262  120.33  5267.2  119.71  5273.7  120.05  5337.3   118.1  5399.2  121.12
    5418  121.08  5424.3  122.02  5459.8  121.39  5464.9  122.38    5476  122.43
  5500.3  122.51  5505.5  123.49  5540.9  123.71  5546.1  124.43  5591.5   125.4
#Mann= 8 ,-1 , 0
    4604     .07       0  4796.2      .1       0  4926.5     .05       0
  4932.2      .1       0    5202     .12       0  5273.7      .1       0
    5418     .07       0    5476      .1       0
Bank Sta=4926.5,4932.2
XS Rating Curve= 0 ,0
Exp/Cntr=0.3,0.1

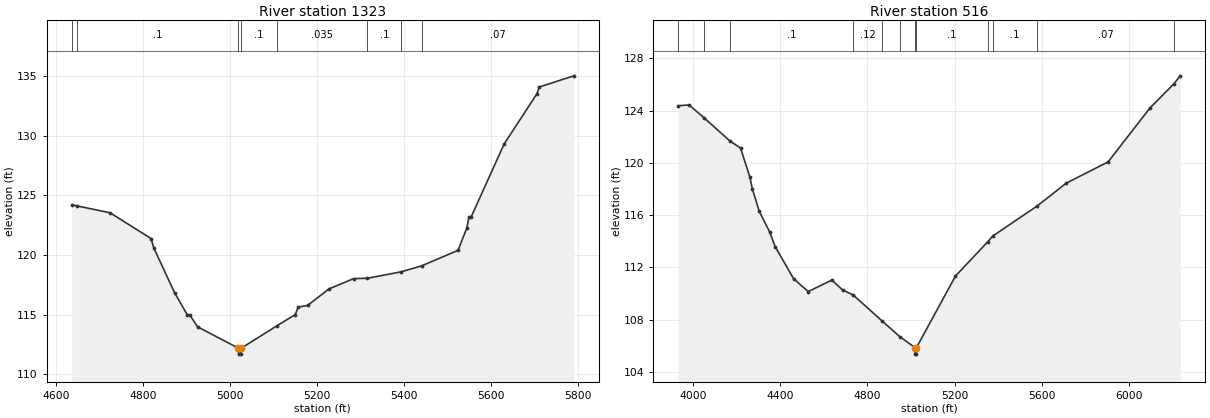
Type RM Length L Ch R = 1 ,1323    ,807,807,807
BEGIN DESCRIPTION:
Mapping XS 4f8e3873
END DESCRIPTION:
XS GIS Cut Line= 4
      2528716.75     13446692.97      2529065.75     13446547.12
        2529347.     13446265.87      2529300.13     13445890.89
#Sta/Elev= 30
  4635.6   124.2  4647.1  124.11  4723.5  123.53  4817.9  121.37  4824.1  120.58
  4871.7  116.84  4900.9  114.99  4906.4  114.98  4924.7  113.97  5018.5  112.18
    5019  111.68  5024.7  111.68  5025.2  112.18  5106.5  114.04  5149.2     115
  5156.2  115.63  5177.5  115.76  5226.9  117.15  5283.5  118.01  5315.1  118.04
  5392.5  118.58  5440.4  119.09  5523.3  120.38  5543.5  122.25  5548.6  123.19
  5553.7   123.2  5629.2  129.29  5704.7  133.51  5709.9  134.07  5789.5  135.01
#Mann= 8 ,-1 , 0
  4635.6     .07       0  4647.1      .1       0  5018.5     .05       0
  5025.2      .1       0  5106.5    .035       0  5315.1      .1       0
  5392.5    .035       0  5440.4     .07       0
Bank Sta=5018.5,5025.2
XS Rating Curve= 0 ,0
Exp/Cntr=0.3,0.1

Type RM Length L Ch R = 1 ,516     ,0,0,0
BEGIN DESCRIPTION:
TRIB 1 TO ROAD CREEK 1.0
END DESCRIPTION:
XS GIS Cut Line= 4
      2528618.28      13446730.6      2529501.47     13447067.82
      2529675.09     13446967.13      2529868.13     13445828.97
#Sta/Elev= 30
  3933.2  124.37  3982.7  124.43  4052.7  123.43  4169.4  121.68  4218.7  121.13
  4261.5   118.9  4272.7  118.01  4304.3  116.29  4352.3   114.7    4377  113.59
  4461.9  111.12  4529.1  110.14  4636.9  111.02  4686.4  110.26  4734.7  109.88
  4867.9  107.88    4949  106.68    5018  105.85  5018.5  105.35  5024.3  105.35
  5024.8  105.85  5203.2  111.32  5350.5  113.94  5374.9   114.4  5577.6  116.69
    5711  118.44    5903  120.07  6095.7  124.22  6202.7  126.02  6233.7  126.66
#Mann= 12 ,-1 , 0
  3933.2      .1       0  4052.7    .035       0  4169.4      .1       0
  4734.7     .12       0  4867.9     .07       0    4949      .1       0
    5018     .05       0  5024.8      .1       0  5350.5     .07       0
  5374.9      .1       0  5577.6     .07       0  6202.7    .035       0
Bank Sta=5018,5024.8
XS Rating Curve= 0 ,0
Exp/Cntr=0.3,0.1

Chan Stop Cuts=-1
Use User Specified Reach Order=0
Composite Channel Slope=5