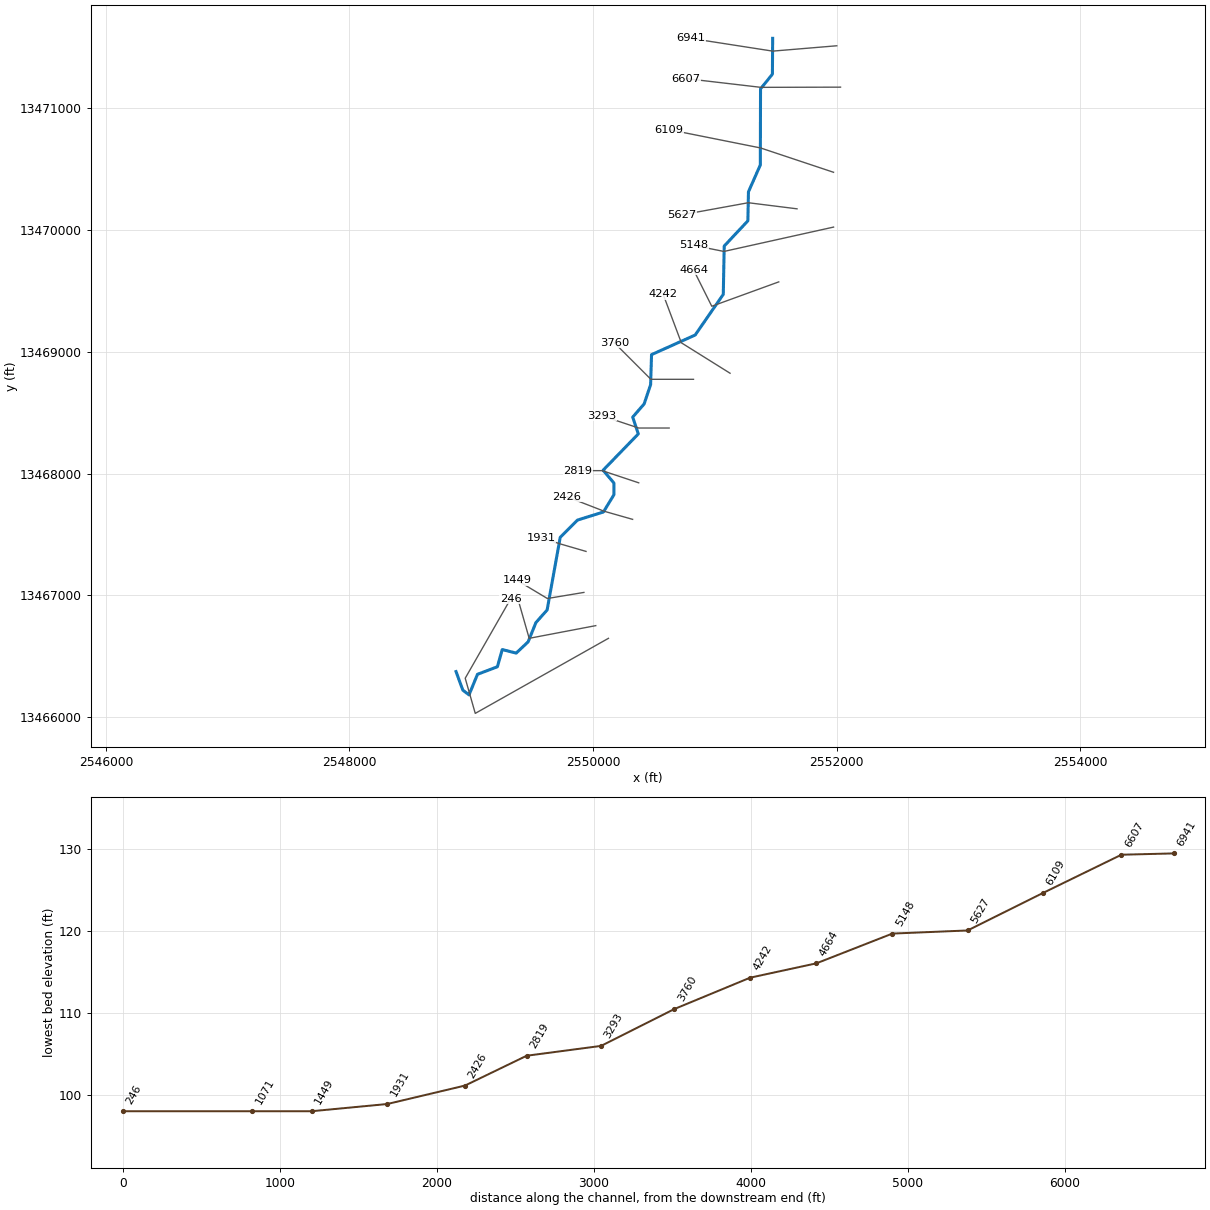
--- TRIB 1 TO TURKEY CREEK.prj (project) ---

Proj Title=TRIB 1 TO TURKEY CREEK Base Level Engineering
Current Plan=p01
Default Exp/Contr=0.3,0.1
English Units
Geom File=g01
Flow File=f01
Plan File=p01
Y Axis Title=Elevation
X Axis Title(PF)=Main Channel Distance
X Axis Title(XS)=Station
BEGIN DESCRIPTION:
TRIB 1 TO TURKEY CREEK
END DESCRIPTION:
DSS Export Rating Curves= 0
DSS Export Rating Curve Sorted= 0
DSS Export Volume Flow Curves= 0
DXF OffsetX= 0
DXF OffsetY= 0
DXF ScaleX= 1
DXF ScaleY= 10

--- TRIB 1 TO TURKEY CREEK.p01 (plan) ---

Plan Title=Multiple Run
Short Identifier=Multiple
Geom File=g01
Flow File=f01
Subcritical Flow
K Sum by GR= 0
Std Step Tol= 0.01
Critical Tol= 0.01
Num of Std Step Trials= 20
Max Error Tol= 0.3
Flow Tol Ratio= 0.001
Split Flow NTrial= 30
Split Flow Tol= 0.02
Split Flow Ratio= 0.02
Log Output Level= 0
Friction Slope Method= 1
Unsteady Friction Slope Method= 2
Unsteady Bridges Friction Slope Method= 1
Parabolic Critical Depth
Global Vel Dist=  1 , 1 , 1
Global Log Level= 0
CheckData=True
Encroach Param= -1, 0, 0, 0
BEGIN DESCRIPTION:
Multiple Run
END DESCRIPTION:

--- TRIB 1 TO TURKEY CREEK.f01 (steady flow) ---

Flow Title=Multiple
Program Version=4.10
Number of Profiles= 7
Profile Names=10-year,25-year,50-year,1pct_min,100-year,1pct_plu,500-year
River Rch & RM=TRIB 1 TO TURKEY,Reach-1         ,6941
     229     338     427     262     523    1044     774
River Rch & RM=TRIB 1 TO TURKEY,Reach-1         ,4242
     369     562     727     455     909    1813    1402
Boundary for River Rch & Prof#=TRIB 1 TO TURKEY,Reach-1         , 1
Up Type= 0
Dn Type= 3
Dn Slope=0.0004
Boundary for River Rch & Prof#=TRIB 1 TO TURKEY,Reach-1         , 2
Up Type= 0
Dn Type= 3
Dn Slope=0.0004
Boundary for River Rch & Prof#=TRIB 1 TO TURKEY,Reach-1         , 3
Up Type= 0
Dn Type= 3
Dn Slope=0.0004
Boundary for River Rch & Prof#=TRIB 1 TO TURKEY,Reach-1         , 4
Up Type= 0
Dn Type= 3
Dn Slope=0.0004
Boundary for River Rch & Prof#=TRIB 1 TO TURKEY,Reach-1         , 5
Up Type= 0
Dn Type= 3
Dn Slope=0.0004
Boundary for River Rch & Prof#=TRIB 1 TO TURKEY,Reach-1         , 6
Up Type= 0
Dn Type= 3
Dn Slope=0.0004
Boundary for River Rch & Prof#=TRIB 1 TO TURKEY,Reach-1         , 7
Up Type= 0
Dn Type= 3
Dn Slope=0.0004
DSS Import GetInterval= 0
DSS Import GetPeak= 0
DSS Import FillOption= 0

--- TRIB 1 TO TURKEY CREEK.g01 (geometry) ---

Geom Title=Existing Conditions
Program Version=4.10

River Reach=TRIB 1 TO TURKEY,Reach-1
Reach XY= 30
        2551475.       13471575.      2551472.93     13471280.86
      2551375.39     13471159.84      2551373.78      13470535.5
      2551276.22      13470314.5      2551271.46     13470076.46
      2551077.06     13469869.15      2551069.53     13469472.55
      2550838.57     13469138.47      2550480.36      13468977.7
      2550472.74     13468730.94      2550419.46     13468572.58
      2550325.61     13468464.37      2550371.87     13468326.63
       2550082.6     13468028.34      2550171.52      13467923.5
      2550171.33     13467826.58      2550085.11     13467685.38
       2549872.7     13467619.17      2549730.52     13467477.43
      2549622.93     13466880.86      2549530.85     13466777.29
      2549466.87     13466618.92      2549368.96     13466526.65
      2549254.49      13466555.9      2549214.64     13466414.85
      2549050.99     13466352.32      2548981.84     13466183.75
      2548930.83     13466222.11        2548875.       13466375.

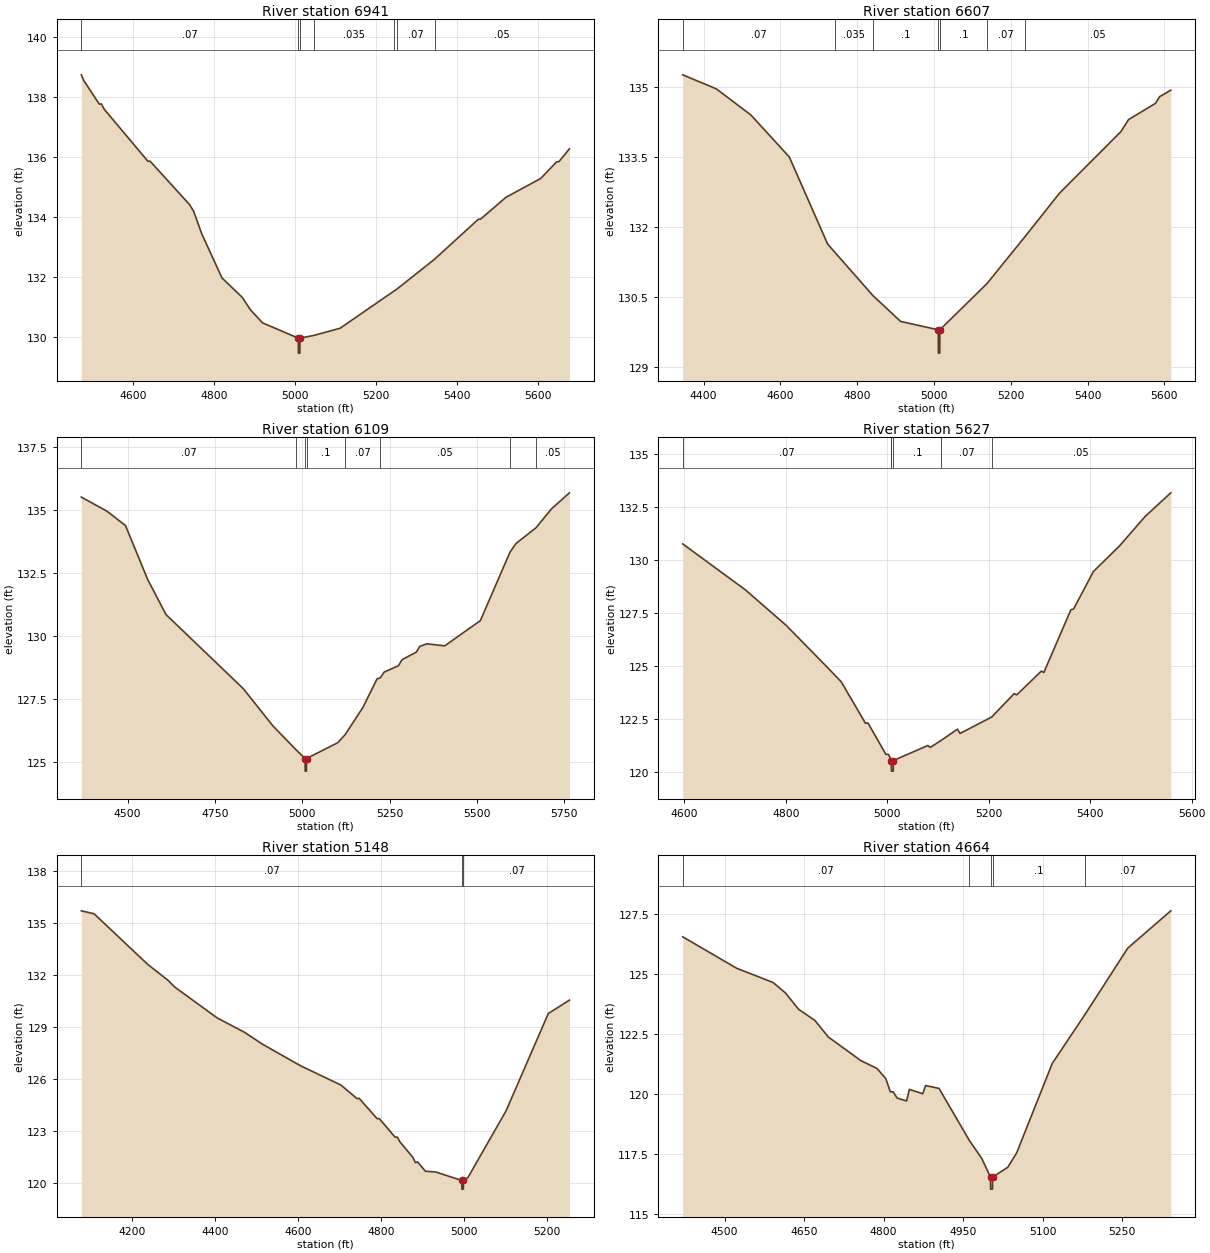
Type RM Length L Ch R = 1 ,6941    ,334,334,334
BEGIN DESCRIPTION:
TRIB 1 TO TURKEY CREEK 13.0
END DESCRIPTION:
XS GIS Cut Line= 3
       2552001.5     13471513.94      2551475.02     13471470.03
      2550804.75      13471574.1
#Sta/Elev= 30
  4471.7  138.74  4478.2  138.54  4516.2  137.76  4521.2  137.77  4528.4  137.59
  4636.6  135.85  4641.6  135.86  4739.1  134.41  4749.2  134.19  4769.2  133.44
  4819.4  131.96  4869.6  131.31  4889.6   130.9  4919.7  130.46  5008.1  129.95
  5008.4  129.45  5011.9  129.45  5012.1  129.95  5046.1  130.04  5111.3  130.28
  5245.5  131.53  5252.1  131.59  5345.4  132.59  5453.2  133.92  5458.3  133.92
  5521.2  134.65  5607.2  135.28  5647.1  135.84  5652.2  135.84  5678.3  136.27
#Mann= 7 ,-1 , 0
  4471.7     .07       0  5008.1     .05       0  5012.1     .07       0
  5046.1    .035       0  5245.5     .05       0  5252.1     .07       0
  5345.4     .05       0
Bank Sta=5008.1,5012.1
XS Rating Curve= 0 ,0
Exp/Cntr=0.3,0.1

Type RM Length L Ch R = 1 ,6607    ,498,498,498
BEGIN DESCRIPTION:
Mapping XS 4ac17342
END DESCRIPTION:
XS GIS Cut Line= 3
      2552032.41     13471174.12      2551378.75     13471172.49
      2550765.77     13471244.03
#Sta/Elev= 20
  4345.8  135.26  4433.2  134.96  4523.2   134.4  4623.2   133.5  4723.2  131.63
  4743.3  131.44  4841.6  130.52  4913.2  129.97  5011.3  129.79  5011.6  129.29
  5015.1  129.29  5015.3  129.79  5137.8  130.78  5237.1  131.79  5326.7  132.72
  5486.5  134.04  5506.6   134.3    5577  134.65  5587.2  134.79  5616.6  134.93
#Mann= 7 ,-1 , 0
  4345.8     .07       0  4743.3    .035       0  4841.6      .1       0
  5011.3     .05       0  5015.3      .1       0  5137.8     .07       0
  5237.1     .05       0
Bank Sta=5011.3,5015.3
XS Rating Curve= 0 ,0
Exp/Cntr=0.3,0.1

Type RM Length L Ch R = 1 ,6109    ,482,482,482
BEGIN DESCRIPTION:
TRIB 1 TO TURKEY CREEK 12.0
END DESCRIPTION:
XS GIS Cut Line= 3
      2551974.96     13470475.01        2551375.       13470675.
      2550624.97     13470825.01
#Sta/Elev= 30
  4367.6  135.51  4441.3  134.95  4494.1  134.38  4557.3  132.25    4610  130.85
  4831.4  127.91  4915.7  126.44  4982.1  125.49  5008.2  125.14  5008.5  124.64
    5012  124.64  5012.2  125.14    5102  125.77  5122.4  126.08  5173.4  127.16
  5214.2   128.3  5223.2  128.34  5234.6  128.57  5275.4  128.82  5285.6  129.06
  5326.4  129.36  5336.6  129.59  5356.9  129.69  5407.9  129.61  5509.9  130.61
  5594.5  133.32  5611.9  133.67  5668.9  134.29  5713.9  135.05  5764.9  135.68
#Mann= 8 ,-1 , 0
  4367.6     .07       0  4982.1      .1       0  5008.2     .05       0
  5012.2      .1       0  5122.4     .07       0  5223.2     .05       0
  5594.5     .07       0  5668.9     .05       0
Bank Sta=5008.2,5012.2
XS Rating Curve= 0 ,0
Exp/Cntr=0.3,0.1

Type RM Length L Ch R = 1 ,5627    ,479,479,479
BEGIN DESCRIPTION:
TRIB 1 TO TURKEY CREEK 11.0
END DESCRIPTION:
XS GIS Cut Line= 3
      2551675.01       13470175.        2551275.       13470225.
      2550725.04     13470125.01
#Sta/Elev= 30
  4596.8  130.78  4720.3  128.61  4800.9  126.93  4881.5  124.96  4909.2  124.27
  4957.1  122.31  4962.1  122.32  4997.4  120.84  5002.5  120.84  5006.8  120.62
  5008.1  120.55  5008.3  120.05  5011.8  120.05  5012.1  120.55    5080  121.26
    5085  121.17  5106.2   121.5  5138.4  122.03  5143.5  121.83  5205.6   122.6
  5250.2  123.71  5255.3  123.65  5303.6  124.77  5308.7  124.71    5362  127.67
  5367.1   127.7  5406.5  129.48  5457.3  130.67  5508.1  132.07  5558.9  133.19
#Mann= 6 ,-1 , 0
  4596.8     .07       0  5006.8      .1       0  5008.1     .05       0
  5012.1      .1       0  5106.2     .07       0  5205.6     .05       0
Bank Sta=5008.1,5012.1
XS Rating Curve= 0 ,0
Exp/Cntr=0.3,0.1

Type RM Length L Ch R = 1 ,5148    ,484,484,484
BEGIN DESCRIPTION:
TRIB 1 TO TURKEY CREEK 10.0
END DESCRIPTION:
XS GIS Cut Line= 3
      2551975.04     13470025.01        2551075.       13469825.
      2550825.04     13469874.99
#Sta/Elev= 30
  4077.6  135.72  4108.4  135.55  4237.7  132.63  4286.4  131.72    4303  131.32
  4405.4  129.54  4470.7  128.72  4514.3  128.03  4606.5  126.78  4703.8  125.67
  4742.2  124.89  4747.3  124.91  4790.9  123.73    4796  123.74  4834.4  122.66
  4839.5  122.67  4845.9  122.39  4876.7  121.51  4883.1   121.2  4888.2  121.24
  4907.4   120.7  4931.7  120.66    4995  120.17  4995.3  119.67  4998.8  119.67
    4999  120.17  5009.8  120.34  5101.6  124.18  5203.6   129.8  5254.5  130.57
#Mann= 3 ,-1 , 0
  4077.6     .07       0    4995     .05       0    4999     .07       0
Bank Sta=4995,4999
XS Rating Curve= 0 ,0
Exp/Cntr=0.3,0.1

Type RM Length L Ch R = 1 ,4664    ,422,422,422
BEGIN DESCRIPTION:
TRIB 1 TO TURKEY CREEK 9.0
END DESCRIPTION:
XS GIS Cut Line= 3
      2551525.02     13469575.01        2550975.       13469375.
      2550824.98     13469675.03
#Sta/Elev= 30
  4420.9  126.54  4522.7  125.23  4591.2  124.64  4614.4  124.21  4639.7  123.52
  4670.3  123.06  4695.6  122.37  4756.8  121.39  4787.4  121.06    4804  120.64
  4812.6  120.09  4817.9  120.09  4825.3  119.83  4843.2  119.71  4848.5  120.19
  4873.8  120.01  4879.1  120.35  4904.4  120.23  4961.8  118.06  4984.9  117.32
  5001.5  116.54  5001.7  116.04  5005.2  116.04  5005.5  116.54  5034.1  116.95
  5050.9  117.55    5118  121.27  5180.4  123.33  5260.5  126.07  5341.6  127.62
#Mann= 5 ,-1 , 0
  4420.9     .07       0  4961.8      .1       0  5001.5     .05       0
  5005.5      .1       0  5180.4     .07       0
Bank Sta=5001.5,5005.5
XS Rating Curve= 0 ,0
Exp/Cntr=0.3,0.1

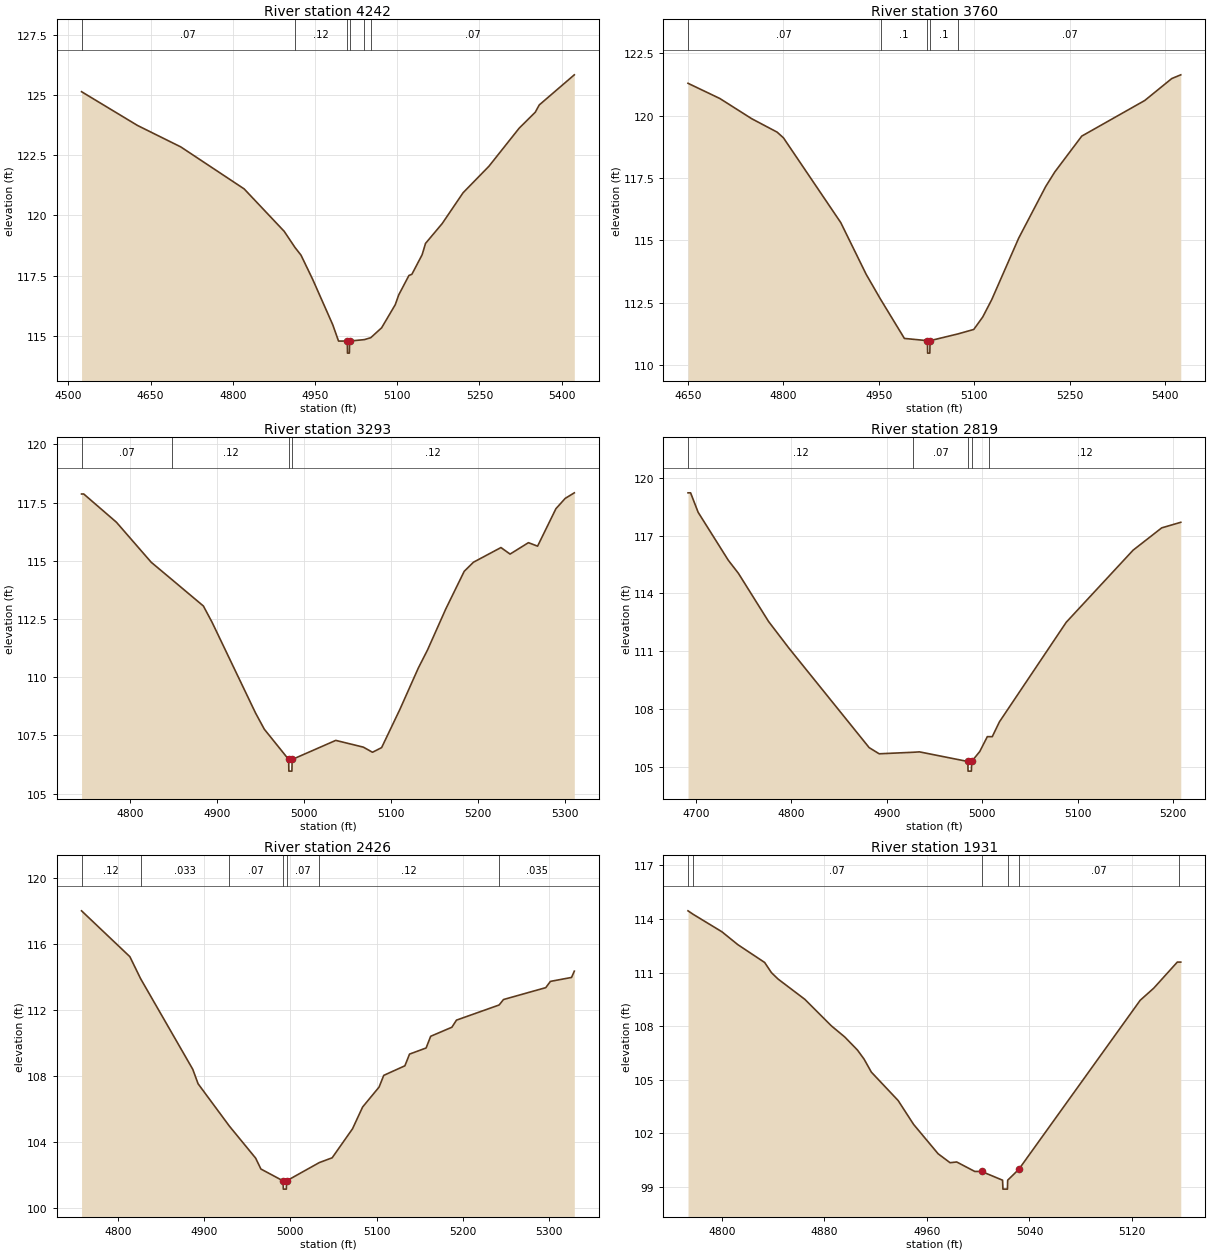
Type RM Length L Ch R = 1 ,4242    ,482,482,482
BEGIN DESCRIPTION:
TRIB 1 TO TURKEY CREEK 8.0
END DESCRIPTION:
XS GIS Cut Line= 3
      2551125.04     13468824.97        2550725.       13469075.
      2550575.02     13469474.95
#Sta/Elev= 30
  4524.1  125.13  4626.2  123.73  4705.2  122.84  4820.7   121.1  4893.8  119.34
  4913.2  118.68  4924.5  118.35  4945.7  117.35  4982.3  115.47  4992.9  114.79
    5009  114.79  5009.2  114.29  5012.7  114.29    5013  114.79  5040.1  114.85
  5051.7  114.93  5071.5  115.34  5096.4   116.3  5102.6   116.7  5121.3  117.51
  5126.7  117.56  5145.4  118.37  5151.6  118.84  5181.9  119.66  5220.1  120.94
  5267.3  122.04  5322.5  123.62  5351.8  124.28    5359  124.58    5423  125.83
#Mann= 6 ,-1 , 0
  4524.1     .07       0  4913.2     .12       0    5009     .05       0
    5013     .12       0  5040.1      .1       0  5051.7     .07       0
Bank Sta=5009,5013
XS Rating Curve= 0 ,0
Exp/Cntr=0.3,0.1

Type RM Length L Ch R = 1 ,3760    ,467,467,467
BEGIN DESCRIPTION:
TRIB 1 TO TURKEY CREEK 7.0
END DESCRIPTION:
XS GIS Cut Line= 3
        2550825.       13468775.        2550475.       13468775.
      2550174.98     13469075.02
#Sta/Elev= 24
  4650.4   121.3  4700.4  120.69  4750.4  119.88  4790.4  119.34  4800.4  119.11
  4890.4  115.71  4930.4  113.63    4953  112.63  4990.4  111.06  5026.7  110.97
  5026.9  110.47  5030.4  110.47  5030.7  110.97  5074.4  111.24  5099.4  111.42
  5113.5  111.92  5127.7  112.62  5170.1  115.09  5212.5  117.16  5226.7  117.74
  5269.1  119.18  5368.1  120.61  5410.5  121.49  5424.7  121.64
#Mann= 5 ,-1 , 0
  4650.4     .07       0    4953      .1       0  5026.7     .05       0
  5030.7      .1       0  5074.4     .07       0
Bank Sta=5026.7,5030.7
XS Rating Curve= 0 ,0
Exp/Cntr=0.3,0.1

Type RM Length L Ch R = 1 ,3293    ,474,474,474
BEGIN DESCRIPTION:
TRIB 1 TO TURKEY CREEK 6.0
END DESCRIPTION:
XS GIS Cut Line= 3
      2550624.97       13468375.        2550375.       13468375.
        2550075.       13468475.
#Sta/Elev= 30
  4744.6  117.87  4747.1  117.87  4784.6  116.66  4824.6  114.94  4848.9  114.18
  4884.6  113.06  4894.6  112.36  4944.6  108.46  4954.6  107.77  4982.6  106.47
  4982.8  105.97  4986.3  105.97  4986.6  106.47  5036.7  107.29  5068.4     107
  5078.9  106.78  5089.4  106.98  5110.5  108.63  5131.6   110.4  5142.1  111.17
  5163.2  112.94  5184.3  114.55  5194.9  114.94  5226.5  115.57    5237  115.29
  5258.1  115.78  5268.6  115.63  5289.7  117.24  5300.3  117.68  5310.8  117.92
#Mann= 4 ,-1 , 0
  4744.6     .07       0  4848.9     .12       0  4982.6     .05       0
  4986.6     .12       0
Bank Sta=4982.6,4986.6
XS Rating Curve= 0 ,0
Exp/Cntr=0.3,0.1

Type RM Length L Ch R = 1 ,2819    ,393,393,393
BEGIN DESCRIPTION:
TRIB 1 TO TURKEY CREEK 5.0
END DESCRIPTION:
XS GIS Cut Line= 3
      2550375.05     13467924.98        2550075.       13468025.
      2549874.98       13468025.
#Sta/Elev= 24
  4691.6  119.22  4694.3  119.22  4702.2  118.21  4733.8  115.72  4744.4  115.04
    4776  112.54  4797.1  111.17  4881.4  105.99  4891.9  105.67  4927.8  105.75
  4934.1  105.77  4984.8  105.27    4985  104.77  4988.5  104.77  4988.8  105.27
  4997.3  105.79  5005.2  106.56  5007.3  106.56  5010.4  106.56  5017.9  107.33
  5087.9   112.5  5157.9  116.24  5187.9   117.4  5207.9  117.69
#Mann= 5 ,-1 , 0
  4691.6     .12       0  4927.8     .07       0  4984.8     .05       0
  4988.8     .07       0  5007.3     .12       0
Bank Sta=4984.8,4988.8
XS Rating Curve= 0 ,0
Exp/Cntr=0.3,0.1

Type RM Length L Ch R = 1 ,2426    ,495,495,495
BEGIN DESCRIPTION:
TRIB 1 TO TURKEY CREEK 4.0
END DESCRIPTION:
XS GIS Cut Line= 3
      2550324.98     13467625.01      2550092.13      13467691.3
      2549785.38      13467810.5
#Sta/Elev= 30
  4757.9  118.01  4813.9  115.23  4826.3   113.9  4886.8   108.4    4893  107.52
  4929.3  104.95  4959.7  103.01  4965.8  102.35  4991.5  101.63  4991.8  101.13
  4995.3  101.13  4995.5  101.63  5033.5  102.74  5048.4  103.03    5072  104.79
  5083.7  106.11  5102.8  107.32  5108.2  108.03  5132.7  108.61  5138.1  109.32
  5157.3  109.69  5162.6   110.4  5187.2  110.95  5192.5  111.38    5242   112.3
    5247  112.63    5296  113.35  5301.4  113.73  5325.9  113.97  5329.1  114.35
#Mann= 7 ,-1 , 0
  4757.9     .12       0  4826.3    .033       0  4929.3     .07       0
  4991.5     .05       0  4995.5     .07       0  5033.5     .12       0
    5242    .035       0
Bank Sta=4991.5,4995.5
XS Rating Curve= 0 ,0
Exp/Cntr=0.3,0.1

Type RM Length L Ch R = 1 ,1931    ,482,482,482
BEGIN DESCRIPTION:
TRIB 1 TO TURKEY CREEK 3.0
END DESCRIPTION:
XS GIS Cut Line= 3
      2549942.45      13467361.8        2549725.       13467425.
      2549574.96     13467475.01
#Sta/Elev= 30
  4773.5  114.46  4777.4  114.27  4799.9  113.29  4812.5  112.56  4833.3  111.57
  4838.6     111  4843.8  110.64  4864.6  109.51  4885.4  108.02  4895.8   107.4
  4905.7  106.67  4910.9  106.16  4916.6  105.43  4937.5  103.84  4949.6   102.5
  4968.7  100.86    4978  100.36  4983.2   100.4  4997.3   99.87  5002.6   99.87
    5019   99.38  5019.3   98.88  5022.8   98.88    5023   99.38  5031.6   99.98
  5126.4  109.45    5137  110.13  5155.4  111.59  5157.1  111.59  5158.1  111.59
#Mann= 6 ,-1 , 0
  4773.5     .12       0  4777.4     .07       0  5002.6     .05       0
    5023     .05       0  5031.6     .07       0  5157.1    .035       0
Bank Sta=5002.6,5031.6
XS Rating Curve= 0 ,0
Exp/Cntr=0.3,0.1

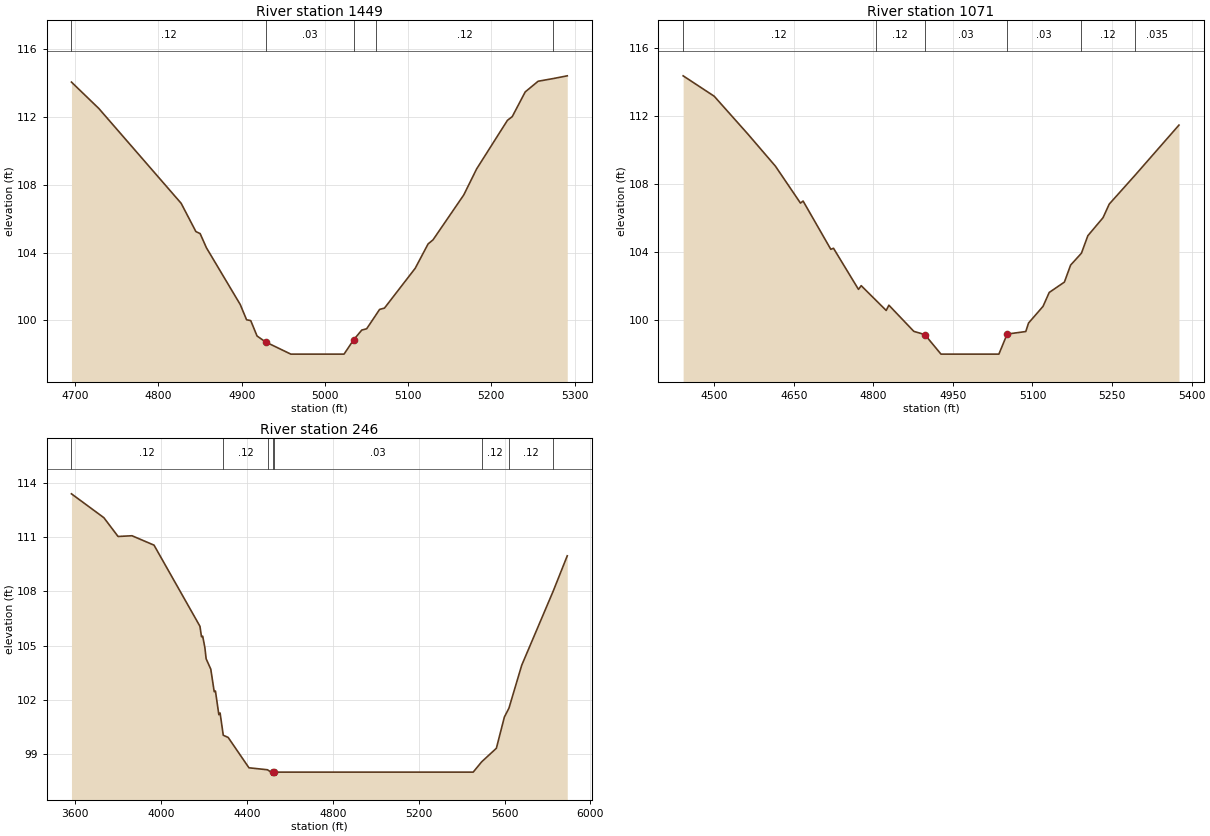
Type RM Length L Ch R = 1 ,1449    ,378,378,378
BEGIN DESCRIPTION:
TRIB 1 TO TURKEY CREEK 2.0
END DESCRIPTION:
XS GIS Cut Line= 3
        2549925.       13467025.        2549625.       13466975.
      2549374.99     13467125.01
#Sta/Elev= 30
  4695.5  114.07  4728.4  112.51  4827.3  106.91    4845  105.24  4850.1  105.12
  4857.7  104.28  4898.3  100.93  4905.9  100.03  4910.9   99.98  4918.5   99.07
  4928.7   98.72  4959.1      98    5023      98  5034.6   98.85  5044.3   99.42
  5050.2    99.5    5061  100.29  5065.7  100.64  5071.6  100.72  5108.5  103.07
    5124  104.51  5129.9  104.75  5166.8   107.4  5182.3  108.94  5219.3  111.81
  5225.1  112.03  5240.7  113.49  5256.2  114.12  5274.5  114.28  5291.2  114.44
#Mann= 5 ,-1 , 0
  4695.5     .12       0  4928.7     .03       0  5034.6     .03       0
    5061     .12       0  5274.5    .035       0
Bank Sta=4928.7,5034.6
XS Rating Curve= 0 ,0
Exp/Cntr=0.3,0.1

Type RM Length L Ch R = 1 ,1071    ,825,825,825
BEGIN DESCRIPTION:
Mapping XS 1113f9f4
END DESCRIPTION:
XS GIS Cut Line= 3
      2550022.43     13466752.26      2549475.52     13466648.09
      2549371.74     13467011.32
#Sta/Elev= 30
  4441.6  114.38  4500.1  113.18  4563.4  110.96  4615.6  109.06  4662.7  106.89
  4667.7  107.01  4719.9  104.17    4725  104.23  4772.1  101.81  4777.2  102.03
  4804.3  101.19  4824.3  100.57  4829.4  100.88  4876.4   99.34  4897.1   99.15
  4927.6      98  5036.7      98  5052.3   99.18  5087.4   99.33  5092.6   99.83
  5119.9  100.81  5131.6  101.63  5160.2  102.24  5171.9  103.24  5192.3  103.94
  5204.4  104.97    5233  106.03  5244.7  106.83  5293.4  108.53  5376.1  111.48
#Mann= 6 ,-1 , 0
  4441.6     .12       0  4804.3     .12       0  4897.1     .03       0
  5052.3     .03       0  5192.3     .12       0  5293.4    .035       0
Bank Sta=4897.1,5052.3
XS Rating Curve= 0 ,0
Exp/Cntr=0.3,0.1

Type RM Length L Ch R = 1 ,246     ,0,0,0
BEGIN DESCRIPTION:
TRIB 1 TO TURKEY CREEK 1.0
END DESCRIPTION:
XS GIS Cut Line= 4
      2550126.56     13466648.09      2549032.81     13466031.77
      2548950.35      13466320.4      2549325.02     13466975.04
#Sta/Elev= 30
  3582.2   113.4  3733.2  112.08  3799.4  111.04  3864.4  111.08  3966.9  110.56
  4180.9  106.07    4188  105.49  4193.7  105.52  4203.8  104.89  4209.7  104.27
  4231.3   103.7  4247.3  102.45    4253  102.49  4268.9  101.18  4274.7  101.27
  4289.5  100.04  4312.3   99.92  4409.1   98.24  4495.7   98.13  4511.7      98
  4523.2      98  4527.2      98  5453.8      98  5493.3   98.57  5561.8   99.32
  5599.2  101.05  5620.4  101.54  5679.8  103.91  5826.4  108.01  5892.1  109.97
#Mann= 8 ,-1 , 0
  3582.2     .12       0  4289.5     .12       0  4495.7     .03       0
  4523.2     .03       0  4527.2     .03       0  5493.3     .12       0
  5620.4     .12       0  5826.4    .035       0
Bank Sta=4523.2,4527.2
XS Rating Curve= 0 ,0
Exp/Cntr=0.3,0.1

Chan Stop Cuts=-1
Use User Specified Reach Order=0
Composite Channel Slope=5