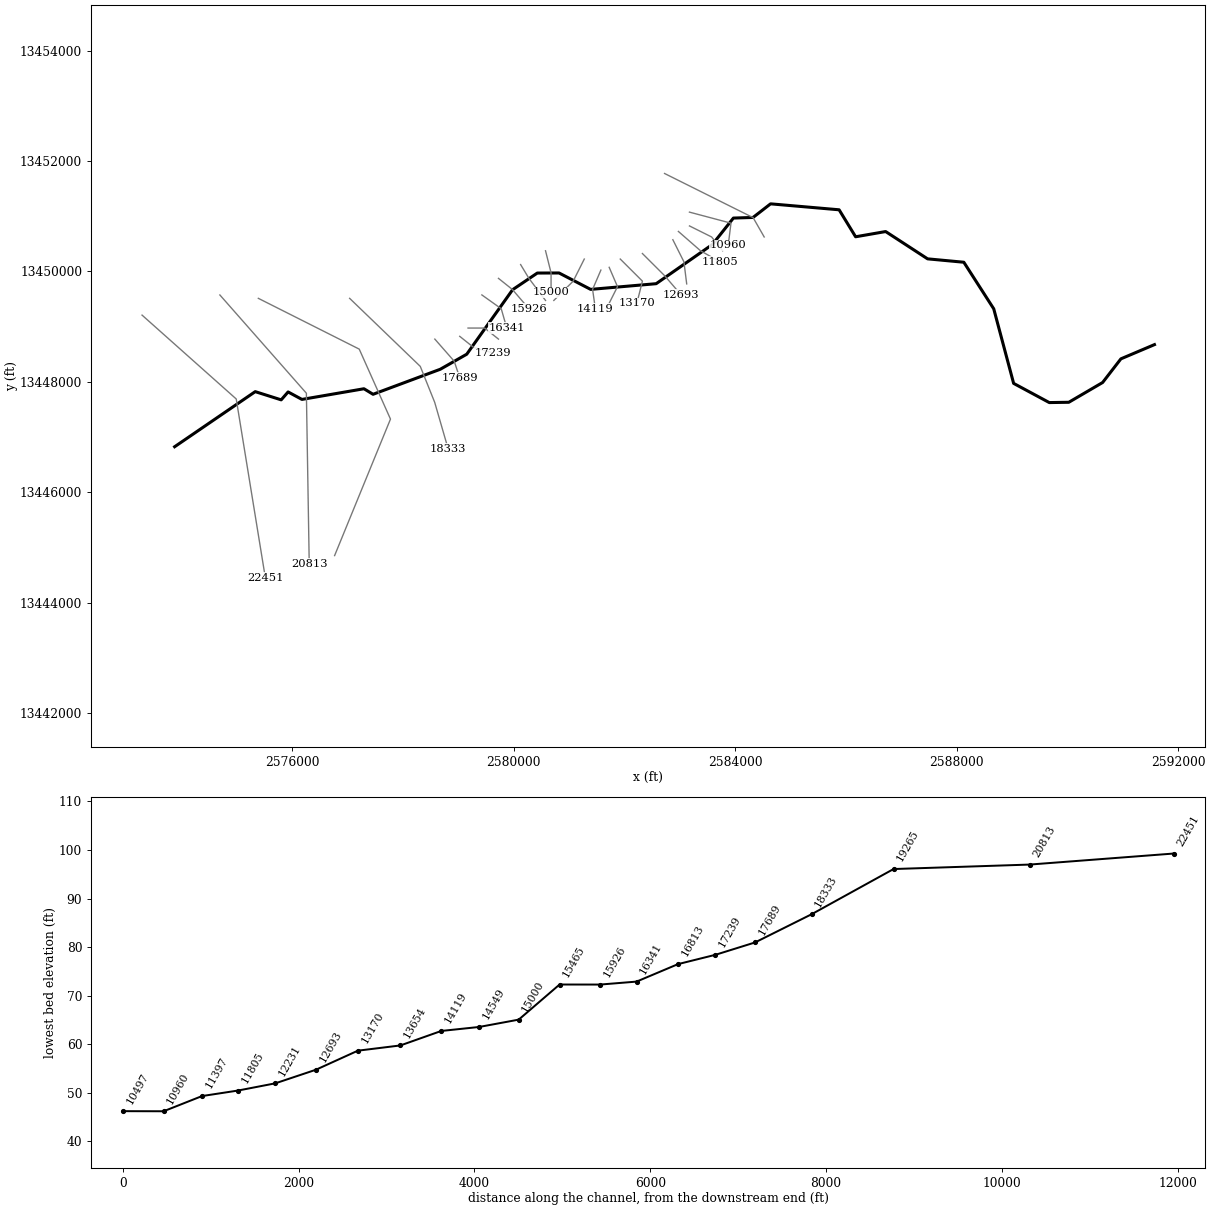
--- TRIB 1A TO COLETO CREEK.prj (project) ---

Proj Title=TRIB 1A TO COLETO CREEK Base Level Engineering
Current Plan=p01
Default Exp/Contr=0.3,0.1
English Units
Geom File=g01
Flow File=f01
Plan File=p01
Y Axis Title=Elevation
X Axis Title(PF)=Main Channel Distance
X Axis Title(XS)=Station
BEGIN DESCRIPTION:
TRIB 1A TO COLETO CREEK
END DESCRIPTION:
DSS Export Rating Curves= 0
DSS Export Rating Curve Sorted= 0
DSS Export Volume Flow Curves= 0
DXF OffsetX= 0
DXF OffsetY= 0
DXF ScaleX= 1
DXF ScaleY= 10

--- TRIB 1A TO COLETO CREEK.p01 (plan) ---

Plan Title=Multiple Run
Program Version=4.10
Short Identifier=Multiple
Geom File=g01
Flow File=f01
Subcritical Flow
K Sum by GR= 0
Std Step Tol= 0.01
Critical Tol= 0.01
Num of Std Step Trials= 20
Max Error Tol= 0.3
Flow Tol Ratio= 0.001
Split Flow NTrial= 30
Split Flow Tol= 0.02
Split Flow Ratio= 0.02
Log Output Level= 0
Friction Slope Method= 1
Unsteady Friction Slope Method= 2
Unsteady Bridges Friction Slope Method= 1
Parabolic Critical Depth
Global Vel Dist= 1 , 1 , 1
Global Log Level= 0
CheckData=True
Encroach Param=-1 ,0,0, 0
BEGIN DESCRIPTION:
Multiple Run
END DESCRIPTION:
Computation Interval=1HOUR
Output Interval=1HOUR
Run HTab= 0
Run UNet= 0
Run PostProcess= 0
Run WQNet= 0
UNET Theta= 1
UNET Theta Warmup= 1
UNET ZTol= 0.02
UNET ZSATol= 0.05
UNET MxIter= 20
UNET MaxInSteps= 0
UNET DtIC= 0
UNET DtMin= 0
UNET MaxCRTS= 20
UNET WFStab= 2
UNET SFStab= 1
UNET WFX= 1
UNET SFX= 1
UNET DSS MLevel= 4
UNET DZMax Abort= 100
UNET Convert EG Bridges= 0
UNET Use Existing IB Tables=-1
UNET Froude Reduction=False
UNET Froude Limit= 1
UNET Froude Power= 10
UNET Time Slicing=0,0, 5
UNET Junction Losses=0
Instantaneous Interval=1HOUR
Write IC File= 0
Write IC File at Sim End=0
Echo Input=False
Echo Parameters=False
Echo Output=False
Write Detailed= 0
WQ AD Non Conservative
WQ ULTIMATE=-1
WQ Max Comp Step=1HOUR
WQ Output Interval=15MIN
WQ Output Selected Increments= 0
WQ Output face flow=0
WQ Output face velocity=0
WQ Output face area=0
WQ Output face dispersion=0
WQ Output cell volume=0
WQ Output cell surface area=0
WQ Output cell continuity=0
WQ Output cumulative cell continuity=0
WQ Output face conc=0
WQ Output face dconc_dx=0
WQ Output face courant=0
WQ Output face peclet=0
WQ Output face adv mass=0
WQ Output face disp mass=0
WQ Output cell mass=0
WQ Output cell source sink temp=0
WQ Output cell source sink nsm=0
WQ Output MaxMinRange=-1
WQ Daily Max Min Mean=-1
WQ Daily Range=0
WQ Daily Time=0
WQ Create Restart=0
WQ Fixed Restart=0
WQ System Summary=0
WQ Use Fixed Temperature=0
Sorting and Armoring Iterations= 10
XS Update Threshold= 0.02
Hydraulics Update Threshold= 0.02
Energy Slope Method= 1
Volume Change Method= 0
XS Weighting Method= 0
Number of US Weighted Cross Sections= 1
Number of DS Weighted Cross Sections= 1
Upstream XS Weight=0.25
Main XS Weight=0.5
Downstream XS Weight=0.25
Number of DS XS's Weighted with US Boundary= 1
Upstream Boundary Weight= 1
Weight of XSs Associated with US Boundary= 0
Number of US XS's Weighted with DS Boundary= 1
Downstream Boundary Weight= 0.5
Weight of XSs Associated with DS Boundary= 0.5
Sediment Output Level= 4
Mass or Volume Output= 0
Output Increment Type= 1
Profile and TS Output Increment= 10
XS Output Flag= 0
XS Output Increment= 10
Disregard all LS=0
Disregard all Conn=0
Disregard all Breaches=0
Disregard all Pumps=0

--- TRIB 1A TO COLETO CREEK.f01 (steady flow) ---

Flow Title=Multiple
Number of Profiles=7
Profile Names=10-year,25-year,50-year,1pct_min,100-year,1pct_plu,500-year
River Rch & RM= TRIB 1A TO COLET,Reach-1,22451
     446     671     859     531    1060    2115    1593
River Rch & RM= TRIB 1A TO COLET,Reach-1,18333
     776    1211    1588    1004    2004    3998    3156
River Rch & RM= TRIB 1A TO COLET,Reach-1,17689
    1175    1894    2541    1644    3281    6546    5409
Boundary for River Rch & Prof#=TRIB 1A TO COLET,Reach-1,1
Up Type=0
Dn Type=3
Dn Slope=0.005
Boundary for River Rch & Prof#=TRIB 1A TO COLET,Reach-1,2
Up Type=0
Dn Type=3
Dn Slope=0.005
Boundary for River Rch & Prof#=TRIB 1A TO COLET,Reach-1,3
Up Type=0
Dn Type=3
Dn Slope=0.005
Boundary for River Rch & Prof#=TRIB 1A TO COLET,Reach-1,4
Up Type=0
Dn Type=3
Dn Slope=0.005
Boundary for River Rch & Prof#=TRIB 1A TO COLET,Reach-1,5
Up Type=0
Dn Type=3
Dn Slope=0.005
Boundary for River Rch & Prof#=TRIB 1A TO COLET,Reach-1,6
Up Type=0
Dn Type=3
Dn Slope=0.005
Boundary for River Rch & Prof#=TRIB 1A TO COLET,Reach-1,7
Up Type=0
Dn Type=3
Dn Slope=0.005

--- TRIB 1A TO COLETO CREEK.g01 (geometry) ---

Geom Title=Existing Conditions
Program Version=4.10

River Reach=TRIB 1A TO COLET,Reach-1
Reach XY= 30
        2573875.       13446825.      2575331.13     13447823.16
      2575800.08     13447674.37       2575924.7     13447817.74
       2576174.7      13447682.2      2577295.16     13447875.46
      2577459.59     13447775.02      2578673.53     13448228.55
      2579151.87     13448501.18      2579980.44     13449669.82
       2580426.5     13449971.38      2580819.07     13449972.75
      2581390.16     13449675.39      2582573.54     13449778.54
      2583589.02     13450488.62      2583968.54     13450967.26
      2584323.53     13450978.55      2584640.34     13451225.05
      2585878.43     13451117.21      2586176.22     13450628.44
      2586718.89      13450723.2      2587476.47     13450228.55
      2588131.19     13450167.18      2588671.38      13449323.5
      2589030.83     13447972.69        2589675.       13447625.
      2590027.45     13447630.45      2590638.21     13447988.62
      2590968.55     13448417.25        2591575.       13448675.

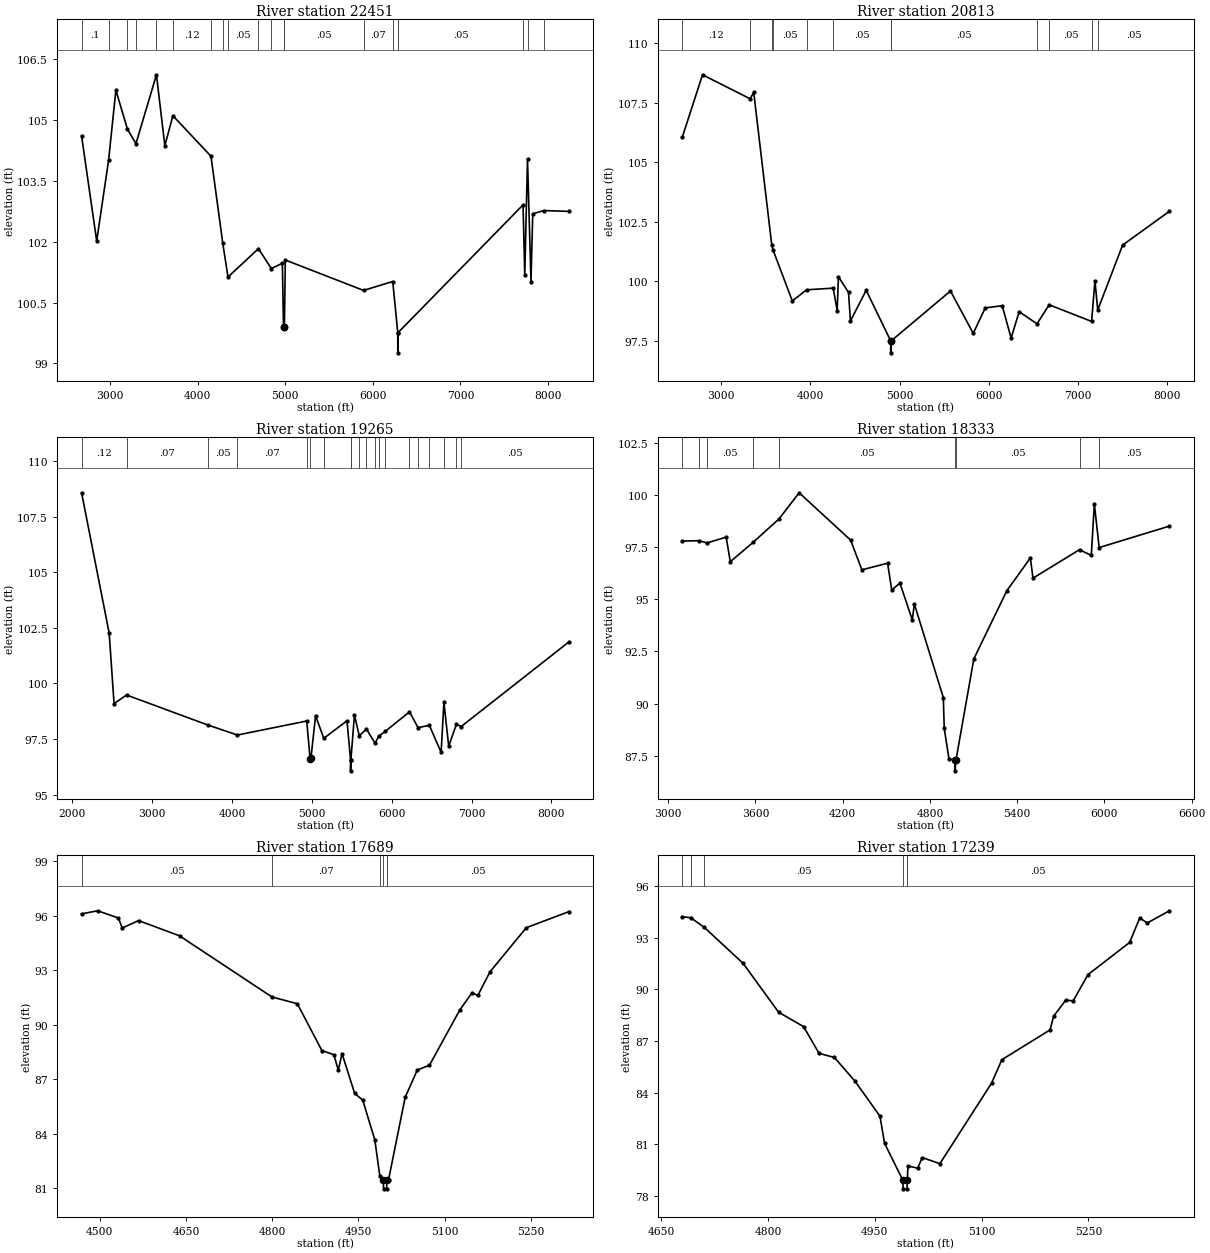
Type RM Length L Ch R = 1 ,22451   ,1638,1638,1638
BEGIN DESCRIPTION:
Mapping XS 41328f26
END DESCRIPTION:
XS GIS Cut Line= 3
      2573286.32     13449209.49      2574987.73     13447690.37
      2575514.07     13444448.93
#Sta/Elev= 30
    2673  104.61  2845.5  102.02  2981.3  104.01  3064.7  105.74  3196.3  104.78
  3293.8  104.42    3528  106.12    3624  104.37    3716  105.11  4150.9  104.11
    4286  101.96  4345.2  101.13    4693  101.83  4839.9  101.34  4966.2  101.47
  4979.6   99.89  4989.7   99.89  4999.9  101.55    5894   100.8    6227  101.02
  6284.5   99.76  6284.8   99.26  6288.6   99.76  7715.5  102.91  7735.2  101.18
  7766.4  104.04  7806.2  101.02  7826.4  102.69  7954.7  102.77  8237.8  102.75
#Mann= 20 ,-1 , 0
    2673      .1       0  2981.3     .12       0  3196.3     .07       0
  3293.8     .12       0    3528    .035       0    3716     .12       0
  4150.9     .05       0    4286    .035       0  4345.2     .05       0
    4693     .07       0  4839.9     .05       0  4979.6     .05       0
  4989.7     .05       0    5894     .07       0    6227     .05       0
  6284.5     .05       0  6288.6     .05       0  7715.5    .035       0
  7766.4     .07       0  7954.7     .05       0
Bank Sta=4979.6,4989.7
XS Rating Curve= 0 ,0
Exp/Cntr=0.3,0.1

Type RM Length L Ch R = 1 ,20813   ,1548,1548,1548
BEGIN DESCRIPTION:
Mapping XS 58256268
END DESCRIPTION:
XS GIS Cut Line= 3
      2574692.57     13449574.08       2576255.1     13447794.54
       2576306.5     13444700.34
#Sta/Elev= 30
  2562.8  106.05  2790.4  108.68  3324.2  107.67  3364.4  107.94  3566.7  101.52
  3580.5  101.32  3797.1   99.17  3956.6   99.64  4255.3   99.71  4300.1   98.77
  4314.3  100.19  4427.2   99.53    4449   98.33  4625.5   99.62  4900.5   97.49
  4900.8   96.99  4904.7   97.49  5570.6   99.59  5825.6   97.81  5960.7   98.88
  6150.7   98.97  6250.7   97.61  6340.7   98.72  6541.2   98.21    6677   99.01
  7153.1   98.31  7190.8  100.02  7221.8   98.79  7500.9  101.52  8025.6  102.94
#Mann= 12 ,-1 , 0
  2562.8     .12       0  3324.2     .05       0  3566.7    .035       0
  3580.5     .05       0  3956.6     .07       0  4255.3     .05       0
  4900.5     .05       0  4904.7     .05       0  6541.2     .07       0
    6677     .05       0  7153.1    .035       0  7221.8     .05       0
Bank Sta=4900.5,4904.7
XS Rating Curve= 0 ,0
Exp/Cntr=0.3,0.1

Type RM Length L Ch R = 1 ,19265   ,932,932,932
BEGIN DESCRIPTION:
Mapping XS 69461c2a
END DESCRIPTION:
XS GIS Cut Line= 4
        2575387.     13449513.31      2577209.96     13448593.15
      2577774.19     13447325.79      2576764.83     13444853.08
#Sta/Elev= 30
  2117.2  108.57  2462.6  102.26  2523.9   99.09    2680   99.48  3697.6   98.13
  4068.7   97.68  4936.2   98.31  4978.2   96.62  4989.1   96.64  5046.9   98.55
  5149.5   97.53  5440.6   98.32    5485   96.57  5485.3   96.07  5489.3   96.57
  5533.6   98.58  5593.7   97.65  5684.2   97.95  5791.9   97.31  5837.2   97.62
  5917.3   97.84    6223   98.72  6330.7   98.01    6471   98.12    6619    96.9
    6654   99.15  6713.9   97.18  6811.1   98.17  6869.5   98.06  8217.3  101.86
#Mann= 20 ,-1 , 0
  2117.2     .12       0    2680     .07       0  3697.6     .05       0
  4068.7     .07       0  4936.2    .035       0  4978.2    .035       0
  5149.5     .07       0    5485    .035       0  5489.3     .07       0
  5593.7     .07       0  5684.2    .035       0  5791.9     .07       0
  5837.2      .1       0  5917.3     .05       0    6223     .07       0
  6330.7     .07       0    6471    .035       0    6654     .05       0
  6811.1      .1       0  6869.5     .05       0
Bank Sta=4978.2,4989.1
XS Rating Curve= 0 ,0
Exp/Cntr=0.3,0.1

Type RM Length L Ch R = 1 ,18333   ,644,644,644
BEGIN DESCRIPTION:
Mapping XS 9da5ea18
END DESCRIPTION:
XS GIS Cut Line= 4
      2577036.32     13449513.31      2578312.39     13448280.65
       2578572.8     13447629.61       2578815.5     13446788.83
#Sta/Elev= 30
  3096.5    97.8  3213.9   97.82    3267   97.71  3398.6   97.99  3426.9   96.81
    3584   97.74  3762.6   98.87  3900.7  100.12  4254.2   97.85  4332.1   96.42
  4508.8   96.74  4537.1   95.46  4593.7   95.78  4678.6   94.02  4692.8   94.78
  4892.1   90.29  4898.3   88.81  4930.6   87.36  4972.5   87.27    4973   86.77
  4978.6   87.27  5102.1   92.15  5329.1   95.42  5490.7   96.99  5508.7   96.02
  5828.9   97.39  5909.8   97.11  5930.6   99.59  5963.8   97.49    6447   98.52
#Mann= 9 ,-1 , 0
  3096.5     .05       0  3213.9     .07       0    3267     .05       0
    3584     .07       0  3762.6     .05       0  4972.5     .05       0
  4978.6     .05       0  5828.9    .035       0  5963.8     .05       0
Bank Sta=4972.5,4978.6
XS Rating Curve= 0 ,0
Exp/Cntr=0.3,0.1

Type RM Length L Ch R = 1 ,17689   ,450,450,450
BEGIN DESCRIPTION:
TRIB 1A TO COLETO CREEK 30.0
END DESCRIPTION:
XS GIS Cut Line= 3
        2578575.       13448775.        2578925.       13448375.
      2579024.99     13448075.03
#Sta/Elev= 30
  4468.2   96.11  4496.2   96.28  4532.3   95.88  4538.9   95.33  4567.4   95.74
  4638.6    94.9  4799.5   91.53  4843.6   91.16  4886.3   88.58  4907.2   88.35
  4914.8    87.5  4921.4   88.41  4943.2   86.23  4957.5   85.84  4978.4   83.66
  4987.1   81.68  4993.2   81.46  4993.7   80.96    4999   80.96  4999.5   81.46
  5002.3   81.46  5031.3   86.01  5052.4   87.51  5073.5   87.77  5126.2   90.81
  5147.3   91.75  5157.8   91.62  5178.9   92.92  5242.1   95.35  5315.9   96.23
#Mann= 5 ,-1 , 0
  4468.2     .05       0  4799.5     .07       0  4987.1     .05       0
  4993.2     .05       0  4999.5     .05       0
Bank Sta=4993.2,4999.5
XS Rating Curve= 0 ,0
Exp/Cntr=0.3,0.1

Type RM Length L Ch R = 1 ,17239   ,426,426,426
BEGIN DESCRIPTION:
TRIB 1A TO COLETO CREEK 29.0
END DESCRIPTION:
XS GIS Cut Line= 3
        2579025.       13448825.        2579275.       13448625.
      2579625.04     13448524.99
#Sta/Elev= 30
  4679.6   94.23  4691.8   94.16  4710.8    93.6  4765.2   91.51  4814.9   88.68
  4850.1   87.84  4871.7   86.29  4893.3   86.05  4922.1   84.68  4957.3   82.64
  4963.7   81.07  4989.4   78.92  4989.9   78.42  4995.2   78.42  4995.7   78.92
  4996.6   79.75  5010.2   79.62  5016.7   80.24  5041.4   79.88  5114.2   84.57
  5128.5   85.92  5196.1   87.65  5201.3   88.45  5218.2   89.38  5228.6   89.34
  5249.4   90.86  5307.9   92.73  5322.2   94.16  5332.6   93.86  5363.8   94.57
#Mann= 5 ,-1 , 0
  4679.6     .05       0  4691.8     .07       0  4710.8     .05       0
  4989.4     .05       0  4995.7     .05       0
Bank Sta=4989.4,4995.7
XS Rating Curve= 0 ,0
Exp/Cntr=0.3,0.1

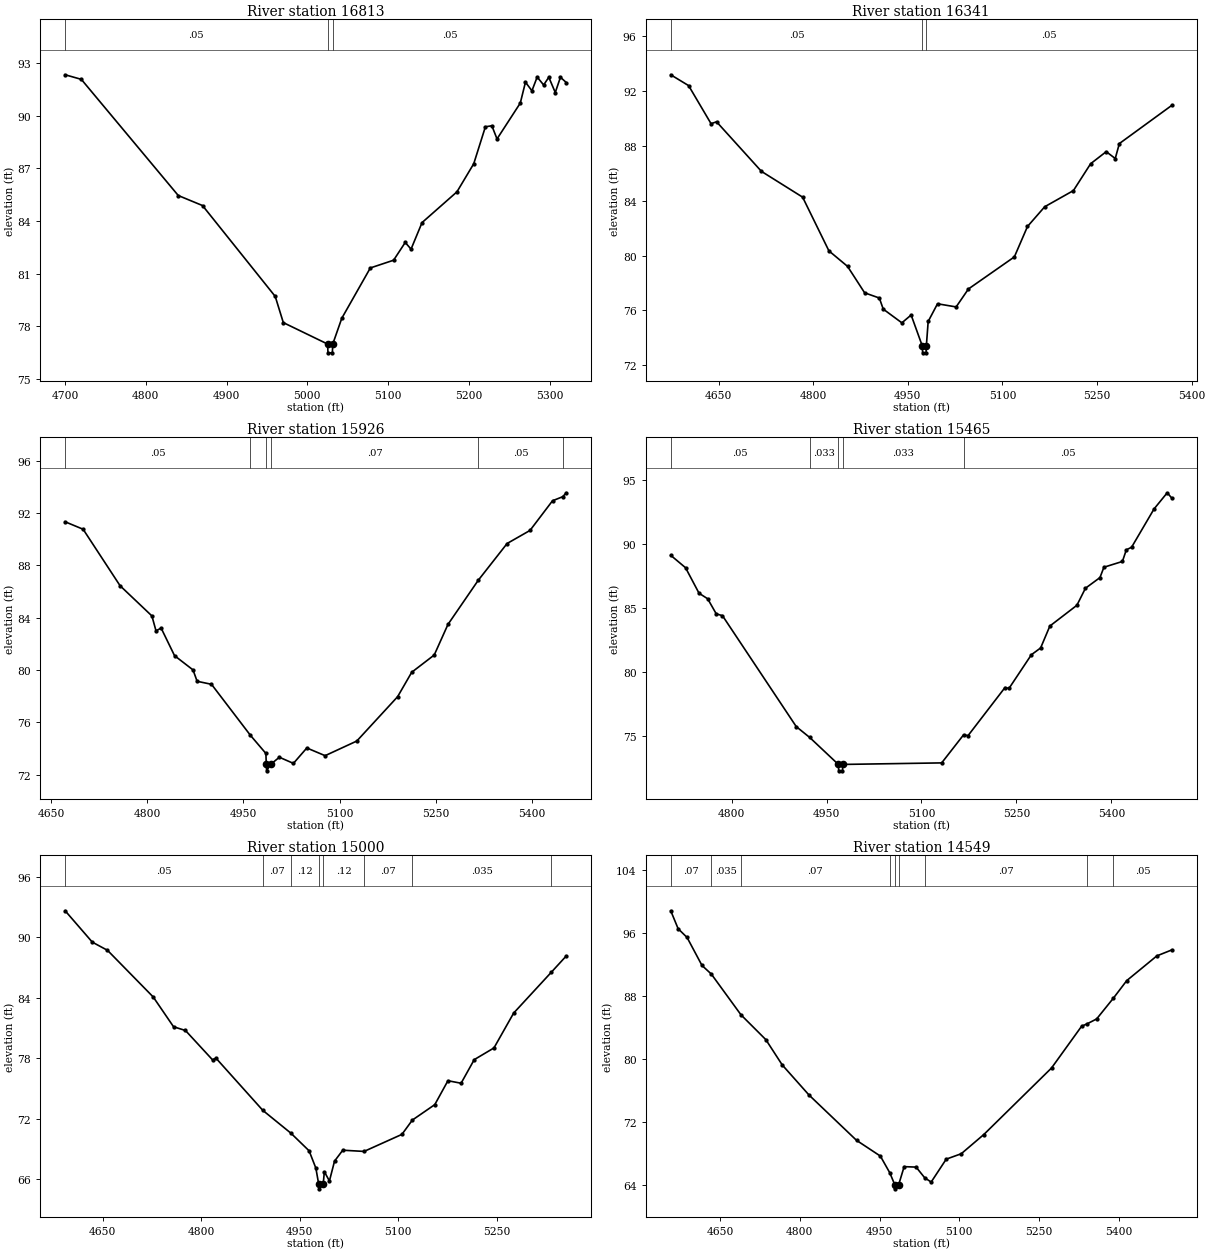
Type RM Length L Ch R = 1 ,16813   ,472,472,472
BEGIN DESCRIPTION:
TRIB 1A TO COLETO CREEK 28.0
END DESCRIPTION:
XS GIS Cut Line= 3
      2579174.99       13448975.        2579475.       13448975.
      2579725.02     13448774.98
#Sta/Elev= 30
  4700.3   92.32  4720.3   92.06  4840.3   85.45  4870.3   84.88  4960.3   79.71
  4970.3   78.22  5025.1      77  5025.6    76.5    5031    76.5  5031.5      77
  5042.7   78.47    5078   81.33  5106.8   81.77  5121.2   82.78  5128.4    82.4
    5142   83.91  5185.2   85.66    5206   87.26  5220.4   89.36  5228.4   89.42
  5234.8   88.67  5263.6   90.71    5270    91.9    5278   91.41  5284.5   92.19
  5292.5   91.74  5298.9   92.18  5306.9   91.31  5313.3   92.18  5320.5   91.88
#Mann= 3 ,-1 , 0
  4700.3     .05       0  5025.1     .05       0  5031.5     .05       0
Bank Sta=5025.1,5031.5
XS Rating Curve= 0 ,0
Exp/Cntr=0.3,0.1

Type RM Length L Ch R = 1 ,16341   ,415,415,415
BEGIN DESCRIPTION:
TRIB 1A TO COLETO CREEK 27.0
END DESCRIPTION:
XS GIS Cut Line= 3
      2579424.96     13449575.03        2579775.       13449325.
      2579875.01     13448974.97
#Sta/Elev= 30
  4574.3   93.19  4602.6    92.4  4638.2   89.62  4646.9   89.76  4718.1   86.14
  4783.3   84.26    4825   80.34  4854.5   79.21  4881.6   77.28  4904.9    76.9
  4911.1   76.09  4940.6   75.09  4955.3   75.66    4973    73.4  4973.5    72.9
  4978.9    72.9  4979.4    73.4  4982.3   75.19  4997.1   76.48  5026.6   76.25
  5046.1   77.56  5118.9    79.9  5139.7   82.12    5167   83.56  5212.5   84.74
  5239.8    86.7  5264.5   87.58  5278.8   87.08  5285.3   88.17  5368.5   90.96
#Mann= 3 ,-1 , 0
  4574.3     .05       0    4973     .05       0  4979.4     .05       0
Bank Sta=4973,4979.4
XS Rating Curve= 0 ,0
Exp/Cntr=0.3,0.1

Type RM Length L Ch R = 1 ,15926   ,461,461,461
BEGIN DESCRIPTION:
TRIB 1A TO COLETO CREEK 26.0
END DESCRIPTION:
XS GIS Cut Line= 3
      2579725.02     13449874.98        2579975.       13449675.
      2580274.99     13449325.01
#Sta/Elev= 30
  4672.2   91.34  4700.2   90.77  4757.8   86.45  4807.4   84.14  4813.8      83
  4821.8   83.21  4842.7    81.1  4871.5   80.01  4877.9   79.14  4900.3   78.91
  4961.1      75  4985.1   73.62  4985.7   72.79  4986.2   72.29  4992.6   72.79
  5006.1   73.33    5028   72.86  5048.9   74.04  5077.4   73.45  5126.8   74.57
  5190.4   77.96  5212.4   79.83  5247.5   81.15  5268.9   83.49    5316   86.86
  5361.1   89.68  5396.8   90.68  5431.9   92.95  5447.8   93.26  5453.3   93.56
#Mann= 6 ,-1 , 0
  4672.2     .05       0  4961.1     .07       0  4985.7     .05       0
  4992.6     .07       0    5316     .05       0  5447.8     .07       0
Bank Sta=4985.7,4992.6
XS Rating Curve= 0 ,0
Exp/Cntr=0.3,0.1

Type RM Length L Ch R = 1 ,15465   ,465,465,465
BEGIN DESCRIPTION:
TRIB 1A TO COLETO CREEK 25.0
END DESCRIPTION:
XS GIS Cut Line= 3
      2580124.98     13450125.03        2580275.       13449875.
      2580575.01     13449474.98
#Sta/Elev= 30
  4703.9   89.12  4727.3   88.15  4748.6   86.16  4762.2   85.73  4775.8   84.55
  4785.6   84.41  4902.2   75.75  4923.3   74.91  4968.7    72.8  4969.2    72.3
  4975.2    72.3  4975.7    72.8  5131.9   72.92  5166.5   75.11  5173.6   75.05
  5231.9    78.8  5238.2   78.73  5273.6   81.36  5288.2   81.89  5302.8    83.6
  5345.5   85.22    5359   86.55  5381.9   87.38  5388.2   88.19  5417.4   88.64
  5423.6   89.55  5431.9   89.75  5467.4   92.74  5488.2      94  5495.5   93.58
#Mann= 5 ,-1 , 0
  4703.9     .05       0  4923.3    .033       0  4968.7    .033       0
  4975.7    .033       0  5166.5     .05       0
Bank Sta=4968.7,4975.7
XS Rating Curve= 0 ,0
Exp/Cntr=0.3,0.1

Type RM Length L Ch R = 1 ,15000   ,451,451,451
BEGIN DESCRIPTION:
TRIB 1A TO COLETO CREEK 24.0
END DESCRIPTION:
XS GIS Cut Line= 3
      2580574.99     13450375.02        2580675.       13449975.
        2580675.     13449625.03
#Sta/Elev= 30
  4593.1   92.64  4634.4   89.53  4657.5   88.72  4727.1   84.09    4758   81.14
  4776.1   80.77  4817.3   77.86  4822.5   78.03  4893.8   72.85  4936.5   70.59
  4964.2   68.84  4974.5   67.12  4978.7   65.57  4979.2   65.07  4985.7   65.57
  4987.4   66.77  4995.1   65.85  5002.9   67.82  5015.4    68.9  5047.8   68.78
  5105.4   70.47  5121.3   71.89  5155.4   73.42  5175.4   75.79  5195.4   75.54
  5215.4   77.88  5245.4   79.04  5275.4    82.5  5332.6   86.54  5355.4   88.16
#Mann= 8 ,-1 , 0
  4593.1     .05       0  4893.8     .07       0  4936.5     .12       0
  4978.7     .05       0  4985.7     .12       0  5047.8     .07       0
  5121.3    .035       0  5332.6     .07       0
Bank Sta=4978.7,4985.7
XS Rating Curve= 0 ,0
Exp/Cntr=0.3,0.1

Type RM Length L Ch R = 1 ,14549   ,430,430,430
BEGIN DESCRIPTION:
TRIB 1A TO COLETO CREEK 23.0
END DESCRIPTION:
XS GIS Cut Line= 3
      2581274.98     13450224.96        2581075.       13449825.
      2580725.03     13449475.03
#Sta/Elev= 30
  4557.4   98.88  4571.3    96.6  4588.1   95.49  4616.1   91.94  4633.7   90.84
  4689.5   85.66  4736.2   82.51    4767    79.3  4817.3   75.48  4906.7   69.72
  4951.5   67.72  4969.2    65.6  4978.7   64.06  4979.2   63.56  4985.8   64.06
  4996.2   66.38  5018.7   66.32  5034.8   64.97    5047   64.42  5075.3   67.33
  5103.6   68.02    5146   70.46  5273.3   78.91  5329.8   84.21  5340.8   84.54
  5358.1   85.14  5389.6   87.78  5414.7   90.01  5471.3   93.15  5499.5   93.91
#Mann= 9 ,-1 , 0
  4557.4     .07       0  4633.7    .035       0  4689.5     .07       0
  4969.2     .12       0  4978.7     .05       0  4985.8     .12       0
  5034.8     .07       0  5340.8    .035       0  5389.6     .05       0
Bank Sta=4978.7,4985.8
XS Rating Curve= 0 ,0
Exp/Cntr=0.3,0.1

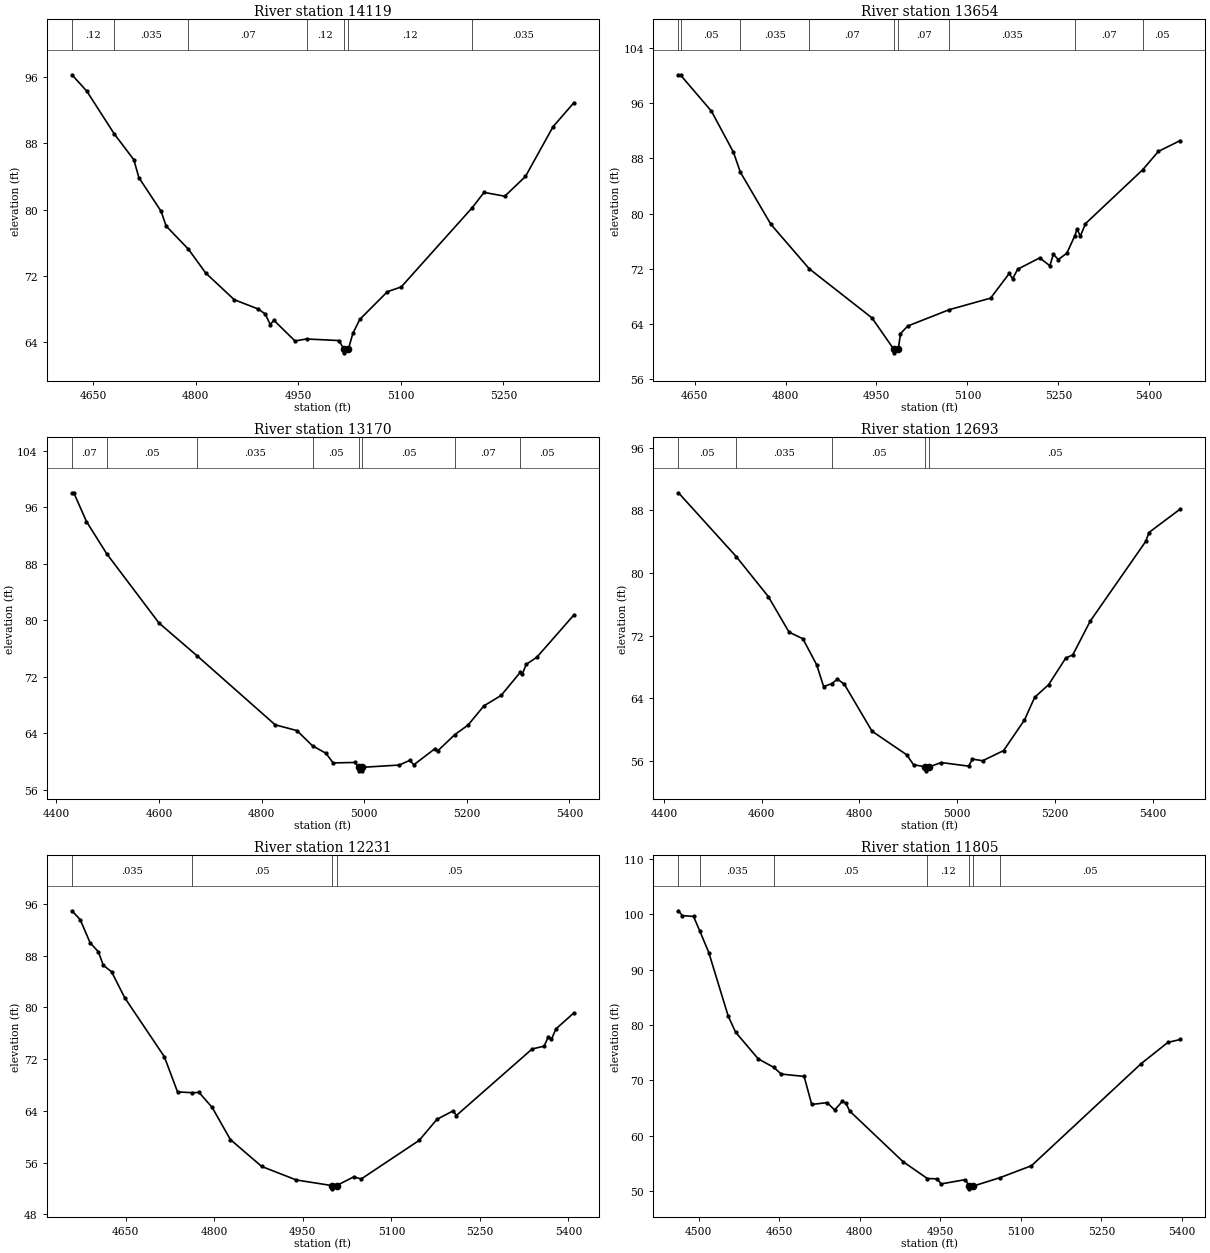
Type RM Length L Ch R = 1 ,14119   ,465,465,465
BEGIN DESCRIPTION:
TRIB 1A TO COLETO CREEK 22.0
END DESCRIPTION:
XS GIS Cut Line= 3
      2581574.99     13450024.97        2581425.       13449675.
        2581475.     13449325.01
#Sta/Elev= 30
  4618.8   96.24  4640.5   94.27  4680.7   89.12  4709.4      86  4716.7   83.85
  4749.3   79.79  4756.6   78.02  4789.3   75.22  4814.6   72.35  4856.3   69.14
  4890.8   68.04  4901.6   67.43  4908.9   66.15  4914.3   66.66  4945.2   64.17
    4962   64.41  5009.7   64.22  5016.2   63.24  5016.7   62.74  5023.4   63.24
  5029.9   65.09    5040   66.77  5080.4   70.11  5100.6   70.68  5204.4   80.22
  5221.8   82.07  5252.1   81.61  5282.4   83.99  5322.8   89.99  5353.1   92.86
#Mann= 7 ,-1 , 0
  4618.8     .12       0  4680.7    .035       0  4789.3     .07       0
    4962     .12       0  5016.2     .05       0  5023.4     .12       0
  5204.4    .035       0
Bank Sta=5016.2,5023.4
XS Rating Curve= 0 ,0
Exp/Cntr=0.3,0.1

Type RM Length L Ch R = 1 ,13654   ,484,484,484
BEGIN DESCRIPTION:
TRIB 1A TO COLETO CREEK 21.0
END DESCRIPTION:
XS GIS Cut Line= 3
      2581724.99     13450075.01        2581875.       13449725.
      2581675.01     13449325.02
#Sta/Elev= 30
  4623.3  100.16    4627  100.09  4677.7   94.87    4714   88.91  4725.4   86.01
  4775.6   78.45  4839.1   71.97  4942.5   64.84  4978.7   60.26  4979.2   59.76
  4985.9   60.26  4989.6   62.54  5001.4   63.65    5070   66.03  5138.3   67.71
    5169   71.29  5174.6   70.53    5183   71.91  5219.3   73.56  5236.1   72.41
  5241.7   74.07  5250.1   73.32    5264   74.23  5277.4    76.8  5280.8   77.73
  5286.4   76.72  5294.8   78.53  5389.2   86.36    5415   89.02  5451.3   90.61
#Mann= 9 ,-1 , 0
  4623.3     .12       0    4627     .05       0  4725.4    .035       0
  4839.1     .07       0  4978.7     .05       0  4985.9     .07       0
    5070    .035       0  5277.4     .07       0  5389.2     .05       0
Bank Sta=4978.7,4985.9
XS Rating Curve= 0 ,0
Exp/Cntr=0.3,0.1

Type RM Length L Ch R = 1 ,13170   ,477,477,477
BEGIN DESCRIPTION:
TRIB 1A TO COLETO CREEK 20.0
END DESCRIPTION:
XS GIS Cut Line= 3
      2581924.99     13450225.01        2582325.       13449825.
        2582225.     13449425.02
#Sta/Elev= 30
  4430.4   98.06    4434   98.06  4458.7   93.99  4498.2   89.42  4600.1   79.61
  4674.5   74.96  4826.4    65.2  4868.8   64.38  4899.3   62.22  4925.4   61.17
  4939.5    59.8    4982   59.87  4988.9   59.18  4989.4   58.68  4995.8   58.68
  4996.3   59.18  5068.3    59.5  5088.9   60.17  5096.6   59.53  5137.8   61.82
    5143   61.49  5176.4    63.8  5202.3   65.16  5233.2   67.88  5266.7   69.35
  5304.5   72.67  5307.9   72.34  5315.6   73.76  5336.3   74.76  5408.4   80.74
#Mann= 8 ,-1 , 0
  4430.4     .07       0  4498.2     .05       0  4674.5    .035       0
  4899.3     .05       0  4988.9     .05       0  4996.3     .05       0
  5176.4     .07       0  5304.5     .05       0
Bank Sta=4988.9,4996.3
XS Rating Curve= 0 ,0
Exp/Cntr=0.3,0.1

Type RM Length L Ch R = 1 ,12693   ,462,462,462
BEGIN DESCRIPTION:
TRIB 1A TO COLETO CREEK 19.0
END DESCRIPTION:
XS GIS Cut Line= 3
      2582325.04     13450324.96        2582725.       13449925.
      2583024.99     13449575.01
#Sta/Elev= 30
  4429.7   90.25  4547.8   82.11  4613.5      77  4655.9   72.46  4684.2   71.62
  4712.5   68.28  4726.6   65.52  4743.1   65.88  4754.9   66.47  4769.1    65.8
  4825.6   59.82  4896.3   56.82  4910.5   55.55    4935   55.26  4935.5   54.76
  4942.5   55.26  4967.1   55.82  5023.3   55.36    5031   56.26  5051.9   56.05
  5094.7   57.34  5137.5   61.25  5158.3   64.14  5186.9   65.76    5222   69.16
  5236.3   69.56  5271.9   73.86  5385.5   84.04  5392.1   85.18  5456.3   88.18
#Mann= 5 ,-1 , 0
  4429.7     .05       0  4547.8    .035       0  4743.1     .05       0
    4935     .05       0  4942.5     .05       0
Bank Sta=4935,4942.5
XS Rating Curve= 0 ,0
Exp/Cntr=0.3,0.1

Type RM Length L Ch R = 1 ,12231   ,426,426,426
BEGIN DESCRIPTION:
TRIB 1A TO COLETO CREEK 18.0
END DESCRIPTION:
XS GIS Cut Line= 3
      2582874.98     13450575.03        2583075.       13450175.
        2583125.     13449774.96
#Sta/Elev= 30
  4558.7   94.92  4572.7   93.55  4589.5   89.97  4603.5   88.59  4611.8    86.5
  4625.8    85.5  4648.2   81.48  4715.3   72.37  4737.6   66.94  4762.6   66.81
    4774   66.86  4796.3   64.54  4827.1   59.58  4880.2   55.42  4938.9   53.33
  4999.4   52.46  4999.9   51.96    5007   52.46  5036.2   53.81  5048.8   53.48
    5147   59.44  5177.3   62.71    5205   64.02    5210   63.28  5338.5   73.57
  5358.7      74  5366.2   75.49  5371.3   75.06  5378.8   76.67  5409.1   79.13
#Mann= 4 ,-1 , 0
  4558.7    .035       0  4762.6     .05       0  4999.4     .05       0
    5007     .05       0
Bank Sta=4999.4,5007
XS Rating Curve= 0 ,0
Exp/Cntr=0.3,0.1

Type RM Length L Ch R = 1 ,11805   ,408,408,408
BEGIN DESCRIPTION:
TRIB 1A TO COLETO CREEK 17.0
END DESCRIPTION:
XS GIS Cut Line= 3
      2582974.97     13450725.02        2583375.       13450375.
      2583725.04     13450174.98
#Sta/Elev= 30
  4462.4  100.59  4469.6   99.71  4490.4   99.58  4501.9      97  4518.9   93.05
    4555   81.61  4568.7   78.72    4611   73.89  4639.8   72.38  4653.7   71.16
  4696.4   70.73  4710.6   65.68  4739.1   66.01  4753.3   64.69  4767.6   66.23
  4774.2   65.92  4781.3   64.49  4880.5   55.38  4925.9   52.33  4944.1   52.27
  4951.7   51.36  4996.8   52.13  5003.8   50.97  5004.3   50.47  5011.4   50.97
  5061.1   52.48  5119.9   54.64  5324.4   73.06    5374   76.87  5397.1   77.39
#Mann= 7 ,-1 , 0
  4462.4     .05       0  4501.9    .035       0  4639.8     .05       0
  4925.9     .12       0  5003.8     .05       0  5011.4     .12       0
  5061.1     .05       0
Bank Sta=5003.8,5011.4
XS Rating Curve= 0 ,0
Exp/Cntr=0.3,0.1

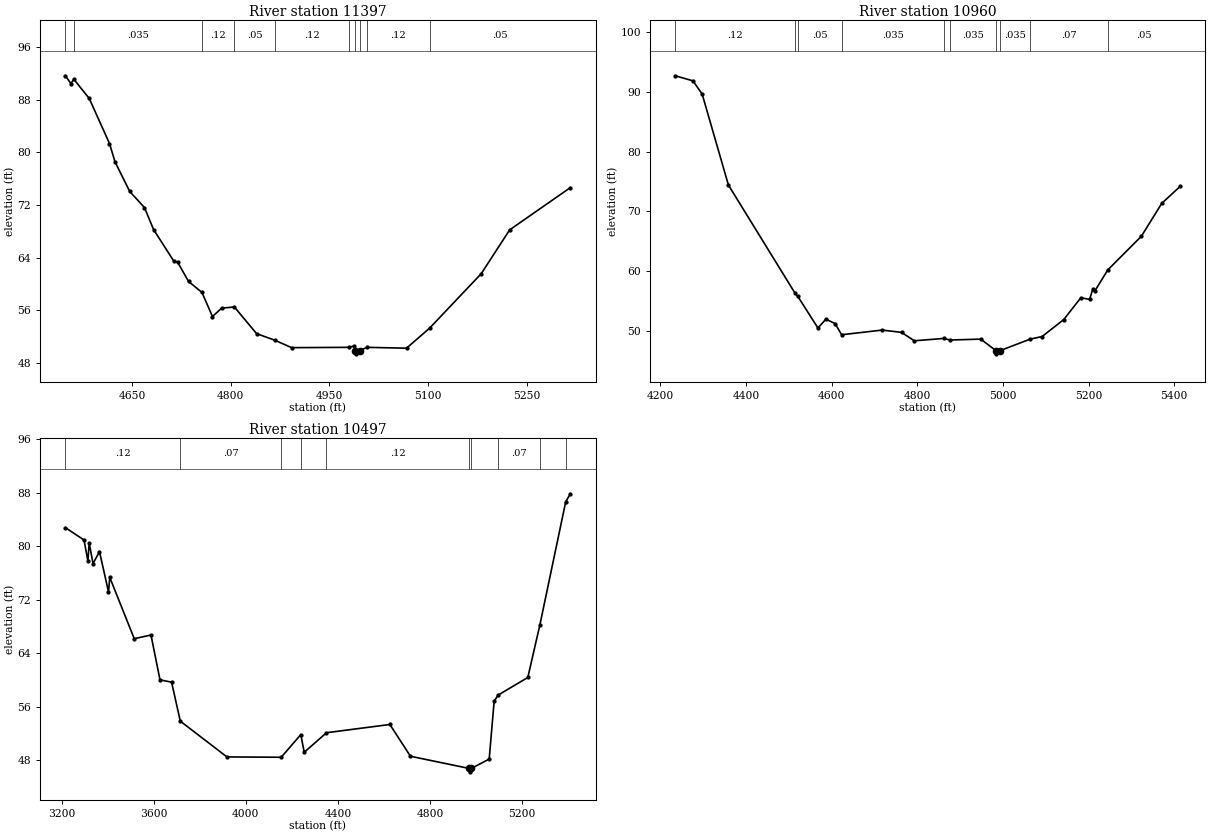
Type RM Length L Ch R = 1 ,11397   ,437,437,437
BEGIN DESCRIPTION:
TRIB 1A TO COLETO CREEK 16.0
END DESCRIPTION:
XS GIS Cut Line= 3
      2583174.99       13450825.        2583575.       13450625.
      2583775.01     13450374.98
#Sta/Elev= 30
  4548.6   91.66    4557   90.48  4561.5   91.12  4584.9   88.21  4615.7   81.35
  4624.1   78.56  4646.4   74.06  4668.8   71.61  4682.8   68.24  4713.5   63.44
  4719.1   63.31  4735.9   60.35  4756.2   58.69  4772.2   55.02  4786.2    56.3
  4805.5   56.47  4839.3   52.41  4867.6   51.39  4892.4   50.28  4979.1   50.33
  4987.4   50.53  4989.2   49.84  4989.7   49.34  4996.9   49.84  5006.8   50.33
  5067.1    50.2  5102.1   53.24  5180.7   61.54  5223.9   68.21    5316   74.63
#Mann= 10 ,-1 , 0
  4548.6     .12       0  4561.5    .035       0  4756.2     .12       0
  4805.5     .05       0  4867.6     .12       0  4979.1     .05       0
  4989.2     .05       0  4996.9     .05       0  5006.8     .12       0
  5102.1     .05       0
Bank Sta=4989.2,4996.9
XS Rating Curve= 0 ,0
Exp/Cntr=0.3,0.1

Type RM Length L Ch R = 1 ,10960   ,463,463,463
BEGIN DESCRIPTION:
TRIB 1A TO COLETO CREEK 15.0
END DESCRIPTION:
XS GIS Cut Line= 3
      2583174.96     13451075.01        2583925.       13450875.
      2583874.99     13450474.96
#Sta/Elev= 30
  4234.5   92.67  4275.9   91.82  4297.3   89.62  4358.7   74.41  4514.2   56.35
  4520.7   55.82  4567.7   50.53  4586.4      52  4607.8   51.27  4623.2    49.4
  4717.7   50.18    4763    49.8  4792.8   48.39  4861.2   48.78  4876.6   48.52
    4948   48.67  4984.3   46.71  4984.8   46.21    4992   46.71  5063.1   48.66
  5091.4    49.1  5141.8   51.93  5182.1   55.59  5202.2    55.3  5209.8      57
  5214.8   56.74  5244.7   60.22  5323.2   65.85    5371   71.36  5413.9   74.19
#Mann= 10 ,-1 , 0
  4234.5     .12       0  4514.2    .035       0  4520.7     .05       0
  4623.2    .035       0  4861.2     .12       0  4876.6    .035       0
  4984.3    .035       0    4992    .035       0  5063.1     .07       0
  5244.7     .05       0
Bank Sta=4984.3,4992
XS Rating Curve= 0 ,0
Exp/Cntr=0.3,0.1

Type RM Length L Ch R = 1 ,10497   ,0,0,0
BEGIN DESCRIPTION:
TRIB 1A TO COLETO CREEK 14.0
END DESCRIPTION:
XS GIS Cut Line= 3
      2582724.96     13451775.02        2584325.       13450975.
        2584525.     13450625.01
#Sta/Elev= 30
  3216.5   82.75  3297.6    80.9  3314.4   77.76    3320   80.45  3336.7   77.37
  3364.7   79.16  3403.8   73.15  3409.4    75.3  3515.6   66.14  3588.3   66.69
  3627.4   59.98  3677.7   59.64  3715.5   53.81  3918.1   48.46  4153.7   48.41
  4238.7    51.8  4253.5   49.15  4350.2   52.08  4625.3   53.31  4714.7   48.56
  4970.7   46.73  4971.2   46.23  4978.5   46.73  5056.5   48.14  5078.1    56.8
  5095.5   57.71  5224.2   60.34  5276.7   68.22  5388.5   86.58  5408.5   87.81
#Mann= 10 ,-1 , 0
  3216.5     .12       0  3715.5     .07       0  4153.7    .035       0
  4238.7     .07       0  4350.2     .12       0  4970.7     .05       0
  4978.5     .12       0  5095.5     .07       0  5276.7     .12       0
  5388.5     .07       0
Bank Sta=4970.7,4978.5
XS Rating Curve= 0 ,0
Exp/Cntr=0.3,0.1

Chan Stop Cuts=-1
Use User Specified Reach Order=0
Composite Channel Slope=5