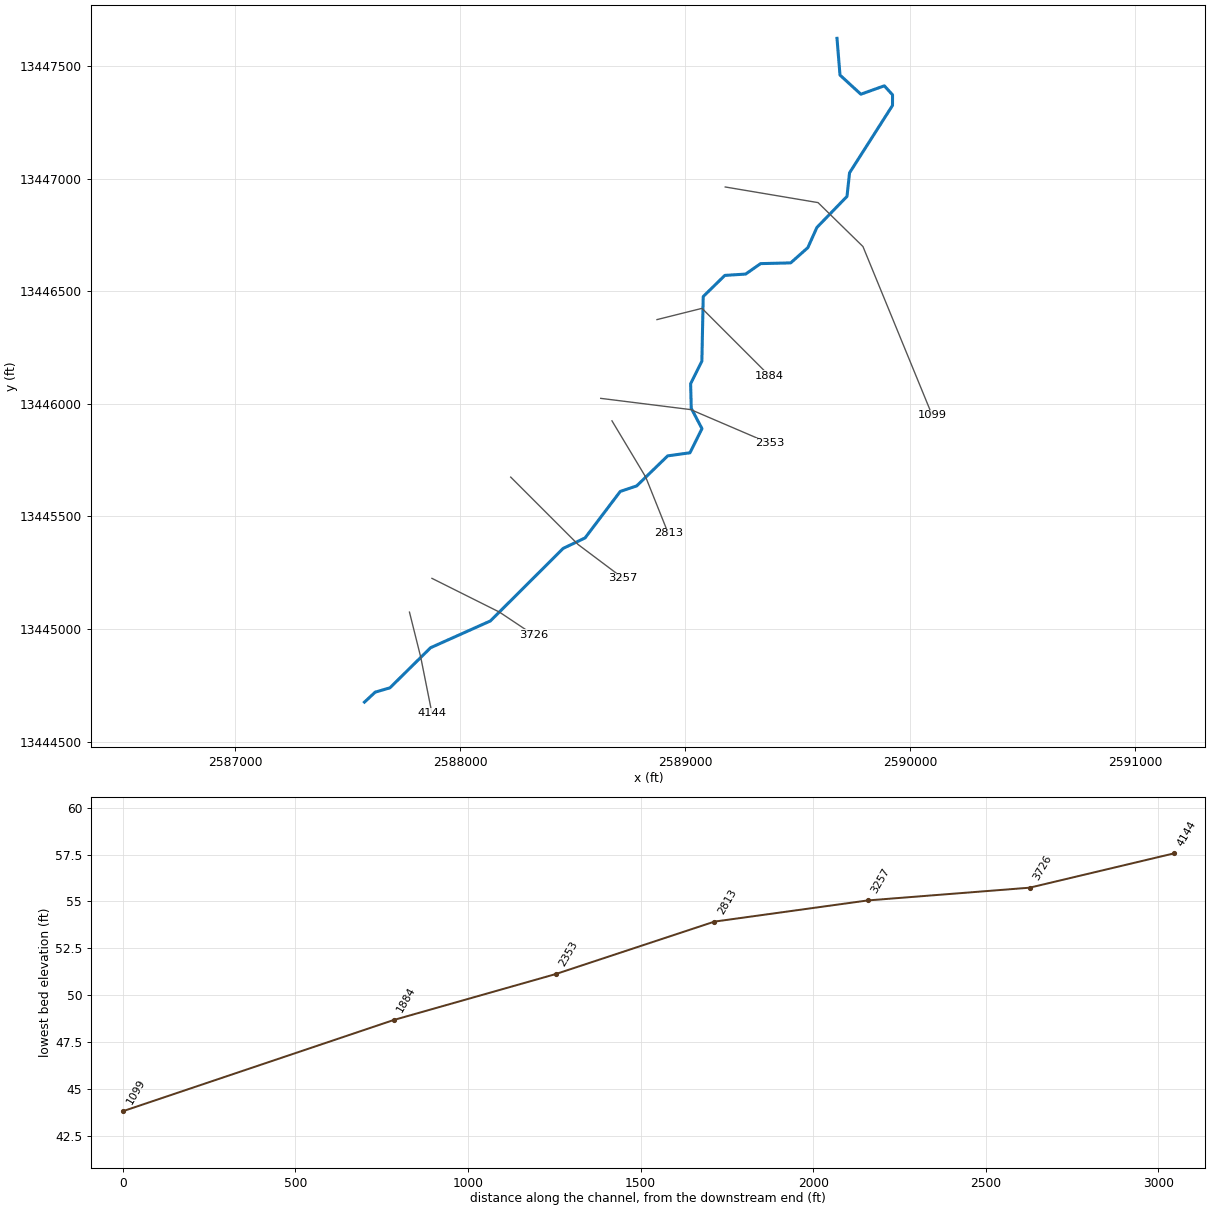
--- TRIB 1A_1 TO COLETO CREEK.prj (project) ---

Proj Title=TRIB 1A_1 TO COLETO CREEK Base Level Engineering
Current Plan=p01
Default Exp/Contr=0.3,0.1
English Units
Geom File=g01
Flow File=f01
Plan File=p01
BEGIN DESCRIPTION:
TRIB 1A_1 TO COLETO CREEK
END DESCRIPTION:

--- TRIB 1A_1 TO COLETO CREEK.p01 (plan) ---

Plan Title=Multiple Run
Short Identifier=Multiple
Geom File=g01
Flow File=f01
Subcritical Flow
K Sum by GR= 0
Std Step Tol= 0.01
Critical Tol= 0.01
Num of Std Step Trials= 20
Max Error Tol= 0.3
Flow Tol Ratio= 0.001
Split Flow NTrial= 30
Split Flow Tol= 0.02
Split Flow Ratio= 0.02
Log Output Level= 0
Friction Slope Method= 1
Unsteady Friction Slope Method= 2
Unsteady Bridges Friction Slope Method= 1
Parabolic Critical Depth
Global Vel Dist=  1 , 1 , 1
Global Log Level= 0
CheckData=True
Encroach Param= -1, 0, 0, 0
BEGIN DESCRIPTION:
Multiple Run
END DESCRIPTION:

--- TRIB 1A_1 TO COLETO CREEK.f01 (steady flow) ---

Flow Title=Multiple
Number of Profiles=7
Profile Names=10-year,25-year,50-year,1pct_min,100-year,1pct_plu,500-year
River Rch & RM= TRIB 1A_1 TO COL,Reach-1,4144
     569     878    1144     720    1436    2866    2238
River Rch & RM= TRIB 1A_1 TO COL,Reach-1,3726
     815    1285    1698    1083    2162    4313    3464
Boundary for River Rch & Prof#=TRIB 1A_1 TO COL,Reach-1,1
Up Type=0
Dn Type=3
Dn Slope=0.005
Boundary for River Rch & Prof#=TRIB 1A_1 TO COL,Reach-1,2
Up Type=0
Dn Type=3
Dn Slope=0.005
Boundary for River Rch & Prof#=TRIB 1A_1 TO COL,Reach-1,3
Up Type=0
Dn Type=3
Dn Slope=0.005
Boundary for River Rch & Prof#=TRIB 1A_1 TO COL,Reach-1,4
Up Type=0
Dn Type=3
Dn Slope=0.005
Boundary for River Rch & Prof#=TRIB 1A_1 TO COL,Reach-1,5
Up Type=0
Dn Type=3
Dn Slope=0.005
Boundary for River Rch & Prof#=TRIB 1A_1 TO COL,Reach-1,6
Up Type=0
Dn Type=3
Dn Slope=0.005
Boundary for River Rch & Prof#=TRIB 1A_1 TO COL,Reach-1,7
Up Type=0
Dn Type=3
Dn Slope=0.005

--- TRIB 1A_1 TO COLETO CREEK.g01 (geometry) ---

Geom Title=Existing Conditions

River Reach=TRIB 1A_1 TO COL,Reach-1
Reach XY= 30
      2587575.00     13444675.00      2587622.65     13444719.29
      2587688.23     13444738.57      2587868.94     13444916.86
      2588134.68     13445035.76      2588458.33     13445358.35
      2588555.23     13445404.58      2588711.76     13445611.38
      2588784.68     13445635.78      2588922.63     13445769.45
      2589021.63     13445783.15      2589074.93     13445890.37
      2589027.28     13445980.93      2589024.53     13446090.16
      2589074.48     13446190.22      2589080.45     13446477.47
      2589176.48     13446571.39      2589269.02     13446577.36
      2589335.51     13446623.77      2589469.15     13446627.06
      2589545.42     13446694.76      2589585.78     13446784.68
      2589719.48     13446922.57      2589730.77     13447027.32
      2589921.69     13447326.80      2589921.88     13447373.84
      2589885.49     13447414.02      2589781.04     13447376.65
      2589688.35     13447461.65      2589675.00     13447625.00

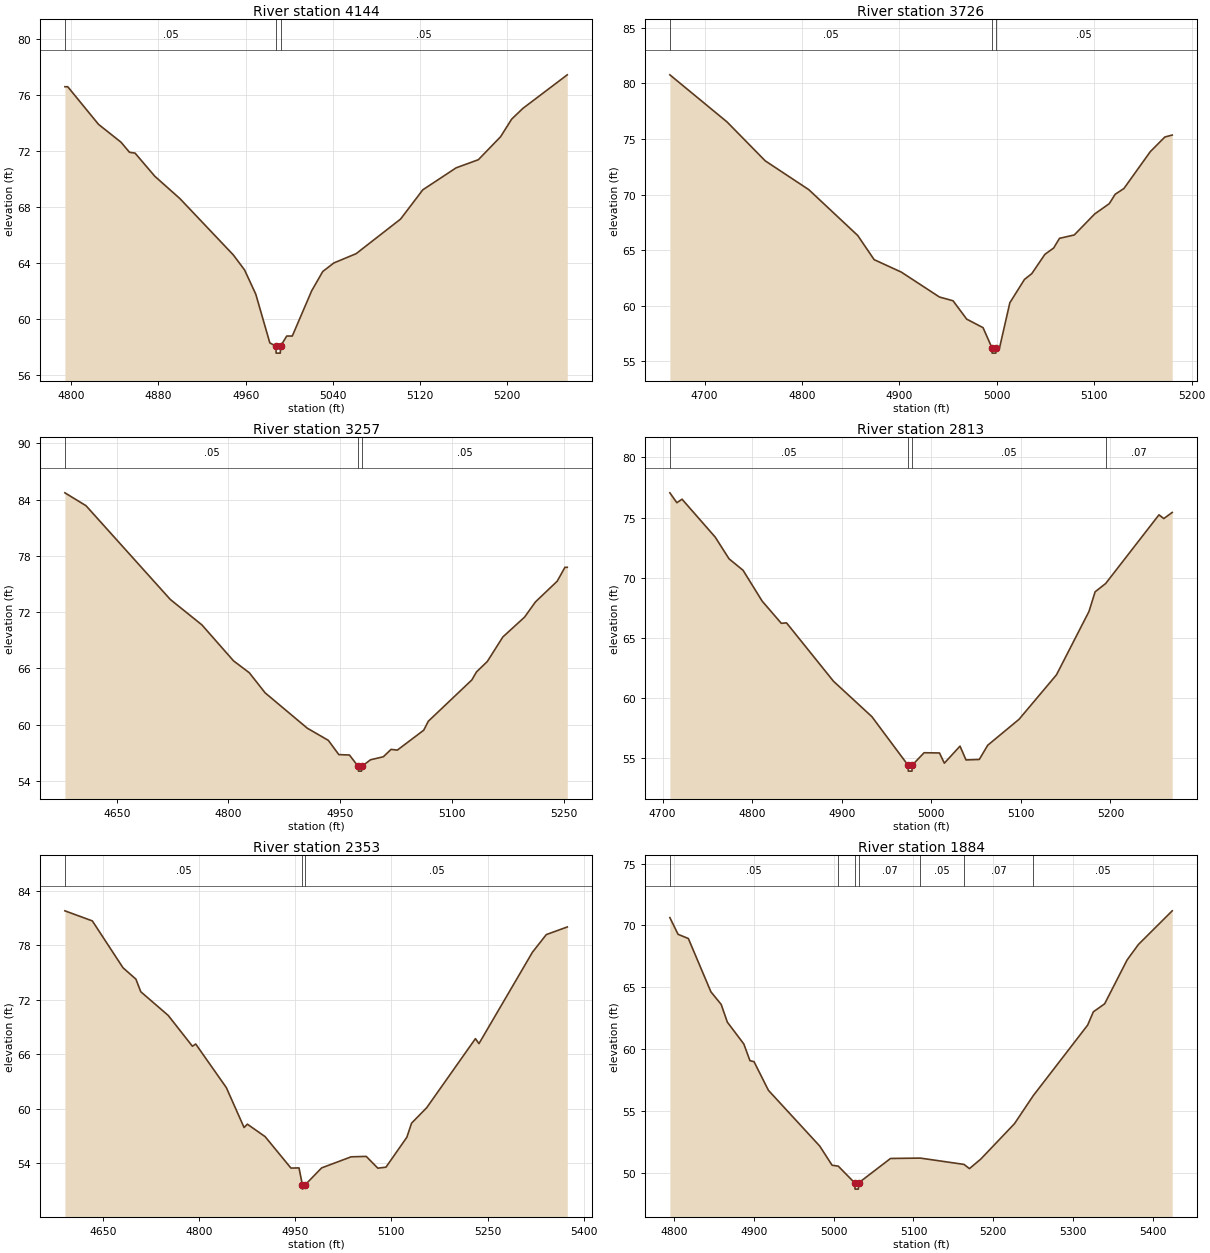
Type RM Length L Ch R = 1,4144,418,418,418
BEGIN DESCRIPTION:
TRIB 1A-1 TO COLETO CREEK 7.0
END DESCRIPTION:
XS GIS Cut Line= 3
      2587775.00     13445074.99      2587825.00     13444875.00
      2587875.00     13444625.00
#Sta/Elev= 30
  4794.1   76.58  4796.7   76.58  4825.0   73.89  4845.6   72.62  4853.4   71.90
  4858.5   71.84  4876.6   70.19  4899.7   68.59  4948.7   64.57  4959.0   63.50
  4969.3   61.77  4982.2   58.29  4987.8   58.06  4988.0   57.56  4991.8   57.56
  4992.1   58.06  4997.7   58.78  5002.8   58.78  5020.6   62.01  5030.8   63.39
  5041.0   64.00  5061.4   64.66  5102.2   67.13  5122.6   69.22  5153.2   70.79
  5173.6   71.37  5194.0   73.01  5204.2   74.27  5214.4   75.03  5255.2   77.43
#Mann=3,-1,0
  4794.1    0.05       0  4987.8    0.05       0  4992.1    0.05       0
Bank Sta=4987.8,4992.1
Exp/Cntr=0.3,0.1

Type RM Length L Ch R = 1,3726,469,469,469
BEGIN DESCRIPTION:
TRIB 1A-1 TO COLETO CREEK 6.0
END DESCRIPTION:
XS GIS Cut Line= 3
      2587874.97     13445225.02      2588175.00     13445075.00
      2588324.98     13444975.01
#Sta/Elev= 30
  4664.3   80.77  4723.0   76.53  4762.2   73.03  4806.9   70.44  4857.2   66.31
  4874.0   64.14  4901.9   63.02  4941.0   60.78  4955.0   60.44  4969.0   58.79
  4985.8   58.02  4994.8   56.23  4995.1   55.73  4998.9   55.73  4999.2   56.23
  5002.8   56.23  5013.3   60.26  5028.3   62.36  5035.8   62.88  5049.3   64.62
  5058.3   65.19  5064.3   66.06  5079.4   66.36  5100.4   68.25  5115.4   69.18
  5121.4   70.02  5130.4   70.54  5157.5   73.86  5172.5   75.18  5180.0   75.35
#Mann=3,-1,0
  4664.3    0.05       0  4994.8    0.05       0  4999.2    0.05       0
Bank Sta=4994.8,4999.2
Exp/Cntr=0.3,0.1

Type RM Length L Ch R = 1,3257,444,444,444
BEGIN DESCRIPTION:
TRIB 1A-1 TO COLETO CREEK 5.0
END DESCRIPTION:
XS GIS Cut Line= 3
      2588224.97     13445675.03      2588525.00     13445375.00
      2588725.00     13445225.00
#Sta/Elev= 30
  4580.5   84.72  4608.8   83.35  4722.0   73.35  4764.4   70.64  4806.8   66.81
  4828.0   65.54  4849.2   63.40  4905.8   59.63  4934.1   58.33  4948.2   56.81
  4962.4   56.77  4974.2   55.55  4974.5   55.05  4978.6   55.05  4978.9   55.55
  4990.7   56.26  5007.9   56.58  5018.3   57.37  5026.7   57.29  5062.1   59.41
  5068.3   60.37  5126.7   64.77  5132.9   65.62  5147.5   66.74  5168.3   69.35
  5197.5   71.47  5212.1   73.09  5241.3   75.30  5251.7   76.78  5254.8   76.78
#Mann=3,-1,0
  4580.5    0.05       0  4974.2    0.05       0  4978.9    0.05       0
Bank Sta=4974.2,4978.9
Exp/Cntr=0.3,0.1

Type RM Length L Ch R = 1,2813,460,460,460
BEGIN DESCRIPTION:
TRIB 1A-1 TO COLETO CREEK 4.0
END DESCRIPTION:
XS GIS Cut Line= 3
      2588674.99     13445925.02      2588825.00     13445675.00
      2588924.99     13445425.02
#Sta/Elev= 30
  4708.2   77.06  4716.0   76.24  4721.8   76.53  4758.8   73.38  4774.3   71.57
  4789.9   70.62  4811.2   68.06  4832.6   66.21  4838.4   66.25  4890.9   61.39
  4933.7   58.45  4974.0   54.42  4974.4   53.92  4978.5   53.92  4978.8   54.42
  4992.0   55.45  5009.2   55.43  5014.6   54.58  5032.1   56.00  5038.8   54.85
  5053.6   54.89  5063.0   56.07  5098.0   58.23  5139.8   61.93  5176.1   67.20
  5182.9   68.83  5194.7   69.52  5254.2   75.23  5259.6   74.92  5269.0   75.43
#Mann=4,-1,0
  4708.2    0.05       0  4974.0    0.05       0  4978.8    0.05       0
  5194.7    0.07       0
Bank Sta=4974,4978.8
Exp/Cntr=0.3,0.1

Type RM Length L Ch R = 1,2353,469,469,469
BEGIN DESCRIPTION:
TRIB 1A-1 TO COLETO CREEK 3.0
END DESCRIPTION:
XS GIS Cut Line= 3
      2588625.03     13446025.00      2589025.00     13445975.00
      2589375.02     13445824.99
#Sta/Elev= 30
  4590.5   81.80  4633.3   80.69  4681.2   75.52  4701.3   74.27  4708.9   72.88
  4751.7   70.27  4789.5   66.87  4794.6   67.12  4842.4   62.31  4870.1   57.91
  4875.2   58.28  4902.9   56.91  4943.2   53.44  4955.8   53.46  4961.0   51.62
  4961.3   51.12  4965.8   51.62  4991.1   53.46  5037.1   54.68  5060.7   54.73
  5078.8   53.43  5091.5   53.54  5124.1   56.84  5131.4   58.39  5155.0   60.09
  5231.1   67.71  5236.6   67.16  5320.0   77.23  5341.7   79.18  5374.4   80.02
#Mann=3,-1,0
  4590.5    0.05       0  4961.0    0.05       0  4965.8    0.05       0
Bank Sta=4961,4965.8
Exp/Cntr=0.3,0.1

Type RM Length L Ch R = 1,1884,785,785,785
BEGIN DESCRIPTION:
TRIB 1A-1 TO COLETO CREEK 2.0
END DESCRIPTION:
XS GIS Cut Line= 3
      2588875.01     13446375.00      2589075.00     13446425.00
      2589374.99     13446125.01
#Sta/Elev= 30
  4794.3   70.63  4804.6   69.28  4817.5   68.94  4845.8   64.63  4858.7   63.61
  4866.4   62.18  4887.1   60.41  4894.8   59.06  4899.9   58.98  4918.0   56.66
  4982.4   52.15  4997.9   50.60  5005.6   50.53  5026.3   49.17  5026.7   48.67
  5030.8   48.67  5031.1   49.17  5071.2   51.15  5108.6   51.18  5163.4   50.67
  5170.2   50.33  5184.3   51.09  5226.7   53.96  5250.3   56.23  5318.6   61.94
  5325.7   63.01  5339.9   63.66  5368.1   67.21  5382.3   68.46  5424.7   71.18
#Mann=7,-1,0
  4794.3    0.05       0  5005.6    0.07       0  5026.3    0.05       0
  5031.1    0.07       0  5108.6    0.05       0  5163.4    0.07       0
  5250.3    0.05       0
Bank Sta=5026.3,5031.1
Exp/Cntr=0.3,0.1

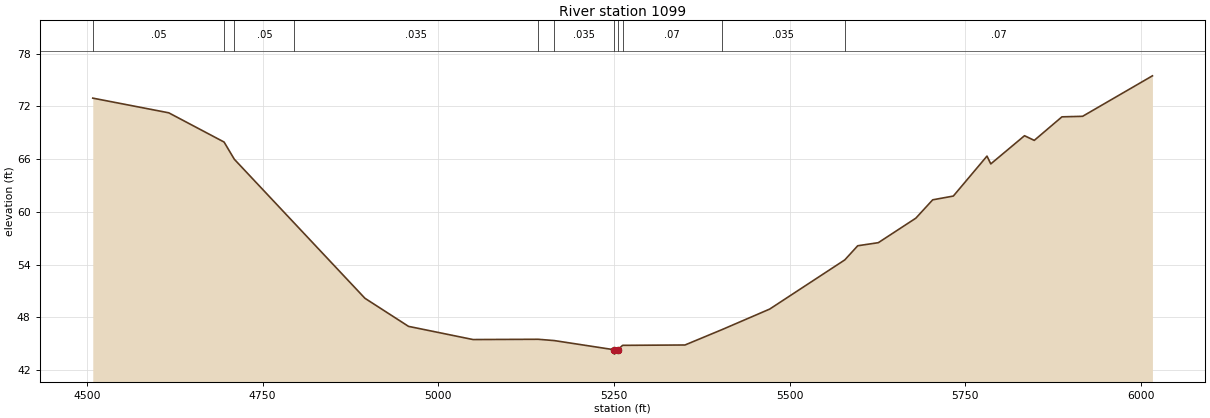
Type RM Length L Ch R = 1,1099,0,0,0
BEGIN DESCRIPTION:
TRIB 1A-1 TO COLETO CREEK 1.0
END DESCRIPTION:
XS GIS Cut Line= 4
      2589178.38     13446964.39      2589590.75     13446894.94
      2589790.40     13446699.63      2590098.29     13445949.43
#Sta/Elev= 30
  4508.2   72.95  4616.3   71.28  4695.1   67.95  4709.7   65.99  4795.3   58.70
  4895.6   50.16  4957.7   46.96  5049.5   45.46  5142.4   45.49  5165.3   45.34
  5250.3   44.30  5250.7   43.80  5255.5   44.30  5262.4   44.80  5351.2   44.84
  5403.9   46.59  5471.8   48.93  5578.7   54.53  5597.1   56.14  5626.4   56.49
  5679.8   59.28  5703.8   61.37  5733.2   61.80  5781.1   66.35  5786.5   65.46
  5834.5   68.67  5848.4   68.14  5887.8   70.82  5917.2   70.88  6016.6   75.49
#Mann=11,-1,0
  4508.2    0.05       0  4695.1   0.035       0  4709.7    0.05       0
  4795.3   0.035       0  5142.4    0.07       0  5165.3   0.035       0
  5250.3   0.035       0  5255.5   0.035       0  5262.4    0.07       0
  5403.9   0.035       0  5578.7    0.07       0
Bank Sta=5250.3,5255.5
Exp/Cntr=0.3,0.1

Chan Stop Cuts=-1