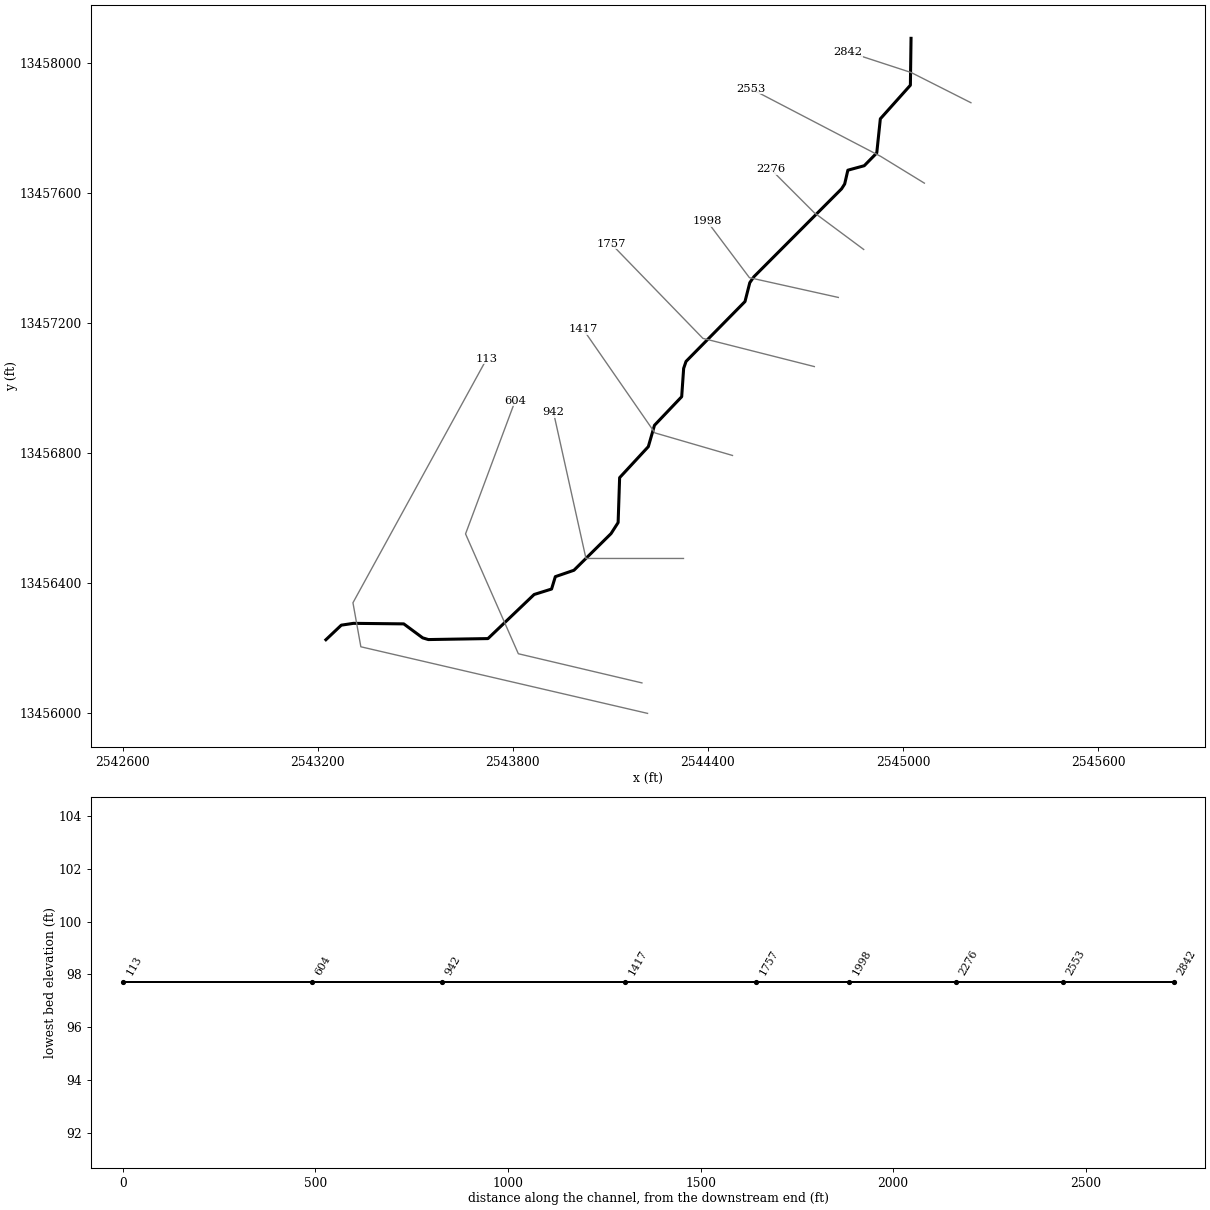
--- TRIB 2 TO COLETO CREEK RESERVOIR.prj (project) ---

Proj Title=TRIB 2 TO COLETO CREEK RESERVOIR Base Level Engineering
Current Plan=p01
Default Exp/Contr=0.3,0.1
English Units
Geom File=g01
Flow File=f01
Plan File=p01
Y Axis Title=Elevation
X Axis Title(PF)=Main Channel Distance
X Axis Title(XS)=Station
BEGIN DESCRIPTION:
TRIB 2 TO COLETO CREEK RESERVOIR
END DESCRIPTION:
DSS Export Rating Curves= 0
DSS Export Rating Curve Sorted= 0
DSS Export Volume Flow Curves= 0
DXF OffsetX= 0
DXF OffsetY= 0
DXF ScaleX= 1
DXF ScaleY= 10

--- TRIB 2 TO COLETO CREEK RESERVOIR.p01 (plan) ---

Plan Title=Multiple Run
Short Identifier=Multiple
Geom File=g01
Flow File=f01
Subcritical Flow
K Sum by GR= 0
Std Step Tol= 0.01
Critical Tol= 0.01
Num of Std Step Trials= 20
Max Error Tol= 0.3
Flow Tol Ratio= 0.001
Split Flow NTrial= 30
Split Flow Tol= 0.02
Split Flow Ratio= 0.02
Log Output Level= 0
Friction Slope Method= 1
Unsteady Friction Slope Method= 2
Unsteady Bridges Friction Slope Method= 1
Parabolic Critical Depth
Global Vel Dist=  1 , 1 , 1
Global Log Level= 0
CheckData=True
Encroach Param= -1, 0, 0, 0
BEGIN DESCRIPTION:
Multiple Run
END DESCRIPTION:

--- TRIB 2 TO COLETO CREEK RESERVOIR.f01 (steady flow) ---

Flow Title=Multiple
Program Version=4.10
Number of Profiles= 7
Profile Names=10-year,25-year,50-year,1pct_min,100-year,1pct_plu,500-year
River Rch & RM=TRIB 2 TO COLETO,Reach-1         ,2842
     202     297     374     229     457     912     673
Boundary for River Rch & Prof#=TRIB 2 TO COLETO,Reach-1         , 1
Up Type= 0
Dn Type= 3
Dn Slope=0.0003
Boundary for River Rch & Prof#=TRIB 2 TO COLETO,Reach-1         , 2
Up Type= 0
Dn Type= 3
Dn Slope=0.0003
Boundary for River Rch & Prof#=TRIB 2 TO COLETO,Reach-1         , 3
Up Type= 0
Dn Type= 3
Dn Slope=0.0003
Boundary for River Rch & Prof#=TRIB 2 TO COLETO,Reach-1         , 4
Up Type= 0
Dn Type= 3
Dn Slope=0.0003
Boundary for River Rch & Prof#=TRIB 2 TO COLETO,Reach-1         , 5
Up Type= 0
Dn Type= 3
Dn Slope=0.0003
Boundary for River Rch & Prof#=TRIB 2 TO COLETO,Reach-1         , 6
Up Type= 0
Dn Type= 3
Dn Slope=0.0003
Boundary for River Rch & Prof#=TRIB 2 TO COLETO,Reach-1         , 7
Up Type= 0
Dn Type= 3
Dn Slope=0.0003
DSS Import GetInterval= 0
DSS Import GetPeak= 0
DSS Import FillOption= 0

--- TRIB 2 TO COLETO CREEK RESERVOIR.g01 (geometry) ---

Geom Title=Existing Conditions
Program Version=4.10

River Reach=TRIB 2 TO COLETO,Reach-1
Reach XY= 30
        2545025.       13458075.      2545022.98     13457930.84
      2544930.54     13457827.42      2544919.54     13457722.34
      2544881.08     13457683.15      2544830.65     13457669.36
      2544820.88     13457627.01      2544811.28     13457612.02
      2544541.65     13457341.67      2544528.98     13457323.35
      2544514.22     13457265.32      2544332.86     13457081.17
      2544325.53     13457059.78      2544319.46     13456972.58
       2544235.8     13456884.67      2544216.82     13456818.96
      2544128.55     13456723.53      2544123.94     13456585.44
      2544102.14     13456551.47        2543988.     13456438.69
      2543930.77     13456419.02      2543919.23     13456380.98
      2543865.57     13456364.15      2543723.54     13456228.54
      2543540.22     13456225.52      2543522.67     13456230.75
      2543464.49     13456273.78      2543309.83     13456275.41
      2543272.41     13456269.86        2543225.       13456225.

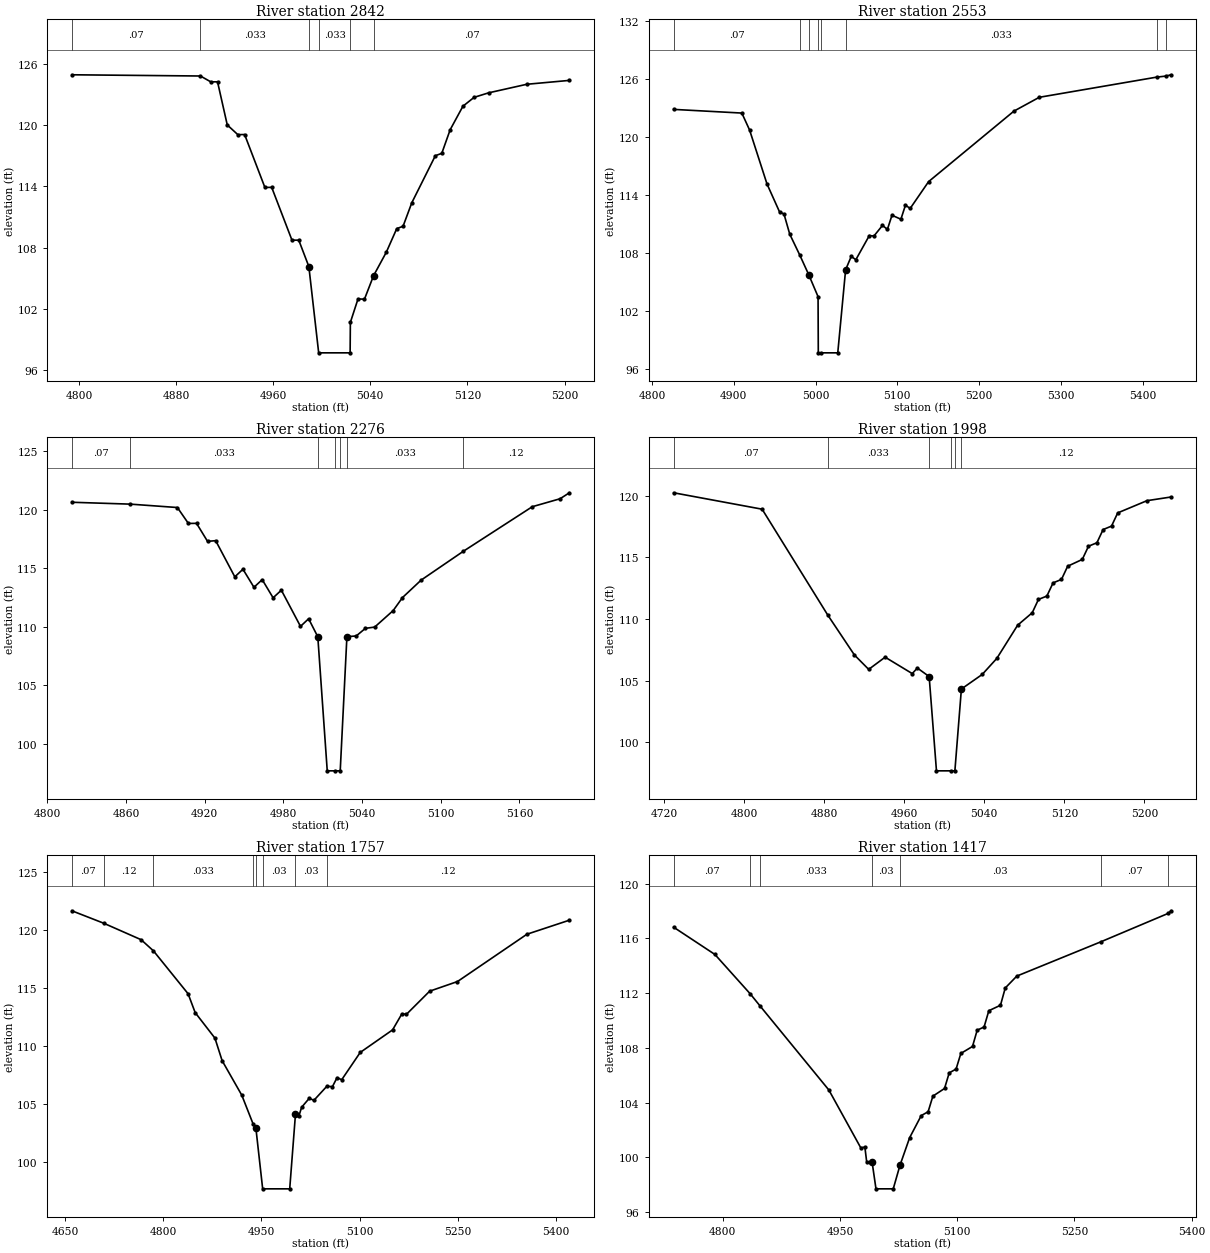
Type RM Length L Ch R = 1 ,2842    ,289,289,289
BEGIN DESCRIPTION:
TRIB 2 TO COLETO CREEK RESERVOIR 4.0
END DESCRIPTION:
XS GIS Cut Line= 3
      2545209.24     13457876.94      2545025.57     13457969.77
      2544831.67     13458033.17
#Sta/Elev= 30
  4794.2  124.92  4900.1   124.8  4908.6  124.23  4914.2  124.23  4922.2  120.01
  4930.9  119.06  4936.5  119.07  4953.2  113.89  4958.8   113.9  4975.5  108.73
  4981.1  108.73  4989.4  106.15  4997.5    97.7  5023.4    97.7  5023.6  100.68
  5029.9  102.98  5035.2  102.95  5042.7  105.25  5053.2  107.55  5061.8  109.86
    5067  110.09  5074.2  112.39  5093.6     117  5098.9  117.23  5105.8  119.54
  5116.3  121.84  5125.5  122.71  5137.4  123.15  5168.9  123.99    5204  124.37
#Mann= 6 ,-1 , 0
  4794.2     .07       0  4900.1    .033       0  4989.4    .033       0
  4997.5    .033       0  5023.6    .033       0  5042.7     .07       0
Bank Sta=4989.4,5042.7
XS Rating Curve= 0 ,0
Exp/Cntr=0.3,0.1

Type RM Length L Ch R = 1 ,2553    ,277,277,277
BEGIN DESCRIPTION:
Mapping XS b6a6f9e8
END DESCRIPTION:
XS GIS Cut Line= 3
      2545066.08     13457629.51      2544931.49       13457712.
       2544531.9     13457920.13
#Sta/Elev= 30
  4826.5  122.88  4909.9   122.5  4919.4  120.74  4940.7  115.16  4956.2  112.24
  4961.4  112.07  4968.5  109.97  4980.7  107.82  4991.7  105.78  5003.1  103.51
  5003.4    97.7  5007.1    97.7  5027.2    97.7  5036.8  106.29  5043.7  107.68
  5049.3  107.33  5065.8  109.83  5071.4  109.78  5081.9  110.88  5087.9  110.47
  5093.5  111.93  5104.4  111.52    5110  112.98  5115.7  112.63  5138.3  115.41
  5242.6   122.7  5273.6  124.13  5417.4  126.22    5428  126.32  5434.9  126.46
#Mann= 8 ,-1 , 0
  4826.5     .07       0  4980.7    .033       0  4991.7    .033       0
  5003.1    .033       0  5007.1    .033       0  5036.8    .033       0
  5417.4    .035       0    5428     .07       0
Bank Sta=4991.7,5036.8
XS Rating Curve= 0 ,0
Exp/Cntr=0.3,0.1

Type RM Length L Ch R = 1 ,2276    ,278,278,278
BEGIN DESCRIPTION:
Mapping XS 7ff197a5
END DESCRIPTION:
XS GIS Cut Line= 3
      2544879.38     13457425.56       2544727.5     13457538.38
      2544592.94     13457672.94
#Sta/Elev= 30
  4818.6  120.64  4863.2  120.48  4899.1  120.19  4907.5  118.83  4913.7  118.84
  4922.1   117.3  4928.3  117.36  4942.9  114.27  4949.1  114.92  4957.5  113.38
  4963.8  114.03  4972.1  112.48  4978.4  113.13    4993  110.04  4999.2  110.69
  5006.2  109.15  5013.4    97.7  5019.3    97.7  5023.3    97.7  5028.4  109.16
  5035.5  109.22  5042.5  109.87  5049.6  109.98  5063.7  111.39  5070.8   112.5
    5085  113.99  5117.3  116.46  5169.8  120.26    5191  120.94  5198.1  121.45
#Mann= 7 ,-1 , 0
  4818.6     .07       0  4863.2    .033       0  5006.2    .033       0
  5019.3    .033       0  5023.3    .033       0  5028.4    .033       0
  5117.3     .12       0
Bank Sta=5006.2,5028.4
XS Rating Curve= 0 ,0
Exp/Cntr=0.3,0.1

Type RM Length L Ch R = 1 ,1998    ,241,241,241
BEGIN DESCRIPTION:
Mapping XS 16393ebc
END DESCRIPTION:
XS GIS Cut Line= 3
      2544801.31     13457277.96      2544527.85     13457338.73
      2544397.67      13457512.3
#Sta/Elev= 30
  4729.6  120.23    4818   118.9  4883.6  110.32  4910.2  107.09  4924.5  105.92
  4940.9  106.91    4968  105.58  4973.1  106.03  4984.9  105.34  4992.2    97.7
  5006.6    97.7  5010.6    97.7  5017.1  104.33  5037.9  105.51  5052.5  106.81
  5073.3   109.5  5087.9  110.51  5094.1  111.59  5102.5  111.86  5108.7  112.93
  5117.1  113.21  5123.3  114.28  5137.9  114.83  5144.1   115.9  5152.5  116.18
  5158.7  117.25  5167.1  117.53  5173.3   118.6  5202.5  119.59  5226.7  119.89
#Mann= 6 ,-1 , 0
  4729.6     .07       0  4883.6    .033       0  4984.9    .033       0
  5006.6    .033       0  5010.6    .033       0  5017.1     .12       0
Bank Sta=4984.9,5017.1
XS Rating Curve= 0 ,0
Exp/Cntr=0.3,0.1

Type RM Length L Ch R = 1 ,1757    ,340,340,340
BEGIN DESCRIPTION:
Mapping XS 14a2a2e0
END DESCRIPTION:
XS GIS Cut Line= 3
       2544727.5     13457065.29      2544384.62      13457152.1
      2544101.96     13457443.68
#Sta/Elev= 30
  4660.6  121.63  4709.2  120.56  4766.4  119.14  4785.2  118.18  4838.1  114.49
  4848.9  112.87  4879.1  110.67  4890.1  108.73  4920.1  105.76  4937.2  103.31
  4941.7   102.9    4952    97.7  4993.3    97.7  5002.1  104.13  5007.2  103.95
  5011.5  104.72  5023.1  105.49  5030.3  105.32  5049.9  106.52  5058.6   106.5
  5065.6  107.27  5072.7  107.09    5101  109.44  5150.4  111.38  5164.6  112.76
  5171.6  112.72    5207  114.71  5249.5  115.54  5355.5  119.61  5420.4  120.82
#Mann= 8 ,-1 , 0
  4660.6     .07       0  4709.2     .12       0  4785.2    .033       0
  4937.2     .07       0  4941.7    .033       0    4952     .03       0
  5002.1     .03       0  5049.9     .12       0
Bank Sta=4941.7,5002.1
XS Rating Curve= 0 ,0
Exp/Cntr=0.3,0.1

Type RM Length L Ch R = 1 ,1417    ,475,475,475
BEGIN DESCRIPTION:
Mapping XS 8f5c2dee
END DESCRIPTION:
XS GIS Cut Line= 3
      2544475.73     13456791.87      2544237.05      13456861.3
      2544016.22     13457180.36
#Sta/Elev= 30
  4737.1  116.81  4789.9  114.82    4835  111.95  4847.5  111.07  4935.7  104.92
  4976.6  100.69  4981.8  100.75  4984.1   99.67    4991   99.67    4996    97.7
  5018.1    97.7  5026.7   99.42  5039.1  101.44  5053.9  103.05  5062.7  103.33
  5068.8  104.47  5083.7  105.03  5089.7  106.17  5098.5  106.45  5104.6  107.59
  5119.5   108.1  5125.5  109.29  5134.3  109.52  5140.4  110.71  5155.3  111.11
  5161.4  112.37  5176.2  113.24  5283.6  115.74  5369.9  117.82  5373.7  118.01
#Mann= 7 ,-1 , 0
  4737.1     .07       0    4835     .12       0  4847.5    .033       0
    4991     .03       0  5026.7     .03       0  5283.6     .07       0
  5369.9     .12       0
Bank Sta=4991,5026.7
XS Rating Curve= 0 ,0
Exp/Cntr=0.3,0.1

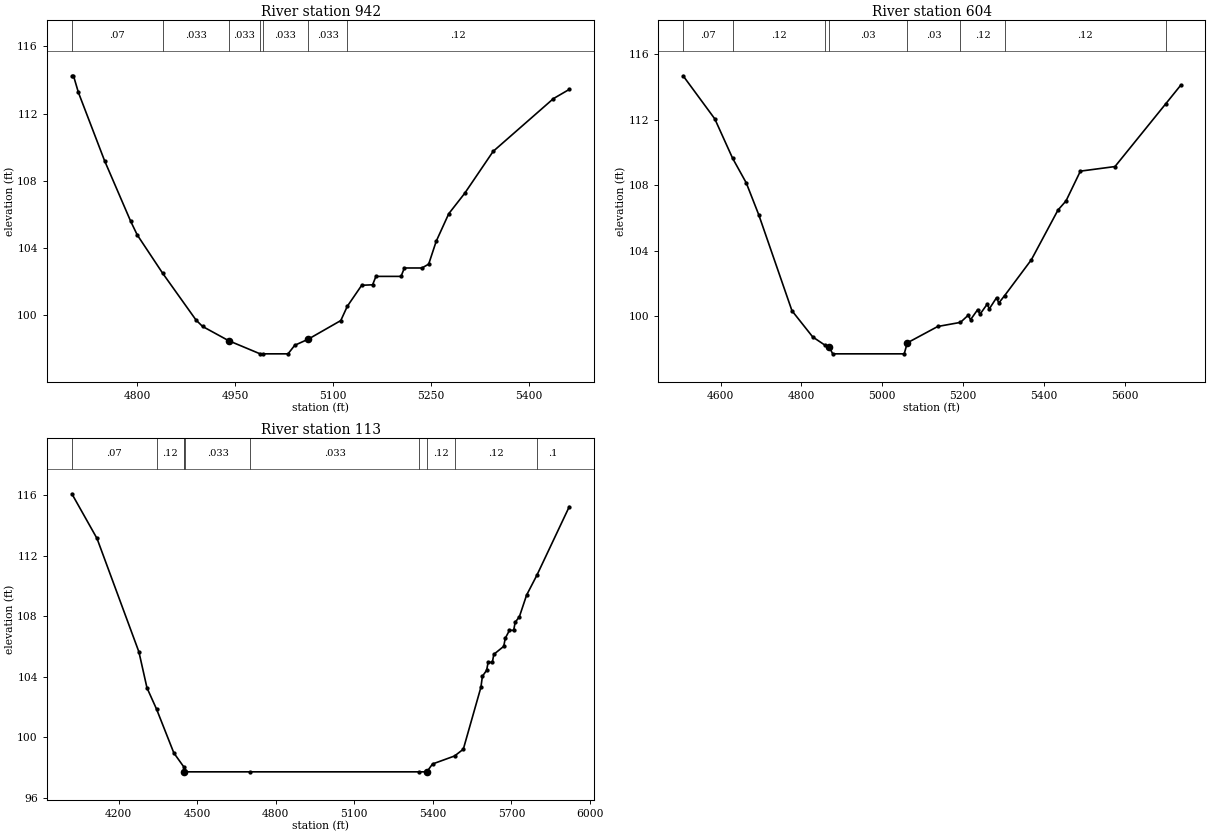
Type RM Length L Ch R = 1 ,942     ,338,338,338
BEGIN DESCRIPTION:
TRIB 2 TO COLETO CREEK RESERVOIR 2.0
END DESCRIPTION:
XS GIS Cut Line= 3
      2544325.01       13456475.        2544025.       13456475.
        2543925.     13456925.01
#Sta/Elev= 30
  4700.3  114.25  4702.8  114.25  4710.3  113.26  4750.3   109.2  4790.3  105.59
  4800.3  104.78    4839  102.51  4890.3   99.71  4900.3   99.33  4940.3   98.48
  4988.3    97.7  4992.3    97.7    5031    97.7  5041.3   98.21  5061.8   98.57
  5111.7   99.68  5121.7  100.53  5143.7  101.78  5160.4  101.81  5165.5  102.31
  5203.9  102.31    5209  102.81  5235.9  102.81  5246.2  103.04  5257.7   104.4
  5276.9  106.04  5301.2  107.25  5344.8  109.75    5437  112.89  5461.3  113.44
#Mann= 7 ,-1 , 0
  4700.3     .07       0    4839    .033       0  4940.3    .033       0
  4988.3    .033       0  4992.3    .033       0  5061.8    .033       0
  5121.7     .12       0
Bank Sta=4940.3,5061.8
XS Rating Curve= 0 ,0
Exp/Cntr=0.3,0.1

Type RM Length L Ch R = 1 ,604     ,491,491,491
BEGIN DESCRIPTION:
Mapping XS 3f1a0e82
END DESCRIPTION:
XS GIS Cut Line= 4
      2544197.14      13456092.2      2543816.98      13456181.9
      2543654.58     13456550.54      2543807.32     13456960.16
#Sta/Elev= 30
  4507.2  114.67  4585.6  112.04  4629.6  109.64  4663.5  108.13  4694.3  106.19
  4776.5  100.33  4827.9   98.73  4858.7   98.22    4869    98.1  4877.3    97.7
  5054.2    97.7  5061.8   98.37  5137.2   99.37  5193.3   99.62  5212.7  100.06
  5218.2   99.78    5236   100.4  5241.5  100.11  5259.4  100.73  5264.8  100.45
  5282.7  101.13  5288.1   100.8  5302.8  101.26  5368.7  103.44  5434.7  106.48
  5454.4  107.03    5490  108.85  5575.6  109.13  5701.5  112.97  5737.8  114.08
#Mann= 8 ,-1 , 0
  4507.2     .07       0  4629.6     .12       0  4858.7     .03       0
    4869     .03       0  5061.8     .03       0  5193.3     .12       0
  5302.8     .12       0  5701.5      .1       0
Bank Sta=4869,5061.8
XS Rating Curve= 0 ,0
Exp/Cntr=0.3,0.1

Type RM Length L Ch R = 1 ,113     ,0,0,0
BEGIN DESCRIPTION:
TRIB 2 TO COLETO CREEK RESERVOIR 1.0
END DESCRIPTION:
XS GIS Cut Line= 4
      2544214.44     13455998.46      2543332.53     13456203.32
      2543308.23     13456338.73      2543720.12     13457089.83
#Sta/Elev= 30
  4021.4  116.11  4117.5  113.15  4277.5  105.64  4308.3  103.26  4344.9  101.85
  4410.9   98.95    4450      98  4450.3    97.7    4454    97.7  4703.4    97.7
  5347.5    97.7  5376.9    97.7  5398.7   98.22    5483   98.75  5516.3    99.2
  5583.5   103.3  5589.2  104.03  5605.3  104.42    5611  104.95  5627.1  104.95
  5632.8  105.48  5670.7  106.01  5676.4  106.54  5692.5  107.07  5708.6  107.07
  5714.3   107.6  5730.4  107.97  5757.9   109.4  5797.6  110.73    5921  115.26
#Mann= 10 ,-1 , 0
  4021.4     .07       0  4344.9     .12       0    4450     .03       0
  4450.3     .03       0    4454    .033       0  4703.4    .033       0
  5347.5    .033       0  5376.9     .12       0    5483     .12       0
  5797.6      .1       0
Bank Sta=4450.3,5376.9
XS Rating Curve= 0 ,0
Exp/Cntr=0.3,0.1

Chan Stop Cuts=-1
Use User Specified Reach Order=0
Composite Channel Slope=5