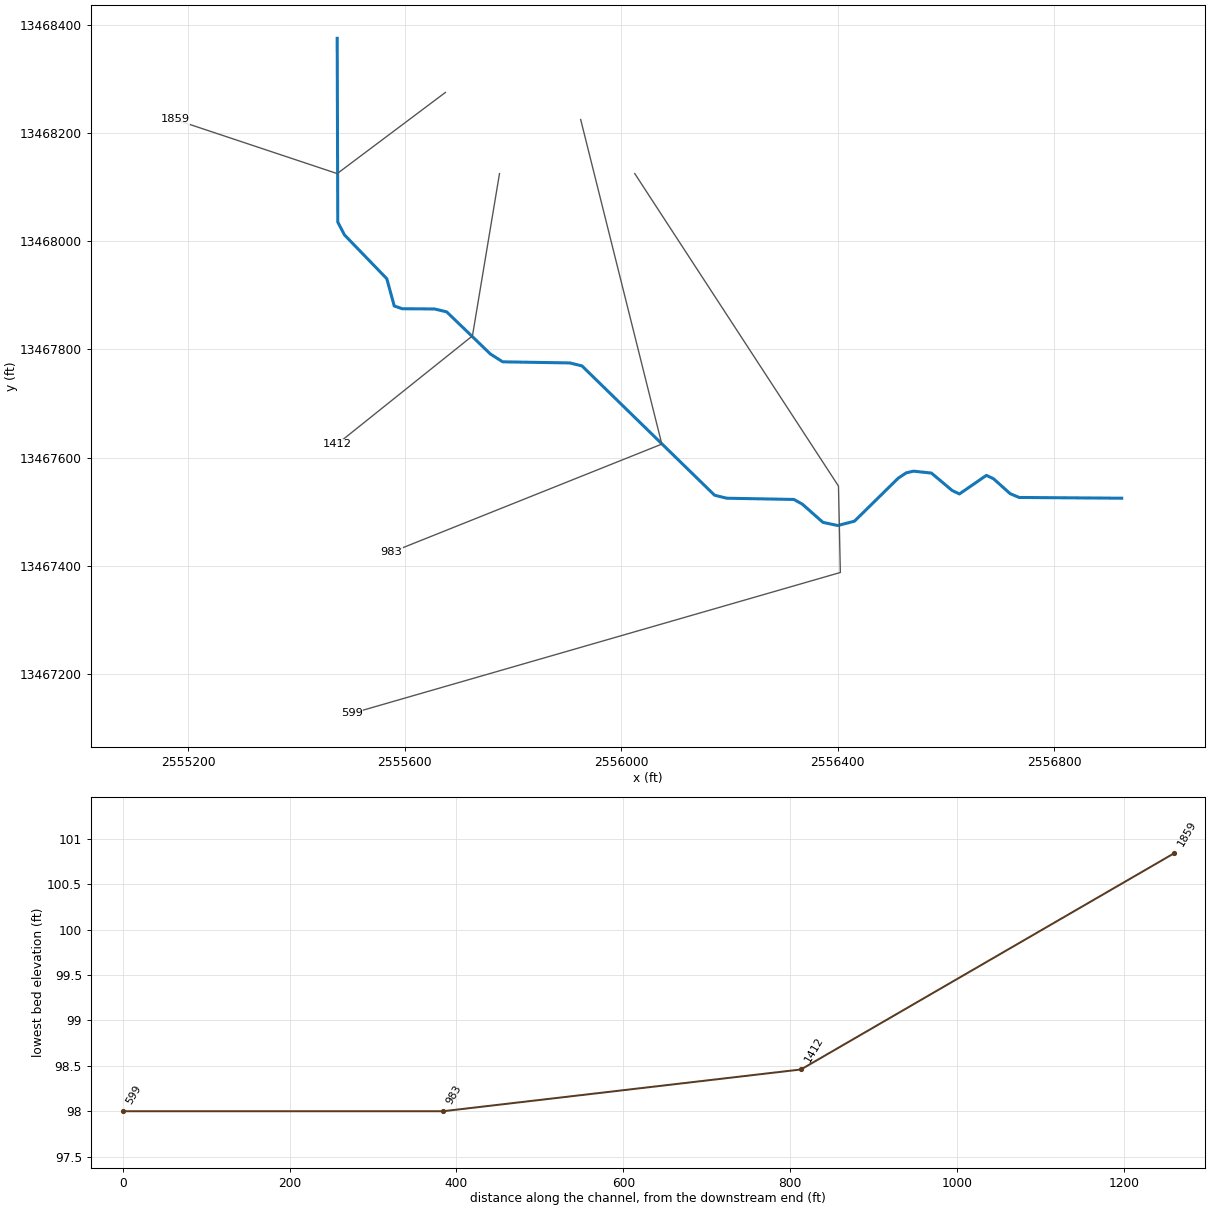
--- TRIB 2 TO COLETO CREEK.prj (project) ---

Proj Title=TRIB 2 TO COLETO CREEK Base Level Engineering
Current Plan=p01
Default Exp/Contr=0.3,0.1
English Units
Geom File=g01
Flow File=f01
Plan File=p01
Y Axis Title=Elevation
X Axis Title(PF)=Main Channel Distance
X Axis Title(XS)=Station
BEGIN DESCRIPTION:
TRIB 2 TO COLETO CREEK
END DESCRIPTION:
DSS Export Rating Curves= 0
DSS Export Rating Curve Sorted= 0
DSS Export Volume Flow Curves= 0
DXF OffsetX= 0
DXF OffsetY= 0
DXF ScaleX= 1
DXF ScaleY= 10

--- TRIB 2 TO COLETO CREEK.p01 (plan) ---

Plan Title=Multiple Run
Short Identifier=Multiple
Geom File=g01
Flow File=f01
Subcritical Flow
K Sum by GR= 0
Std Step Tol= 0.01
Critical Tol= 0.01
Num of Std Step Trials= 20
Max Error Tol= 0.3
Flow Tol Ratio= 0.001
Split Flow NTrial= 30
Split Flow Tol= 0.02
Split Flow Ratio= 0.02
Log Output Level= 0
Friction Slope Method= 1
Unsteady Friction Slope Method= 2
Unsteady Bridges Friction Slope Method= 1
Parabolic Critical Depth
Global Vel Dist=  1 , 1 , 1
Global Log Level= 0
CheckData=True
Encroach Param= -1, 0, 0, 0
BEGIN DESCRIPTION:
Multiple Run
END DESCRIPTION:

--- TRIB 2 TO COLETO CREEK.f01 (steady flow) ---

Flow Title=Multiple
Program Version=4.10
Number of Profiles= 7
Profile Names=10-year,25-year,50-year,1pct_min,100-year,1pct_plu,500-year
River Rch & RM=TRIB 2 TO COLETO,Reach-1         ,1859
     106     147     179     106     212     422     290
Boundary for River Rch & Prof#=TRIB 2 TO COLETO,Reach-1         , 1
Up Type= 0
Dn Type= 3
Dn Slope=0.0005
Boundary for River Rch & Prof#=TRIB 2 TO COLETO,Reach-1         , 2
Up Type= 0
Dn Type= 3
Dn Slope=0.0005
Boundary for River Rch & Prof#=TRIB 2 TO COLETO,Reach-1         , 3
Up Type= 0
Dn Type= 3
Dn Slope=0.0005
Boundary for River Rch & Prof#=TRIB 2 TO COLETO,Reach-1         , 4
Up Type= 0
Dn Type= 3
Dn Slope=0.0005
Boundary for River Rch & Prof#=TRIB 2 TO COLETO,Reach-1         , 5
Up Type= 0
Dn Type= 3
Dn Slope=0.0005
Boundary for River Rch & Prof#=TRIB 2 TO COLETO,Reach-1         , 6
Up Type= 0
Dn Type= 3
Dn Slope=0.0005
Boundary for River Rch & Prof#=TRIB 2 TO COLETO,Reach-1         , 7
Up Type= 0
Dn Type= 3
Dn Slope=0.0005
DSS Import GetInterval= 0
DSS Import GetPeak= 0
DSS Import FillOption= 0

--- TRIB 2 TO COLETO CREEK.g01 (geometry) ---

Geom Title=Existing Conditions
Program Version=4.10

River Reach=TRIB 2 TO COLETO,Reach-1
Reach XY= 30
        2555475.       13468375.      2555476.05     13468035.44
       2555488.4     13468011.69      2555566.68      13467930.7
      2555580.47     13467880.26      2555595.26     13467875.22
      2555654.79      13467874.8      2555677.36     13467869.44
      2555758.25     13467791.47      2555780.86     13467777.08
      2555905.01     13467775.02      2555927.45     13467769.53
      2556172.55     13467530.47      2556194.99     13467524.98
      2556319.07      13467522.7      2556334.67     13467514.08
      2556372.83     13467480.35      2556400.04     13467474.51
      2556431.05      13467482.5       2556511.8     13467561.83
      2556526.65     13467571.83      2556540.36     13467574.98
      2556573.35     13467571.44      2556611.81     13467539.14
      2556625.08     13467532.83       2556674.9     13467567.21
      2556688.16     13467560.93      2556718.81     13467533.43
      2556735.43     13467526.37        2556925.       13467525.

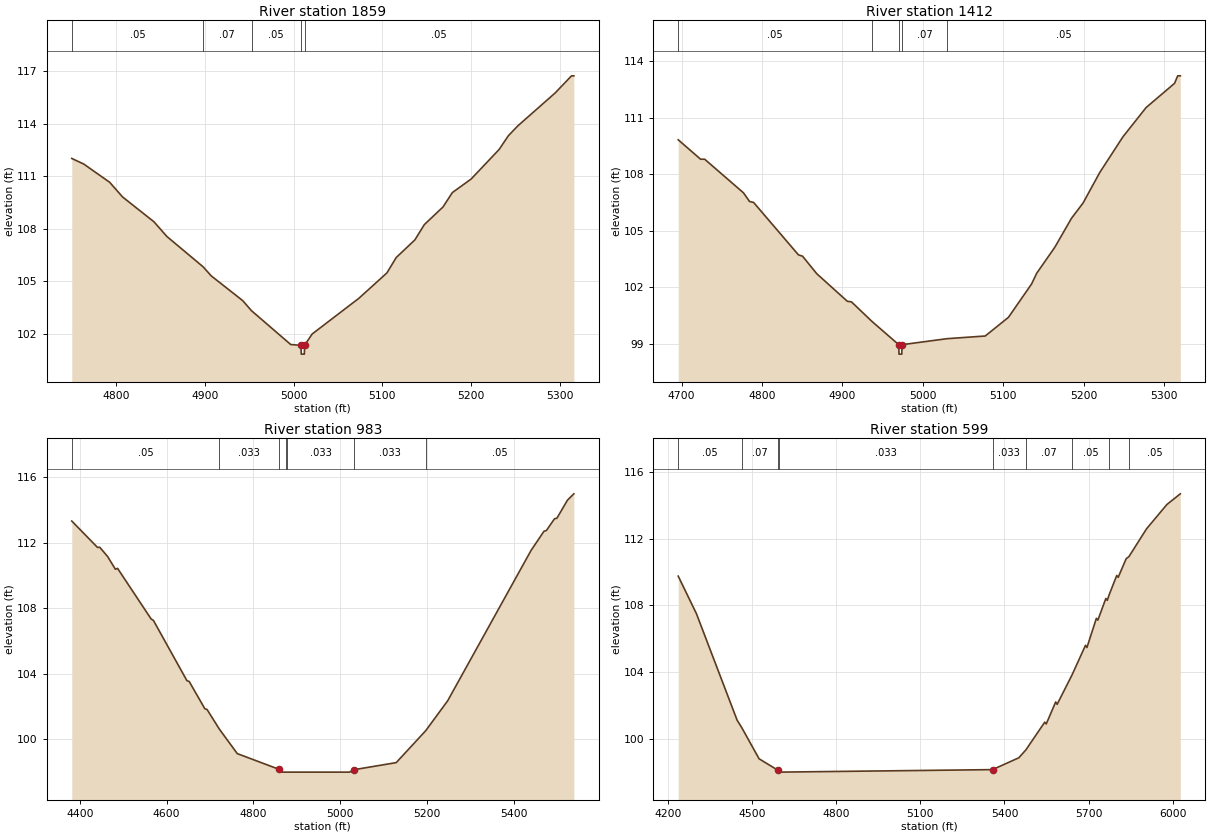
Type RM Length L Ch R = 1 ,1859    ,447,447,447
BEGIN DESCRIPTION:
TRIB 2 TO COLETO CREEK 4.0
END DESCRIPTION:
XS GIS Cut Line= 3
        2555675.       13468275.        2555475.       13468125.
      2555175.02     13468224.99
#Sta/Elev= 30
  4749.9  112.02  4763.4   111.7  4792.6  110.66  4807.2  109.82  4842.6   108.4
  4857.2  107.56    4898  105.83  4907.2  105.31  4942.6   103.9  4952.6  103.32
  4996.8  101.39  5008.4  101.34  5008.7  100.84  5012.2  100.84  5012.4  101.34
    5021  101.99  5073.7  104.03  5105.3  105.48  5115.8  106.36  5136.9  107.37
  5147.5  108.24  5168.6  109.25  5179.1  110.07  5200.2  110.84  5231.8  112.53
  5242.3  113.32  5252.9  113.88    5295  115.76  5313.5  116.74  5316.1  116.74
#Mann= 5 ,-1 , 0
  4749.9     .05       0    4898     .07       0  4952.6     .05       0
  5008.4     .05       0  5012.4     .05       0
Bank Sta=5008.4,5012.4
XS Rating Curve= 0 ,0
Exp/Cntr=0.3,0.1

Type RM Length L Ch R = 1 ,1412    ,429,429,429
BEGIN DESCRIPTION:
TRIB 2 TO COLETO CREEK 3.0
END DESCRIPTION:
XS GIS Cut Line= 3
      2555774.99     13468124.96        2555725.       13467825.
      2555474.97     13467624.97
#Sta/Elev= 30
  4695.9  109.82  4723.7  108.79  4728.8  108.79    4777  107.01  4784.6  106.55
  4789.6   106.5  4845.4  103.72  4850.5  103.65  4868.2  102.72  4906.2  101.26
  4911.3  101.23  4936.6   100.2  4970.1   98.96  4970.4   98.46  4973.9   98.46
  4974.1   98.96  5030.4   99.28  5077.6   99.42  5106.5  100.41  5135.3  102.18
  5141.7  102.75  5164.1  104.12  5184.9  105.66  5199.3  106.47  5220.1  108.09
  5248.9  109.98  5277.7  111.53    5313  112.81    5317  113.21  5320.2  113.21
#Mann= 5 ,-1 , 0
  4695.9     .05       0  4936.6     .07       0  4970.1     .05       0
  4974.1     .07       0  5030.4     .05       0
Bank Sta=4970.1,4974.1
XS Rating Curve= 0 ,0
Exp/Cntr=0.3,0.1

Type RM Length L Ch R = 1 ,983     ,384,384,384
BEGIN DESCRIPTION:
TRIB 2 TO COLETO CREEK 2.0
END DESCRIPTION:
XS GIS Cut Line= 3
        2555925.     13468224.99        2556075.       13467625.
      2555574.97     13467424.99
#Sta/Elev= 30
  4381.5  113.32  4440.8  111.71  4445.9  111.72    4464  111.16    4482  110.38
  4487.1  110.43  4564.5  107.34  4569.6  107.26  4646.9  103.58  4652.1  103.53
  4688.1  101.87  4693.3  101.82  4721.5  100.63  4762.9   99.13  4858.2   98.18
    4866      98  4874.3      98  4878.3      98  5021.5      98  5032.3   98.15
  5129.2   98.58  5197.2  100.53  5247.7  102.35  5440.2  111.54  5469.8   112.7
  5475.2  112.74    5494  113.46  5499.4  113.49  5523.7  114.59  5538.5  114.98
#Mann= 7 ,-1 , 0
  4381.5     .05       0  4721.5    .033       0  4858.2    .033       0
  4874.3    .033       0  4878.3    .033       0  5032.3    .033       0
  5197.2     .05       0
Bank Sta=4858.2,5032.3
XS Rating Curve= 0 ,0
Exp/Cntr=0.3,0.1

Type RM Length L Ch R = 1 ,599     ,0,0,0
BEGIN DESCRIPTION:
TRIB 2 TO COLETO CREEK 1.0
END DESCRIPTION:
XS GIS Cut Line= 4
      2556025.02     13468124.96      2556401.53     13467547.44
        2556405.     13467387.71      2555502.19     13467127.29
#Sta/Elev= 30
  4237.7  109.76  4302.5  107.51  4447.4  101.12  4463.7  100.68  4525.8    98.8
  4592.3   98.12  4596.2    98.1  4596.5      98  5357.5   98.15  5451.1   98.86
  5476.1   99.33  5543.6     101  5548.8  100.89  5582.5  102.21  5587.7  102.07
  5640.4  103.82  5688.7  105.61  5693.9  105.48  5727.5  107.23  5732.7  107.12
  5761.2  108.42  5766.4  108.31  5773.2  108.65    5800   109.8  5805.2  109.69
  5833.7  110.81  5843.4  110.93  5906.2   112.6  5978.7  114.06  6026.5   114.7
#Mann= 9 ,-1 , 0
  4237.7     .05       0  4463.7     .07       0  4592.3     .05       0
  4596.2    .033       0  5357.5    .033       0  5476.1     .07       0
  5640.4     .05       0  5773.2    .035       0  5843.4     .05       0
Bank Sta=4592.3,5357.5
XS Rating Curve= 0 ,0
Exp/Cntr=0.3,0.1

Chan Stop Cuts=-1
Use User Specified Reach Order=0
Composite Channel Slope=5