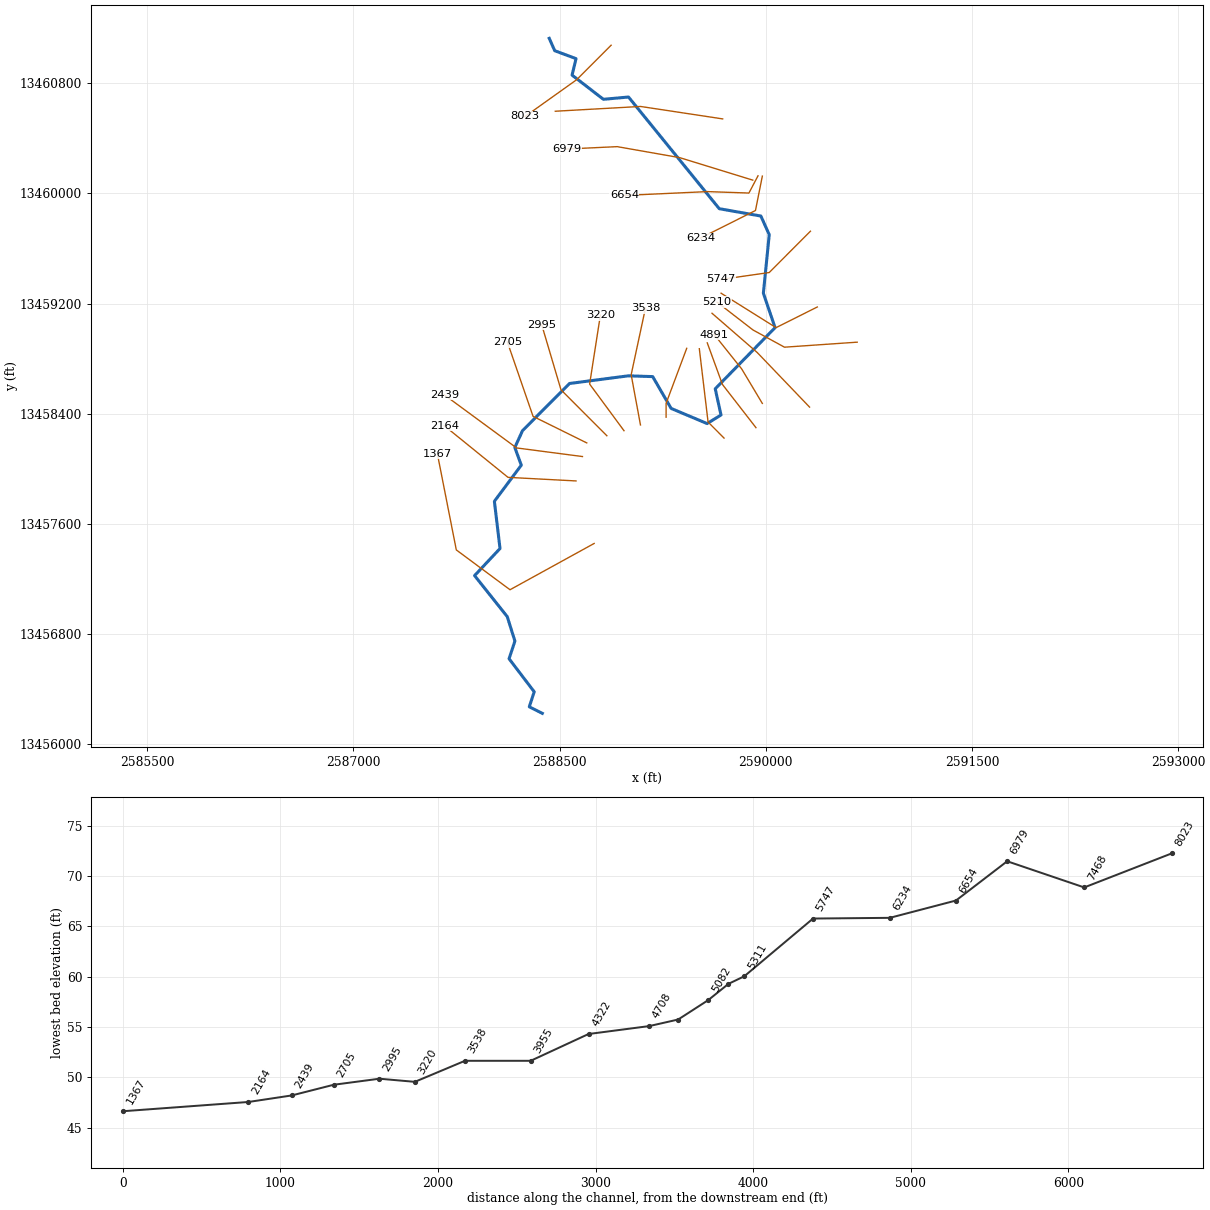
--- TRIB 2 TO COURT BRANCH.prj (project) ---

Proj Title=TRIB 2 TO COURT BRANCH Base Level Engineering
Current Plan=p01
Default Exp/Contr=0.3,0.1
English Units
Geom File=g01
Flow File=f01
Plan File=p01
Y Axis Title=Elevation
X Axis Title(PF)=Main Channel Distance
X Axis Title(XS)=Station
BEGIN DESCRIPTION:
TRIB 2 TO COURT BRANCH
END DESCRIPTION:
DSS Export Rating Curves= 0
DSS Export Rating Curve Sorted= 0
DSS Export Volume Flow Curves= 0
DXF OffsetX= 0
DXF OffsetY= 0
DXF ScaleX= 1
DXF ScaleY= 10

--- TRIB 2 TO COURT BRANCH.p01 (plan) ---

Plan Title=Multiple Run
Short Identifier=Multiple
Geom File=g01
Flow File=f01
Subcritical Flow
K Sum by GR= 0
Std Step Tol= 0.01
Critical Tol= 0.01
Num of Std Step Trials= 20
Max Error Tol= 0.3
Flow Tol Ratio= 0.001
Split Flow NTrial= 30
Split Flow Tol= 0.02
Split Flow Ratio= 0.02
Log Output Level= 0
Friction Slope Method= 1
Unsteady Friction Slope Method= 2
Unsteady Bridges Friction Slope Method= 1
Parabolic Critical Depth
Global Vel Dist=  1 , 1 , 1
Global Log Level= 0
CheckData=True
Encroach Param= -1, 0, 0, 0
BEGIN DESCRIPTION:
Multiple Run
END DESCRIPTION:

--- TRIB 2 TO COURT BRANCH.f01 (steady flow) ---

Flow Title=Multiple
Number of Profiles=7
Profile Names=10-year,25-year,50-year,1pct_min,100-year,1pct_plu,500-year
River Rch & RM= TRIB 2 TO COURT ,Reach-1,8023
     562     865    1126     709    1414    2822    2202
River Rch & RM= TRIB 2 TO COURT ,Reach-1,7468
     833    1316    1743    1115    2225    4439    3582
Boundary for River Rch & Prof#=TRIB 2 TO COURT ,Reach-1,1
Up Type=0
Dn Type=3
Dn Slope=0.005
Boundary for River Rch & Prof#=TRIB 2 TO COURT ,Reach-1,2
Up Type=0
Dn Type=3
Dn Slope=0.005
Boundary for River Rch & Prof#=TRIB 2 TO COURT ,Reach-1,3
Up Type=0
Dn Type=3
Dn Slope=0.005
Boundary for River Rch & Prof#=TRIB 2 TO COURT ,Reach-1,4
Up Type=0
Dn Type=3
Dn Slope=0.005
Boundary for River Rch & Prof#=TRIB 2 TO COURT ,Reach-1,5
Up Type=0
Dn Type=3
Dn Slope=0.005
Boundary for River Rch & Prof#=TRIB 2 TO COURT ,Reach-1,6
Up Type=0
Dn Type=3
Dn Slope=0.005
Boundary for River Rch & Prof#=TRIB 2 TO COURT ,Reach-1,7
Up Type=0
Dn Type=3
Dn Slope=0.005

--- TRIB 2 TO COURT BRANCH.g01 (geometry) ---

Geom Title=Existing Conditions
Program Version=4.10

River Reach=TRIB 2 TO COURT ,Reach-1
Reach XY= 30
        2588425.       13461125.      2588464.91     13461035.27
        2588620.     13460977.57      2588591.15     13460857.92
      2588818.94     13460682.48      2589001.82     13460698.96
      2589661.66     13459888.36      2589964.39     13459835.06
      2590025.21     13459700.09      2589982.56       13459275.
      2590067.68      13459024.9      2589632.47     13458581.07
      2589674.48     13458390.88      2589573.45     13458328.66
      2589311.73     13458438.63      2589177.48     13458669.54
      2588999.92      13458675.2      2588572.53     13458619.54
      2588230.83      13458277.3      2588174.71     13458154.82
      2588221.87     13458026.63      2588026.08     13457764.46
      2588067.01     13457421.66      2587882.08       13457225.
      2588119.48     13456927.44      2588175.39       13456750.
      2588132.81     13456621.59      2588315.83     13456381.72
      2588279.88     13456272.49        2588375.       13456225.

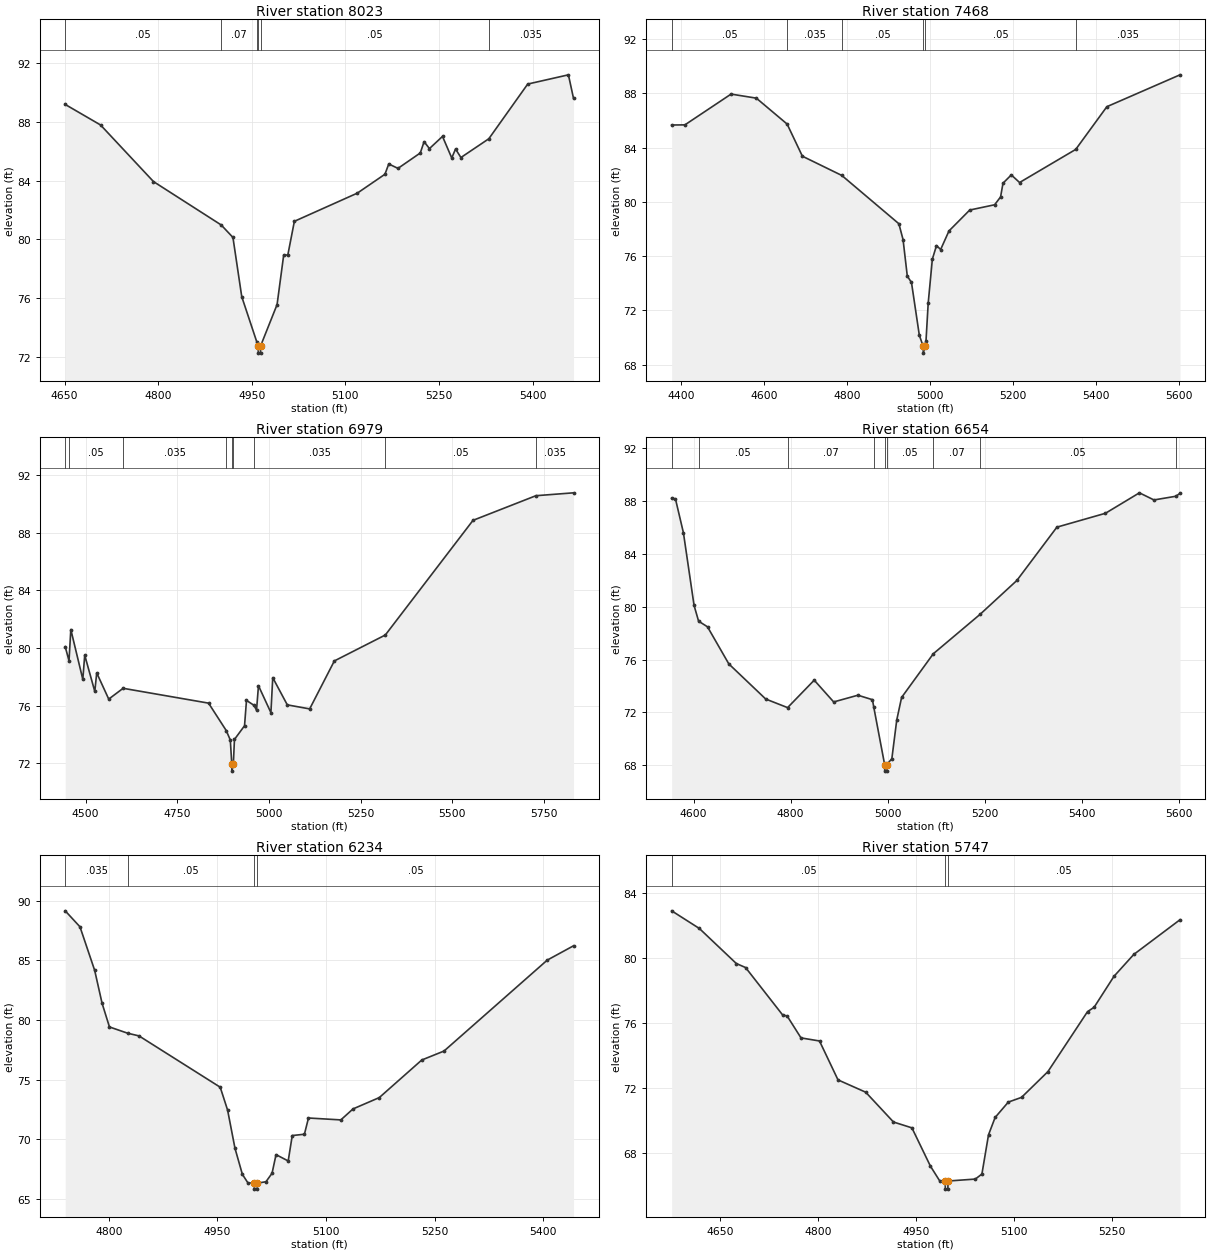
Type RM Length L Ch R = 1 ,8023    ,555,555,555
BEGIN DESCRIPTION:
TRIB 2 TO COURT BRANCH 15.0
END DESCRIPTION:
XS GIS Cut Line= 3
        2588875.       13461075.        2588625.       13460825.
      2588249.57      13460557.9
#Sta/Elev= 30
  4651.1   89.19  4707.7   87.79  4792.5   83.93    4901   80.97  4919.8   80.12
  4933.9   76.08  4957.8   73.02  4960.2   72.73  4960.5   72.23    4964   72.23
  4964.2   72.73  4990.5   75.54  5001.1   78.92  5007.7   78.92  5018.2   81.22
    5119   83.14  5163.3   84.43  5169.4   85.13  5184.2   84.83  5219.9   85.88
    5226   86.65  5234.6   86.18  5255.5   87.01  5270.3   85.54  5276.4   86.15
    5285   85.57  5329.7   86.85    5392   90.58  5457.2   91.21  5465.4    89.6
#Mann= 6 ,-1 , 0
  4651.1     .05       0    4901     .07       0  4957.8     .05       0
  4960.2     .05       0  4964.2     .05       0  5329.7    .035       0
Bank Sta=4960.2,4964.2
XS Rating Curve= 0 ,0
Exp/Cntr=0.3,0.1

Type RM Length L Ch R = 1 ,7468    ,489,489,489
BEGIN DESCRIPTION:
Mapping XS 0e7449e3
END DESCRIPTION:
XS GIS Cut Line= 3
      2589686.58     13460540.22       2589089.4     13460630.49
      2588468.93     13460595.83
#Sta/Elev= 30
  4377.2   85.67  4409.1   85.68  4520.4   87.95  4581.3   87.65  4655.5   85.74
  4692.3   83.37  4787.4   81.95  4924.9   78.39    4935   77.22  4945.2   74.53
  4955.3   74.06  4974.2   70.17  4983.5   69.35  4983.8   68.85  4987.7   69.35
  4990.3   69.75  4995.6   72.54  5005.6   75.78  5015.6   76.78  5025.6   76.49
  5045.7   77.86  5095.7    79.4  5155.8   79.79  5170.1   80.37  5175.9   81.38
  5195.9   81.99  5215.9   81.43  5351.2   83.87  5426.3   87.02  5602.6   89.37
#Mann= 6 ,-1 , 0
  4377.2     .05       0  4655.5    .035       0  4787.4     .05       0
  4983.5     .05       0  4987.7     .05       0  5351.2    .035       0
Bank Sta=4983.5,4987.7
XS Rating Curve= 0 ,0
Exp/Cntr=0.3,0.1

Type RM Length L Ch R = 1 ,6979    ,325,325,325
BEGIN DESCRIPTION:
Mapping XS 2fefcfb9
END DESCRIPTION:
XS GIS Cut Line= 4
      2589905.39     13460095.76      2589374.12     13460258.97
      2588919.26     13460338.83      2588551.16     13460321.46
#Sta/Elev= 30
  4444.3   80.09  4454.7   79.11  4459.6   81.28  4492.3   77.82  4497.5    79.5
    4525   76.98  4530.2   78.27    4563   76.45  4602.2    77.2  4835.2   76.17
  4883.3   74.27  4894.5   73.61  4898.5   71.95  4898.8   71.45  4902.8   71.95
  4905.8   73.65  4933.3    74.6  4938.6   76.36    4959   76.02    4966   75.68
  4971.3   77.38  5005.2   75.51  5010.2   77.94  5049.9   76.05  5110.9   75.77
  5178.2    79.1  5317.2    80.9  5556.3   88.86  5727.8   90.57  5830.4   90.77
#Mann= 9 ,-1 , 0
  4444.3    .035       0  4454.7     .05       0  4602.2    .035       0
  4883.3     .07       0  4898.5    .035       0  4902.8     .07       0
    4959    .035       0  5317.2     .05       0  5727.8    .035       0
Bank Sta=4898.5,4902.8
XS Rating Curve= 0 ,0
Exp/Cntr=0.3,0.1

Type RM Length L Ch R = 1 ,6654    ,420,420,420
BEGIN DESCRIPTION:
Mapping XS 32d754ef
END DESCRIPTION:
XS GIS Cut Line= 4
      2589943.57     13460127.04      2589877.59     13460002.02
      2589575.51     13460012.44      2588971.37     13459984.66
#Sta/Elev= 30
  4554.6   88.23  4562.4   88.17  4578.8   85.61  4600.8    80.1  4610.1   78.91
  4628.5   78.48  4672.5   75.67  4748.6   73.01  4793.7   72.36  4848.6   74.44
  4888.7   72.79  4938.7    73.3  4968.7   72.96  4971.4    72.4  4993.8   68.05
  4994.1   67.55  4997.9   67.55  4998.2   68.05  5008.7   68.49  5018.8   71.42
  5028.8   73.13  5094.2   76.44  5190.5   79.42  5266.5   81.99  5349.1   86.03
  5449.2   87.08  5519.3   88.63  5549.3   88.09  5594.4   88.37    5603   88.59
#Mann= 9 ,-1 , 0
  4554.6    .035       0  4610.1     .05       0  4793.7     .07       0
  4971.4     .05       0  4993.8     .05       0  4998.2     .05       0
  5094.2     .07       0  5190.5     .05       0  5594.4    .035       0
Bank Sta=4993.8,4998.2
XS Rating Curve= 0 ,0
Exp/Cntr=0.3,0.1

Type RM Length L Ch R = 1 ,6234    ,487,487,487
BEGIN DESCRIPTION:
TRIB 2 TO COURT BRANCH 11.0
END DESCRIPTION:
XS GIS Cut Line= 3
      2589974.99     13460124.96        2589925.       13459875.
      2589525.02     13459675.01
#Sta/Elev= 30
  4739.9   89.15  4760.3   87.81  4780.6   84.16  4790.8   81.41    4801   79.42
  4826.4   78.89  4841.8   78.67    4954   74.37  4964.2   72.45  4974.4   69.25
  4984.6   67.07  4992.3   66.35    5001   66.33  5001.3   65.83  5005.1   65.83
  5005.4   66.33  5017.2   66.45  5025.6   67.16  5031.1   68.72  5047.9   68.19
  5053.5   70.32  5070.3   70.43  5075.9   71.79  5120.6   71.63  5137.4   72.55
  5173.7    73.5  5232.4   76.65  5263.1    77.4  5405.7   85.02    5442   86.22
#Mann= 4 ,-1 , 0
  4739.9    .035       0  4826.4     .05       0    5001     .05       0
  5005.4     .05       0
Bank Sta=5001,5005.4
XS Rating Curve= 0 ,0
Exp/Cntr=0.3,0.1

Type RM Length L Ch R = 1 ,5747    ,436,436,436
BEGIN DESCRIPTION:
TRIB 2 TO COURT BRANCH 10.0
END DESCRIPTION:
XS GIS Cut Line= 3
      2590324.96     13459724.96        2590025.       13459425.
      2589674.97       13459375.
#Sta/Elev= 30
  4575.9   82.93  4618.3   81.84  4674.8   79.68    4689   79.43  4745.6   76.51
  4752.6   76.44  4773.8   75.09  4802.1    74.9  4830.4    72.5  4872.8   71.74
  4915.3    69.9  4943.5   69.54  4971.8   67.18    4986   66.27  4994.4   66.26
  4994.7   65.76  4998.5   65.76  4998.8   66.26  5040.5   66.38  5050.6   66.69
  5060.7   69.11  5070.8   70.18    5091   71.13  5111.2   71.42  5151.6   73.01
  5212.2   76.71  5222.3   76.98  5252.7   78.89    5283   80.24  5353.7   82.38
#Mann= 3 ,-1 , 0
  4575.9     .05       0  4994.4     .05       0  4998.8     .05       0
Bank Sta=4994.4,4998.8
XS Rating Curve= 0 ,0
Exp/Cntr=0.3,0.1

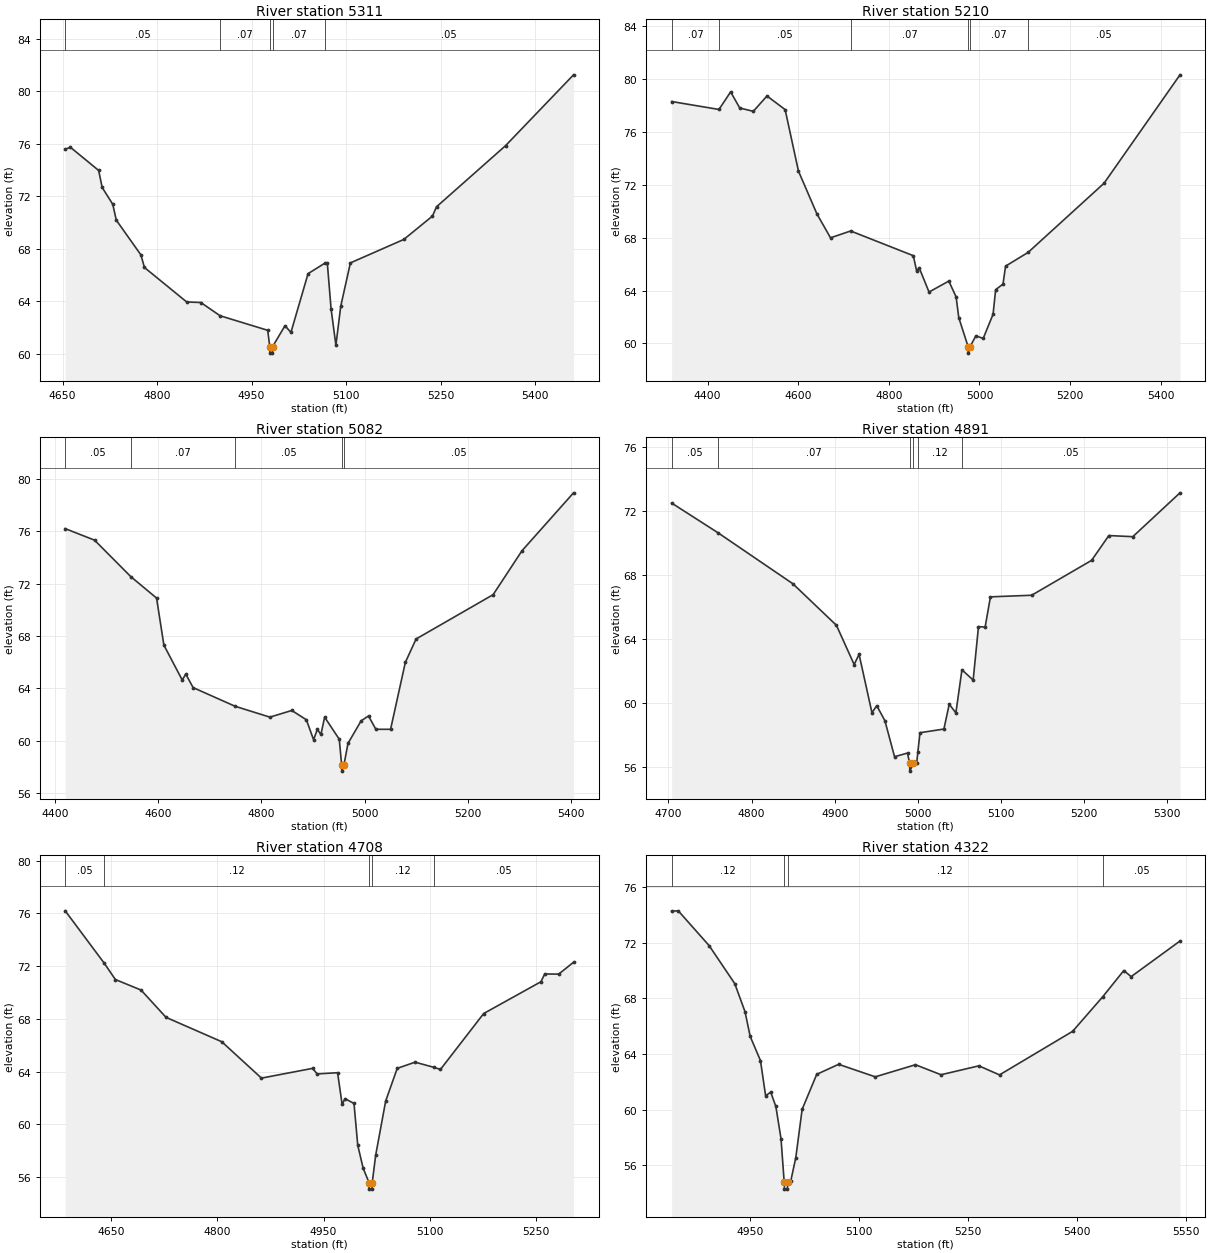
Type RM Length L Ch R = 1 ,5311    ,101,101,101
BEGIN DESCRIPTION:
TRIB 2 TO COURT BRANCH 9.0
END DESCRIPTION:
XS GIS Cut Line= 3
      2590375.03     13459175.02        2590075.       13459025.
      2589675.04     13459274.98
#Sta/Elev= 30
  4654.1   75.58  4662.5   75.72  4707.2   73.96  4712.8   72.66  4729.6   71.38
  4735.2   70.17  4774.3   67.52  4779.9   66.56    4847   63.93  4869.4   63.89
    4900   62.88  4975.6   61.77  4978.9   60.53  4979.2   60.03  4983.1   60.03
  4983.4   60.53  5003.1   62.12  5012.5   61.61  5039.7   66.09  5066.4   66.89
  5070.3   66.88  5076.2   63.42  5083.9   60.63  5091.6   63.61  5106.9   66.91
  5191.8    68.7  5237.2   70.48  5243.7   71.19  5353.3   75.85  5461.2   81.25
#Mann= 5 ,-1 , 0
  4654.1     .05       0    4900     .07       0  4978.9     .07       0
  4983.4     .07       0  5066.4     .05       0
Bank Sta=4978.9,4983.4
XS Rating Curve= 0 ,0
Exp/Cntr=0.3,0.1

Type RM Length L Ch R = 1 ,5210    ,128,128,128
BEGIN DESCRIPTION:
Mapping XS f8983c5f
END DESCRIPTION:
XS GIS Cut Line= 4
      2590664.91     13458919.56      2590136.27      13458883.1
       2589907.1      13459008.1      2589644.85     13459210.63
#Sta/Elev= 30
  4320.5    78.3  4424.9    77.7  4450.7   79.03  4470.8   77.81  4500.8   77.56
  4530.9   78.72    4571   77.69  4600.4   73.04  4641.2    69.8  4671.2   67.99
  4715.6   68.51    4854   66.64  4861.2    65.5  4866.9   65.73  4888.7   63.89
  4932.4   64.72  4948.5   63.52  4954.4   61.95  4974.9   59.77  4975.2   59.27
  4979.4   59.77  4992.2   60.58  5008.3   60.38  5030.1   62.21  5035.8   64.07
    5052   64.49  5057.7   65.85  5107.5   66.89  5275.1   72.12  5442.8   80.32
#Mann= 6 ,-1 , 0
  4320.5     .07       0  4424.9     .05       0  4715.6     .07       0
  4974.9     .07       0  4979.4     .07       0  5107.5     .05       0
Bank Sta=4974.9,4979.4
XS Rating Curve= 0 ,0
Exp/Cntr=0.3,0.1

Type RM Length L Ch R = 1 ,5082    ,191,191,191
BEGIN DESCRIPTION:
Mapping XS 5b40882b
END DESCRIPTION:
XS GIS Cut Line= 3
      2590318.53     13458448.23      2589938.35     13458844.04
       2589609.1     13459129.22
#Sta/Elev= 30
    4420   76.21  4476.8   75.33    4547   72.54  4596.9    70.9  4611.1    67.3
  4646.6   64.63  4653.5   65.08  4667.7   64.05  4749.1   62.62  4816.4   61.79
  4858.8    62.3    4887   61.59    4901   60.06  4908.2   60.85  4915.2   60.47
  4922.4   61.79  4950.7    60.1  4955.3   58.16  4955.6   57.66  4959.9   58.16
  4967.6   59.78  4993.1   61.51  5007.4   61.88  5021.6   60.86  5050.1   60.86
  5078.7   65.98  5099.5   67.77  5248.7   71.16  5304.6   74.52  5404.4   78.95
#Mann= 5 ,-1 , 0
    4420     .05       0    4547     .07       0  4749.1     .05       0
  4955.3     .05       0  4959.9     .05       0
Bank Sta=4955.3,4959.9
XS Rating Curve= 0 ,0
Exp/Cntr=0.3,0.1

Type RM Length L Ch R = 1 ,4891    ,183,183,183
BEGIN DESCRIPTION:
TRIB 2 TO COURT BRANCH 8.0
END DESCRIPTION:
XS GIS Cut Line= 3
        2589975.       13458475.        2589825.       13458725.
        2589625.       13458975.
#Sta/Elev= 30
  4703.9   72.48  4759.2   70.64  4849.7   67.44  4902.2   64.84  4923.5   62.39
  4929.4   63.03  4944.9   59.38  4950.7   59.82  4960.5   58.88  4972.1   56.63
  4987.7   56.86  4990.2   56.23  4990.5   55.73  4994.8   56.23  4998.7   56.23
  5000.1    56.9  5002.7   58.13  5031.5   58.36  5037.9   59.91  5045.9   59.37
  5053.2   62.06  5066.7   61.42  5073.1   64.76  5081.1   64.73  5087.5   66.62
  5137.1   66.72  5209.2    68.9    5230   70.45  5258.8   70.38  5315.6   73.12
#Mann= 6 ,-1 , 0
  4703.9     .05       0  4759.2     .07       0  4990.2     .07       0
  4994.8     .07       0  5000.1     .12       0  5053.2     .05       0
Bank Sta=4990.2,4994.8
XS Rating Curve= 0 ,0
Exp/Cntr=0.3,0.1

Type RM Length L Ch R = 1 ,4708    ,386,386,386
BEGIN DESCRIPTION:
Mapping XS c7122aa8
END DESCRIPTION:
XS GIS Cut Line= 3
      2589928.68     13458299.01      2589684.88     13458612.47
      2589574.58     13458914.34
#Sta/Elev= 30
  4584.9   76.19  4640.3    72.2  4655.8   70.98  4692.1   70.18  4727.4   68.11
  4806.2   66.26  4862.3    63.5  4934.5   64.24    4941   63.82  4969.9   63.91
  4976.3   61.51  4980.4   61.94  4993.1   61.58  4998.4   58.41    5006   56.67
  5014.3   55.58  5014.6   55.08  5018.6   55.08  5018.9   55.58  5023.7   57.64
  5037.9   61.77  5054.2   64.24  5079.4   64.71  5106.6   64.31  5115.3   64.16
  5176.4    68.4  5257.3   70.81  5262.7    71.4  5282.5   71.39  5303.4   72.29
#Mann= 5 ,-1 , 0
  4584.9     .05       0  4640.3     .12       0  5014.3     .07       0
  5018.9     .12       0  5106.6     .05       0
Bank Sta=5014.3,5018.9
XS Rating Curve= 0 ,0
Exp/Cntr=0.3,0.1

Type RM Length L Ch R = 1 ,4322    ,367,367,367
BEGIN DESCRIPTION:
Mapping XS efd525e5
END DESCRIPTION:
XS GIS Cut Line= 3
      2589696.46     13458223.53      2589580.38     13458339.61
      2589516.74     13458871.85
#Sta/Elev= 30
  4841.6   74.27  4850.7   74.29  4893.2   71.79  4928.5   69.06  4942.7   67.03
  4949.7   65.27  4963.9   63.53    4971      61    4978   61.26  4985.1   60.23
  4992.2   57.92  4996.6   54.79    4997   54.29    5001   54.29  5001.3   54.79
  5005.8   54.91  5012.6   56.56  5021.3   60.02  5041.4   62.54  5071.6   63.26
    5122   62.36  5177.4   63.23  5212.6   62.51  5264.8   63.15  5293.2    62.5
  5393.9   65.63  5435.3   68.11  5464.4      70  5474.5   69.56  5541.8   72.12
#Mann= 4 ,-1 , 0
  4841.6     .12       0  4996.6     .07       0  5001.3     .12       0
  5435.3     .05       0
Bank Sta=4996.6,5001.3
XS Rating Curve= 0 ,0
Exp/Cntr=0.3,0.1

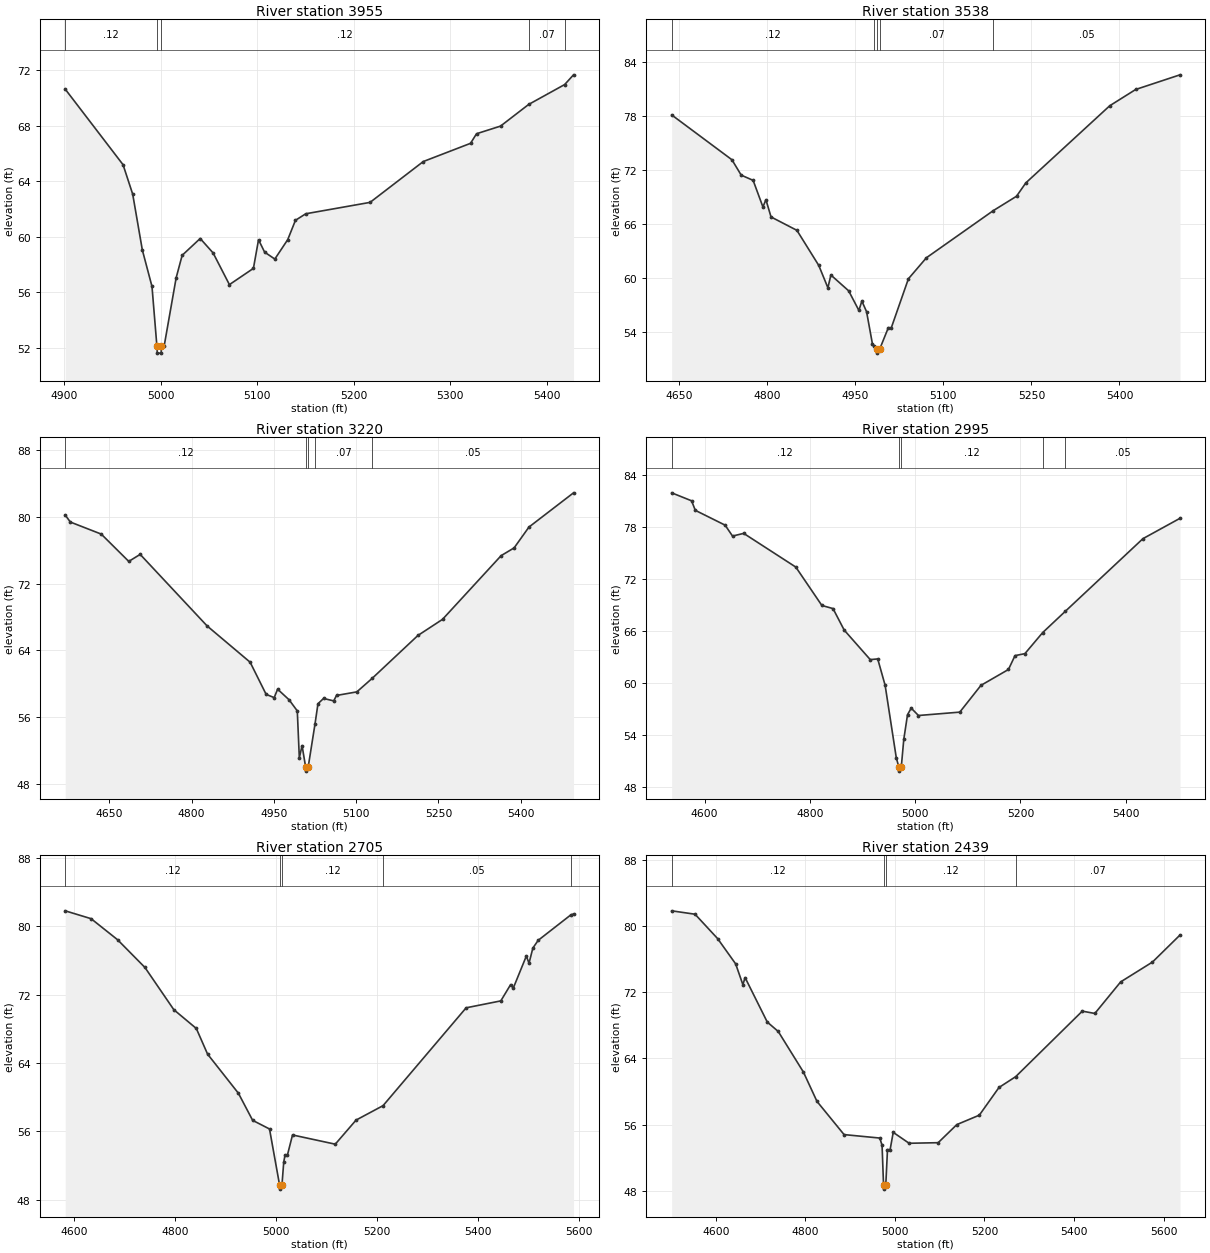
Type RM Length L Ch R = 1 ,3955    ,417,417,417
BEGIN DESCRIPTION:
TRIB 2 TO COURT BRANCH 6.0
END DESCRIPTION:
XS GIS Cut Line= 3
        2589275.     13458375.03        2589275.       13458475.
      2589425.01     13458875.03
#Sta/Elev= 30
  4900.8   70.63  4960.8   65.19  4970.8   63.07  4980.8   59.05  4990.8   56.43
  4995.9   52.13  4996.3   51.63  5000.3   51.63  5000.6   52.13  5003.4   52.13
  5015.9   57.06  5022.1   58.67  5040.8   59.88  5054.2   58.84  5071.1   56.56
    5096   57.73  5101.3   59.79  5107.6    58.9  5118.2    58.4  5131.6    59.8
  5139.6   61.19  5150.3   61.66    5217   62.48  5272.2   65.42  5321.2   66.73
  5327.4   67.42  5352.3   67.97  5381.5   69.53  5418.8   70.96    5428   71.66
#Mann= 5 ,-1 , 0
  4900.8     .12       0  4995.9     .07       0  5000.6     .12       0
  5381.5     .07       0  5418.8     .05       0
Bank Sta=4995.9,5000.6
XS Rating Curve= 0 ,0
Exp/Cntr=0.3,0.1

Type RM Length L Ch R = 1 ,3538    ,318,318,318
BEGIN DESCRIPTION:
Mapping XS 7b6f3a5a
END DESCRIPTION:
XS GIS Cut Line= 3
      2589088.65     13458318.52      2589020.94     13458683.07
       2589125.1     13459167.41
#Sta/Elev= 30
    4637   78.13  4739.7   73.14  4755.5   71.43  4775.8   70.85  4792.5   67.89
  4797.6    68.7  4806.3   66.78  4850.4   65.29  4887.7   61.38  4903.2    58.9
  4908.3   60.32  4938.6   58.56    4956   56.38  4961.1   57.42  4969.1   56.24
  4979.2   52.62  4982.4   52.42  4987.1   52.13  4987.4   51.63  4991.8   52.13
  5006.2   54.46  5011.3   54.46  5040.4    59.9  5071.1   62.24    5185   67.48
  5224.6   69.08  5240.5   70.57  5383.5   79.15  5427.7   80.96  5503.2   82.59
#Mann= 5 ,-1 , 0
    4637     .12       0  4982.4     .07       0  4987.1     .07       0
  4991.8     .07       0    5185     .05       0
Bank Sta=4987.1,4991.8
XS Rating Curve= 0 ,0
Exp/Cntr=0.3,0.1

Type RM Length L Ch R = 1 ,3220    ,225,225,225
BEGIN DESCRIPTION:
Mapping XS a8aa3ba0
END DESCRIPTION:
XS GIS Cut Line= 3
      2588968.85     13458276.83      2588718.86     13458615.36
      2588796.99     13459115.37
#Sta/Elev= 30
  4569.4    80.2  4578.8   79.36  4635.1   77.92  4685.3   74.65  4706.1   75.49
  4828.2   66.92  4906.6   62.58  4935.8   58.73  4950.5   58.34  4956.7   59.35
  4977.5   58.09  4992.6   56.75  4996.3   51.13  5001.3   52.59  5007.8   50.04
  5008.1   49.54  5012.5   50.04    5025   55.23  5030.3   57.61  5040.5   58.24
    5059   57.95  5064.1    58.6  5101.2   59.03    5129   60.64  5212.5   65.78
  5257.4   67.71  5364.3   75.34    5388   76.27    5415   78.76  5496.3   82.86
#Mann= 5 ,-1 , 0
  4569.4     .12       0  5007.8     .07       0  5012.5     .12       0
    5025     .07       0    5129     .05       0
Bank Sta=5007.8,5012.5
XS Rating Curve= 0 ,0
Exp/Cntr=0.3,0.1

Type RM Length L Ch R = 1 ,2995    ,290,290,290
BEGIN DESCRIPTION:
Mapping XS 21fa156d
END DESCRIPTION:
XS GIS Cut Line= 3
      2588843.86     13458240.36      2588510.53     13458573.69
      2588369.95     13459047.48
#Sta/Elev= 30
  4537.5   81.97  4575.3   81.05  4582.4   79.95    4639   78.24  4653.1   76.98
  4674.3   77.29  4773.3    73.4  4822.8   68.97    4844   68.61  4865.2   66.13
  4914.7   62.72  4928.9    62.8    4943   59.75  4964.2   51.38  4968.9   50.35
  4969.3   49.85  4973.7   50.35  4978.4   53.51  4985.5   56.36  4992.5   57.12
  5006.3   56.27  5084.8   56.66    5125   59.75  5177.2   61.58  5189.7   63.18
  5208.5   63.41  5242.1   65.83  5285.5   68.31  5432.7   76.68  5503.1   79.03
#Mann= 5 ,-1 , 0
  4537.5     .12       0  4968.9     .07       0  4973.7     .12       0
  5242.1     .07       0  5285.5     .05       0
Bank Sta=4968.9,4973.7
XS Rating Curve= 0 ,0
Exp/Cntr=0.3,0.1

Type RM Length L Ch R = 1 ,2705    ,266,266,266
BEGIN DESCRIPTION:
Mapping XS c278bded
END DESCRIPTION:
XS GIS Cut Line= 3
      2588698.03     13458188.27       2588307.4     13458380.98
      2588120.42     13458921.16
#Sta/Elev= 30
    4582   81.82  4633.3    80.9  4685.7   78.44    4740   75.19  4797.2   70.25
  4841.8   68.05  4864.1   65.05  4925.2   60.47  4953.4    57.3  4986.8   56.29
  5006.7   49.75  5007.1   49.25  5011.5   49.75    5015   52.42  5017.6   53.24
  5022.3   53.24  5032.4   55.59  5117.1   54.51  5158.3   57.33  5211.8   59.02
  5376.4   70.47  5445.1   71.28  5464.6   73.19  5469.9   72.79  5495.7   76.53
    5501   75.69  5508.6   77.46  5519.2   78.37  5583.5   81.33  5589.2   81.45
#Mann= 5 ,-1 , 0
    4582     .12       0  5006.7     .07       0  5011.5     .12       0
  5211.8     .05       0  5583.5     .07       0
Bank Sta=5006.7,5011.5
XS Rating Curve= 0 ,0
Exp/Cntr=0.3,0.1

Type RM Length L Ch R = 1 ,2439    ,275,275,275
BEGIN DESCRIPTION:
Mapping XS cf35f8f7
END DESCRIPTION:
XS GIS Cut Line= 3
      2588666.74     13458089.32      2588187.61     13458151.82
      2587661.58     13458537.22
#Sta/Elev= 30
  4501.5   81.87  4553.7   81.46  4604.1   78.51  4644.4   75.45  4660.5   72.94
  4665.5   73.79    4715   68.41  4739.5   67.27  4795.7   62.36    4826   58.81
  4886.5   54.79  4966.4   54.37  4971.4   53.49  4974.7   48.69  4975.1   48.19
  4979.7   48.69  4983.5   52.97  4989.4   52.97  4996.3   55.06  5031.8   53.74
  5096.7   53.81  5138.4      56  5188.6   57.14  5232.5   60.49  5269.8    61.8
  5418.6   69.73  5446.6   69.45  5504.3   73.27  5575.3   75.67  5636.8   78.94
#Mann= 4 ,-1 , 0
  4501.5     .12       0  4974.7     .07       0  4979.7     .12       0
  5269.8     .07       0
Bank Sta=4974.7,4979.7
XS Rating Curve= 0 ,0
Exp/Cntr=0.3,0.1

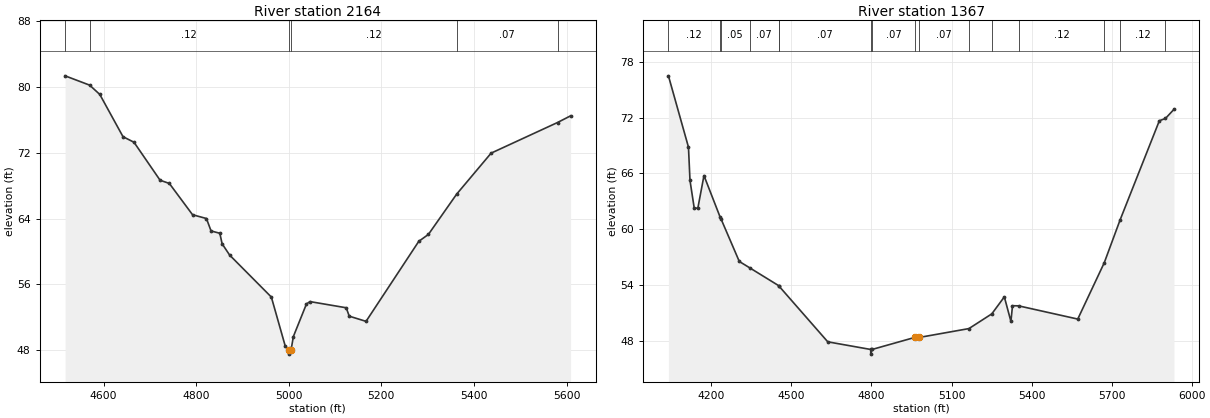
Type RM Length L Ch R = 1 ,2164    ,797,797,797
BEGIN DESCRIPTION:
Mapping XS 31c01d6d
END DESCRIPTION:
XS GIS Cut Line= 3
      2588619.91     13457912.23      2588125.11     13457938.27
      2587661.58     13458313.26
#Sta/Elev= 30
  4516.9   81.34  4569.9   80.21  4591.9   79.08    4642   73.95  4665.8   73.27
  4722.1   68.66  4742.1   68.27  4792.2   64.47  4822.2   64.01  4832.2    62.5
  4851.1   62.22  4856.1   60.94  4872.3   59.57  4962.4   54.47  4992.5    48.5
    5000   48.04  5000.4   47.54    5005   48.04  5009.9   49.67  5038.2   53.63
  5045.8   53.92  5124.1   53.17  5130.6   52.15  5166.9   51.52  5280.8   61.24
  5301.6   62.08  5362.7   66.98    5437   71.95  5580.4   75.67  5608.6   76.48
#Mann= 6 ,-1 , 0
  4516.9     .05       0  4569.9     .12       0    5000     .07       0
    5005     .12       0  5362.7     .07       0  5580.4     .05       0
Bank Sta=5000,5005
XS Rating Curve= 0 ,0
Exp/Cntr=0.3,0.1

Type RM Length L Ch R = 1 ,1367    ,0,0,0
BEGIN DESCRIPTION:
TRIB 2 TO COURT BRANCH 1.0
END DESCRIPTION:
XS GIS Cut Line= 4
      2588751.76     13457458.36      2588139.76     13457122.42
      2587749.14     13457411.48      2587611.54     13458108.64
#Sta/Elev= 30
  4038.9   76.47    4114   68.82  4119.7   65.25  4135.8   62.24  4149.3    62.3
  4172.1   65.77  4232.9    61.3  4235.9   61.13  4304.5   56.56  4342.8   55.89
  4451.8   53.97  4453.2   53.92  4636.1   47.94  4797.1   47.12  4797.4   46.62
  4802.1   47.12  4964.5   48.43  4979.1   48.41  5165.2   49.36    5251   50.94
  5297.9   52.76  5322.6   50.13  5328.5   51.81    5351    51.8  5573.1   50.38
  5672.4   56.42    5732   61.03  5878.9   71.65  5901.9    71.9  5933.6   72.87
#Mann= 16 ,-1 , 0
  4038.9     .12       0  4232.9     .07       0  4235.9     .05       0
  4342.8     .07       0  4451.8     .12       0  4453.2     .07       0
  4797.1     .07       0  4802.1     .07       0  4964.5     .07       0
  4979.1     .07       0  5165.2     .12       0    5251     .07       0
    5351     .12       0  5672.4     .07       0    5732     .12       0
  5901.9     .07       0
Bank Sta=4964.5,4979.1
XS Rating Curve= 0 ,0
Exp/Cntr=0.3,0.1

Chan Stop Cuts=-1
Use User Specified Reach Order=0
Composite Channel Slope=5