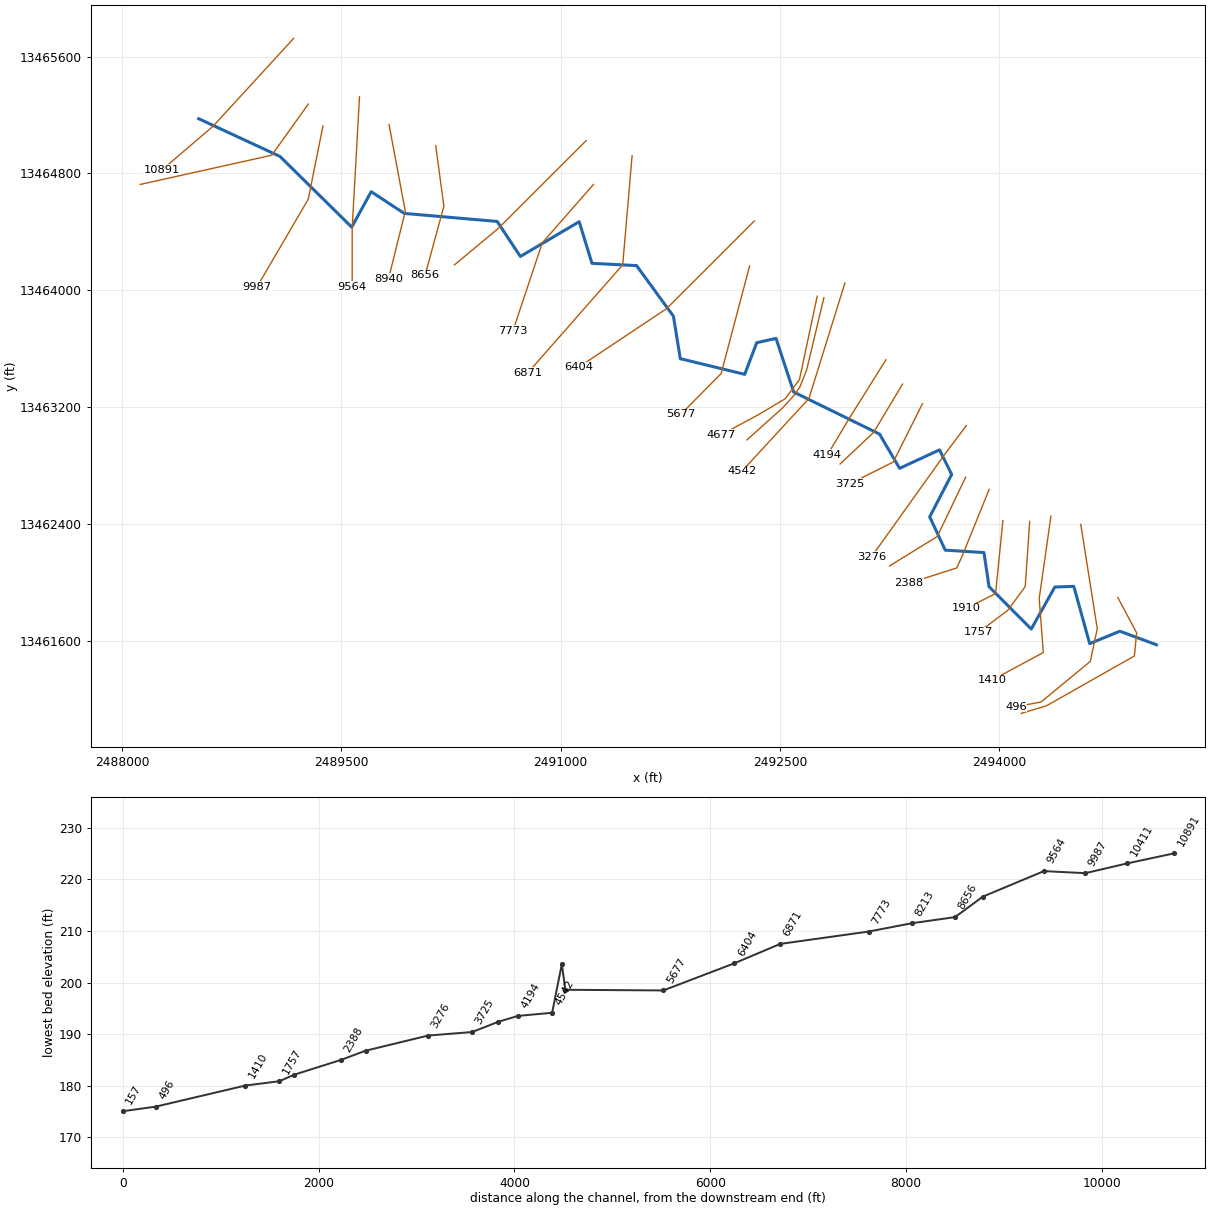
--- TRIB 2 TO FARMER CREEK.prj (project) ---

Proj Title=TRIB 2 TO FARMER CREEK Base Level Engineering
Current Plan=p01
Default Exp/Contr=0.3,0.1
English Units
Geom File=g01
Flow File=f01
Plan File=p01
Y Axis Title=Elevation
X Axis Title(PF)=Main Channel Distance
X Axis Title(XS)=Station
BEGIN DESCRIPTION:
TRIB 2 TO FARMER CREEK
END DESCRIPTION:
DSS Export Rating Curves= 0
DSS Export Rating Curve Sorted= 0
DSS Export Volume Flow Curves= 0
DXF OffsetX= 0
DXF OffsetY= 0
DXF ScaleX= 1
DXF ScaleY= 10

--- TRIB 2 TO FARMER CREEK.p01 (plan) ---

Plan Title=Multiple Run
Short Identifier=Multiple
Geom File=g01
Flow File=f01
Subcritical Flow
K Sum by GR= 0
Std Step Tol= 0.01
Critical Tol= 0.01
Num of Std Step Trials= 20
Max Error Tol= 0.3
Flow Tol Ratio= 0.001
Split Flow NTrial= 30
Split Flow Tol= 0.02
Split Flow Ratio= 0.02
Log Output Level= 0
Friction Slope Method= 1
Unsteady Friction Slope Method= 2
Unsteady Bridges Friction Slope Method= 1
Parabolic Critical Depth
Global Vel Dist=  1 , 1 , 1
Global Log Level= 0
CheckData=True
Encroach Param= -1, 0, 0, 0
BEGIN DESCRIPTION:
Multiple Run
END DESCRIPTION:

--- TRIB 2 TO FARMER CREEK.f01 (steady flow) ---

Flow Title=Multiple
Number of Profiles=7
Profile Names=10-year,25-year,50-year,1pct_min,100-year,1pct_plu,500-year
River Rch & RM= TRIB 2 TO FARMER,Reach-1,10891
     758    1228    1655    1079    2153    4297    3606
River Rch & RM= TRIB 2 TO FARMER,Reach-1,3993
     795    1289    1738    1133    2261    4511    3785
Boundary for River Rch & Prof#=TRIB 2 TO FARMER,Reach-1,1
Up Type=0
Dn Type=3
Dn Slope=0.005
Boundary for River Rch & Prof#=TRIB 2 TO FARMER,Reach-1,2
Up Type=0
Dn Type=3
Dn Slope=0.005
Boundary for River Rch & Prof#=TRIB 2 TO FARMER,Reach-1,3
Up Type=0
Dn Type=3
Dn Slope=0.005
Boundary for River Rch & Prof#=TRIB 2 TO FARMER,Reach-1,4
Up Type=0
Dn Type=3
Dn Slope=0.005
Boundary for River Rch & Prof#=TRIB 2 TO FARMER,Reach-1,5
Up Type=0
Dn Type=3
Dn Slope=0.005
Boundary for River Rch & Prof#=TRIB 2 TO FARMER,Reach-1,6
Up Type=0
Dn Type=3
Dn Slope=0.005
Boundary for River Rch & Prof#=TRIB 2 TO FARMER,Reach-1,7
Up Type=0
Dn Type=3
Dn Slope=0.005

--- TRIB 2 TO FARMER CREEK.g01 (geometry) ---

Geom Title=Existing Conditions
Program Version=4.10

River Reach=TRIB 2 TO FARMER,Reach-1
Reach XY= 30
        2488525.       13465175.      2489081.05     13464916.84
      2489571.98     13464432.75      2489704.76      13464675.5
      2489930.68     13464526.97      2490566.68     13464471.85
      2490724.98     13464232.08      2491127.32     13464469.94
      2491214.83     13464185.28      2491519.56     13464169.76
      2491771.87     13463823.37      2491818.79     13463532.81
      2492259.42     13463425.55      2492341.45     13463642.15
      2492473.51     13463671.55      2492594.27     13463304.52
      2493181.07     13463016.85      2493318.63     13462782.33
      2493591.71     13462908.81      2493674.64     13462740.27
      2493524.58       13462450.      2493630.71     13462222.41
      2493895.53     13462205.91      2493930.34     13461972.26
      2494218.94     13461682.45      2494380.08     13461969.98
      2494509.96      13461974.7       2494618.5     13461582.62
       2494824.9     13461667.67        2495075.       13461575.

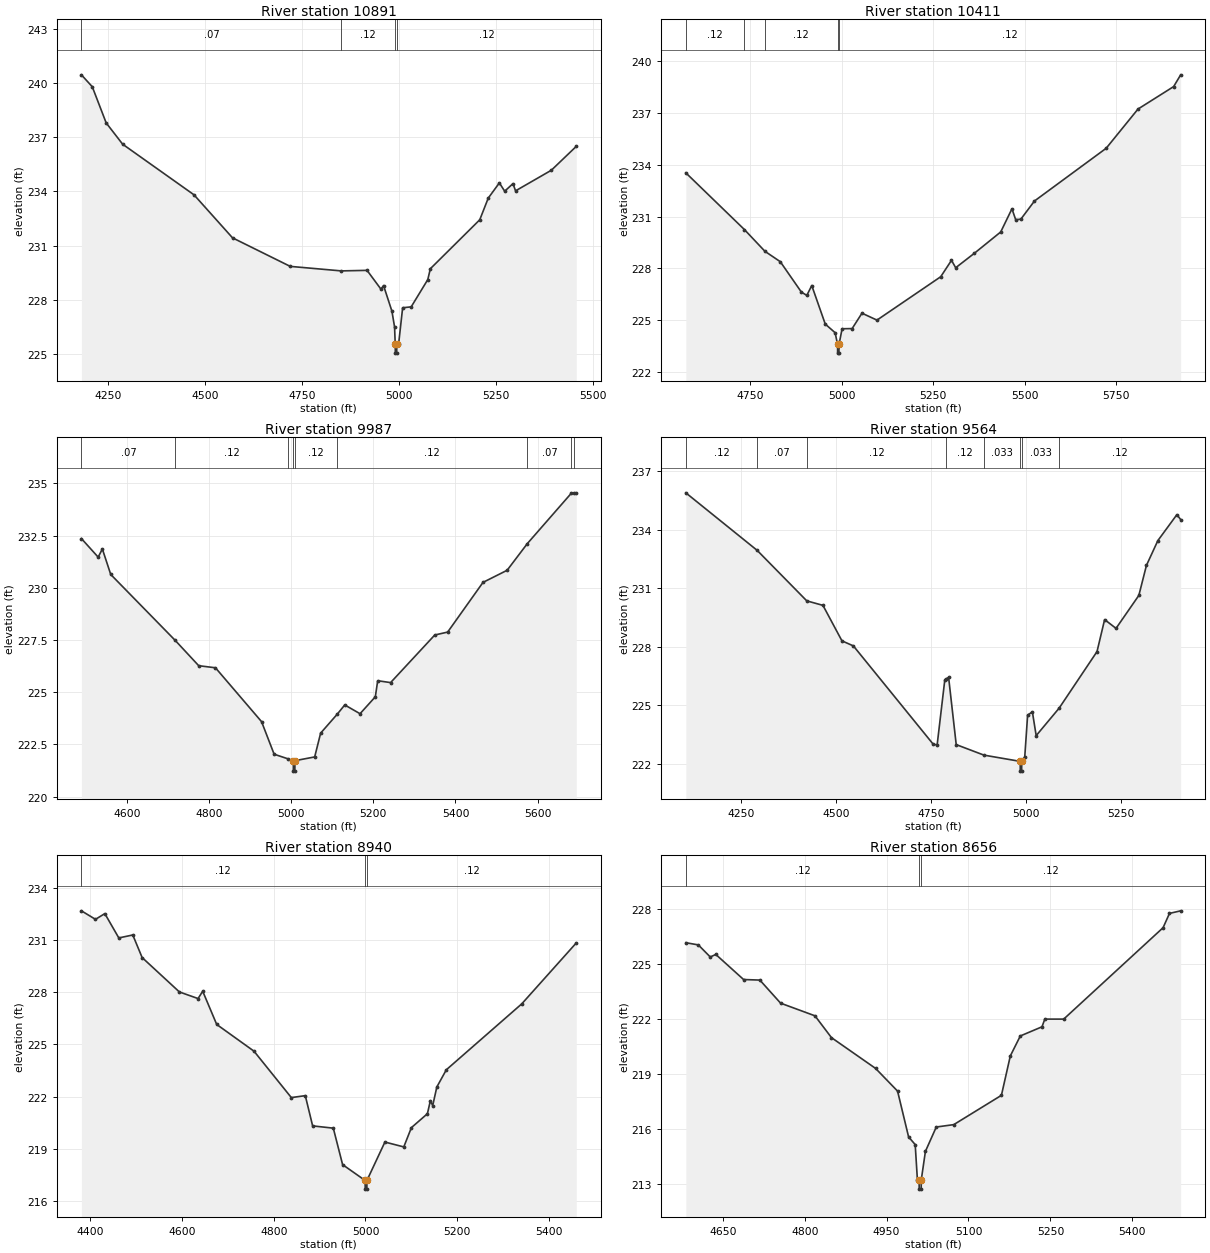
Type RM Length L Ch R = 1 ,10891   ,480,480,480
BEGIN DESCRIPTION:
TRIB 2 TO FARMER CREEK 22.0
END DESCRIPTION:
XS GIS Cut Line= 3
      2489174.97     13465724.96        2488625.       13465125.
      2488274.98     13464824.98
#Sta/Elev= 30
  4181.3  240.45  4209.3  239.79  4245.1  237.79  4287.6  236.61  4471.4  233.81
  4570.6  231.43  4719.3  229.85  4850.8   229.6  4917.2  229.63    4953  228.59
  4959.7  228.79  4981.3  227.37  4988.1   226.5  4989.8  225.55  4990.1  225.05
  4993.6  225.05  4993.8  225.55  4998.5  225.55  5008.9  227.56  5030.9  227.61
  5073.7  229.12  5080.3  229.72  5207.6  232.43  5229.5  233.63  5258.1  234.47
  5271.8  234.01  5293.2  234.43  5299.8  234.03    5392  235.17  5456.2  236.49
#Mann= 4 ,-1 , 0
  4181.3     .07       0  4850.8     .12       0  4989.8     .05       0
  4993.8     .12       0
Bank Sta=4989.8,4993.8
XS Rating Curve= 0 ,0
Exp/Cntr=0.3,0.1

Type RM Length L Ch R = 1 ,10411   ,424,424,424
BEGIN DESCRIPTION:
TRIB 2 TO FARMER CREEK 21.0
END DESCRIPTION:
XS GIS Cut Line= 3
        2489275.     13465274.99        2489025.       13464925.
      2488124.97     13464724.99
#Sta/Elev= 30
  4574.4  233.53  4734.4  230.25  4790.6  228.99  4832.5  228.39  4890.2  226.63
    4905  226.44  4918.5  227.01  4955.4  224.78  4982.4  224.28    4989   223.6
  4989.2   223.1  4992.7   223.1    4993   223.6  5001.4  224.51  5028.8  224.52
  5055.7  225.41  5096.7  225.01  5270.9  227.52  5300.3  228.47  5311.8  228.04
    5363  228.88  5434.8  230.11  5465.5  231.45  5475.7  230.82  5489.8  230.85
    5527   231.9  5722.9  234.95  5809.9  237.22  5907.3  238.52  5926.5   239.2
#Mann= 5 ,-1 , 0
  4574.4     .12       0  4734.4     .07       0  4790.6     .12       0
    4989     .05       0    4993     .12       0
Bank Sta=4989,4993
XS Rating Curve= 0 ,0
Exp/Cntr=0.3,0.1

Type RM Length L Ch R = 1 ,9987    ,423,423,423
BEGIN DESCRIPTION:
TRIB 2 TO FARMER CREEK 20.0
END DESCRIPTION:
XS GIS Cut Line= 3
        2489375.       13465125.        2489275.       13464625.
      2488925.01     13464025.02
#Sta/Elev= 30
  4489.5  232.36  4530.3  231.47  4540.5  231.86  4560.9  230.64  4717.9  227.48
    4775  226.27  4815.8  226.17    4928  223.59  4958.6  222.03  4992.2  221.81
  5005.3  221.72  5005.5  221.22    5009  221.22  5009.3  221.72  5057.3   221.9
  5071.8  223.04  5111.9  223.94  5130.5  224.39  5167.7  223.97  5204.9  224.78
  5210.7  225.55  5242.1  225.46  5349.6  227.74    5381  227.88    5467  230.26
  5525.7  230.84    5575  232.12  5682.4  234.54  5687.8  234.55    5694  234.52
#Mann= 9 ,-1 , 0
  4489.5     .07       0  4717.9     .12       0  4992.2     .12       0
  5005.3     .05       0  5009.3     .12       0  5111.9     .12       0
    5575     .07       0  5682.4     .12       0  5687.8     .07       0
Bank Sta=5005.3,5009.3
XS Rating Curve= 0 ,0
Exp/Cntr=0.3,0.1

Type RM Length L Ch R = 1 ,9564    ,624,624,624
BEGIN DESCRIPTION:
TRIB 2 TO FARMER CREEK 19.0
END DESCRIPTION:
XS GIS Cut Line= 3
        2489625.     13465325.02        2489575.       13464425.
        2489575.       13464025.
#Sta/Elev= 30
  4105.8  235.89  4293.4  232.94  4423.9  230.35  4466.4  230.12  4516.4   228.3
  4546.5  228.04  4756.8  222.99  4766.8  222.97  4786.9   226.3    4791  226.35
  4796.9  226.43  4816.9  222.98  4889.9  222.44  4985.2  222.12  4985.4  221.62
  4988.9  221.62  4989.2  222.12  4997.2  222.36  5004.7  224.49  5017.2  224.66
  5027.2  223.44  5087.6  224.85  5187.2  227.75  5207.2  229.39  5237.2  228.94
  5297.2  230.63  5317.2  232.17  5347.2  233.44  5397.2  234.77  5407.2  234.52
#Mann= 8 ,-1 , 0
  4105.8     .12       0  4293.4     .07       0  4423.9     .12       0
    4791     .12       0  4889.9    .033       0  4985.2    .033       0
  4989.2    .033       0  5087.6     .12       0
Bank Sta=4985.2,4989.2
XS Rating Curve= 0 ,0
Exp/Cntr=0.3,0.1

Type RM Length L Ch R = 1 ,8940    ,284,284,284
BEGIN DESCRIPTION:
Mapping XS d4680327
END DESCRIPTION:
XS GIS Cut Line= 3
      2489827.07      13465135.2      2489938.18     13464541.42
      2489823.65      13464079.8
#Sta/Elev= 30
  4380.2  232.69  4410.9   232.2  4431.3  232.53  4461.8  231.13  4492.3   231.3
  4512.7     230    4594  228.02  4634.7  227.64  4644.9  228.06  4675.4  226.15
  4756.8  224.61  4838.2  221.94  4868.7  222.05  4884.7  220.31  4929.8  220.18
  4950.1  218.08  4999.2  217.17  4999.5  216.67    5003  216.67  5003.2  217.17
  5042.4  219.38  5083.6   219.1  5100.2  220.21  5135.1  221.01  5141.6  221.76
  5146.7  221.48  5155.7  222.55  5176.4  223.54  5341.2  227.34  5459.9  230.84
#Mann= 3 ,-1 , 0
  4380.2     .12       0  4999.2     .05       0  5003.2     .12       0
Bank Sta=4999.2,5003.2
XS Rating Curve= 0 ,0
Exp/Cntr=0.3,0.1

Type RM Length L Ch R = 1 ,8656    ,443,443,443
BEGIN DESCRIPTION:
Mapping XS 7a97eee1
END DESCRIPTION:
XS GIS Cut Line= 3
      2490146.51     13464989.36      2490202.07     13464576.14
      2490073.61     13464103.94
#Sta/Elev= 30
  4582.3  226.15  4605.2  226.03  4627.1  225.37  4637.2  225.51  4688.1  224.14
  4717.9  224.11  4755.9  222.85  4818.8  222.16    4849  220.97  4929.8  219.29
  4970.1  218.05  4990.3  215.55  5002.4  215.13  5006.4  213.22  5009.5   213.2
  5009.8   212.7  5013.3   212.7  5013.5   213.2  5021.1  214.76    5041  216.09
    5073  216.22  5160.3  217.82  5176.6  219.97  5194.9  221.06  5234.6  221.56
  5239.8  221.98  5274.4  221.98  5456.4  226.97  5468.1  227.75  5488.6  227.89
#Mann= 3 ,-1 , 0
  4582.3     .12       0  5009.5     .05       0  5013.5     .12       0
Bank Sta=5009.5,5013.5
XS Rating Curve= 0 ,0
Exp/Cntr=0.3,0.1

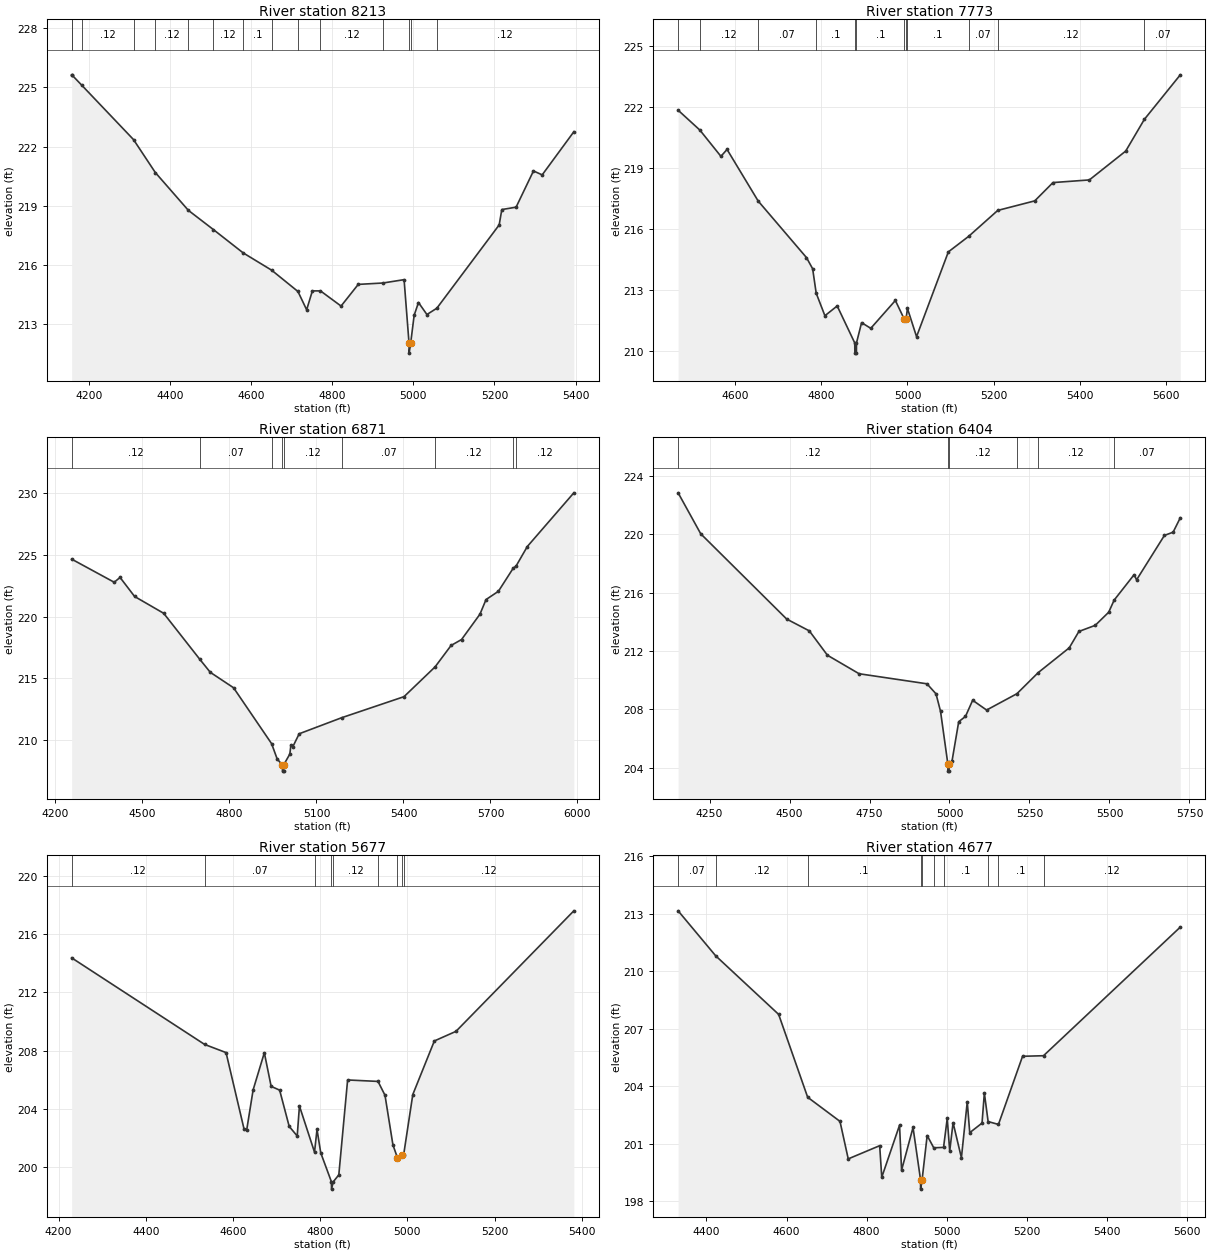
Type RM Length L Ch R = 1 ,8213    ,440,440,440
BEGIN DESCRIPTION:
TRIB 2 TO FARMER CREEK 16.0
END DESCRIPTION:
XS GIS Cut Line= 3
      2491174.98     13465024.98        2490575.       13464425.
      2490275.01     13464175.01
#Sta/Elev= 30
  4156.9  225.64  4157.3  225.64  4181.5  225.12  4309.6  222.35  4363.3  220.68
  4444.8  218.76  4506.8  217.78    4580   216.6  4650.4  215.72  4715.2  214.64
  4736.7  213.71  4750.8  214.67  4770.8  214.67  4821.6   213.9    4864     215
  4924.8  215.07  4977.1  215.24  4989.3  212.01  4989.5  211.51  4993.3  212.01
  5001.9  213.43  5012.6  214.08  5033.4  213.47  5057.9  213.79  5211.7  218.02
  5218.2   218.8  5253.4  218.92  5296.3  220.76  5317.8  220.56  5395.9  222.75
#Mann= 15 ,-1 , 0
  4156.9     .12       0  4157.3     .07       0  4181.5     .12       0
  4309.6     .07       0  4363.3     .12       0  4444.8     .07       0
  4506.8     .12       0    4580      .1       0  4650.4     .12       0
  4715.2      .1       0  4770.8     .12       0  4924.8      .1       0
  4989.3     .05       0  4993.3      .1       0  5057.9     .12       0
Bank Sta=4989.3,4993.3
XS Rating Curve= 0 ,0
Exp/Cntr=0.3,0.1

Type RM Length L Ch R = 1 ,7773    ,902,902,902
BEGIN DESCRIPTION:
TRIB 2 TO FARMER CREEK 15.0
END DESCRIPTION:
XS GIS Cut Line= 3
      2491224.98     13464724.98        2490875.       13464325.
      2490675.01     13463725.03
#Sta/Elev= 30
  4468.5  221.85    4519  220.87  4567.7  219.58  4581.9  219.92  4654.1  217.38
    4766   214.6  4780.3  214.05  4788.5  212.85  4808.7  211.74  4837.2  212.22
  4877.9   210.4  4878.2   209.9  4881.7   209.9  4881.9   210.4  4893.7   211.4
    4915  211.12    4972  212.49  4992.9  211.56  4996.7  211.56    5000   212.1
  5021.1  210.71  5094.8  214.88  5141.6  215.64  5209.3  216.92  5295.1  217.39
  5337.3  218.29  5421.6  218.42  5505.9  219.84  5549.1   221.4  5632.4  223.59
#Mann= 12 ,-1 , 0
  4468.5     .07       0    4519     .12       0  4654.1     .07       0
  4788.5      .1       0  4877.9     .07       0  4881.9      .1       0
  4992.9     .05       0  4996.7     .07       0    5000      .1       0
  5141.6     .07       0  5209.3     .12       0  5549.1     .07       0
Bank Sta=4992.9,4996.7
XS Rating Curve= 0 ,0
Exp/Cntr=0.3,0.1

Type RM Length L Ch R = 1 ,6871    ,467,467,467
BEGIN DESCRIPTION:
TRIB 2 TO FARMER CREEK 14.0
END DESCRIPTION:
XS GIS Cut Line= 3
      2491489.18     13464921.27        2491425.       13464175.
       2490776.7     13463436.53
#Sta/Elev= 30
  4255.7  224.65  4402.5  222.78  4422.6  223.17  4472.8  221.63  4573.1  220.27
  4696.6  216.58  4733.7   215.5    4814  214.25  4945.2  209.73  4964.6  208.48
  4982.7  208.01  4982.9  207.51  4986.4  207.51  4986.7  208.01  5008.1  208.89
  5011.8  209.63  5018.5  209.49  5040.3  210.53    5187  211.83  5401.8  213.53
    5509  215.94  5564.1  217.67  5600.2  218.15  5663.7   220.2  5684.6  221.38
  5727.3  222.05  5778.2  223.91  5788.2  224.09    5827  225.67  5987.4  230.01
#Mann= 9 ,-1 , 0
  4255.7     .12       0  4696.6     .07       0  4945.2     .12       0
  4982.7     .05       0  4986.7     .12       0    5187     .07       0
    5509     .12       0  5778.2     .07       0  5788.2     .12       0
Bank Sta=4982.7,4986.7
XS Rating Curve= 0 ,0
Exp/Cntr=0.3,0.1

Type RM Length L Ch R = 1 ,6404    ,727,727,727
BEGIN DESCRIPTION:
TRIB 2 TO FARMER CREEK 13.0
END DESCRIPTION:
XS GIS Cut Line= 3
      2492324.98     13464474.98        2491725.       13463875.
      2491125.01       13463475.
#Sta/Elev= 30
  4151.8  222.85  4222.5  220.04  4491.2  214.19  4561.9  213.38  4618.5  211.71
  4717.5  210.44  4929.6  209.75  4957.9  209.06    4972  207.86  4994.8  204.26
    4995  203.76  4998.5  203.76  4998.8  204.26  5007.8  204.44  5028.8  207.15
  5049.9  207.51  5072.4  208.62    5116  207.95  5210.7  209.07  5277.4  210.52
  5374.4  212.22  5404.4  213.34  5455.5  213.76  5497.6  214.66  5514.6  215.49
  5577.2  217.24  5584.7  216.88  5671.8  219.93  5698.9  220.15  5721.4  221.14
#Mann= 6 ,-1 , 0
  4151.8     .12       0  4994.8     .05       0  4998.8     .12       0
  5210.7     .07       0  5277.4     .12       0  5514.6     .07       0
Bank Sta=4994.8,4998.8
XS Rating Curve= 0 ,0
Exp/Cntr=0.3,0.1

Type RM Length L Ch R = 1 ,5677    ,1000,1000,1000
BEGIN DESCRIPTION:
Mapping XS 01fa81ab
END DESCRIPTION:
XS GIS Cut Line= 3
      2492292.82     13464167.38      2492098.38     13463431.27
       2491824.1     13463153.52
#Sta/Elev= 30
  4230.1  214.38  4535.1  208.43  4584.2  207.87  4625.6   202.6  4631.7  202.58
  4646.3  205.31    4672  207.86  4687.6  205.55  4707.1  205.29    4729   202.8
  4747.4  202.14  4752.5   204.2  4787.1  201.03  4792.8  202.59  4801.4  200.98
  4825.9  198.99  4826.1  198.49  4829.9  198.99  4842.8  199.47    4863  205.99
  4932.7  205.89  4948.7  204.94  4966.9  201.53  4977.3  200.64  4988.3  200.85
  4991.5  200.85  5012.5  204.99  5061.9  208.67  5111.5  209.33  5381.8  217.61
#Mann= 9 ,-1 , 0
  4230.1     .12       0  4535.1     .07       0  4787.1     .12       0
  4825.9     .07       0  4829.9     .12       0  4932.7     .12       0
  4977.3     .05       0  4988.3     .07       0  4991.5     .12       0
Bank Sta=4977.3,4988.3
XS Rating Curve= 0 ,0
Exp/Cntr=0.3,0.1

Type RM Length L Ch R = 1 ,4677    ,36,36,36
BEGIN DESCRIPTION:
Mapping XS a5d2457b
END DESCRIPTION:
XS GIS Cut Line= 5
      2492755.22     13463960.46       2492633.7     13463389.74
      2492536.04     13463258.45       2492351.2     13463148.31
      2492094.41     13463009.96
#Sta/Elev= 30
  4329.3  213.16  4423.1  210.81  4580.3  207.75  4652.8  203.42  4733.5  202.16
  4754.1   200.2  4832.6  200.89  4837.8  199.24  4882.2  201.96  4887.3  199.61
  4915.9  201.84  4934.6  199.12  4934.8  198.62  4938.6  199.12  4951.2  201.42
  4967.6  200.78  4992.1   200.8  5001.3  202.31  5007.5  200.61  5015.9  202.09
  5036.7  200.26  5051.3  203.18  5057.5  201.57  5088.2  202.07    5094  203.64
  5103.4  202.15  5129.2     202  5189.4  205.56  5241.7  205.59  5583.3  212.31
#Mann= 10 ,-1 , 0
  4329.3     .07       0  4423.1     .12       0  4652.8      .1       0
  4934.6     .05       0  4938.6      .1       0  4967.6     .07       0
  4992.1      .1       0  5103.4     .07       0  5129.2      .1       0
  5241.7     .12       0
Bank Sta=4934.6,4938.6
XS Rating Curve= 0 ,0
Exp/Cntr=0.3,0.1

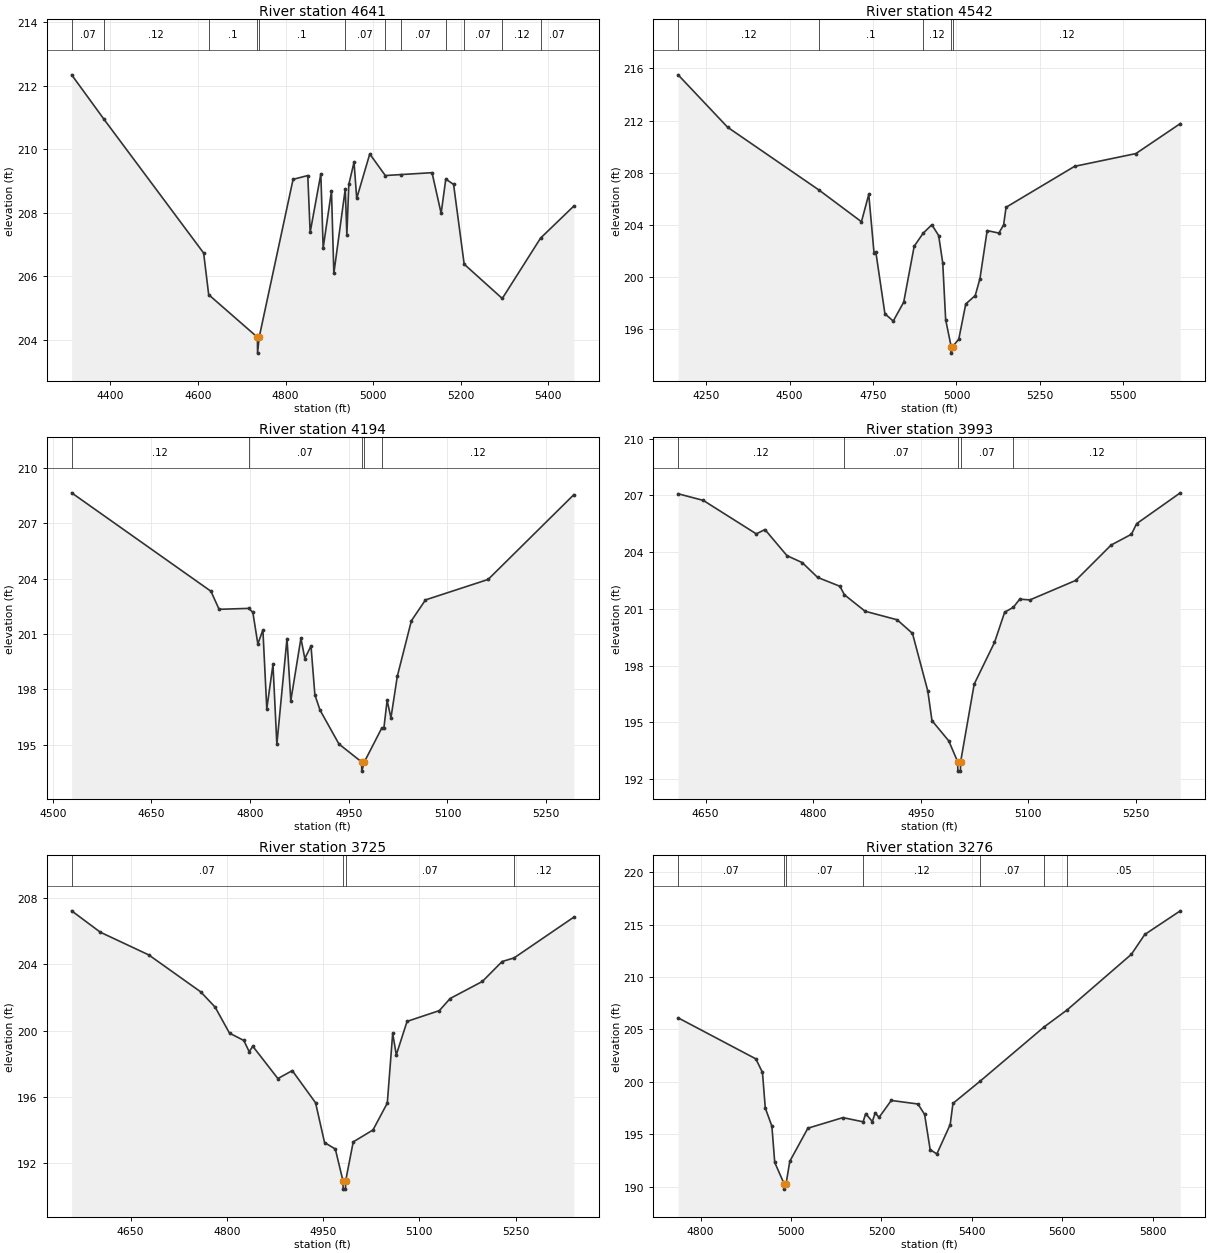
Type RM Length L Ch R = 1 ,4641    ,99,99,99
BEGIN DESCRIPTION:
Mapping XS 07b72ecf
END DESCRIPTION:
XS GIS Cut Line= 6
      2492800.78     13463949.59      2492682.96     13463455.59
      2492636.73     13463338.66      2492601.38       13463287.
       2492519.8     13463197.26      2492275.09     13462977.02
#Sta/Elev= 30
  4311.5  212.34  4385.4  210.94  4612.9  206.73  4624.4  205.42  4735.7  204.08
    4736  203.58  4739.7  204.08  4817.1  209.05  4850.7  209.17  4856.1  207.38
  4880.5  209.22  4885.8  206.89  4904.8  208.68  4910.2  206.09  4936.3  208.75
  4939.9   207.3  4944.4  208.89  4956.3  209.59  4962.4  208.45  4992.2  209.85
  5027.7  209.17    5063   209.2  5134.4  209.26  5155.2  207.98  5165.8  209.06
  5183.6  208.89  5207.8  206.38  5294.8   205.3  5382.2   207.2  5458.2  208.21
#Mann= 12 ,-1 , 0
  4311.5     .07       0  4385.4     .12       0  4624.4      .1       0
  4735.7     .05       0  4739.7      .1       0  4936.3     .07       0
  5027.7      .1       0    5063     .07       0  5165.8      .1       0
  5207.8     .07       0  5294.8     .12       0  5382.2     .07       0
Bank Sta=4735.7,4739.7
XS Rating Curve= 0 ,0
Exp/Cntr=0.3,0.1

Type RM Length L Ch R = 1 ,4542    ,348,348,348
BEGIN DESCRIPTION:
Mapping XS 0fe45126
END DESCRIPTION:
XS GIS Cut Line= 3
      2492944.47     13464050.37       2492698.6     13463260.17
      2492239.77     13462762.32
#Sta/Elev= 30
  4166.1  215.51  4314.4  211.49  4587.7  206.68  4715.4  204.24  4737.3  206.34
  4753.2  201.81  4758.4  201.93  4785.7  197.18  4810.6  196.62    4842  198.07
  4873.4  202.36  4900.3  203.36  4926.3  204.01  4946.7  203.18  4958.9  201.09
  4967.7  196.72  4984.2  194.66  4984.4  194.16  4988.2  194.66  5006.9  195.22
  5027.9  197.93  5056.3  198.58  5070.4  199.87    5092  203.56  5127.1  203.37
  5141.3     204  5148.7  205.35    5354  208.49  5537.7  209.47  5670.7  211.77
#Mann= 5 ,-1 , 0
  4166.1     .12       0  4587.7      .1       0  4900.3     .12       0
  4984.2     .05       0  4988.2     .12       0
Bank Sta=4984.2,4988.2
XS Rating Curve= 0 ,0
Exp/Cntr=0.3,0.1

Type RM Length L Ch R = 1 ,4194    ,201,201,201
BEGIN DESCRIPTION:
TRIB 2 TO FARMER CREEK 8.0
END DESCRIPTION:
XS GIS Cut Line= 3
      2493225.01     13463525.01        2492975.       13463125.
      2492824.98     13462874.96
#Sta/Elev= 30
  4528.8  208.66  4740.5  203.32  4752.9  202.34  4797.8  202.39  4804.2  202.18
  4811.8  200.46  4819.5  201.22  4825.4  196.94  4834.8  199.35  4840.7  195.02
  4856.1  200.75  4861.9  197.38  4877.3  200.77  4883.2  199.67  4892.6  200.35
  4898.5   197.7  4906.2  196.88  4935.1  195.03  4969.5  194.06  4969.8  193.56
  4973.7  194.06  5000.2   195.9  5003.4   195.9  5008.3   197.4  5014.1  196.45
  5023.8  198.71  5045.2  201.72  5066.6  202.85  5161.8  203.96  5292.1  208.56
#Mann= 5 ,-1 , 0
  4528.8     .12       0  4797.8     .07       0  4969.5     .05       0
  4973.7     .07       0  5000.2     .12       0
Bank Sta=4969.5,4973.7
XS Rating Curve= 0 ,0
Exp/Cntr=0.3,0.1

Type RM Length L Ch R = 1 ,3993    ,268,268,268
BEGIN DESCRIPTION:
Mapping XS 898c16ed
END DESCRIPTION:
XS GIS Cut Line= 3
       2493338.8     13463358.89      2493140.87     13463028.14
      2492911.68     13462811.97
#Sta/Elev= 30
  4611.6  207.08  4646.7  206.73  4720.7  204.96  4732.7  205.19  4763.4  203.81
  4784.8  203.44  4806.2  202.66  4837.3  202.19  4843.6  201.74  4872.5  200.87
  4917.1  200.42  4938.5   199.7  4959.9  196.65  4965.7  195.09  4989.1  194.02
  5001.5  192.92  5001.8  192.42  5005.4  192.42  5005.7  192.92  5024.6  197.02
  5052.9  199.22  5067.1  200.82  5079.2  201.08  5088.1  201.51  5102.3  201.47
  5166.2   202.5  5215.6  204.37  5243.9  204.94  5251.2   205.5  5312.1  207.13
#Mann= 5 ,-1 , 0
  4611.6     .12       0  4843.6     .07       0  5001.5     .05       0
  5005.7     .07       0  5079.2     .12       0
Bank Sta=5001.5,5005.7
XS Rating Curve= 0 ,0
Exp/Cntr=0.3,0.1

Type RM Length L Ch R = 1 ,3725    ,449,449,449
BEGIN DESCRIPTION:
TRIB 2 TO FARMER CREEK 7.0
END DESCRIPTION:
XS GIS Cut Line= 3
        2493475.       13463225.        2493275.       13462825.
      2492975.02     13462675.01
#Sta/Elev= 30
  4558.1  207.22  4602.8  205.93  4678.3  204.56  4759.3  202.33  4781.7  201.41
  4804.1  199.84  4826.4   199.4  4834.8  198.72  4840.4  199.05  4879.5   197.1
  4901.9  197.58  4938.2  195.64  4952.2  193.24    4969  192.85  4980.9  190.93
  4981.2  190.43  4984.8  190.43  4985.1  190.93  4996.9  193.28  5027.7     194
    5050  195.62  5058.4  199.83    5064  198.53  5080.8  200.55  5131.1   201.2
  5147.9  201.93  5198.2  202.96  5228.9  204.16  5247.6  204.38  5340.7  206.84
#Mann= 4 ,-1 , 0
  4558.1     .07       0  4980.9     .05       0  4985.1     .07       0
  5247.6     .12       0
Bank Sta=4980.9,4985.1
XS Rating Curve= 0 ,0
Exp/Cntr=0.3,0.1

Type RM Length L Ch R = 1 ,3276    ,639,639,639
BEGIN DESCRIPTION:
TRIB 2 TO FARMER CREEK 6.0
END DESCRIPTION:
XS GIS Cut Line= 3
      2493775.01     13463075.01        2493625.       13462875.
      2493125.02     13462175.03
#Sta/Elev= 30
  4750.5  206.11  4922.4  202.19    4937  200.89  4943.2   197.5  4957.8  195.76
  4964.1   192.3  4984.9  190.25  4985.1  189.75  4989.1  190.25  4997.4  192.41
  5037.4  195.57  5114.8  196.58  5159.4  196.18  5165.2  196.96  5179.9   196.2
  5186.1  197.03  5194.7   196.6  5221.7  198.22  5280.7  197.88  5295.4  196.89
  5307.7  193.52  5322.5  193.11    5352  195.92  5358.1  197.94  5417.6  200.04
  5559.6  205.24  5610.6  206.87  5752.6  212.18  5782.1  214.07  5860.7  216.33
#Mann= 7 ,-1 , 0
  4750.5     .07       0  4984.9     .05       0  4989.1     .07       0
  5159.4     .12       0  5417.6     .07       0  5559.6     .12       0
  5610.6     .05       0
Bank Sta=4984.9,4989.1
XS Rating Curve= 0 ,0
Exp/Cntr=0.3,0.1

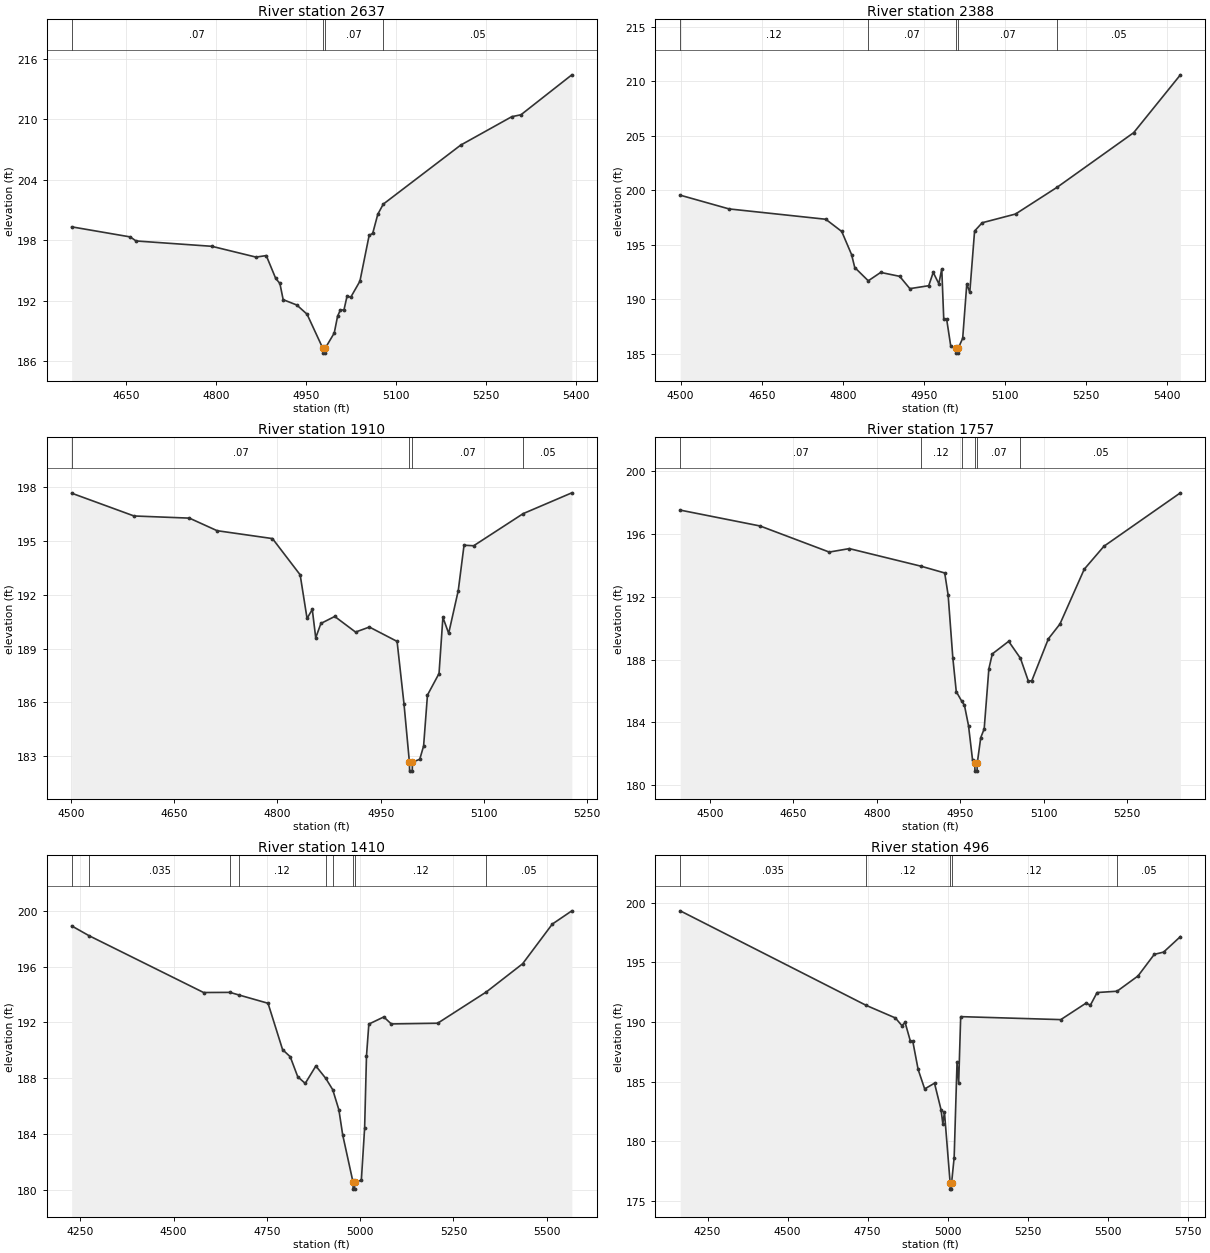
Type RM Length L Ch R = 1 ,2637    ,249,249,249
BEGIN DESCRIPTION:
Mapping XS d167100a
END DESCRIPTION:
XS GIS Cut Line= 3
      2493770.37     13462721.76      2493575.94     13462315.55
      2493249.78      13462114.3
#Sta/Elev= 30
  4559.6  199.33  4657.2  198.33  4666.9  197.93  4793.2   197.4  4866.8  196.33
  4883.9  196.48  4899.7  194.21  4906.6  193.72  4912.1  192.11  4934.8  191.58
  4951.9  190.67    4978  187.31  4978.3  186.81    4982  186.81  4982.3  187.31
  4997.2   188.8  5002.8  190.48  5007.5  191.09  5013.4  191.09  5018.7   192.5
  5024.6  192.34    5040  193.94  5055.4  198.49  5061.3  198.68  5069.8  200.58
  5078.9  201.58  5207.9  207.43  5293.1  210.25  5308.4  210.44  5393.2   214.4
#Mann= 4 ,-1 , 0
  4559.6     .07       0    4978     .05       0  4982.3     .07       0
  5078.9     .05       0
Bank Sta=4978,4982.3
XS Rating Curve= 0 ,0
Exp/Cntr=0.3,0.1

Type RM Length L Ch R = 1 ,2388    ,478,478,478
BEGIN DESCRIPTION:
Mapping XS b04ddd55
END DESCRIPTION:
XS GIS Cut Line= 4
      2493931.23     13462638.63      2493747.21     13462183.78
      2493709.02     13462100.45      2493382.67     13461996.29
#Sta/Elev= 30
  4499.2  199.54  4589.4  198.28  4768.3  197.33  4797.8  196.21    4816  194.09
  4821.9   192.9  4846.9  191.68  4869.9  192.45    4905  192.09  4923.8  190.96
  4958.7  191.23    4967  192.45  4977.4  191.41  4982.8  192.78  4986.5  188.14
  4991.9  188.14  4999.5  185.66  5009.4  185.54  5009.7  185.04  5013.4  185.04
  5013.7  185.54  5021.5   186.4  5029.1   191.4  5034.6  190.62  5043.5  196.25
  5057.6  197.01  5119.2  197.81  5196.8  200.29  5337.7  205.28  5424.1  210.59
#Mann= 5 ,-1 , 0
  4499.2     .12       0  4846.9     .07       0  5009.4     .05       0
  5013.7     .07       0  5196.8     .05       0
Bank Sta=5009.4,5013.7
XS Rating Curve= 0 ,0
Exp/Cntr=0.3,0.1

Type RM Length L Ch R = 1 ,1910    ,153,153,153
BEGIN DESCRIPTION:
TRIB 2 TO FARMER CREEK 3.0
END DESCRIPTION:
XS GIS Cut Line= 3
        2494025.     13462425.05        2493975.       13461925.
      2493775.04     13461825.02
#Sta/Elev= 30
  4501.4  197.66  4591.9  196.39  4672.3  196.27  4712.5  195.57  4792.9  195.13
  4833.1  193.11  4843.1  190.68  4850.7  191.18  4855.7   189.6  4863.2   190.4
  4883.3  190.79  4913.5  189.92  4933.6   190.2  4973.8   189.4  4983.8  185.93
  4991.7  182.67    4992  182.17  4995.8  182.17  4996.1  182.67  5006.7  182.83
  5012.3  183.57  5017.9  186.41  5034.7  187.61  5040.3  190.74  5048.7  189.85
  5062.6  192.23    5071  194.76    5085  194.73  5156.8  196.52  5227.5  197.68
#Mann= 4 ,-1 , 0
  4501.4     .07       0  4991.7     .05       0  4996.1     .07       0
  5156.8     .05       0
Bank Sta=4991.7,4996.1
XS Rating Curve= 0 ,0
Exp/Cntr=0.3,0.1

Type RM Length L Ch R = 1 ,1757    ,347,347,347
BEGIN DESCRIPTION:
Mapping XS efc364d3
END DESCRIPTION:
XS GIS Cut Line= 4
      2494208.19     13462418.26      2494177.81     13461973.37
      2494058.45     13461810.61      2493857.47     13461659.34
#Sta/Elev= 30
  4446.5  197.51  4590.1   196.5  4714.4  194.84  4750.5  195.06  4879.5  193.94
    4922  193.51  4928.2   192.1  4936.6  188.11  4942.8  185.96  4952.3  185.37
  4957.5  185.09  4964.8   183.8  4972.1   181.6  4976.1   181.4  4976.4   180.9
  4980.2   180.9  4980.5   181.4  4986.8  183.03    4993  183.59  5001.4  187.41
  5007.6  188.36    5037  189.16  5058.2  188.08  5072.5  186.62  5078.7  186.66
  5108.4  189.32  5129.2  190.26  5172.9  193.75  5208.3  195.21  5345.8  198.61
#Mann= 6 ,-1 , 0
  4446.5     .07       0  4879.5     .12       0  4952.3     .07       0
  4976.1     .05       0  4980.5     .07       0  5058.2     .05       0
Bank Sta=4976.1,4980.5
XS Rating Curve= 0 ,0
Exp/Cntr=0.3,0.1

Type RM Length L Ch R = 1 ,1410    ,914,914,914
BEGIN DESCRIPTION:
Mapping XS f729e7ef
END DESCRIPTION:
XS GIS Cut Line= 4
      2494353.58     13462455.12      2494273.29     13461890.91
       2494301.5     13461521.98       2493948.9     13461331.62
#Sta/Elev= 30
  4226.7  198.91  4273.2  198.21  4580.3  194.14    4651  194.15  4674.1  193.97
    4753  193.37    4792  190.05  4812.5  189.54  4832.6  188.11  4852.7  187.63
  4881.2  188.88  4907.8  187.99  4926.4  187.18  4942.9  185.74    4953  183.96
  4980.8  180.56  4981.1  180.06  4984.9  180.06  4985.2  180.56  5003.1  180.69
  5011.9  184.44  5016.9   189.6  5023.2  191.88  5063.3  192.39  5083.3  191.89
  5207.6  191.94  5338.1  194.18  5435.4   196.2  5514.9  199.04  5567.3  199.99
#Mann= 9 ,-1 , 0
  4226.7     .12       0  4273.2    .035       0    4651     .07       0
  4674.1     .12       0  4907.8     .05       0  4926.4     .12       0
  4980.8     .05       0  4985.2     .12       0  5338.1     .05       0
Bank Sta=4980.8,4985.2
XS Rating Curve= 0 ,0
Exp/Cntr=0.3,0.1

Type RM Length L Ch R = 1 ,496     ,339,339,339
BEGIN DESCRIPTION:
Mapping XS 5419abbe
END DESCRIPTION:
XS GIS Cut Line= 5
      2494557.59     13462398.68      2494670.43     13461684.75
      2494622.68     13461461.22      2494286.31     13461183.44
      2494114.88     13461150.89
#Sta/Elev= 30
  4164.6  199.31  4745.7  191.38  4836.5  190.33  4856.8  189.69  4866.9  189.95
  4883.4  188.38  4890.8  188.38  4907.6  186.01    4928  184.38  4958.7  184.86
  4979.2  182.63  4984.7  181.46  4989.8  182.42  5007.6  176.48  5007.9  175.98
  5011.7  175.98    5012  176.48  5020.1  178.63  5029.1  186.62  5034.2  184.89
  5040.5  190.44  5353.2  190.19  5431.3  191.56  5445.7  191.41  5466.5  192.46
  5528.9  192.57  5594.3  193.85  5645.1  195.66  5674.2  195.85  5726.7  197.15
#Mann= 5 ,-1 , 0
  4164.6    .035       0  4745.7     .12       0  5007.6     .05       0
    5012     .12       0  5528.9     .05       0
Bank Sta=5007.6,5012
XS Rating Curve= 0 ,0
Exp/Cntr=0.3,0.1

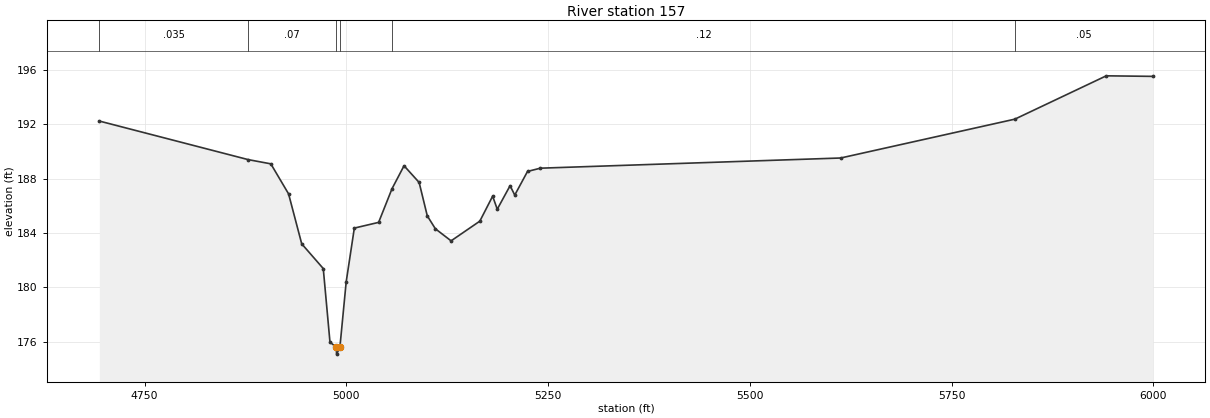
Type RM Length L Ch R = 1 ,157     ,0,0,0
BEGIN DESCRIPTION:
TRIB 2 TO FARMER CREEK 1.0
END DESCRIPTION:
XS GIS Cut Line= 5
      2494810.92     13461898.75      2494939.52     13461656.53
      2494924.33     13461498.11      2494323.21      13461157.4
       2494149.8     13461105.38
#Sta/Elev= 30
  4693.9  192.24  4878.4   189.4  4906.4  189.09  4928.4  186.88  4944.7   183.2
  4971.4  181.38  4979.7  175.97  4987.6  175.58  4987.9  175.08    4992  175.58
  4999.8   180.4  5009.9  184.36    5040  184.78  5056.6  187.26  5071.5  188.95
  5090.2  187.72  5100.3  185.26  5110.3  184.31  5129.8  183.42  5165.4  184.87
  5181.3  186.71    5187  185.75  5202.9  187.48  5208.7  186.79  5224.5  188.53
  5240.4  188.77  5612.6  189.52  5828.4  192.38  5941.7  195.57  5999.3  195.53
#Mann= 6 ,-1 , 0
  4693.9    .035       0  4878.4     .07       0  4987.6     .05       0
    4992     .07       0  5056.6     .12       0  5828.4     .05       0
Bank Sta=4987.6,4992
XS Rating Curve= 0 ,0
Exp/Cntr=0.3,0.1

Chan Stop Cuts=-1
Use User Specified Reach Order=0
Composite Channel Slope=5