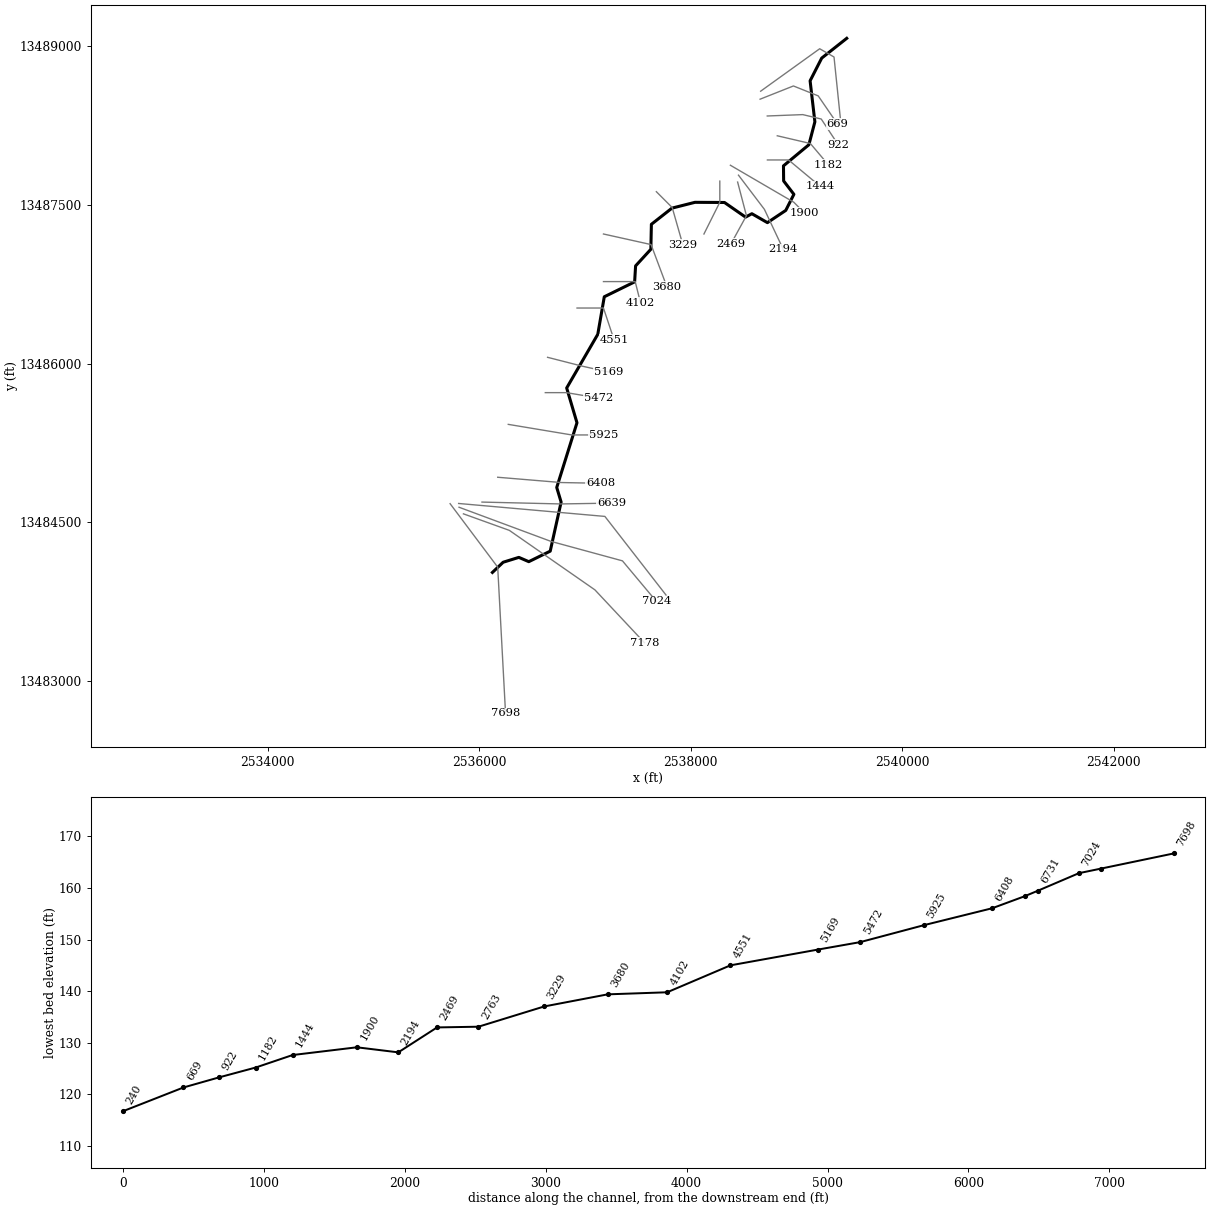
--- TRIB 2 TO HOG THIEF CREEK.prj (project) ---

Proj Title=TRIB 2 TO HOG THIEF CREEK Base Level Engineering
Current Plan=p01
Default Exp/Contr=0.3,0.1
English Units
Geom File=g01
Flow File=f01
Plan File=p01
Y Axis Title=Elevation
X Axis Title(PF)=Main Channel Distance
X Axis Title(XS)=Station
BEGIN DESCRIPTION:
TRIB 2 TO HOG THIEF CREEK
END DESCRIPTION:
DSS Export Rating Curves= 0
DSS Export Rating Curve Sorted= 0
DSS Export Volume Flow Curves= 0
DXF OffsetX= 0
DXF OffsetY= 0
DXF ScaleX= 1
DXF ScaleY= 10

--- TRIB 2 TO HOG THIEF CREEK.p01 (plan) ---

Plan Title=Multiple Run
Short Identifier=Multiple
Geom File=g01
Flow File=f01
Subcritical Flow
K Sum by GR= 0
Std Step Tol= 0.01
Critical Tol= 0.01
Num of Std Step Trials= 20
Max Error Tol= 0.3
Flow Tol Ratio= 0.001
Split Flow NTrial= 30
Split Flow Tol= 0.02
Split Flow Ratio= 0.02
Log Output Level= 0
Friction Slope Method= 1
Unsteady Friction Slope Method= 2
Unsteady Bridges Friction Slope Method= 1
Parabolic Critical Depth
Global Vel Dist=  1 , 1 , 1
Global Log Level= 0
CheckData=True
Encroach Param= -1, 0, 0, 0
BEGIN DESCRIPTION:
Multiple Run
END DESCRIPTION:

--- TRIB 2 TO HOG THIEF CREEK.f01 (steady flow) ---

Flow Title=Multiple
Number of Profiles=7
Profile Names=10-year,25-year,50-year,1pct_min,100-year,1pct_plu,500-year
River Rch & RM= TRIB 2 TO HOG TH,Reach-1,7698
     379     581     755     475     949    1893    1478
River Rch & RM= TRIB 2 TO HOG TH,Reach-1,5925
     499     779    1025     653    1303    2599    2079
River Rch & RM= TRIB 2 TO HOG TH,Reach-1,2194
     680    1084    1445     932    1859    3710    3042
Boundary for River Rch & Prof#=TRIB 2 TO HOG TH,Reach-1,1
Up Type=0
Dn Type=3
Dn Slope=0.005
Boundary for River Rch & Prof#=TRIB 2 TO HOG TH,Reach-1,2
Up Type=0
Dn Type=3
Dn Slope=0.005
Boundary for River Rch & Prof#=TRIB 2 TO HOG TH,Reach-1,3
Up Type=0
Dn Type=3
Dn Slope=0.005
Boundary for River Rch & Prof#=TRIB 2 TO HOG TH,Reach-1,4
Up Type=0
Dn Type=3
Dn Slope=0.005
Boundary for River Rch & Prof#=TRIB 2 TO HOG TH,Reach-1,5
Up Type=0
Dn Type=3
Dn Slope=0.005
Boundary for River Rch & Prof#=TRIB 2 TO HOG TH,Reach-1,6
Up Type=0
Dn Type=3
Dn Slope=0.005
Boundary for River Rch & Prof#=TRIB 2 TO HOG TH,Reach-1,7
Up Type=0
Dn Type=3
Dn Slope=0.005

--- TRIB 2 TO HOG THIEF CREEK.g01 (geometry) ---

Geom Title=Existing Conditions
Program Version=4.10

River Reach=TRIB 2 TO HOG TH,Reach-1
Reach XY= 30
        2536125.       13484025.      2536226.48     13484121.44
      2536375.01     13484167.41      2536468.87     13484126.86
      2536671.49     13484226.25      2536774.61     13484690.28
      2536733.08      13484828.3       2536924.5     13485440.22
      2536827.14     13485769.03      2537121.25     13486276.55
      2537182.73      13486631.5      2537469.64      13486772.3
      2537478.75     13486923.47        2537623.     13487080.68
      2537628.07      13487316.7      2537822.55     13487469.53
      2538040.22     13487524.48      2538319.14     13487522.94
      2538518.45     13487384.58      2538578.23     13487416.76
      2538725.08      13487332.3      2538898.52     13487447.99
       2538975.5     13487600.03      2538878.54     13487726.47
      2538876.97     13487869.32      2539117.18     13488068.81
       2539173.9     13488285.55      2539128.75     13488673.45
      2539238.61     13488888.24        2539475.       13489075.

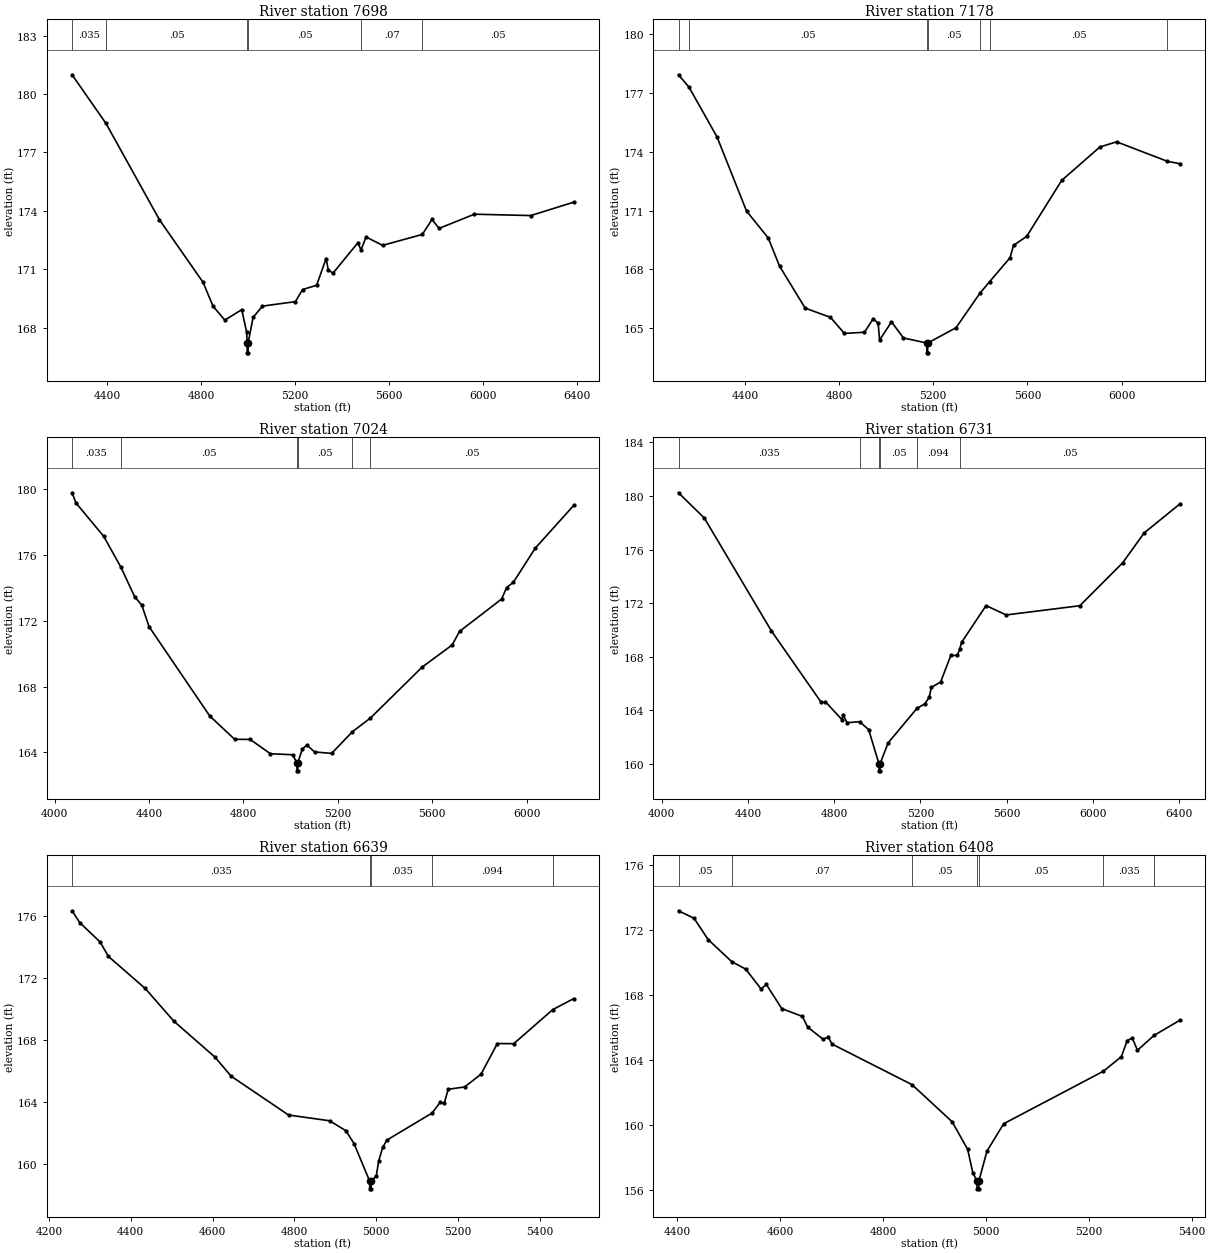
Type RM Length L Ch R = 1 ,7698    ,520,520,520
BEGIN DESCRIPTION:
TRIB 2 TO HOG THIEF CREEK 16.0
END DESCRIPTION:
XS GIS Cut Line= 3
      2535724.97     13484675.04        2536175.       13484075.
      2536249.14     13482692.43
#Sta/Elev= 30
  4250.3  180.99  4394.7  178.49  4622.2  173.54  4807.6  170.33  4850.3   169.1
  4900.3  168.39  4972.2  168.93  4993.1  167.76  4995.2  167.21  4995.5  166.71
    4999  166.71  4999.2  167.21  5020.4  168.53  5060.4  169.11  5200.6  169.34
  5230.7  169.96  5290.8  170.18  5330.8  171.55  5340.8  170.95  5360.9  170.81
  5466.6  172.37  5479.3  171.99  5501.1  172.66  5571.2  172.23  5740.3  172.79
  5781.5  173.56  5811.5   173.1  5961.7  173.83  6202.1  173.76  6384.9  174.45
#Mann= 6 ,-1 , 0
  4250.3    .035       0  4394.7     .05       0  4995.2     .05       0
  4999.2     .05       0  5479.3     .07       0  5740.3     .05       0
Bank Sta=4995.2,4999.2
XS Rating Curve= 0 ,0
Exp/Cntr=0.3,0.1

Type RM Length L Ch R = 1 ,7178    ,154,154,154
BEGIN DESCRIPTION:
Mapping XS 7ebf33c3
END DESCRIPTION:
XS GIS Cut Line= 4
      2535850.99     13484579.03      2536285.02     13484422.77
      2537094.05     13483860.27      2537562.78     13483360.29
#Sta/Elev= 30
  4117.5  177.93  4162.5  177.29  4281.2  174.76  4406.6  170.98  4498.7  169.61
  4546.9  168.17  4655.8  166.03  4763.2  165.56  4822.4  164.74  4907.6   164.8
  4944.2  165.48  4965.7  165.27  4971.8   164.4  5022.5  165.33  5073.1  164.51
  5172.4  164.25  5172.6  163.75  5176.1  163.75  5176.4  164.25  5296.6  165.03
  5397.7  166.78  5439.5  167.38  5526.1   168.6    5541  169.23    5597  169.69
  5745.5  172.54  5908.2  174.25    5979  174.51  6194.2  173.52  6249.5  173.39
#Mann= 7 ,-1 , 0
  4117.5    .035       0  4162.5     .05       0  5172.4     .05       0
  5176.4     .05       0  5397.7    .035       0  5439.5     .05       0
  6194.2     .07       0
Bank Sta=5172.4,5176.4
XS Rating Curve= 0 ,0
Exp/Cntr=0.3,0.1

Type RM Length L Ch R = 1 ,7024    ,293,293,293
BEGIN DESCRIPTION:
Mapping XS 6d054f8f
END DESCRIPTION:
XS GIS Cut Line= 4
      2535809.34     13484641.52      2536677.36     13484319.02
      2537354.47     13484134.58      2537673.91     13483752.63
#Sta/Elev= 30
    4074  179.79  4090.7  179.17  4208.1  177.14  4280.7  175.27  4339.1  173.47
  4369.5  172.95  4400.1  171.65    4657  166.22  4762.5   164.8  4828.5  164.79
  4914.3  163.92  5007.9  163.86  5026.6  163.38  5026.9  162.88  5030.4  162.88
  5030.6  163.38  5049.4   164.2  5068.6  164.45  5101.2  164.03  5173.7  163.94
  5260.9  165.25    5338  166.09  5557.2  169.19    5684  170.53  5715.6  171.36
  5893.9  173.33  5914.7  174.02  5943.3  174.34  6035.7  176.41  6199.7  179.03
#Mann= 6 ,-1 , 0
    4074    .035       0  4280.7     .05       0  5026.6     .05       0
  5030.6     .05       0  5260.9    .035       0    5338     .05       0
Bank Sta=5026.6,5030.6
XS Rating Curve= 0 ,0
Exp/Cntr=0.3,0.1

Type RM Length L Ch R = 1 ,6731    ,92,92,92
BEGIN DESCRIPTION:
Mapping XS 2685f7d7
END DESCRIPTION:
XS GIS Cut Line= 3
      2535805.59     13484677.09      2537188.39     13484554.69
      2537766.06     13483811.75
#Sta/Elev= 30
  4077.3  180.24  4197.2  178.35  4508.4  169.92  4739.3  164.59  4759.4  164.62
  4836.4  163.28  4841.4  163.65  4859.8  163.06  4918.3  163.13  4960.1  162.54
  5008.3  159.96  5008.6  159.46  5012.1  159.46  5012.3  159.96  5050.5  161.55
  5184.4  164.13  5221.2  164.47  5241.2  164.97  5251.3   165.7  5294.2   166.1
  5341.6  168.09  5371.7  168.08  5382.3  168.55  5391.8  169.07  5505.1  171.81
  5598.3  171.11  5940.4   171.8  6139.4  175.01    6239  177.24  6406.6  179.43
#Mann= 6 ,-1 , 0
  4077.3    .035       0  4918.3     .05       0  5008.3     .05       0
  5012.3     .05       0  5184.4    .094       0  5382.3     .05       0
Bank Sta=5008.3,5012.3
XS Rating Curve= 0 ,0
Exp/Cntr=0.3,0.1

Type RM Length L Ch R = 1 ,6639    ,231,231,231
BEGIN DESCRIPTION:
TRIB 2 TO HOG THIEF CREEK 14.0
END DESCRIPTION:
XS GIS Cut Line= 3
      2536026.32     13484690.24      2536769.31     13484672.69
      2537251.75     13484680.34
#Sta/Elev= 30
  4256.8  176.34  4275.5  175.58  4325.5  174.32  4345.5   173.4  4435.5  171.33
  4505.5  169.22  4605.6  166.91  4645.6  165.67  4785.6  163.17  4885.7   162.8
  4925.7  162.16  4945.7  161.32  4983.7  158.91  4983.9  158.41  4987.4  158.41
  4987.7  158.91    5000  159.25  5005.7  160.19  5015.7  161.09  5025.7  161.55
  5136.4   163.3  5155.7  163.98  5165.7  163.92  5175.7  164.83  5215.7  164.98
  5255.7   165.8  5295.7  167.78  5335.7  167.77  5431.2  169.97  5482.5  170.68
#Mann= 5 ,-1 , 0
  4256.8    .035       0  4983.7    .035       0  4987.7    .035       0
  5136.4    .094       0  5431.2    .035       0
Bank Sta=4983.7,4987.7
XS Rating Curve= 0 ,0
Exp/Cntr=0.3,0.1

Type RM Length L Ch R = 1 ,6408    ,483,483,483
BEGIN DESCRIPTION:
TRIB 2 TO HOG THIEF CREEK 13.0
END DESCRIPTION:
XS GIS Cut Line= 3
      2536174.98       13484925.        2536775.       13484875.
      2537148.14      13484867.9
#Sta/Elev= 30
  4402.5  173.16  4432.6   172.7  4460.2  171.39  4505.8  170.04    4533  169.58
  4563.1  168.35  4573.1  168.64  4603.2  167.15  4643.3  166.67  4653.4  166.02
  4683.5  165.27  4693.5   165.4    4701  164.97  4856.4  162.48  4934.4   160.2
  4964.5  158.51  4974.5  157.07  4982.5  156.58  4982.8  156.08  4986.3  156.08
  4986.5  156.58  5002.1   158.4  5034.6  160.08  5228.2   163.3  5263.4   164.2
  5274.6  165.19  5284.6  165.34  5294.6  164.59  5326.6   165.5  5377.8  166.45
#Mann= 7 ,-1 , 0
  4402.5     .05       0  4505.8     .07       0  4856.4     .05       0
  4982.5     .05       0  4986.5     .05       0  5228.2    .035       0
  5326.6     .05       0
Bank Sta=4982.5,4986.5
XS Rating Curve= 0 ,0
Exp/Cntr=0.3,0.1

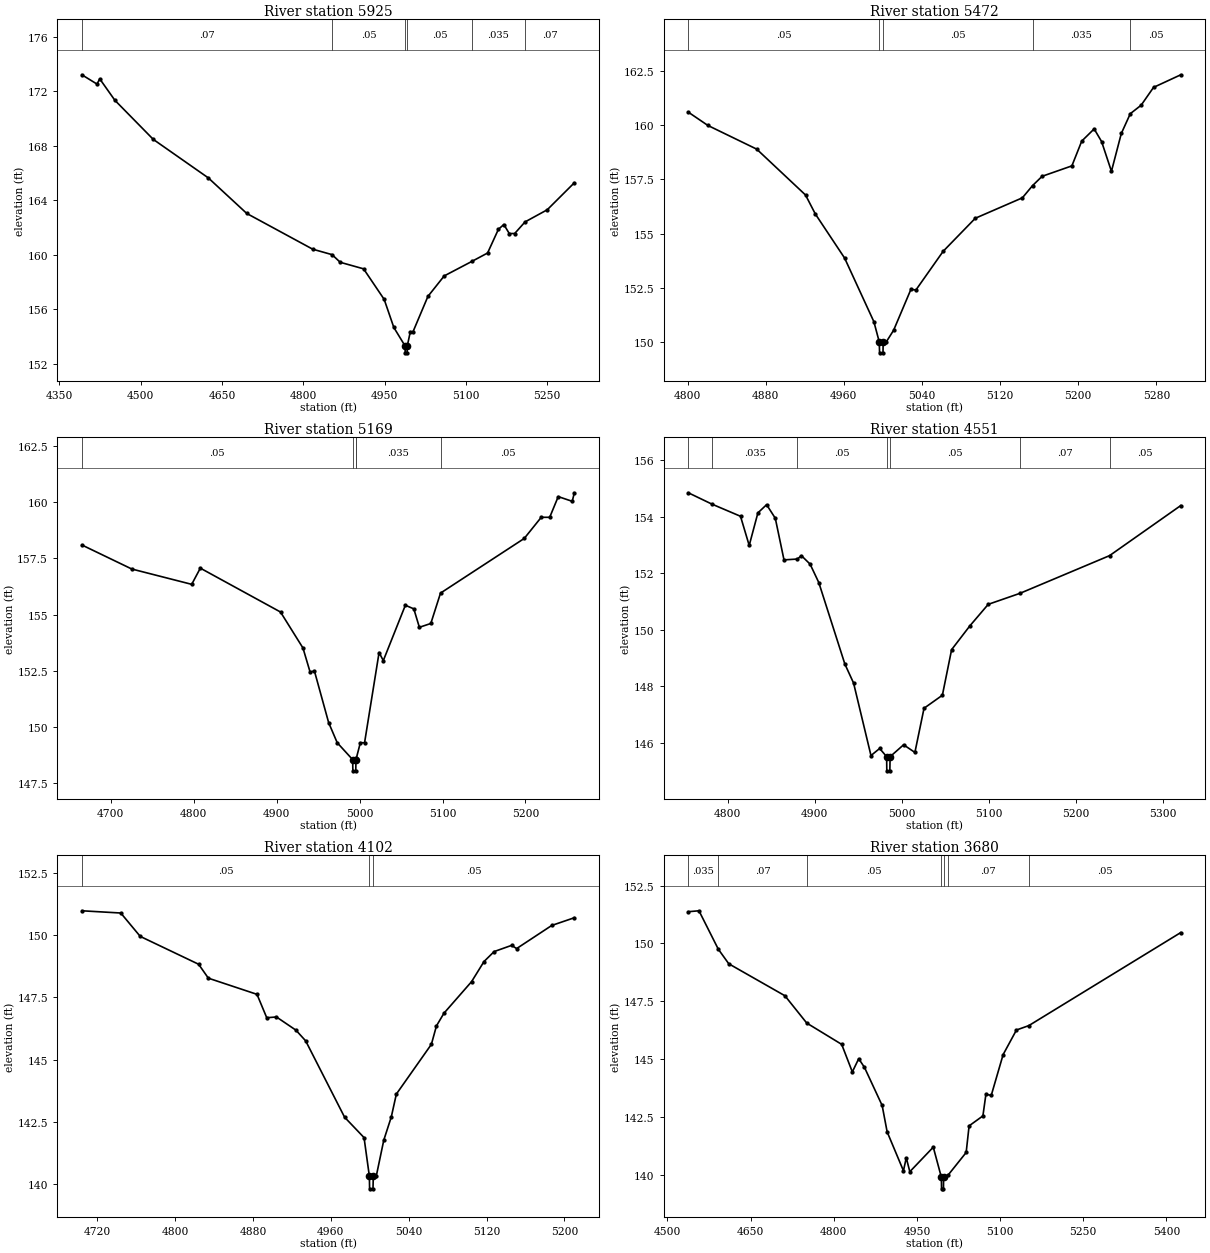
Type RM Length L Ch R = 1 ,5925    ,453,453,453
BEGIN DESCRIPTION:
TRIB 2 TO HOG THIEF CREEK 12.0
END DESCRIPTION:
XS GIS Cut Line= 3
      2536274.98       13485425.        2536875.       13485325.
        2537175.       13485325.
#Sta/Elev= 30
  4391.7   173.2  4419.6  172.52  4424.7   172.9  4452.6  171.33  4523.5  168.46
  4624.9  165.64  4695.9  163.03  4817.5  160.41  4853.2  160.01  4868.2  159.45
  4911.3  158.97  4949.3  156.73  4967.1  154.67  4987.9  153.31  4988.1  152.81
  4991.6  152.81  4991.9  153.31  4997.5  154.36  5002.5  154.36    5030  156.95
    5060  158.45  5110.8  159.51    5140  160.13    5160  161.87    5170  162.22
    5180  161.56    5190  161.56  5209.1  162.41    5250   163.3    5300  165.28
#Mann= 6 ,-1 , 0
  4391.7     .07       0  4853.2     .05       0  4987.9     .05       0
  4991.9     .05       0  5110.8    .035       0  5209.1     .07       0
Bank Sta=4987.9,4991.9
XS Rating Curve= 0 ,0
Exp/Cntr=0.3,0.1

Type RM Length L Ch R = 1 ,5472    ,303,303,303
BEGIN DESCRIPTION:
TRIB 2 TO HOG THIEF CREEK 11.0
END DESCRIPTION:
XS GIS Cut Line= 3
      2536624.97       13485725.        2536825.       13485725.
      2537125.03     13485674.99
#Sta/Elev= 30
  4800.8  160.59  4820.8  159.98  4870.8  158.89  4920.8  156.78  4930.8  155.91
  4960.8  153.88  4990.8  150.95  4996.3  150.02  4996.6  149.52  5000.1  149.52
  5000.3  150.02  5003.4  150.02    5011  150.56  5028.7  152.44  5033.8  152.41
  5061.7  154.19  5094.6  155.71  5142.8  156.65  5153.2  157.21    5163  157.64
  5193.5  158.12  5203.6  159.26  5216.3  159.82  5223.9  159.24    5234  157.87
  5244.1  159.61  5253.3  160.52  5264.4  160.91  5277.1  161.73    5305  162.31
#Mann= 5 ,-1 , 0
  4800.8     .05       0  4996.3     .05       0  5000.3     .05       0
  5153.2    .035       0  5253.3     .05       0
Bank Sta=4996.3,5000.3
XS Rating Curve= 0 ,0
Exp/Cntr=0.3,0.1

Type RM Length L Ch R = 1 ,5169    ,618,618,618
BEGIN DESCRIPTION:
Mapping XS fd75b4fd
END DESCRIPTION:
XS GIS Cut Line= 3
      2536646.59     13486058.97      2536974.02     13485975.37
      2537223.99     13485919.82
#Sta/Elev= 30
    4665   158.1  4725.3  157.03  4797.5  156.35  4807.9  157.07  4904.6  155.12
  4931.7  153.52  4940.3  152.45  4945.5   152.5  4962.7   150.2    4973  149.31
  4991.6  148.56  4991.9  148.06  4995.4  148.06  4995.6  148.56  4996.2  148.64
  5000.9  149.31    5006  149.31  5023.5  153.32  5028.6  152.96  5055.2  155.42
  5065.4  155.26  5072.1  154.44  5085.9  154.61  5097.6  155.96  5198.6  158.39
  5219.1  159.33  5229.3  159.33  5239.6  160.25  5256.5  160.04    5259  160.42
#Mann= 5 ,-1 , 0
    4665     .05       0  4991.6    .035       0  4995.6     .05       0
  4996.2    .035       0  5097.6     .05       0
Bank Sta=4991.6,4995.6
XS Rating Curve= 0 ,0
Exp/Cntr=0.3,0.1

Type RM Length L Ch R = 1 ,4551    ,449,449,449
BEGIN DESCRIPTION:
TRIB 2 TO HOG THIEF CREEK 9.0
END DESCRIPTION:
XS GIS Cut Line= 3
      2536925.04       13486525.        2537175.       13486525.
        2537275.     13486224.99
#Sta/Elev= 30
  4754.7  154.84  4781.8  154.44  4814.7  154.01  4824.7  152.98  4834.7  154.13
  4844.7  154.42  4854.7  153.94  4864.7  152.47  4880.1   152.5  4884.7  152.62
  4894.7  152.32  4904.7  151.67  4934.7  148.79  4944.7  148.12  4964.7  145.56
  4974.7  145.81  4982.7  145.52  4982.9  145.02  4986.4  145.02  4986.7  145.52
  5002.2  145.94  5015.2  145.67  5025.7  147.23  5046.8  147.69  5057.4   149.3
  5078.4  150.14  5099.5   150.9  5136.1  151.29    5239  152.62  5320.9  154.39
#Mann= 7 ,-1 , 0
  4754.7     .05       0  4781.8    .035       0  4880.1     .05       0
  4982.7     .05       0  4986.7     .05       0  5136.1     .07       0
    5239     .05       0
Bank Sta=4982.7,4986.7
XS Rating Curve= 0 ,0
Exp/Cntr=0.3,0.1

Type RM Length L Ch R = 1 ,4102    ,422,422,422
BEGIN DESCRIPTION:
TRIB 2 TO HOG THIEF CREEK 8.0
END DESCRIPTION:
XS GIS Cut Line= 3
      2537175.04       13486775.        2537475.       13486775.
        2537525.     13486575.01
#Sta/Elev= 30
  4704.1  150.98  4744.1  150.89  4764.1  149.95  4824.1  148.83  4834.1  148.27
  4884.1  147.62  4894.1  146.68  4904.1  146.71  4924.1  146.18  4934.1  145.75
  4974.1  142.68  4994.1  141.86  4999.6   140.3  4999.8   139.8  5003.3   139.8
  5003.6   140.3  5006.6   140.3  5014.4  141.76  5022.1  142.69  5027.3  143.61
  5063.3  145.61  5068.5  146.35  5076.2  146.86  5104.6  148.13  5117.4  148.94
  5127.8  149.34  5145.8  149.59  5150.9  149.46    5187  150.39  5210.2   150.7
#Mann= 3 ,-1 , 0
  4704.1     .05       0  4999.6     .05       0  5003.6     .05       0
Bank Sta=4999.6,5003.6
XS Rating Curve= 0 ,0
Exp/Cntr=0.3,0.1

Type RM Length L Ch R = 1 ,3680    ,451,451,451
BEGIN DESCRIPTION:
TRIB 2 TO HOG THIEF CREEK 7.0
END DESCRIPTION:
XS GIS Cut Line= 3
      2537174.98     13487225.01        2537625.       13487125.
        2537775.       13486725.
#Sta/Elev= 30
  4537.7  151.37  4556.9  151.41  4591.8  149.75  4610.7  149.12  4711.9  147.74
  4751.3  146.56  4814.3  145.64  4833.5  144.45    4845  145.02  4855.3  144.65
  4887.3     143  4896.3  141.86  4925.7  140.18  4930.8  140.74  4937.2  140.14
  4979.5   141.2  4994.1   139.9  4994.4   139.4  4997.9   139.4  4998.1   139.9
  5006.1  139.99  5038.8  140.97  5044.1  142.12    5069  142.55  5074.4  143.48
  5084.1  143.44  5105.5   145.2  5129.5  146.26  5151.8  146.45  5425.9  150.47
#Mann= 7 ,-1 , 0
  4537.7    .035       0  4591.8     .07       0  4751.3     .05       0
  4994.1     .05       0  4998.1     .05       0  5006.1     .07       0
  5151.8     .05       0
Bank Sta=4994.1,4998.1
XS Rating Curve= 0 ,0
Exp/Cntr=0.3,0.1

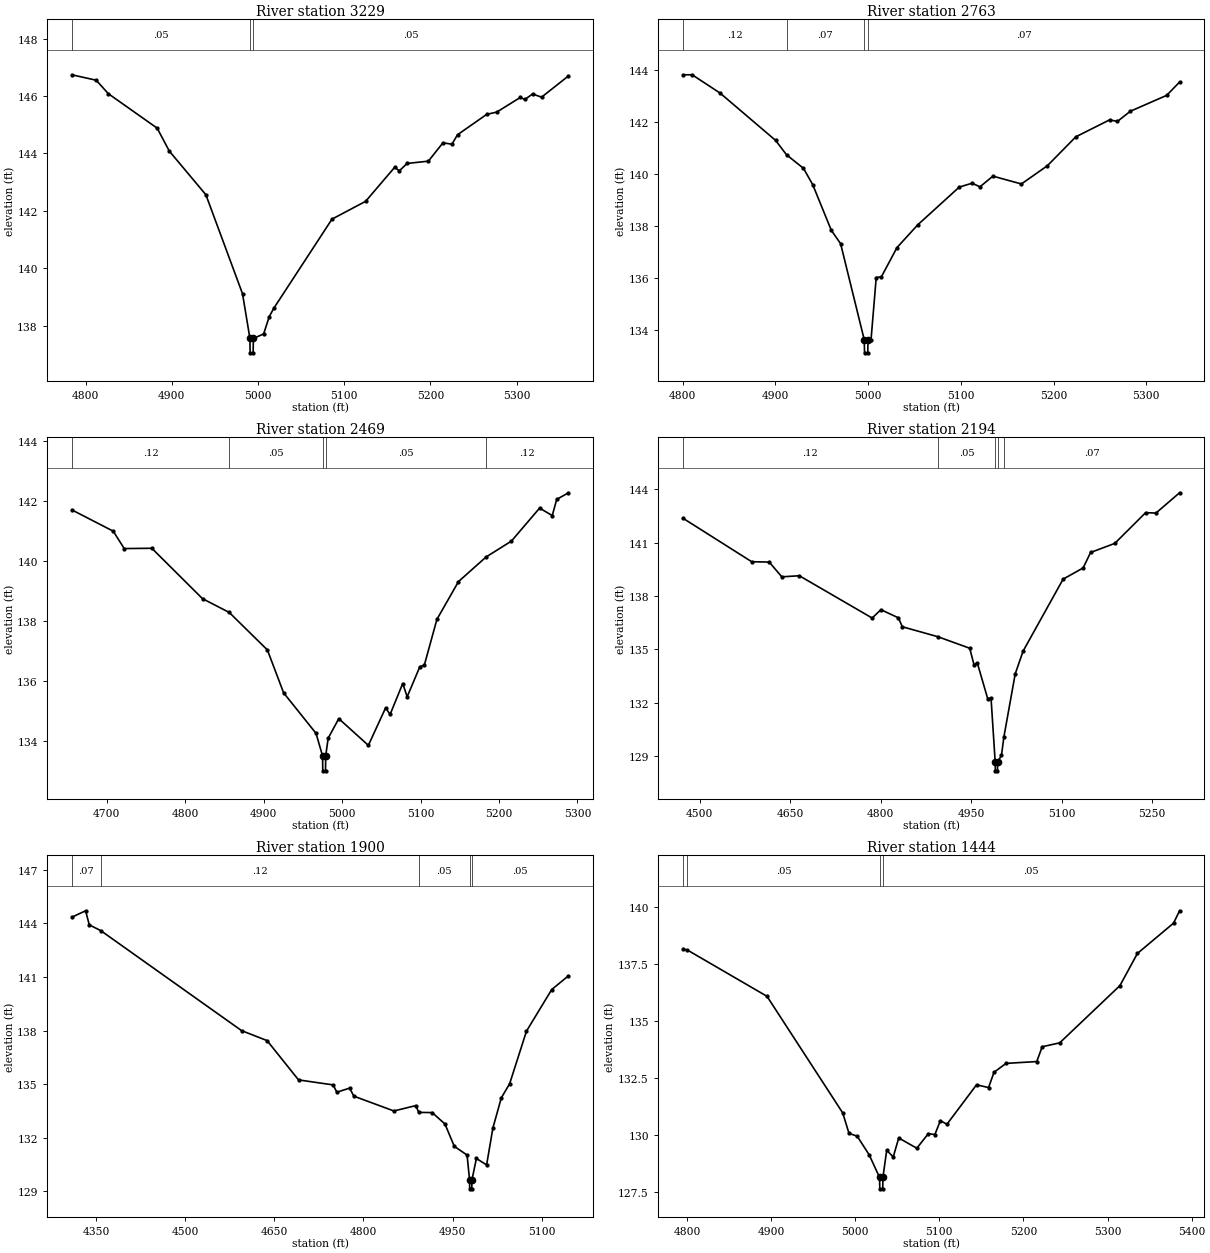
Type RM Length L Ch R = 1 ,3229    ,466,466,466
BEGIN DESCRIPTION:
TRIB 2 TO HOG THIEF CREEK 6.0
END DESCRIPTION:
XS GIS Cut Line= 3
      2537675.02     13487624.98        2537825.       13487475.
        2537925.     13487125.02
#Sta/Elev= 30
    4784  146.74  4812.3  146.55  4826.4  146.08    4883  144.88  4897.1  144.08
  4939.5  142.56    4982  139.11  4990.6  137.55  4990.8  137.05  4994.3  137.05
  4994.6  137.55  5006.5  137.71    5013  138.31  5018.2   138.6  5085.8  141.71
  5124.8  142.33  5158.6  143.52  5163.8  143.39  5172.9  143.65  5197.6  143.73
  5214.5  144.37  5224.9  144.32  5231.4  144.65  5265.2  145.36  5276.9  145.44
  5304.2  145.95  5309.4  145.88  5318.5  146.07  5328.9  145.96  5360.1   146.7
#Mann= 3 ,-1 , 0
    4784     .05       0  4990.6     .05       0  4994.6     .05       0
Bank Sta=4990.6,4994.6
XS Rating Curve= 0 ,0
Exp/Cntr=0.3,0.1

Type RM Length L Ch R = 1 ,2763    ,294,294,294
BEGIN DESCRIPTION:
TRIB 2 TO HOG THIEF CREEK 5.0
END DESCRIPTION:
XS GIS Cut Line= 3
        2538275.     13487725.04        2538275.       13487525.
      2538125.02     13487225.04
#Sta/Elev= 30
  4800.4   143.8  4810.4   143.8  4840.4   143.1  4900.4  141.28  4912.1  140.73
  4930.4  140.21  4940.4  139.58  4960.4  137.83  4970.4  137.32  4995.9  133.63
  4996.2  133.13  4999.7  133.13  4999.9  133.63  5003.2  133.63  5008.8  136.02
  5014.4  136.05  5031.2  137.17  5053.5  138.04  5098.3  139.49  5112.2  139.64
  5120.6   139.5  5134.6  139.91  5165.3  139.61  5193.3  140.31    5224  141.42
  5260.4  142.07  5268.8  142.01  5282.7   142.4  5321.9  143.01  5335.8  143.52
#Mann= 4 ,-1 , 0
  4800.4     .12       0  4912.1     .07       0  4995.9     .05       0
  4999.9     .07       0
Bank Sta=4995.9,4999.9
XS Rating Curve= 0 ,0
Exp/Cntr=0.3,0.1

Type RM Length L Ch R = 1 ,2469    ,275,275,275
BEGIN DESCRIPTION:
Mapping XS 3828f6ee
END DESCRIPTION:
XS GIS Cut Line= 3
      2538443.43     13487716.12      2538526.76     13487398.43
      2538380.33     13487131.26
#Sta/Elev= 30
  4655.5  141.69  4708.3  140.98  4722.3   140.4  4757.5  140.41  4822.1  138.73
  4856.2  138.27  4904.8  137.02  4925.5  135.59  4966.8  134.24  4975.1  133.49
  4975.4  132.99  4978.9  132.99  4979.1  133.49  4982.3  134.08  4995.8  134.73
  5033.5  133.84  5055.5  135.09  5061.2  134.87  5077.3   135.9    5083  135.46
  5099.1  136.46  5104.8  136.51  5120.9  138.04  5148.4   139.3  5183.6  140.12
  5215.9  140.65  5251.8  141.75  5267.9   141.5  5273.6  142.04  5288.6  142.26
#Mann= 5 ,-1 , 0
  4655.5     .12       0  4856.2     .05       0  4975.1     .05       0
  4979.1     .05       0  5183.6     .12       0
Bank Sta=4975.1,4979.1
XS Rating Curve= 0 ,0
Exp/Cntr=0.3,0.1

Type RM Length L Ch R = 1 ,2194    ,294,294,294
BEGIN DESCRIPTION:
Mapping XS 52a7ab9e
END DESCRIPTION:
XS GIS Cut Line= 3
      2538451.51     13487781.32      2538696.71       13487458.
      2538874.66     13487080.41
#Sta/Elev= 30
  4472.4  142.38  4586.4  139.93  4615.5  139.91  4636.3  139.08  4665.4  139.14
  4786.1  136.76  4800.6  137.23  4829.7  136.77    4836  136.27  4894.9  135.71
  4947.8  135.06  4954.8  134.14  4960.3  134.24  4977.6  132.22  4983.1  132.26
    4990  128.66  4990.3  128.16  4993.8  128.16    4994  128.66  5000.4  129.03
  5004.5  130.08  5023.2  133.62  5036.3   134.9  5102.6  138.95  5135.8  139.58
  5148.1  140.45  5188.2  140.96  5239.3  142.69  5256.5  142.67  5295.6  143.81
#Mann= 5 ,-1 , 0
  4472.4     .12       0  4894.9     .05       0    4990     .05       0
    4994     .05       0  5004.5     .07       0
Bank Sta=4990,4994
XS Rating Curve= 0 ,0
Exp/Cntr=0.3,0.1

Type RM Length L Ch R = 1 ,1900    ,456,456,456
BEGIN DESCRIPTION:
TRIB 2 TO HOG THIEF CREEK 3.0
END DESCRIPTION:
XS GIS Cut Line= 3
        2538375.       13487875.        2538975.       13487525.
      2539074.97     13487425.03
#Sta/Elev= 30
  4309.2  144.35  4332.4  144.71  4338.6  143.92  4357.9   143.6  4594.9     138
  4637.9  137.44  4690.8  135.24  4749.1  134.96  4755.3  134.55  4776.8  134.78
  4783.9  134.33  4851.3   133.5  4888.1   133.8  4893.2  133.42  4915.8  133.41
  4937.3  132.77    4953  131.52  4974.5  131.03  4978.7  129.64  4978.9  129.14
  4982.4  129.14  4982.7  129.64  4990.2  130.84  5007.4  130.48    5018  132.55
  5032.1  134.23  5046.2  135.03  5074.5  137.97    5117   140.3  5145.2  141.07
#Mann= 5 ,-1 , 0
  4309.2     .07       0  4357.9     .12       0  4893.2     .05       0
  4978.7     .05       0  4982.7     .05       0
Bank Sta=4978.7,4982.7
XS Rating Curve= 0 ,0
Exp/Cntr=0.3,0.1

Type RM Length L Ch R = 1 ,1444    ,262,262,262
BEGIN DESCRIPTION:
TRIB 2 TO HOG THIEF CREEK 2.0
END DESCRIPTION:
XS GIS Cut Line= 3
      2538724.98       13487925.        2538925.       13487925.
      2539224.97     13487675.02
#Sta/Elev= 30
  4795.1  138.14  4800.4  138.11  4895.1  136.08  4985.1  130.97  4992.6  130.07
  5002.3  129.95  5016.6  129.13  5028.9  128.14  5029.2  127.64  5032.7  127.64
  5032.9  128.14  5037.4  129.33  5045.2  129.04  5051.7  129.87  5073.2  129.42
  5086.9  130.06  5094.7  130.02  5101.2  130.63    5109  130.47  5144.2   132.2
  5158.5  132.08    5165  132.75  5179.3  133.14  5215.8  133.22  5222.3  133.87
  5243.1  134.04  5314.7  136.55  5335.5  137.96  5378.5  139.29  5385.6  139.83
#Mann= 4 ,-1 , 0
  4795.1     .07       0  4800.4     .05       0  5028.9     .05       0
  5032.9     .05       0
Bank Sta=5028.9,5032.9
XS Rating Curve= 0 ,0
Exp/Cntr=0.3,0.1

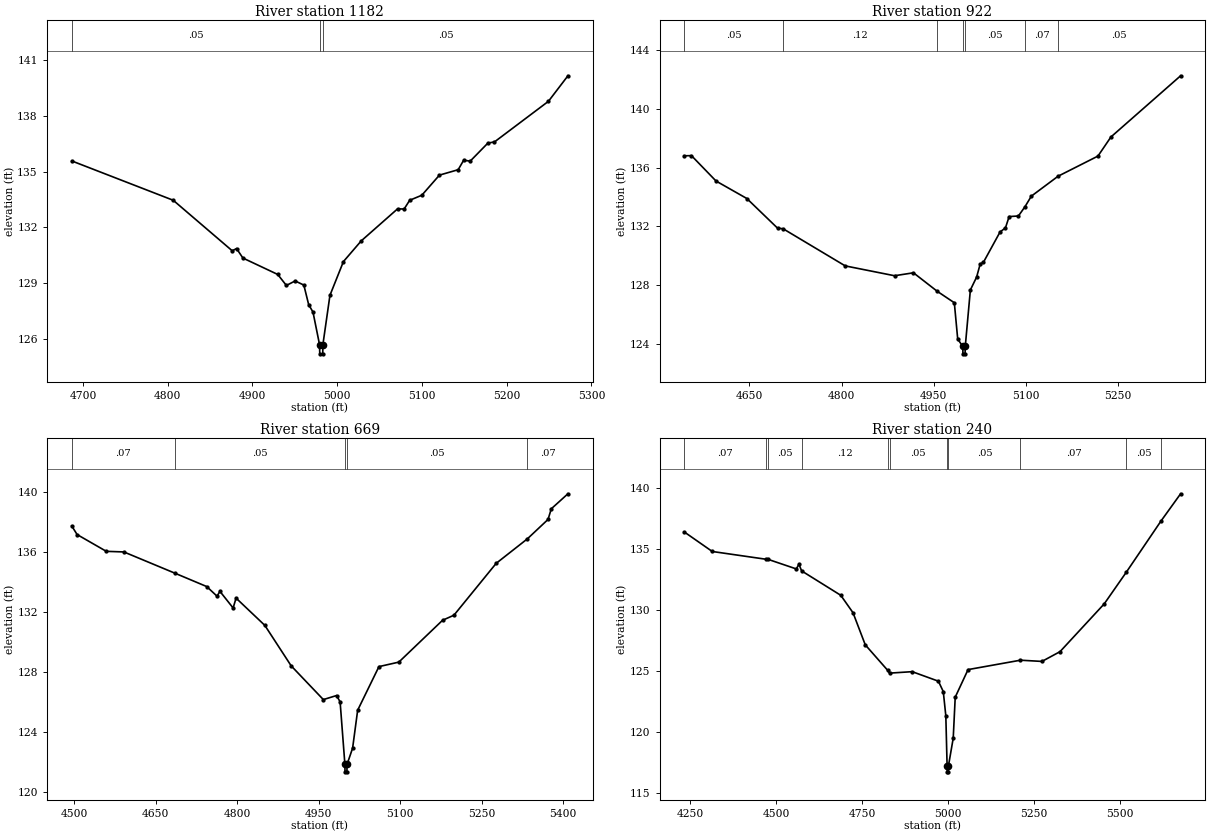
Type RM Length L Ch R = 1 ,1182    ,260,260,260
BEGIN DESCRIPTION:
Mapping XS 0cf86e47
END DESCRIPTION:
XS GIS Cut Line= 3
      2538818.39     13488153.65      2539130.93     13488080.73
      2539301.75     13487878.84
#Sta/Elev= 30
  4686.9  135.57  4806.6  133.46  4876.2  130.75  4881.3  130.87  4888.8  130.36
  4929.9  129.48  4940.1  128.89  4950.4  129.13  4960.7  128.91  4966.4  127.86
  4971.5  127.46  4979.2  125.72  4979.5  125.22    4983  125.22  4983.2  125.72
  4991.5  128.36  5007.4  130.17  5028.4  131.28  5071.3     133    5079  132.99
  5085.6  133.46  5099.9  133.73  5120.7  134.81  5142.8   135.1  5149.3  135.61
    5157  135.56  5177.9  136.53  5185.6  136.59  5249.3  138.77  5272.3  140.14
#Mann= 3 ,-1 , 0
  4686.9     .05       0  4979.2     .05       0  4983.2     .05       0
Bank Sta=4979.2,4983.2
XS Rating Curve= 0 ,0
Exp/Cntr=0.3,0.1

Type RM Length L Ch R = 1 ,922     ,253,253,253
BEGIN DESCRIPTION:
Mapping XS 1eca423c
END DESCRIPTION:
XS GIS Cut Line= 4
      2538723.61     13488340.81      2539059.56     13488353.83
      2539234.04     13488312.17      2539394.66     13488068.65
#Sta/Elev= 30
  4544.3   136.8  4555.7  136.81  4595.7  135.08  4645.8  133.89  4695.8  131.87
  4704.8  131.83  4805.9   129.3  4886.1  128.63  4916.9  128.83  4955.6  127.57
  4983.4  126.79  4988.9  124.32  4997.2  123.81  4997.4  123.31  5000.9  123.31
  5001.2  123.81  5009.5  127.66  5019.7  128.54  5025.5  129.43  5030.7  129.54
  5057.8  131.61  5066.6  131.89  5072.6  132.66  5087.7   132.7  5098.5  133.34
  5108.7  134.05  5152.3  135.41  5217.1  136.78  5238.2  138.08  5351.6  142.25
#Mann= 7 ,-1 , 0
  4544.3     .05       0  4704.8     .12       0  4955.6     .05       0
  4997.2     .05       0  5001.2     .05       0  5098.5     .07       0
  5152.3     .05       0
Bank Sta=4997.2,5001.2
XS Rating Curve= 0 ,0
Exp/Cntr=0.3,0.1

Type RM Length L Ch R = 1 ,669     ,429,429,429
BEGIN DESCRIPTION:
Mapping XS cebc7b53
END DESCRIPTION:
XS GIS Cut Line= 4
      2538655.87     13488499.65      2538971.02     13488624.67
      2539205.39     13488530.92      2539387.67     13488265.32
#Sta/Elev= 30
  4495.2  137.75    4505  137.18  4558.8  136.06  4591.1  136.02  4684.6  134.61
  4743.7  133.71  4762.6  133.07    4768  133.39  4792.3  132.28  4797.7  132.94
  4850.7  131.12  4899.2  128.42  4958.4  126.17  4982.7  126.44  4989.3  126.02
  4998.1  121.85  4998.3  121.35  5001.8  121.35  5002.1  121.85  5012.3  122.93
  5021.6  125.46  5060.8  128.37  5097.4  128.67  5177.9  131.46  5198.9   131.8
  5276.7  135.26    5334  136.89  5372.2  138.19  5378.2   138.9  5408.8   139.9
#Mann= 5 ,-1 , 0
  4495.2     .07       0  4684.6     .05       0  4998.1     .05       0
  5002.1     .05       0    5334     .07       0
Bank Sta=4998.1,5002.1
XS Rating Curve= 0 ,0
Exp/Cntr=0.3,0.1

Type RM Length L Ch R = 1 ,240     ,0,0,0
BEGIN DESCRIPTION:
TRIB 2 TO HOG THIEF CREEK 1.0
END DESCRIPTION:
XS GIS Cut Line= 4
      2538661.12     13488575.18      2539219.47     13488976.56
      2539354.88     13488898.43      2539416.33     13488304.38
#Sta/Elev= 30
  4234.4   136.4  4315.2  134.81  4472.3  134.17  4476.8  134.17  4559.4  133.38
  4566.9  133.77  4574.7  133.22  4688.4  131.22    4724  129.79  4759.6  127.16
  4824.4  125.08    4830  124.84  4895.9  124.96    4972  124.18  4986.2  123.33
  4993.6  121.34  4997.3  117.25  4997.6  116.75  5001.1  116.75  5001.3  117.25
  5015.1  119.51  5020.9  122.87  5058.2  125.13  5210.4   125.9  5272.8   125.8
  5325.3   126.6  5453.8  130.52  5518.3  133.13  5618.7  137.31  5675.6  139.54
#Mann= 11 ,-1 , 0
  4234.4     .07       0  4472.3     .12       0  4476.8     .05       0
  4574.7     .12       0  4824.4     .07       0    4830     .05       0
  4997.3     .05       0  5001.3     .05       0  5210.4     .07       0
  5518.3     .05       0  5618.7     .07       0
Bank Sta=4997.3,5001.3
XS Rating Curve= 0 ,0
Exp/Cntr=0.3,0.1

Chan Stop Cuts=-1
Use User Specified Reach Order=0
Composite Channel Slope=5