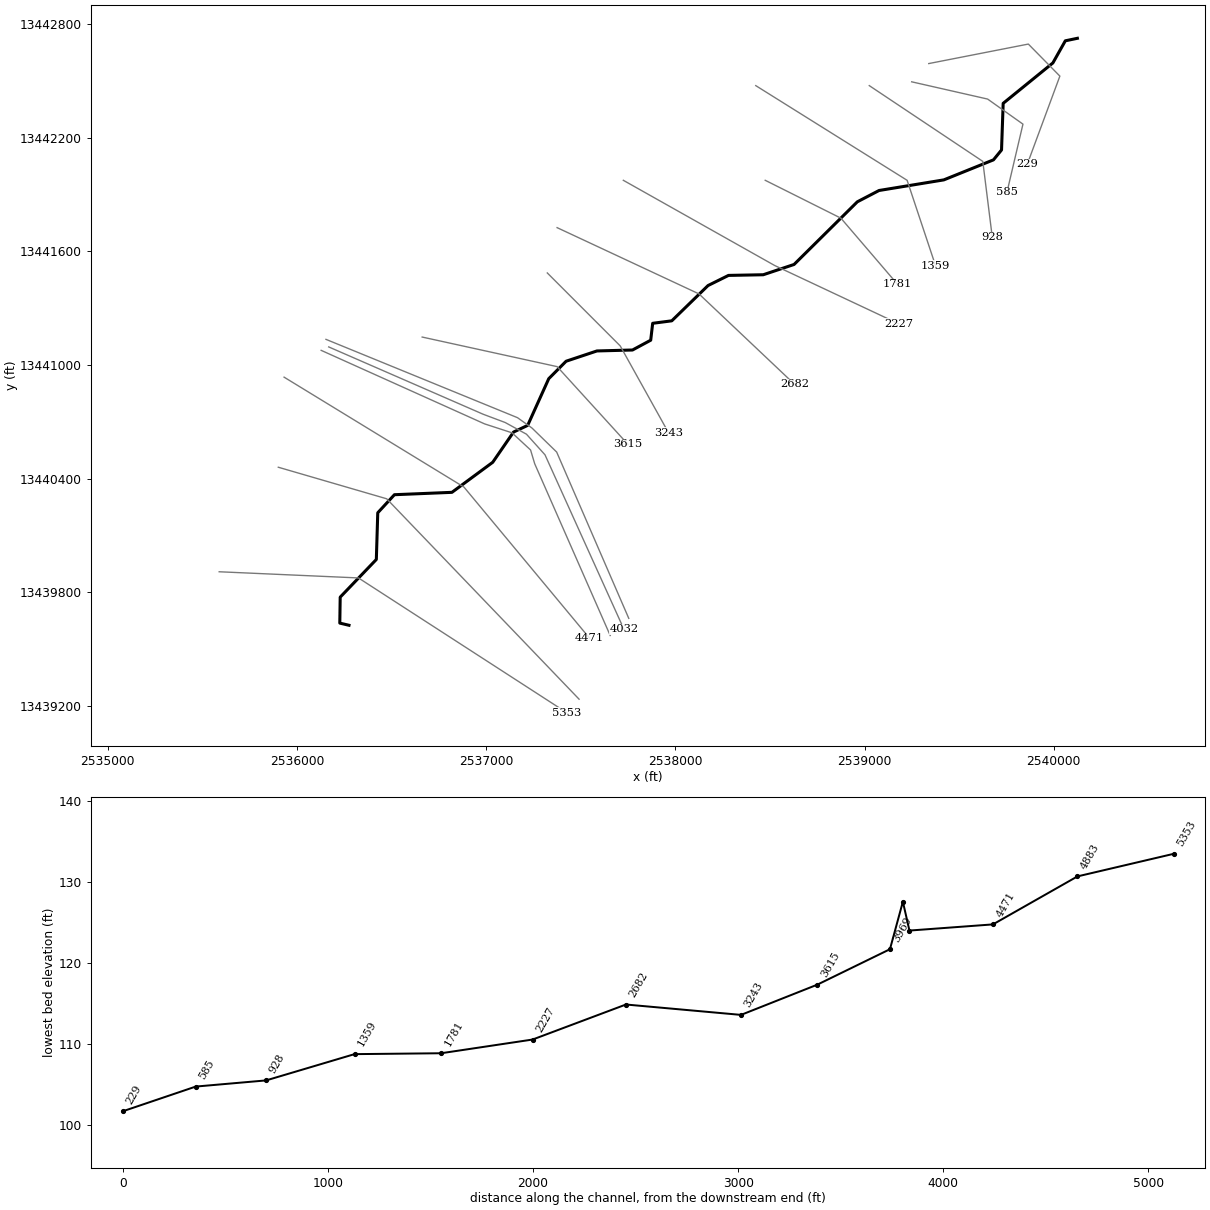
--- TRIB 2 TO PAYTON BRANCH.prj (project) ---

Proj Title=TRIB 2 TO PAYTON BRANCH Base Level Engineering
Current Plan=p01
Default Exp/Contr=0.3,0.1
English Units
Geom File=g01
Flow File=f01
Plan File=p01
Y Axis Title=Elevation
X Axis Title(PF)=Main Channel Distance
X Axis Title(XS)=Station
BEGIN DESCRIPTION:
TRIB 2 TO PAYTON BRANCH
END DESCRIPTION:
DSS Export Rating Curves= 0
DSS Export Rating Curve Sorted= 0
DSS Export Volume Flow Curves= 0
DXF OffsetX= 0
DXF OffsetY= 0
DXF ScaleX= 1
DXF ScaleY= 10

--- TRIB 2 TO PAYTON BRANCH.p01 (plan) ---

Plan Title=Multiple Run
Short Identifier=Multiple
Geom File=g01
Flow File=f01
Subcritical Flow
K Sum by GR= 0
Std Step Tol= 0.01
Critical Tol= 0.01
Num of Std Step Trials= 20
Max Error Tol= 0.3
Flow Tol Ratio= 0.001
Split Flow NTrial= 30
Split Flow Tol= 0.02
Split Flow Ratio= 0.02
Log Output Level= 0
Friction Slope Method= 1
Unsteady Friction Slope Method= 2
Unsteady Bridges Friction Slope Method= 1
Parabolic Critical Depth
Global Vel Dist=  1 , 1 , 1
Global Log Level= 0
CheckData=True
Encroach Param= -1, 0, 0, 0
BEGIN DESCRIPTION:
Multiple Run
END DESCRIPTION:

--- TRIB 2 TO PAYTON BRANCH.f01 (steady flow) ---

Flow Title=Multiple
Number of Profiles=7
Profile Names=10-year,25-year,50-year,1pct_min,100-year,1pct_plu,500-year
River Rch & RM= TRIB 2 TO PAYTON,Reach-1,5353
     476     732     950     596    1189    2372    1842
River Rch & RM= TRIB 2 TO PAYTON,Reach-1,3243
     569     888    1165     739    1475    2943    2337
River Rch & RM= TRIB 2 TO PAYTON,Reach-1,2227
     659    1033    1359     864    1725    3441    2746
Boundary for River Rch & Prof#=TRIB 2 TO PAYTON,Reach-1,1
Up Type=0
Dn Type=3
Dn Slope=0.005
Boundary for River Rch & Prof#=TRIB 2 TO PAYTON,Reach-1,2
Up Type=0
Dn Type=3
Dn Slope=0.005
Boundary for River Rch & Prof#=TRIB 2 TO PAYTON,Reach-1,3
Up Type=0
Dn Type=3
Dn Slope=0.005
Boundary for River Rch & Prof#=TRIB 2 TO PAYTON,Reach-1,4
Up Type=0
Dn Type=3
Dn Slope=0.005
Boundary for River Rch & Prof#=TRIB 2 TO PAYTON,Reach-1,5
Up Type=0
Dn Type=3
Dn Slope=0.005
Boundary for River Rch & Prof#=TRIB 2 TO PAYTON,Reach-1,6
Up Type=0
Dn Type=3
Dn Slope=0.005
Boundary for River Rch & Prof#=TRIB 2 TO PAYTON,Reach-1,7
Up Type=0
Dn Type=3
Dn Slope=0.005

--- TRIB 2 TO PAYTON BRANCH.g01 (geometry) ---

Geom Title=Existing Conditions
Program Version=4.10

River Reach=TRIB 2 TO PAYTON,Reach-1
Reach XY= 30
        2536275.       13439625.      2536226.41     13439636.44
      2536228.52     13439773.53      2536419.54     13439972.55
      2536427.05     13440219.16      2536515.17     13440314.53
      2536819.15     13440327.06       2537034.7     13440485.77
      2537144.73     13440645.43      2537219.38     13440680.62
      2537330.83     13440927.31      2537422.56     13441019.48
       2537585.5     13441073.78      2537773.48     13441078.74
      2537869.72     13441130.52      2537880.14     13441219.82
      2537981.12     13441232.88       2538172.7     13441419.17
      2538280.93     13441472.76       2538464.5     13441476.22
      2538627.43     13441530.52      2538961.78     13441861.38
      2539076.58     13441921.18      2539419.06     13441977.26
      2539681.39       13442083.      2539724.01     13442135.28
      2539732.69     13442381.48      2539995.38     13442594.84
      2540061.22     13442711.73        2540125.       13442725.

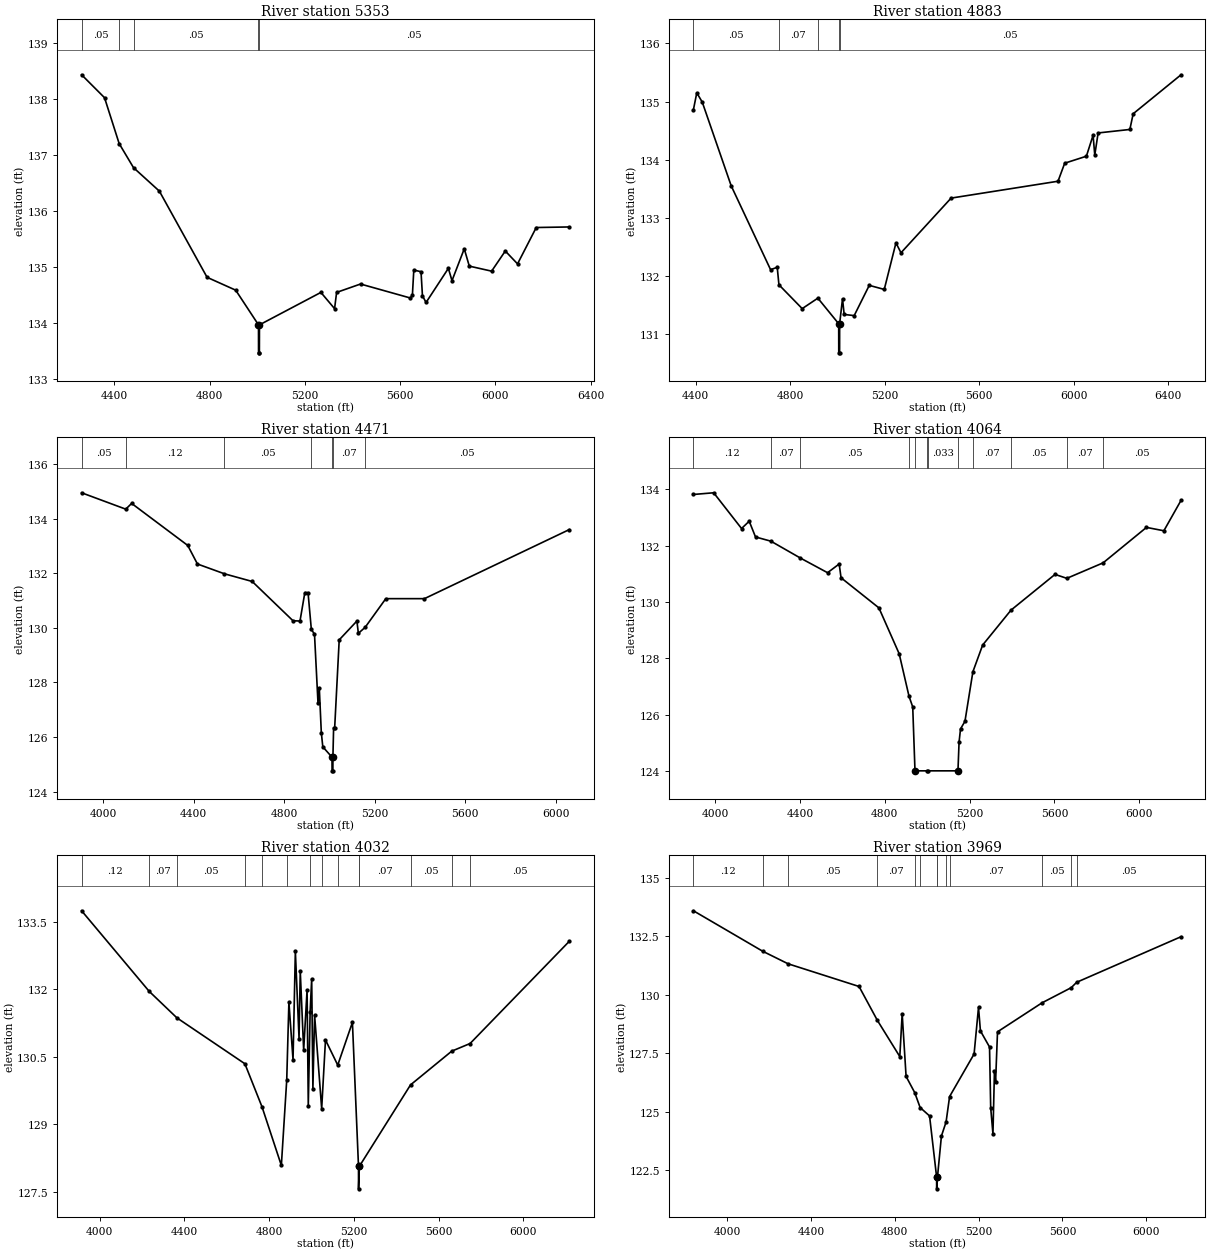
Type RM Length L Ch R = 1 ,5353    ,470,470,470
BEGIN DESCRIPTION:
TRIB 2 TO PAYTON BRANCH 9.0
END DESCRIPTION:
XS GIS Cut Line= 3
      2535588.91     13439907.59        2536325.       13439875.
      2537424.92     13439164.05
#Sta/Elev= 30
  4263.2  138.44  4359.4  138.03  4420.8  137.21    4481  136.78  4589.6  136.36
  4789.8  134.82  4909.9  134.59  5005.6  133.97  5005.8  133.47  5009.3  133.47
  5009.6  133.97  5267.5  134.55  5324.9  134.26  5333.4  134.55  5433.8   134.7
    5643  134.45  5651.5   134.5  5657.4  134.95  5687.7  134.92  5693.7  134.49
  5708.9  134.37  5802.5  134.98  5817.7  134.76  5869.2  135.33  5890.3  135.02
    5984  134.93  6041.4  135.29  6092.8  135.06  6171.3  135.71  6309.7  135.72
#Mann= 5 ,-1 , 0
  4263.2     .05       0  4420.8     .07       0    4481     .05       0
  5005.6     .05       0  5009.6     .05       0
Bank Sta=5005.6,5009.6
XS Rating Curve= 0 ,0
Exp/Cntr=0.3,0.1

Type RM Length L Ch R = 1 ,4883    ,412,412,412
BEGIN DESCRIPTION:
Mapping XS 17b4ce60
END DESCRIPTION:
XS GIS Cut Line= 3
      2535901.35     13440459.67      2536474.28     13440293.01
      2537491.06     13439234.67
#Sta/Elev= 30
  4390.6  134.86  4404.8  135.15    4428  134.99  4550.6  133.55  4717.2  132.11
  4745.4  132.15  4752.6  131.85  4851.1  131.44  4917.4  131.62  5005.6  131.18
  5005.9  130.68  5009.4  130.68  5009.6  131.18  5021.8  131.61  5028.7  131.34
  5071.2  131.32    5135  131.84  5198.5  131.77    5248  132.57  5269.3   132.4
  5481.5  133.34  5934.1  133.63  5962.4  133.94  6054.2  134.06  6082.5  134.42
  6089.7  134.08  6103.9  134.46  6238.2  134.52  6252.3  134.79  6454.9  135.46
#Mann= 5 ,-1 , 0
  4390.6     .05       0  4752.6     .07       0  4917.4     .05       0
  5005.6     .05       0  5009.6     .05       0
Bank Sta=5005.6,5009.6
XS Rating Curve= 0 ,0
Exp/Cntr=0.3,0.1

Type RM Length L Ch R = 1 ,4471    ,407,407,407
BEGIN DESCRIPTION:
Mapping XS 503d8c91
END DESCRIPTION:
XS GIS Cut Line= 3
      2535931.92     13440935.39      2536882.75     13440354.74
      2537546.86     13439556.35
#Sta/Elev= 30
  3905.9  134.95  4100.7  134.35  4126.8  134.56  4374.5  133.02  4417.2  132.34
  4536.7  131.98    4659   131.7  4839.1  130.26    4870  130.25  4891.3  131.29
  4905.5  131.29  4920.1  129.94    4934  129.77  4949.4  127.26  4955.3  127.78
  4964.1  126.16  4970.7  125.64  5011.3  125.26  5011.6  124.76  5015.1  124.76
  5015.3  125.26  5018.4  126.34  5023.1  126.34  5043.1  129.56  5121.2  130.25
  5127.7   129.8  5157.7  130.02  5248.8  131.07  5419.3  131.07  6058.5   133.6
#Mann= 7 ,-1 , 0
  3905.9     .05       0  4100.7     .12       0  4536.7     .05       0
  4920.1     .07       0  5011.3     .05       0  5015.3     .07       0
  5157.7     .05       0
Bank Sta=5011.3,5015.3
XS Rating Curve= 0 ,0
Exp/Cntr=0.3,0.1

Type RM Length L Ch R = 1 ,4064    ,32,32,32
BEGIN DESCRIPTION:
Mapping XS 6a83320a
END DESCRIPTION:
XS GIS Cut Line= 6
      2536127.88     13441076.94      2536991.63     13440688.61
      2537136.79     13440641.43      2537234.78     13440550.71
      2537256.55     13440478.13      2537655.75     13439570.85
#Sta/Elev= 30
  3897.1  133.82  3992.6  133.88  4124.2  132.61  4160.2  132.87    4190  132.31
  4262.6  132.16  4401.9  131.56  4529.9  131.04  4584.7  131.35  4593.5  130.86
  4772.1  129.79  4867.7  128.16  4914.1  126.65  4931.6  126.27  4942.3     124
    4998     124    5002     124    5145     124  5150.2  125.02  5157.1  125.49
    5178  125.76  5215.4  127.52  5261.5  128.47  5395.2  129.71  5602.8  130.98
  5658.6  130.84  5829.7  131.39  6034.2  132.65  6116.3  132.53  6197.3  133.61
#Mann= 12 ,-1 , 0
  3897.1     .12       0  4262.6     .07       0  4401.9     .05       0
  4914.1    .033       0  4942.3    .033       0    4998    .033       0
    5002    .033       0    5145    .033       0  5215.4     .07       0
  5395.2     .05       0  5658.6     .07       0  5829.7     .05       0
Bank Sta=4942.3,5145
XS Rating Curve= 0 ,0
Exp/Cntr=0.3,0.1

Type RM Length L Ch R = 1 ,4032    ,63,63,63
BEGIN DESCRIPTION:
Mapping XS 550d3cf4
END DESCRIPTION:
XS GIS Cut Line= 6
      2536167.83     13441095.07      2536984.37     13440739.42
       2537100.5     13440695.87        2537213.     13440634.18
      2537310.99      13440525.3      2537728.33     13439603.52
#Sta/Elev= 30
  3914.8  133.74  4233.6  131.95  4364.6  131.36  4685.4  130.34  4766.4  129.38
  4857.5  128.08  4882.9  129.98  4893.1  131.71  4912.6  130.43  4923.6  132.84
    4941   130.9  4946.7   132.4  4962.8  130.64  4978.9  131.98  4984.6  129.41
  4993.4   131.5  5000.7  132.23  5006.4  129.79  5014.4  131.42  5047.8  129.34
  5065.8  130.87  5123.6  130.31  5192.9  131.26  5221.6  128.06  5221.8  127.56
  5225.6  128.06  5467.1  129.87  5661.6  130.62  5748.3  130.79  6216.1  133.06
#Mann= 14 ,-1 , 0
  3914.8     .12       0  4233.6     .07       0  4364.6     .05       0
  4685.4     .07       0  4766.4     .05       0  4882.9    .033       0
  4993.4     .07       0  5047.8    .033       0  5123.6     .07       0
  5221.6     .05       0  5225.6     .07       0  5467.1     .05       0
  5661.6     .07       0  5748.3     .05       0
Bank Sta=5221.6,5225.6
XS Rating Curve= 0 ,0
Exp/Cntr=0.3,0.1

Type RM Length L Ch R = 1 ,3969    ,354,354,354
BEGIN DESCRIPTION:
Mapping XS e62cfd4c
END DESCRIPTION:
XS GIS Cut Line= 5
      2536153.31     13441134.99      2537165.82     13440721.28
      2537242.04     13440666.84      2537372.68     13440539.82
      2537753.74     13439661.57
#Sta/Elev= 30
    3839   133.6  4169.2  131.87    4291  131.33  4629.4  130.36  4716.8  128.91
  4823.9  127.36  4835.2  129.19  4853.9  126.51    4895  125.82  4920.9  125.18
  4965.9  124.82  4999.6   122.2  4999.8   121.7  5003.6   122.2  5022.5  123.96
  5044.7  124.56  5061.5  125.65  5178.4  127.47  5199.5  129.47  5208.6  128.46
  5252.1  127.77  5257.6  125.17  5268.4  124.05  5275.6  126.75    5281  126.28
  5290.2  128.42  5502.5  129.66  5642.1  130.31  5667.9  130.54    6166  132.49
#Mann= 13 ,-1 , 0
    3839     .12       0  4169.2     .07       0    4291     .05       0
  4716.8     .07       0    4895    .033       0  4920.9     .07       0
  4999.6     .05       0  5003.6     .07       0  5044.7      .1       0
  5061.5     .07       0  5502.5     .05       0  5642.1     .07       0
  5667.9     .05       0
Bank Sta=4999.6,5003.6
XS Rating Curve= 0 ,0
Exp/Cntr=0.3,0.1

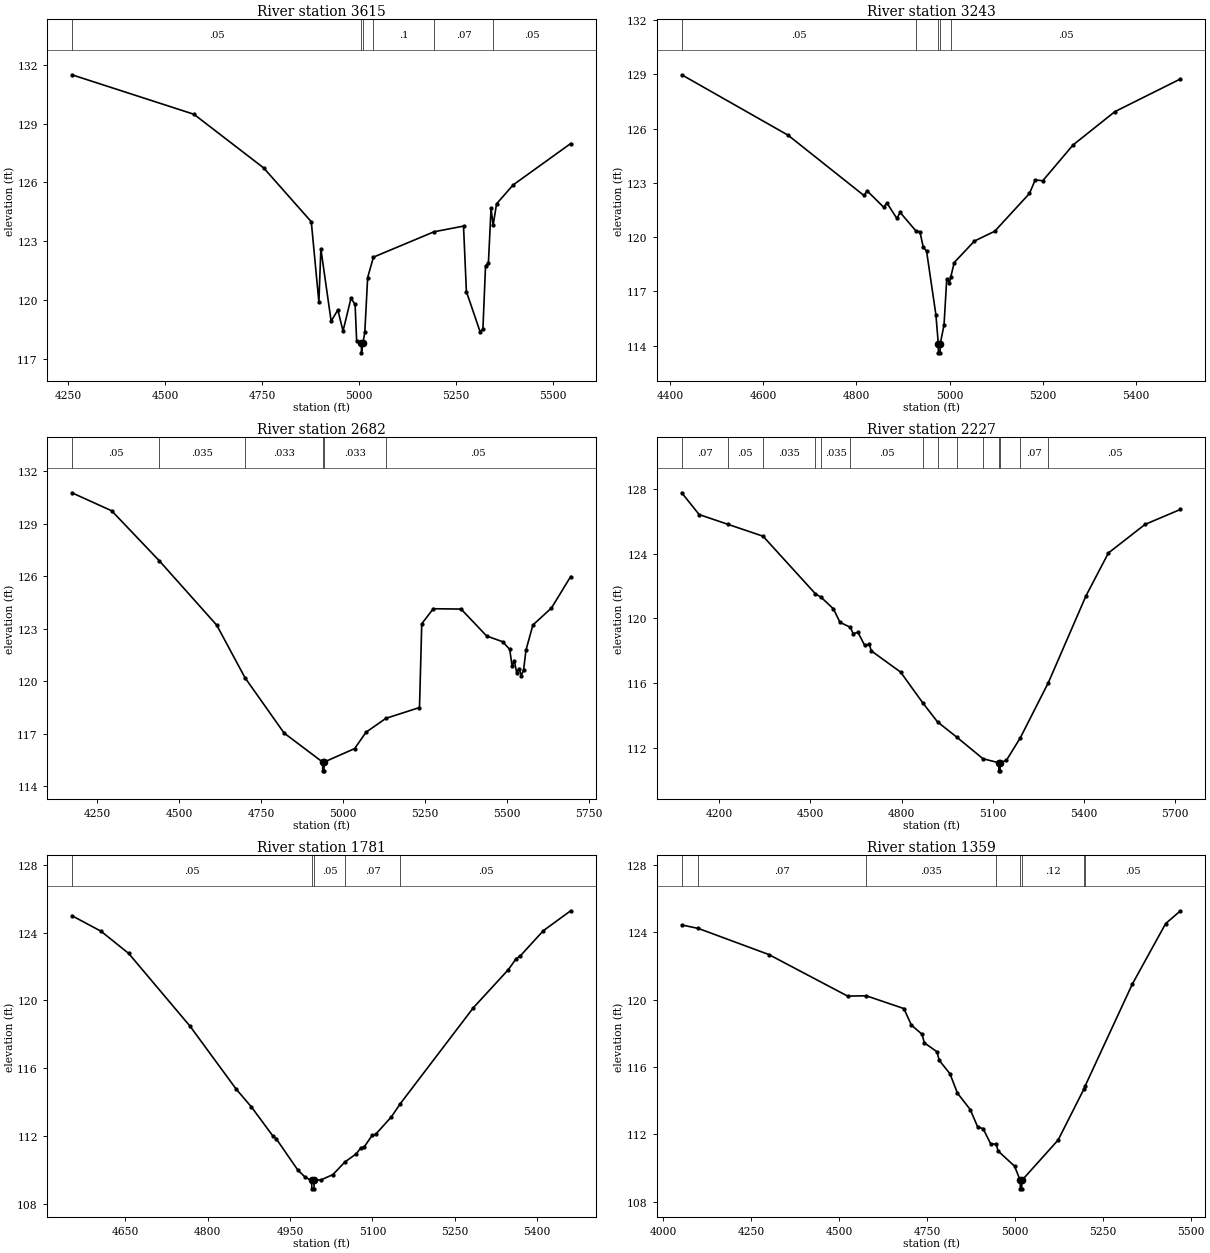
Type RM Length L Ch R = 1 ,3615    ,372,372,372
BEGIN DESCRIPTION:
Mapping XS 8d58afa7
END DESCRIPTION:
XS GIS Cut Line= 3
      2536661.78     13441147.17      2537375.32     13440990.92
      2537749.94     13440579.88
#Sta/Elev= 30
    4259  131.48  4573.8  129.47  4753.7  126.74  4876.5     124  4896.1  119.91
  4901.2  122.62  4927.7  118.94    4945  119.51  4958.4  118.44  4978.9  120.11
  4989.5  119.79  4993.5  117.93  5005.7  117.83  5005.9  117.33  5009.8  117.83
  5014.5  118.37  5021.9  121.16  5036.8   122.2  5193.1  123.49  5269.2  123.78
  5276.6  120.45  5311.8  118.41  5319.2  118.53    5326  121.76  5333.4   121.9
  5340.2  124.68  5345.6  123.83  5354.4  124.91  5396.9  125.87  5545.6  127.98
#Mann= 6 ,-1 , 0
    4259     .05       0  5005.7     .05       0  5009.8     .05       0
  5036.8      .1       0  5193.1     .07       0  5345.6     .05       0
Bank Sta=5005.7,5009.8
XS Rating Curve= 0 ,0
Exp/Cntr=0.3,0.1

Type RM Length L Ch R = 1 ,3243    ,561,561,561
BEGIN DESCRIPTION:
Mapping XS ed8d59ea
END DESCRIPTION:
XS GIS Cut Line= 3
       2537323.2     13441485.75      2537708.65      13441100.3
      2537963.86     13440641.97
#Sta/Elev= 30
  4425.5  128.97  4653.6  125.63  4816.2   122.3  4823.3  122.55  4858.6  121.65
  4865.7  121.88  4886.9  121.03    4894  121.36  4927.8  120.34  4936.4  120.29
  4943.5  119.44  4950.6  119.23  4970.6  115.71  4975.8   114.1    4976   113.6
  4979.7   113.6    4980   114.1  4988.1  115.15  4993.9  117.69  4999.6  117.47
  5002.6   117.8  5009.9  118.59  5053.3  119.78  5096.8  120.32  5171.3  122.41
  5183.7  123.16  5199.7  123.11  5264.8  125.09  5354.4  126.93  5495.2  128.74
#Mann= 5 ,-1 , 0
  4425.5     .05       0  4927.8    .035       0  4975.8    .035       0
    4980    .035       0  5002.6     .05       0
Bank Sta=4975.8,4980
XS Rating Curve= 0 ,0
Exp/Cntr=0.3,0.1

Type RM Length L Ch R = 1 ,2682    ,455,455,455
BEGIN DESCRIPTION:
TRIB 2 TO PAYTON BRANCH 6.0
END DESCRIPTION:
XS GIS Cut Line= 3
      2537374.99       13441725.        2538125.       13441375.
      2538630.26     13440897.42
#Sta/Elev= 30
  4172.6  130.78    4294  129.75    4439   126.9  4614.8  123.21  4700.9  120.21
  4820.5  117.04  4938.2  115.38  4938.5  114.88  4942.2  114.88  4942.5  115.38
  5035.7  116.15  5070.8  117.09  5131.2  117.88  5233.9   118.5  5240.8  123.29
    5276  124.15  5360.9  124.13    5439  122.59  5488.3  122.26  5509.4  121.82
  5516.7  120.87  5523.5  121.18  5530.8  120.48  5537.7  120.73    5545  120.33
  5551.9  120.67  5559.1  121.79  5580.2  123.22  5636.8  124.19  5695.5  125.99
#Mann= 6 ,-1 , 0
  4172.6     .05       0    4439    .035       0  4700.9    .033       0
  4938.2    .033       0  4942.5    .033       0  5131.2     .05       0
Bank Sta=4938.2,4942.5
XS Rating Curve= 0 ,0
Exp/Cntr=0.3,0.1

Type RM Length L Ch R = 1 ,2227    ,446,446,446
BEGIN DESCRIPTION:
TRIB 2 TO PAYTON BRANCH 5.0
END DESCRIPTION:
XS GIS Cut Line= 3
      2537724.98     13441975.01        2538525.       13441525.
       2539180.5     13441217.15
#Sta/Elev= 30
  4076.1  127.79  4133.5  126.44  4227.4  125.84  4343.7   125.1  4516.3  121.53
  4535.3  121.31  4575.5   120.6  4597.2  119.76  4630.8  119.46  4640.6  119.07
  4656.5  119.14  4678.2  118.34  4694.1   118.4  4699.8     118  4796.7  116.68
    4871  114.74  4918.5  113.59  4982.8  112.63    5068  111.31    5120  111.06
  5120.3  110.56  5124.2  110.56  5124.5  111.06    5145  111.21  5190.7   112.6
  5283.3  116.03    5407   121.4  5480.9  124.06  5601.6  125.83  5718.2  126.76
#Mann= 14 ,-1 , 0
  4076.1     .07       0  4227.4     .05       0  4343.7    .035       0
  4516.3     .05       0  4535.3    .035       0  4630.8     .05       0
    4871     .07       0  4918.5     .05       0  4982.8     .07       0
    5068     .05       0    5120     .05       0  5124.5     .05       0
  5190.7     .07       0  5283.3     .05       0
Bank Sta=5120,5124.5
XS Rating Curve= 0 ,0
Exp/Cntr=0.3,0.1

Type RM Length L Ch R = 1 ,1781    ,422,422,422
BEGIN DESCRIPTION:
TRIB 2 TO PAYTON BRANCH 4.0
END DESCRIPTION:
XS GIS Cut Line= 3
      2538474.99       13441975.        2538875.       13441775.
        2539175.       13441425.
#Sta/Elev= 30
  4552.8     125  4605.9  124.08  4656.2  122.77    4768  118.47  4851.9  114.76
  4879.8   113.7    4919  111.98  4924.6  111.84  4963.7     110  4977.7  109.55
  4989.3  109.37  4989.7  108.87  4993.6  108.87  4993.9  109.37  5007.2  109.41
    5028  109.71    5050  110.46  5070.8  110.94  5078.5  111.28  5085.1  111.35
  5099.4  112.02  5105.9  112.09  5134.5  113.12  5150.8   113.9  5283.7  119.56
  5347.4  121.81  5361.7  122.46  5368.8  122.61  5411.1  124.11    5461  125.29
#Mann= 5 ,-1 , 0
  4552.8     .05       0  4989.3     .05       0  4993.9     .05       0
    5050     .07       0  5150.8     .05       0
Bank Sta=4989.3,4993.9
XS Rating Curve= 0 ,0
Exp/Cntr=0.3,0.1

Type RM Length L Ch R = 1 ,1359    ,431,431,431
BEGIN DESCRIPTION:
TRIB 2 TO PAYTON BRANCH 3.0
END DESCRIPTION:
XS GIS Cut Line= 3
      2538425.02     13442474.99        2539225.       13441975.
      2539374.99     13441525.02
#Sta/Elev= 30
  4052.5  124.44  4099.8  124.23  4300.1  122.68  4524.2  120.21    4577  120.23
    4684  119.47  4705.2  118.49  4735.9  117.94  4741.8  117.44  4778.3   116.9
  4784.2   116.4  4814.9   115.6  4836.1  114.45  4872.6  113.47  4893.9  112.43
  4909.2  112.34  4930.4  111.44  4946.5  111.41  4951.7  111.01  4998.5  110.11
  5014.7  109.26    5015  108.76    5019  108.76  5019.3  109.26  5122.4  111.66
    5196   114.7  5198.7  114.85  5333.2  120.92  5428.1  124.52  5470.2  125.28
#Mann= 8 ,-1 , 0
  4052.5    .063       0  4099.8     .07       0    4577    .035       0
  4946.5     .12       0  5014.7     .05       0  5019.3     .12       0
    5196    .035       0  5198.7     .05       0
Bank Sta=5014.7,5019.3
XS Rating Curve= 0 ,0
Exp/Cntr=0.3,0.1

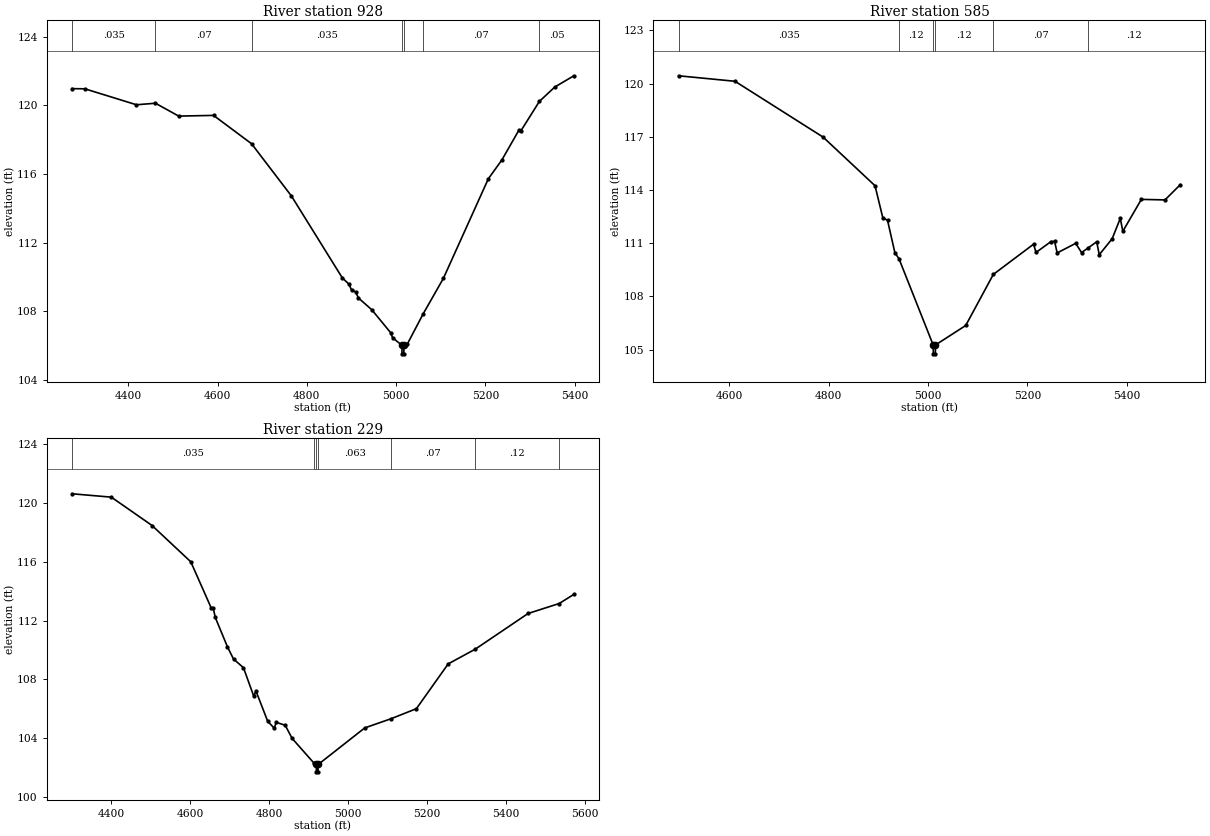
Type RM Length L Ch R = 1 ,928     ,343,343,343
BEGIN DESCRIPTION:
TRIB 2 TO PAYTON BRANCH 2.0
END DESCRIPTION:
XS GIS Cut Line= 3
      2539024.96     13442475.03        2539625.       13442075.
        2539675.     13441674.97
#Sta/Elev= 30
    4274  120.98  4302.6  120.97  4418.3  120.04  4460.8  120.13  4512.9  119.38
    4591  119.42  4676.1  117.77  4765.3  114.73  4879.5  109.95  4894.5  109.58
  4900.5  109.22  4909.5  109.13  4915.5  108.78  4945.6  108.09  4987.6  106.76
  4992.2  106.46    5013  106.02  5013.3  105.52  5017.3  105.52  5017.7  106.02
  5025.4   106.1  5060.7  107.85    5106  109.92  5206.8  115.73    5237  116.82
  5274.8  118.54  5279.9  118.53  5321.2  120.24  5355.4  121.07  5398.3  121.73
#Mann= 7 ,-1 , 0
    4274    .035       0  4460.8     .07       0  4676.1    .035       0
    5013    .035       0  5017.7    .035       0  5060.7     .07       0
  5321.2     .05       0
Bank Sta=5013,5017.7
XS Rating Curve= 0 ,0
Exp/Cntr=0.3,0.1

Type RM Length L Ch R = 1 ,585     ,356,356,356
BEGIN DESCRIPTION:
Mapping XS 439e5b3b
END DESCRIPTION:
XS GIS Cut Line= 4
       2539249.1     13442495.17      2539650.59     13442404.02
      2539837.22     13442271.64      2539752.57     13441911.36
#Sta/Elev= 30
  4497.4  120.44  4611.1  120.13  4788.6  116.98  4893.1  114.24  4908.8  112.43
  4918.3  112.29  4933.1  110.46  4941.4  110.12  5010.2  105.26  5010.6  104.76
  5014.6  104.76  5014.9  105.26  5075.8  106.36  5131.4  109.24  5212.3  110.94
  5217.5  110.48  5247.5  111.09  5254.8   111.1  5259.9  110.45  5297.2  110.99
  5309.1  110.47  5321.7  110.72  5339.6  111.08  5344.7  110.35  5370.7  111.25
  5387.1   112.4  5392.2  111.67  5429.5  113.47  5477.1  113.44    5508   114.3
#Mann= 6 ,-1 , 0
  4497.4    .035       0  4941.4     .12       0  5010.2     .05       0
  5014.9     .12       0  5131.4     .07       0  5321.7     .12       0
Bank Sta=5010.2,5014.9
XS Rating Curve= 0 ,0
Exp/Cntr=0.3,0.1

Type RM Length L Ch R = 1 ,229     ,0,0,0
BEGIN DESCRIPTION:
TRIB 2 TO PAYTON BRANCH 1.0
END DESCRIPTION:
XS GIS Cut Line= 4
      2539339.34     13442591.51      2539865.69     13442694.52
      2540032.36     13442525.25      2539860.22     13442060.27
#Sta/Elev= 30
  4301.6  120.64    4401  120.41    4504  118.48    4602  116.01  4653.5  112.88
  4658.6  112.88    4664  112.22  4694.6  110.23  4710.1  109.39  4735.3   108.8
  4761.6  106.84  4766.7  107.23  4796.5  105.16  4813.1  104.68  4818.2  105.08
    4841  104.88  4858.3  103.99  4913.5  102.31  4919.6  102.21  4919.9  101.71
  4923.9  101.71  4924.3  102.21  5042.2   104.7  5109.2  105.33  5172.9  106.01
  5253.4  109.06  5321.8  110.06  5455.5  112.49  5534.3  113.17  5571.3  113.79
#Mann= 7 ,-1 , 0
  4301.6    .035       0  4913.5    .063       0  4919.6     .05       0
  4924.3    .063       0  5109.2     .07       0  5321.8     .12       0
  5534.3     .07       0
Bank Sta=4919.6,4924.3
XS Rating Curve= 0 ,0
Exp/Cntr=0.3,0.1

Chan Stop Cuts=-1
Use User Specified Reach Order=0
Composite Channel Slope=5