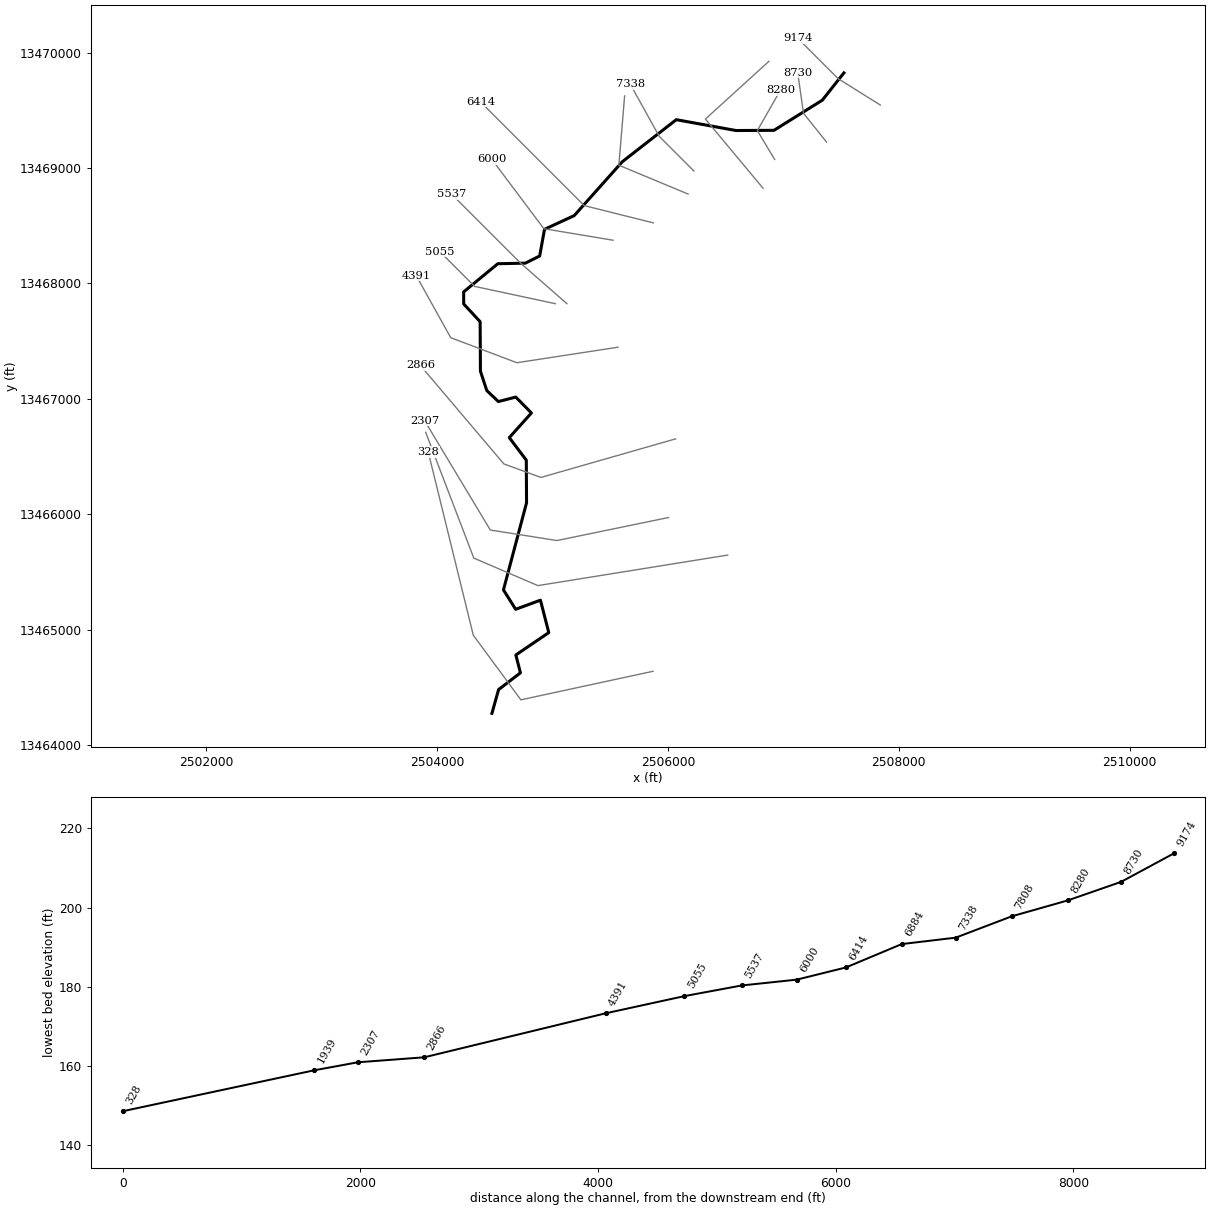
--- TRIB 2 TO PERDIDO CREEK.prj (project) ---

Proj Title=TRIB 2 TO PERDIDO CREEK Base Level Engineering
Current Plan=p01
Default Exp/Contr=0.3,0.1
English Units
Geom File=g01
Flow File=f01
Plan File=p01
Y Axis Title=Elevation
X Axis Title(PF)=Main Channel Distance
X Axis Title(XS)=Station
BEGIN DESCRIPTION:
TRIB 2 TO PERDIDO CREEK
END DESCRIPTION:
DSS Export Rating Curves= 0
DSS Export Rating Curve Sorted= 0
DSS Export Volume Flow Curves= 0
DXF OffsetX= 0
DXF OffsetY= 0
DXF ScaleX= 1
DXF ScaleY= 10

--- TRIB 2 TO PERDIDO CREEK.p01 (plan) ---

Plan Title=Multiple Run
Short Identifier=Multiple
Geom File=g01
Flow File=f01
Subcritical Flow
K Sum by GR= 0
Std Step Tol= 0.01
Critical Tol= 0.01
Num of Std Step Trials= 20
Max Error Tol= 0.3
Flow Tol Ratio= 0.001
Split Flow NTrial= 30
Split Flow Tol= 0.02
Split Flow Ratio= 0.02
Log Output Level= 0
Friction Slope Method= 1
Unsteady Friction Slope Method= 2
Unsteady Bridges Friction Slope Method= 1
Parabolic Critical Depth
Global Vel Dist=  1 , 1 , 1
Global Log Level= 0
CheckData=True
Encroach Param= -1, 0, 0, 0
BEGIN DESCRIPTION:
Multiple Run
END DESCRIPTION:

--- TRIB 2 TO PERDIDO CREEK.f01 (steady flow) ---

Flow Title=Multiple
Number of Profiles=7
Profile Names=10-year,25-year,50-year,1pct_min,100-year,1pct_plu,500-year
River Rch & RM= TRIB 2 TO PERDID,Reach-1,9174
     467     735     971     622    1241    2477    2005
River Rch & RM= TRIB 2 TO PERDID,Reach-1,5055
     698    1124    1508     980    1955    3900    3245
Boundary for River Rch & Prof#=TRIB 2 TO PERDID,Reach-1,1
Up Type=0
Dn Type=3
Dn Slope=0.005
Boundary for River Rch & Prof#=TRIB 2 TO PERDID,Reach-1,2
Up Type=0
Dn Type=3
Dn Slope=0.005
Boundary for River Rch & Prof#=TRIB 2 TO PERDID,Reach-1,3
Up Type=0
Dn Type=3
Dn Slope=0.005
Boundary for River Rch & Prof#=TRIB 2 TO PERDID,Reach-1,4
Up Type=0
Dn Type=3
Dn Slope=0.005
Boundary for River Rch & Prof#=TRIB 2 TO PERDID,Reach-1,5
Up Type=0
Dn Type=3
Dn Slope=0.005
Boundary for River Rch & Prof#=TRIB 2 TO PERDID,Reach-1,6
Up Type=0
Dn Type=3
Dn Slope=0.005
Boundary for River Rch & Prof#=TRIB 2 TO PERDID,Reach-1,7
Up Type=0
Dn Type=3
Dn Slope=0.005

--- TRIB 2 TO PERDIDO CREEK.g01 (geometry) ---

Geom Title=Existing Conditions
Program Version=4.10

River Reach=TRIB 2 TO PERDID,Reach-1
Reach XY= 30
        2507525.       13469825.      2507338.21     13469588.63
      2506919.07     13469327.24      2506590.22     13469325.52
      2506072.55     13469419.54      2505604.87     13469055.23
       2505188.3      13468588.4      2504930.59     13468469.39
      2504889.03     13468238.61       2504764.5      13468176.2
      2504526.46     13468171.46      2504230.29     13467927.67
      2504230.39     13467822.58      2504372.94     13467669.15
      2504375.52     13467240.22      2504430.52     13467072.56
      2504530.88     13466976.96      2504681.74     13467015.87
      2504817.41     13466878.33      2504625.55     13466664.36
      2504772.94     13466469.15       2504775.2     13466099.92
      2504575.04     13465345.03      2504680.71     13465176.88
      2504895.49     13465255.99      2504967.69     13464974.89
      2504682.48     13464781.07      2504721.96     13464626.42
      2504532.85     13464481.19        2504475.       13464275.

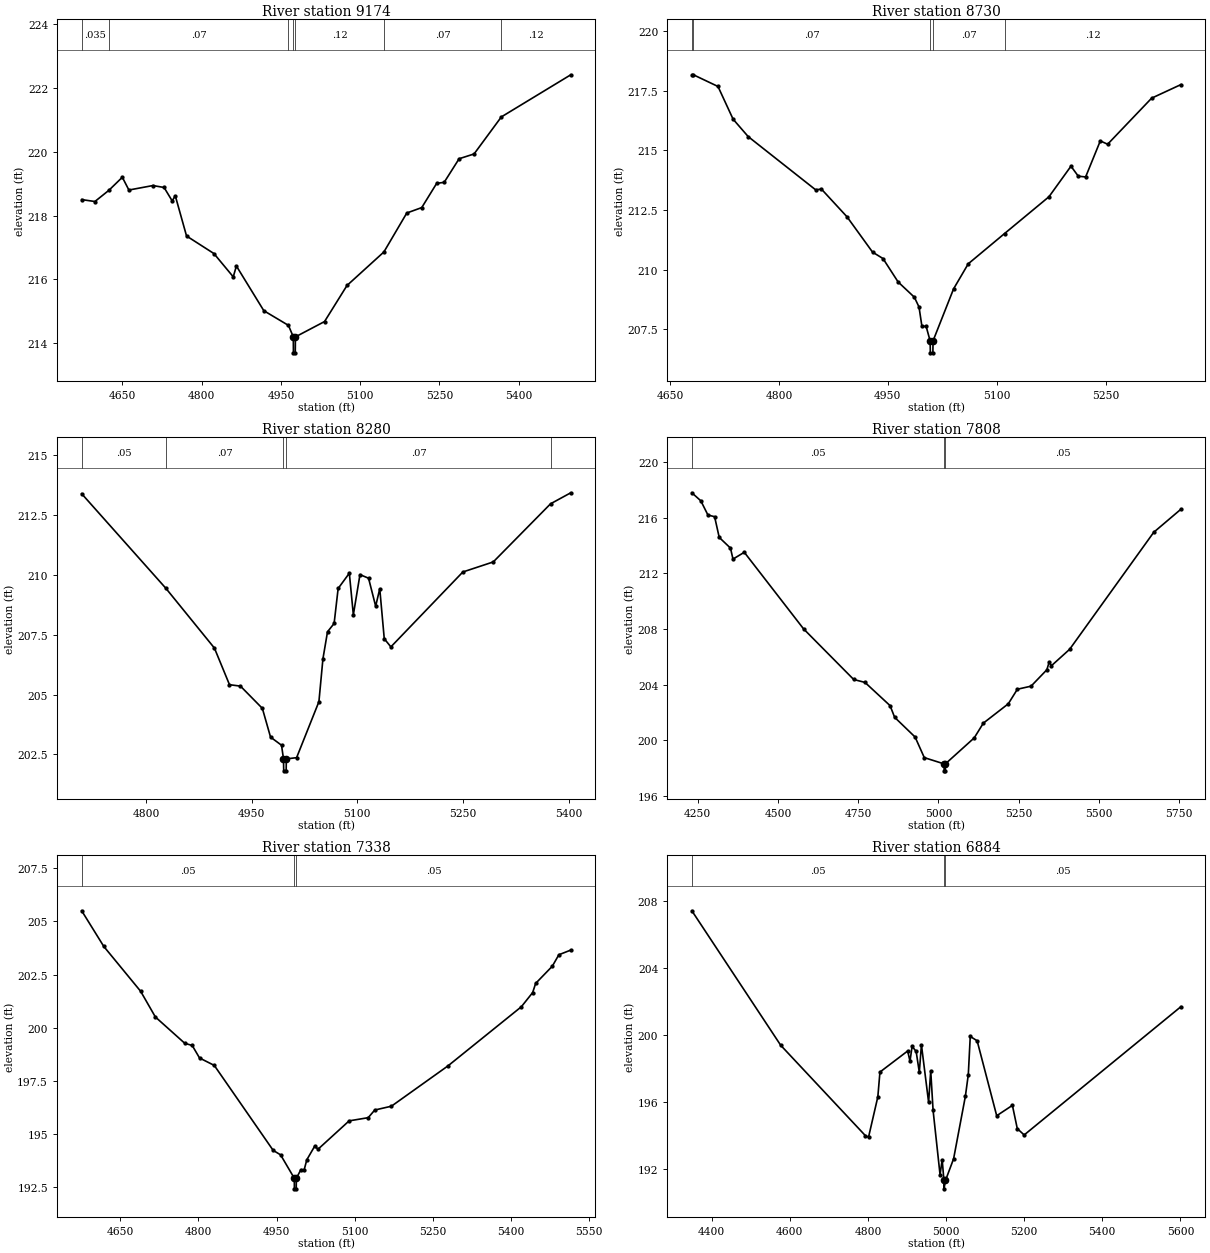
Type RM Length L Ch R = 1 ,9174    ,444,444,444
BEGIN DESCRIPTION:
TRIB 2 TO PERDIDO CREEK 13.0
END DESCRIPTION:
XS GIS Cut Line= 3
      2507840.71     13469546.43        2507475.       13469775.
      2507125.59     13470124.41
#Sta/Elev= 30
  4573.1   218.5  4598.1  218.44  4624.5  218.79    4650   219.2  4662.4   218.8
  4707.8  218.94    4729  218.88  4744.3  218.46  4750.2  218.62  4771.5  217.36
  4823.3  216.81  4859.9  216.08  4865.8  216.42  4917.7  215.02  4964.3  214.56
  4973.5   214.2  4973.7   213.7  4977.2   213.7  4977.5   214.2  5032.6  214.68
  5075.1  215.81  5144.9  216.86  5188.2  218.08  5216.5  218.25  5244.8  219.01
  5258.9  219.04  5287.2  219.78  5315.5  219.93  5367.1  221.09  5498.5  222.41
#Mann= 7 ,-1 , 0
  4573.1    .035       0  4624.5     .07       0  4964.3     .12       0
  4973.5     .05       0  4977.5     .12       0  5144.9     .07       0
  5367.1     .12       0
Bank Sta=4973.5,4977.5
XS Rating Curve= 0 ,0
Exp/Cntr=0.3,0.1

Type RM Length L Ch R = 1 ,8730    ,450,450,450
BEGIN DESCRIPTION:
TRIB 2 TO PERDIDO CREEK 12.0
END DESCRIPTION:
XS GIS Cut Line= 3
      2507374.98     13469225.02        2507175.       13469475.
        2507125.     13469825.02
#Sta/Elev= 30
  4680.1  218.16  4682.2  218.16  4716.1  217.67  4736.9   216.3  4757.7  215.57
  4850.6  213.34  4858.6  213.37  4893.8  212.21    4929  210.73  4943.4  210.46
  4964.2  209.48  4986.6  208.84    4993  208.43    4997  207.62  5002.8  207.62
  5008.3  207.01  5008.6  206.51  5012.1  206.51  5012.3  207.01  5040.6  209.19
  5060.8  210.24  5110.9  211.51    5172  213.05  5202.3  214.33  5212.4  213.91
  5222.5  213.88  5242.7  215.39  5252.8  215.25  5313.4  217.18  5353.8  217.75
#Mann= 5 ,-1 , 0
  4680.1     .12       0  4682.2     .07       0  5008.3     .05       0
  5012.3     .07       0  5110.9     .12       0
Bank Sta=5008.3,5012.3
XS Rating Curve= 0 ,0
Exp/Cntr=0.3,0.1

Type RM Length L Ch R = 1 ,8280    ,472,472,472
BEGIN DESCRIPTION:
TRIB 2 TO PERDIDO CREEK 11.0
END DESCRIPTION:
XS GIS Cut Line= 3
      2506924.99     13469075.01        2506775.       13469325.
      2506974.98     13469674.96
#Sta/Elev= 30
  4708.5  213.39    4828  209.44    4897  206.94  4918.4  205.41    4934  205.35
  4965.1  204.42  4976.7  203.22  4992.3  202.88  4995.1  202.31  4995.4  201.81
  4998.9  201.81  4999.1  202.31  5013.7  202.36  5045.4   204.7  5051.1  206.49
  5057.6  207.62    5067  207.97  5072.7  209.43  5088.6  210.07  5094.3  208.33
  5103.7  210.01  5115.9  209.86    5126  208.69  5131.8  209.42  5138.2  207.33
  5147.6  206.99  5249.8  210.12    5293  210.54  5374.4  212.97  5403.1  213.43
#Mann= 5 ,-1 , 0
  4708.5     .05       0    4828     .07       0  4995.1     .05       0
  4999.1     .07       0  5374.4     .12       0
Bank Sta=4995.1,4999.1
XS Rating Curve= 0 ,0
Exp/Cntr=0.3,0.1

Type RM Length L Ch R = 1 ,7808    ,470,470,470
BEGIN DESCRIPTION:
TRIB 2 TO PERDIDO CREEK 10.0
END DESCRIPTION:
XS GIS Cut Line= 3
        2506825.       13468825.        2506325.       13469425.
      2506874.98     13469924.98
#Sta/Elev= 30
  4231.5  217.79  4259.5  217.21  4281.6  216.19  4302.4  216.07  4316.8  214.58
  4351.9  213.81  4359.7  213.02  4394.9  213.51  4579.7     208  4735.9  204.36
  4771.1  204.15  4849.2  202.48  4863.5  201.64  4927.3  200.22  4955.9  198.74
  5017.6  198.29  5017.9  197.79  5021.4  197.79  5021.6  198.29  5111.5  200.16
  5139.9  201.22  5217.6  202.61    5246  203.66  5288.6  203.88  5337.9  205.06
  5345.3  205.63  5352.1  205.35  5408.8  206.53    5671  214.95  5755.8  216.61
#Mann= 3 ,-1 , 0
  4231.5     .05       0  5017.6     .05       0  5021.6     .05       0
Bank Sta=5017.6,5021.6
XS Rating Curve= 0 ,0
Exp/Cntr=0.3,0.1

Type RM Length L Ch R = 1 ,7338    ,454,454,454
BEGIN DESCRIPTION:
TRIB 2 TO PERDIDO CREEK 9.0
END DESCRIPTION:
XS GIS Cut Line= 3
      2506225.02     13468974.98        2505925.       13469275.
      2505674.99     13469725.02
#Sta/Elev= 30
  4575.9   205.5  4618.4  203.82  4689.1  201.71  4717.4   200.5  4773.9  199.26
  4788.1  199.16  4802.2  198.57  4830.5  198.22  4943.6  194.22  4957.8  194.01
  4984.1  192.91  4984.3  192.41  4987.8  192.41  4988.1  192.91  4996.7  193.31
  5003.1  193.31  5008.2  193.78  5023.1  194.41  5029.9  194.28  5089.4  195.61
    5126  195.76  5138.6  196.12  5170.6   196.3  5279.3   198.2    5420  200.98
  5441.8  201.65  5447.5  202.08  5479.5  202.89  5492.1  203.43    5515  203.65
#Mann= 3 ,-1 , 0
  4575.9     .05       0  4984.1     .05       0  4988.1     .05       0
Bank Sta=4984.1,4988.1
XS Rating Curve= 0 ,0
Exp/Cntr=0.3,0.1

Type RM Length L Ch R = 1 ,6884    ,470,470,470
BEGIN DESCRIPTION:
TRIB 2 TO PERDIDO CREEK 8.0
END DESCRIPTION:
XS GIS Cut Line= 3
      2506174.99       13468775.        2505575.       13469025.
        2505625.     13469625.03
#Sta/Elev= 30
  4349.3  207.41  4576.8  199.37  4793.5  193.97  4801.6  193.88  4825.4  196.29
  4830.8  197.77  4901.8  199.03  4907.7  198.42  4913.2  199.31  4923.5     199
  4931.6  197.76    4937   199.4  4955.4  195.96  4960.8  197.85  4966.8  195.49
  4984.7  191.63  4990.1  192.53  4994.6  191.29  4994.8  190.79  4998.6  191.29
  5019.4  192.59  5049.5  196.32    5057  197.62    5062   199.9  5079.6  199.64
  5129.7  195.16  5169.9  195.78  5182.4  194.39    5200  194.01  5601.4  201.68
#Mann= 3 ,-1 , 0
  4349.3     .05       0  4994.6     .05       0  4998.6     .05       0
Bank Sta=4994.6,4998.6
XS Rating Curve= 0 ,0
Exp/Cntr=0.3,0.1

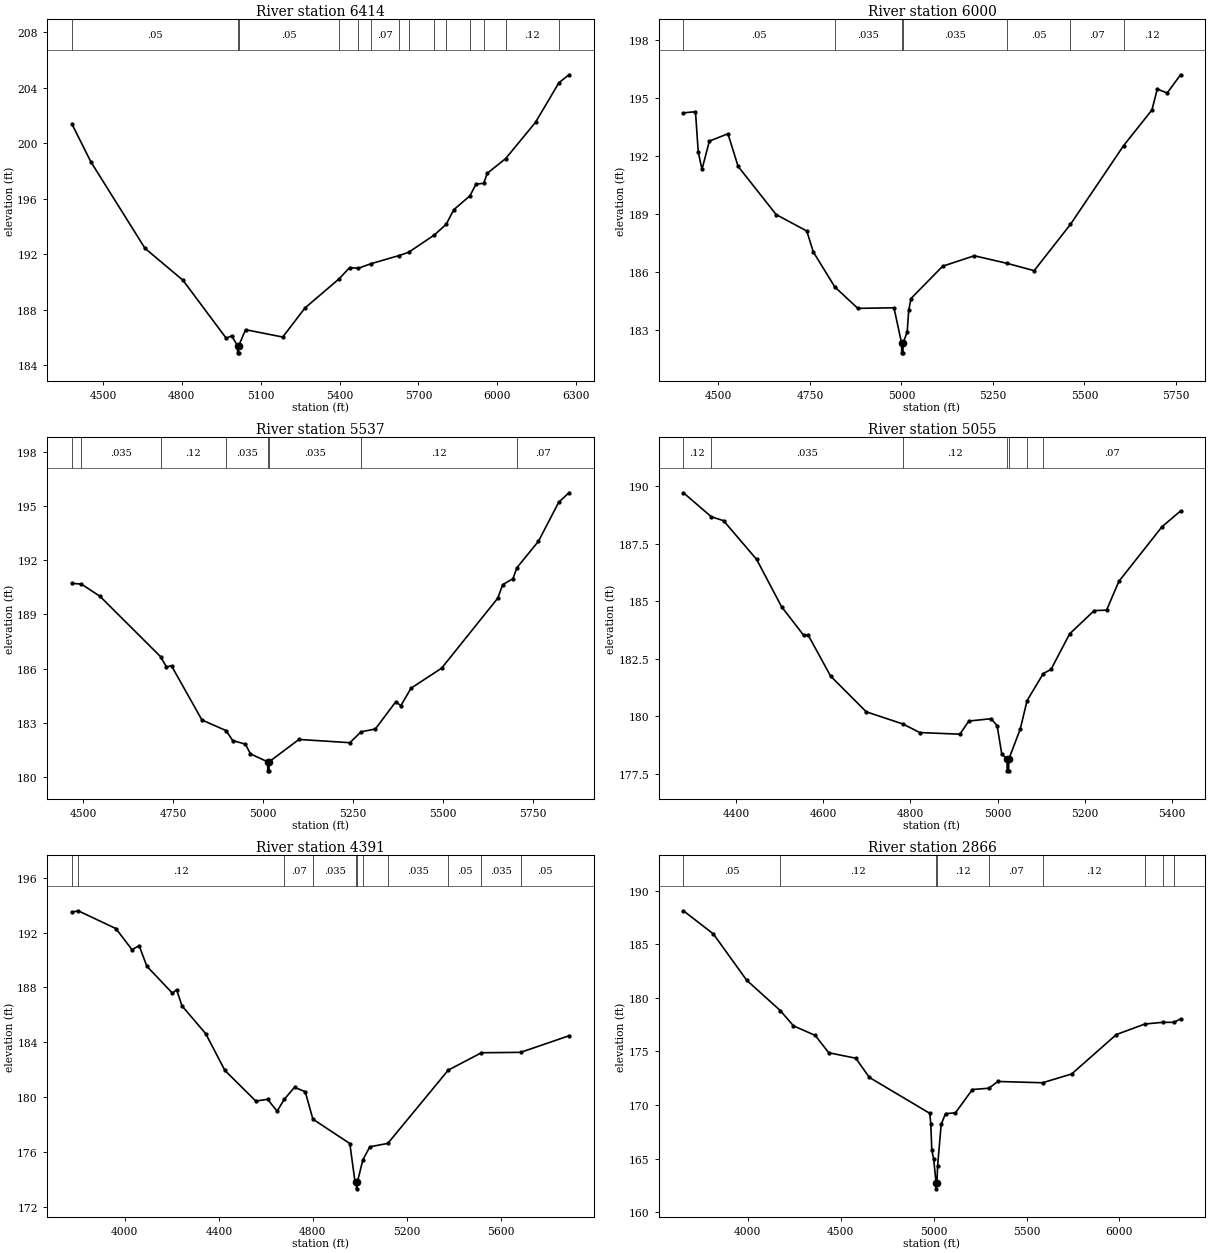
Type RM Length L Ch R = 1 ,6414    ,414,414,414
BEGIN DESCRIPTION:
TRIB 2 TO PERDIDO CREEK 7.0
END DESCRIPTION:
XS GIS Cut Line= 3
      2505874.96     13468525.01        2505275.       13468675.
      2504375.01     13469574.99
#Sta/Elev= 30
  4381.6   201.4  4453.7  198.67  4659.9  192.42  4804.2  190.12  4969.1  185.93
  4989.7  186.11  5012.2  185.38  5012.4  184.88  5015.9  184.88  5016.2  185.38
  5042.5  186.55  5183.9  186.02  5268.7  188.12  5398.4  190.22  5438.4  191.03
  5471.5  190.98  5519.5  191.31  5624.9  191.89  5662.5  192.13  5760.5  193.38
  5805.6  194.15  5834.4   195.2  5896.1  196.21  5919.3  197.05  5948.6  197.11
  5961.7  197.83  6031.7  198.89  6145.5  201.51  6234.7  204.37  6272.8  204.94
#Mann= 14 ,-1 , 0
  4381.6     .05       0  5012.2     .05       0  5016.2     .05       0
  5398.4     .07       0  5471.5     .05       0  5519.5     .07       0
  5624.9     .05       0  5662.5     .12       0  5760.5     .07       0
  5805.6     .12       0  5896.1     .05       0  5948.6     .07       0
  6031.7     .12       0  6234.7     .07       0
Bank Sta=5012.2,5016.2
XS Rating Curve= 0 ,0
Exp/Cntr=0.3,0.1

Type RM Length L Ch R = 1 ,6000    ,463,463,463
BEGIN DESCRIPTION:
TRIB 2 TO PERDIDO CREEK 6.0
END DESCRIPTION:
XS GIS Cut Line= 3
      2505524.98       13468375.        2504925.       13468475.
      2504474.97     13469075.03
#Sta/Elev= 30
  4404.2  194.21  4437.1  194.27  4444.7  192.19  4454.9  191.29  4475.1  192.75
  4525.8  193.13  4553.7  191.44  4657.6  188.95  4741.3   188.1    4759  187.02
  4817.7  185.21  4880.7   184.1  4979.5  184.13  5000.3   182.3  5000.6   181.8
  5004.1   181.8  5004.3   182.3  5015.6  182.88  5019.7  183.99    5026  184.61
  5112.5  186.28  5198.9  186.82    5288  186.43  5362.5  186.05  5461.5  188.44
    5607  192.52  5684.3  194.36  5698.9  195.44    5726  195.24  5762.5  196.18
#Mann= 7 ,-1 , 0
  4404.2     .05       0  4817.7    .035       0  5000.3    .035       0
  5004.3    .035       0    5288     .05       0  5461.5     .07       0
    5607     .12       0
Bank Sta=5000.3,5004.3
XS Rating Curve= 0 ,0
Exp/Cntr=0.3,0.1

Type RM Length L Ch R = 1 ,5537    ,482,482,482
BEGIN DESCRIPTION:
TRIB 2 TO PERDIDO CREEK 5.0
END DESCRIPTION:
XS GIS Cut Line= 3
      2505124.99     13467825.01        2504725.       13468175.
      2504125.01     13468774.99
#Sta/Elev= 30
  4469.1  190.72  4495.6  190.68  4547.4     190  4715.3  186.66  4731.5   186.1
  4745.8  186.15  4830.2  183.15  4897.2  182.56  4915.6  182.01  4950.8  181.81
    4965  181.27  5012.7  180.83    5013  180.33  5016.5  180.33  5016.7  180.83
  5099.6  182.07    5241  181.89  5271.8  182.49  5311.7  182.65  5368.3  184.16
  5382.4  183.94  5410.7  184.91  5495.6  186.02  5651.1  189.89  5665.3  190.65
  5693.6  190.98  5704.7  191.59  5764.3  193.05  5820.8  195.22  5849.1  195.74
#Mann= 8 ,-1 , 0
  4469.1     .12       0  4495.6    .035       0  4715.3     .12       0
  4897.2    .035       0  5012.7    .035       0  5016.7    .035       0
  5271.8     .12       0  5704.7     .07       0
Bank Sta=5012.7,5016.7
XS Rating Curve= 0 ,0
Exp/Cntr=0.3,0.1

Type RM Length L Ch R = 1 ,5055    ,664,664,664
BEGIN DESCRIPTION:
TRIB 2 TO PERDIDO CREEK 4.0
END DESCRIPTION:
XS GIS Cut Line= 3
      2505024.97     13467825.01        2504325.       13467975.
      2504025.02     13468274.98
#Sta/Elev= 30
  4279.3   189.7  4343.3  188.66  4371.3  188.49  4447.2  186.81  4504.3  184.76
  4555.4  183.51  4565.6  183.52  4616.8  181.75  4698.6   180.2  4782.9  179.67
  4821.3   179.3  4913.3  179.23  4933.8   179.8  4984.9   179.9  4998.7   179.6
  5009.3  178.38  5021.4  178.14  5021.7  177.64  5025.2  177.64  5025.4  178.14
  5051.7  179.45  5067.5  180.69  5104.6  181.86  5122.4  182.04  5164.9  183.58
  5221.4  184.59  5249.7  184.61    5278  185.86    5377  188.23  5419.4  188.91
#Mann= 7 ,-1 , 0
  4279.3     .12       0  4343.3    .035       0  4782.9     .12       0
  5021.4     .05       0  5025.4     .12       0  5067.5      .1       0
  5104.6     .07       0
Bank Sta=5021.4,5025.4
XS Rating Curve= 0 ,0
Exp/Cntr=0.3,0.1

Type RM Length L Ch R = 1 ,4391    ,1525,1525,1525
BEGIN DESCRIPTION:
Mapping XS 7b093578
END DESCRIPTION:
XS GIS Cut Line= 4
      2505567.92     13467448.02      2504691.16     13467313.47
      2504118.24     13467530.48      2503819.38     13468067.57
#Sta/Elev= 30
  3774.9  193.49  3801.8   193.6  3962.3   192.3  4030.8  190.76  4061.1  191.05
    4094  189.55  4202.8  187.58  4220.6  187.84  4243.2  186.66  4344.4  184.62
  4425.8  181.94  4557.4   179.7  4607.5  179.83  4647.9  178.96    4678  179.82
    4722  180.71  4767.6  180.38  4800.1  178.38  4957.2   176.6  4978.6  173.88
  4985.4  173.79  4985.7  173.29  4989.4  173.79  5012.6  175.41  5042.4  176.36
  5118.8  176.61  5375.7  181.96  5516.8  183.23  5683.9  183.26  5889.2  184.47
#Mann= 11 ,-1 , 0
  3774.9     .05       0  3801.8     .12       0    4678     .07       0
  4800.1    .035       0  4985.4    .035       0  4989.4    .035       0
  5012.6     .07       0  5118.8    .035       0  5375.7     .05       0
  5516.8    .035       0  5683.9     .05       0
Bank Sta=4985.4,4989.4
XS Rating Curve= 0 ,0
Exp/Cntr=0.3,0.1

Type RM Length L Ch R = 1 ,2866    ,559,559,559
BEGIN DESCRIPTION:
Mapping XS e65cd217
END DESCRIPTION:
XS GIS Cut Line= 4
      2506067.06     13466653.76      2504899.49     13466319.55
      2504578.31     13466436.73      2503854.24     13467290.88
#Sta/Elev= 30
  3653.1  188.13  3814.3  185.97  3993.5  181.65  4174.4  178.82  4245.5  177.39
  4362.6   176.5  4435.4  174.88    4581  174.37  4653.8  172.58  4978.8  169.23
  4984.8  168.26  4990.2  165.76  5000.1  164.99  5013.4  162.68  5013.6  162.18
  5017.4  162.68  5021.4  164.34  5040.6  168.19  5063.9   169.2  5117.2  169.27
  5208.6  171.45  5297.5  171.57  5345.4   172.2  5586.2  172.08  5743.1   172.9
  5983.6  176.58  6137.2  177.56  6232.5  177.72  6294.5  177.72  6329.2  178.04
#Mann= 9 ,-1 , 0
  3653.1     .05       0  4174.4     .12       0  5013.4     .05       0
  5017.4     .12       0  5297.5     .07       0  5586.2     .12       0
  6137.2    .035       0  6232.5     .05       0  6294.5    .035       0
Bank Sta=5013.4,5017.4
XS Rating Curve= 0 ,0
Exp/Cntr=0.3,0.1

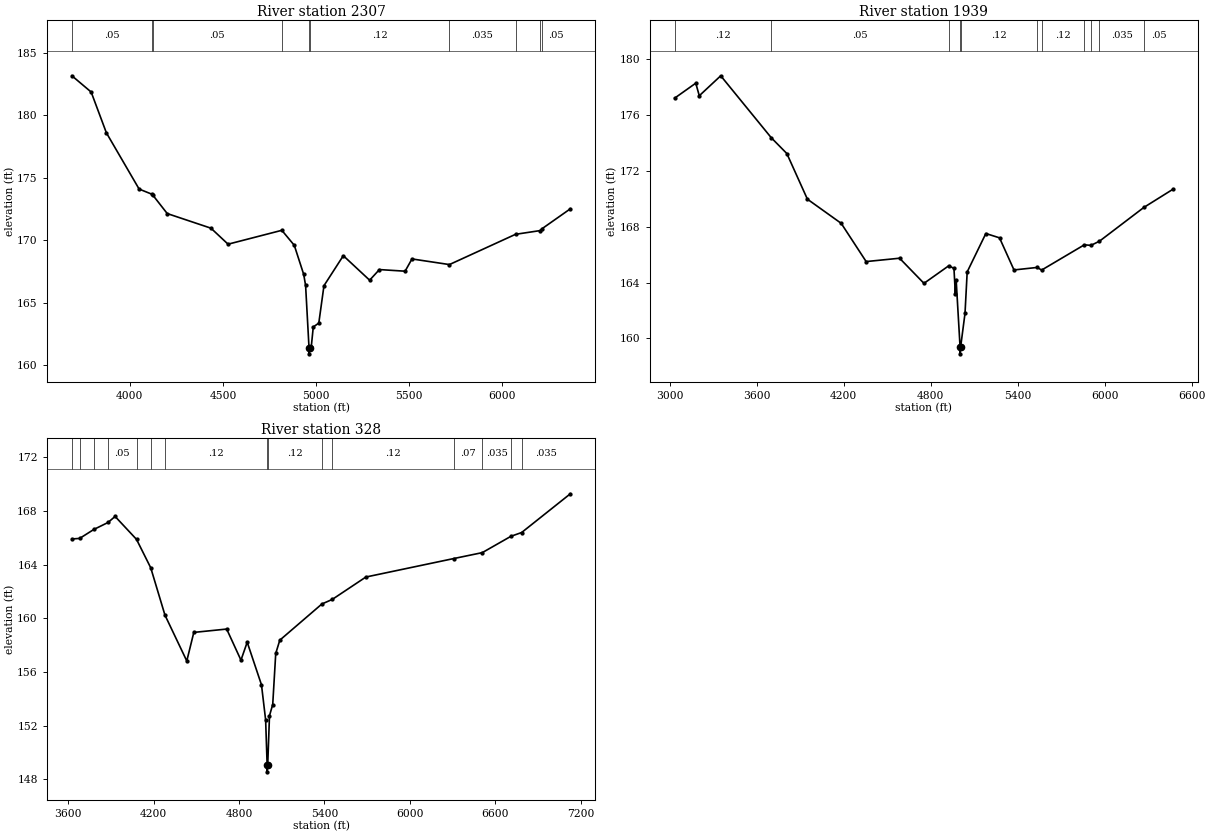
Type RM Length L Ch R = 1 ,2307    ,368,368,368
BEGIN DESCRIPTION:
Mapping XS fba4d37a
END DESCRIPTION:
XS GIS Cut Line= 4
      2506006.31     13465972.33      2505038.38     13465772.67
      2504461.12     13465863.82      2503892.54     13466810.01
#Sta/Elev= 30
  3688.8  183.16  3792.2  181.86  3873.9   178.6  4049.7   174.1    4118  173.69
    4122  173.64  4200.7  172.14  4435.5  170.97  4527.4  169.69  4816.1   170.8
    4883   169.6  4933.6  167.27  4943.7  166.39    4962  161.42  4962.2  160.92
    4966  161.42  4974.1  161.47  4984.9  163.07  5014.6  163.38  5042.3  166.37
  5146.2  168.77  5287.6  166.81    5340  167.66    5478  167.53  5514.9  168.51
    5716  168.06    6071  170.48  6204.2  170.78  6212.6  170.92  6365.4  172.52
#Mann= 10 ,-1 , 0
  3688.8     .05       0    4118     .12       0    4122     .05       0
  4816.1     .12       0    4962     .05       0    4966     .12       0
    5716    .035       0    6071     .05       0  6204.2    .035       0
  6212.6     .05       0
Bank Sta=4962,4966
XS Rating Curve= 0 ,0
Exp/Cntr=0.3,0.1

Type RM Length L Ch R = 1 ,1939    ,1611,1611,1611
BEGIN DESCRIPTION:
Mapping XS 93b3038f
END DESCRIPTION:
XS GIS Cut Line= 4
      2506518.37      13465646.8      2504873.45     13465382.05
      2504317.89     13465620.76      2503901.27     13466710.05
#Sta/Elev= 30
  3035.5  177.21  3180.7  178.28  3205.1  177.38  3352.9  178.81  3701.5  174.37
  3808.7  173.24  3950.5  169.97  4183.5  168.24  4355.6   165.5  4586.1  165.74
  4754.3  163.94  4925.4   165.2  4961.1  165.01  4970.8  163.16  4976.2  164.19
  5003.2  159.39  5003.5  158.89  5007.2  159.39  5037.3  161.79  5052.3  164.76
    5181  167.51  5275.2   167.2    5375   164.9  5535.5  165.08  5565.5  164.89
  5860.1   166.7  5905.4  166.66  5964.5  166.96  6270.7  169.38  6472.5  170.69
#Mann= 11 ,-1 , 0
  3035.5     .12       0  3701.5     .05       0  4925.4     .12       0
  5003.2     .05       0  5007.2     .12       0  5535.5     .07       0
  5565.5     .12       0  5860.1    .035       0  5905.4     .12       0
  5964.5    .035       0  6270.7     .05       0
Bank Sta=5003.2,5007.2
XS Rating Curve= 0 ,0
Exp/Cntr=0.3,0.1

Type RM Length L Ch R = 1 ,328     ,0,0,0
BEGIN DESCRIPTION:
TRIB 2 TO PERDIDO CREEK 1.0
END DESCRIPTION:
XS GIS Cut Line= 4
       2505871.7     13464639.86      2504725.88     13464392.46
      2504313.55     13464952.36      2503923.03     13466540.48
#Sta/Elev= 30
  3624.9  165.92  3679.2  165.96  3779.2  166.63  3879.1  167.15  3928.4   167.6
    4079  165.89  4178.9  163.77  4278.9  160.24  4432.3  156.82  4481.6  158.95
  4712.6   159.2    4813  156.88  4856.9  158.22  4957.2  155.04  4986.4  152.42
    4997  149.05  4997.2  148.55    5001  149.05  5013.5  152.74  5036.2  153.57
  5057.4  157.38  5085.9  158.37  5381.8  161.07  5454.6  161.41  5690.8  163.08
    6309  164.46  6508.9   164.9  6710.6  166.12  6785.5   166.4  7127.9  169.29
#Mann= 15 ,-1 , 0
  3624.9     .07       0  3679.2     .05       0  3779.2     .07       0
  3879.1     .05       0    4079    .035       0  4178.9     .05       0
  4278.9     .12       0    4997     .05       0    5001     .12       0
  5381.8     .07       0  5454.6     .12       0    6309     .07       0
  6508.9    .035       0  6710.6     .12       0  6785.5    .035       0
Bank Sta=4997,5001
XS Rating Curve= 0 ,0
Exp/Cntr=0.3,0.1

Chan Stop Cuts=-1
Use User Specified Reach Order=0
Composite Channel Slope=5