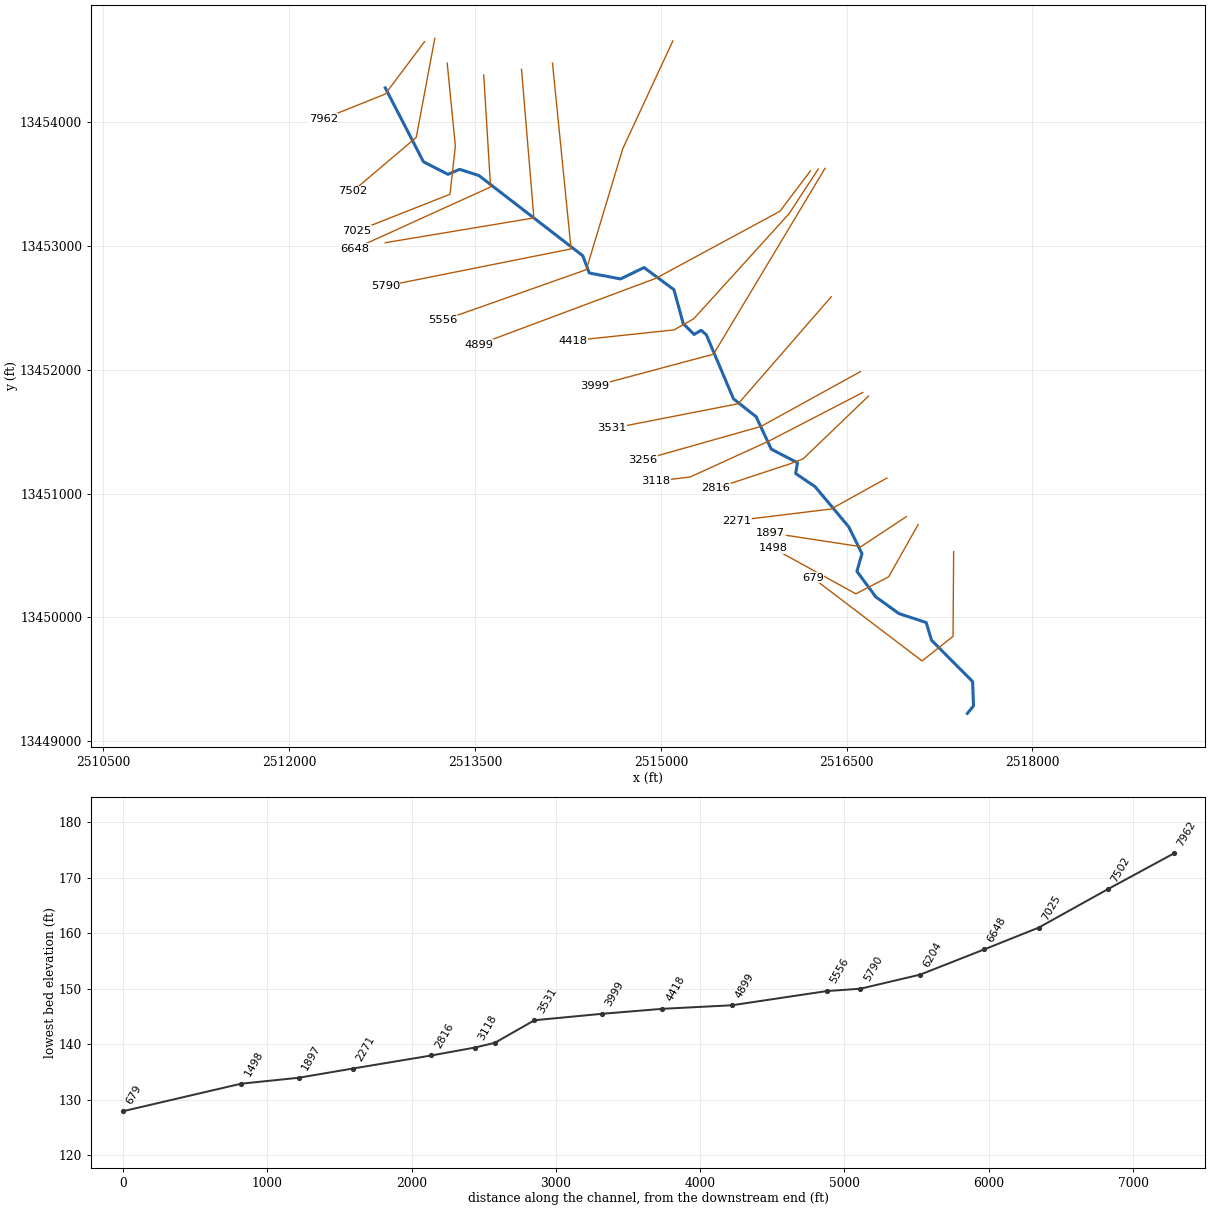
--- TRIB 2 TO ROAD CREEK.prj (project) ---

Proj Title=TRIB 2 TO ROAD CREEK Base Level Engineering
Current Plan=p01
Default Exp/Contr=0.3,0.1
English Units
Geom File=g01
Flow File=f01
Plan File=p01
Y Axis Title=Elevation
X Axis Title(PF)=Main Channel Distance
X Axis Title(XS)=Station
BEGIN DESCRIPTION:
TRIB 2 TO ROAD CREEK
END DESCRIPTION:
DSS Export Rating Curves= 0
DSS Export Rating Curve Sorted= 0
DSS Export Volume Flow Curves= 0
DXF OffsetX= 0
DXF OffsetY= 0
DXF ScaleX= 1
DXF ScaleY= 10

--- TRIB 2 TO ROAD CREEK.p01 (plan) ---

Plan Title=Multiple Run
Short Identifier=Multiple
Geom File=g01
Flow File=f01
Subcritical Flow
K Sum by GR= 0
Std Step Tol= 0.01
Critical Tol= 0.01
Num of Std Step Trials= 20
Max Error Tol= 0.3
Flow Tol Ratio= 0.001
Split Flow NTrial= 30
Split Flow Tol= 0.02
Split Flow Ratio= 0.02
Log Output Level= 0
Friction Slope Method= 1
Unsteady Friction Slope Method= 2
Unsteady Bridges Friction Slope Method= 1
Parabolic Critical Depth
Global Vel Dist=  1 , 1 , 1
Global Log Level= 0
CheckData=True
Encroach Param= -1, 0, 0, 0
BEGIN DESCRIPTION:
Multiple Run
END DESCRIPTION:

--- TRIB 2 TO ROAD CREEK.f01 (steady flow) ---

Flow Title=Multiple
Number of Profiles=7
Profile Names=10-year,25-year,50-year,1pct_min,100-year,1pct_plu,500-year
River Rch & RM= TRIB 2 TO ROAD C,Reach-1,7962
     485     763    1007     644    1285    2564    2069
River Rch & RM= TRIB 2 TO ROAD C,Reach-1,4418
     676    1083    1447     936    1867    3726    3074
Boundary for River Rch & Prof#=TRIB 2 TO ROAD C,Reach-1,1
Up Type=0
Dn Type=3
Dn Slope=0.005
Boundary for River Rch & Prof#=TRIB 2 TO ROAD C,Reach-1,2
Up Type=0
Dn Type=3
Dn Slope=0.005
Boundary for River Rch & Prof#=TRIB 2 TO ROAD C,Reach-1,3
Up Type=0
Dn Type=3
Dn Slope=0.005
Boundary for River Rch & Prof#=TRIB 2 TO ROAD C,Reach-1,4
Up Type=0
Dn Type=3
Dn Slope=0.005
Boundary for River Rch & Prof#=TRIB 2 TO ROAD C,Reach-1,5
Up Type=0
Dn Type=3
Dn Slope=0.005
Boundary for River Rch & Prof#=TRIB 2 TO ROAD C,Reach-1,6
Up Type=0
Dn Type=3
Dn Slope=0.005
Boundary for River Rch & Prof#=TRIB 2 TO ROAD C,Reach-1,7
Up Type=0
Dn Type=3
Dn Slope=0.005

--- TRIB 2 TO ROAD CREEK.g01 (geometry) ---

Geom Title=Existing Conditions
Program Version=4.10

River Reach=TRIB 2 TO ROAD C,Reach-1
Reach XY= 30
        2512775.       13454275.      2513083.15     13453678.38
      2513281.12     13453576.84      2513374.99     13453617.41
      2513531.17     13453567.14      2514369.74     13452919.53
      2514422.27     13452780.35      2514675.01     13452732.53
      2514864.38     13452824.41      2515105.53     13452645.54
      2515180.52     13452372.54      2515268.32      13452284.3
      2515325.24     13452317.54      2515367.14      13452281.8
      2515585.76     13451765.32      2515769.41     13451619.39
      2515891.49     13451357.95      2516102.64     13451248.71
      2516088.51     13451161.32      2516245.41     13451055.23
      2516516.86     13450731.06      2516623.91     13450514.45
       2516582.8     13450371.58      2516735.65       13450165.
      2516922.58     13450030.54      2517142.13     13449958.55
      2517185.52     13449815.22      2517517.17     13449481.19
      2517524.04      13449285.4        2517475.       13449225.

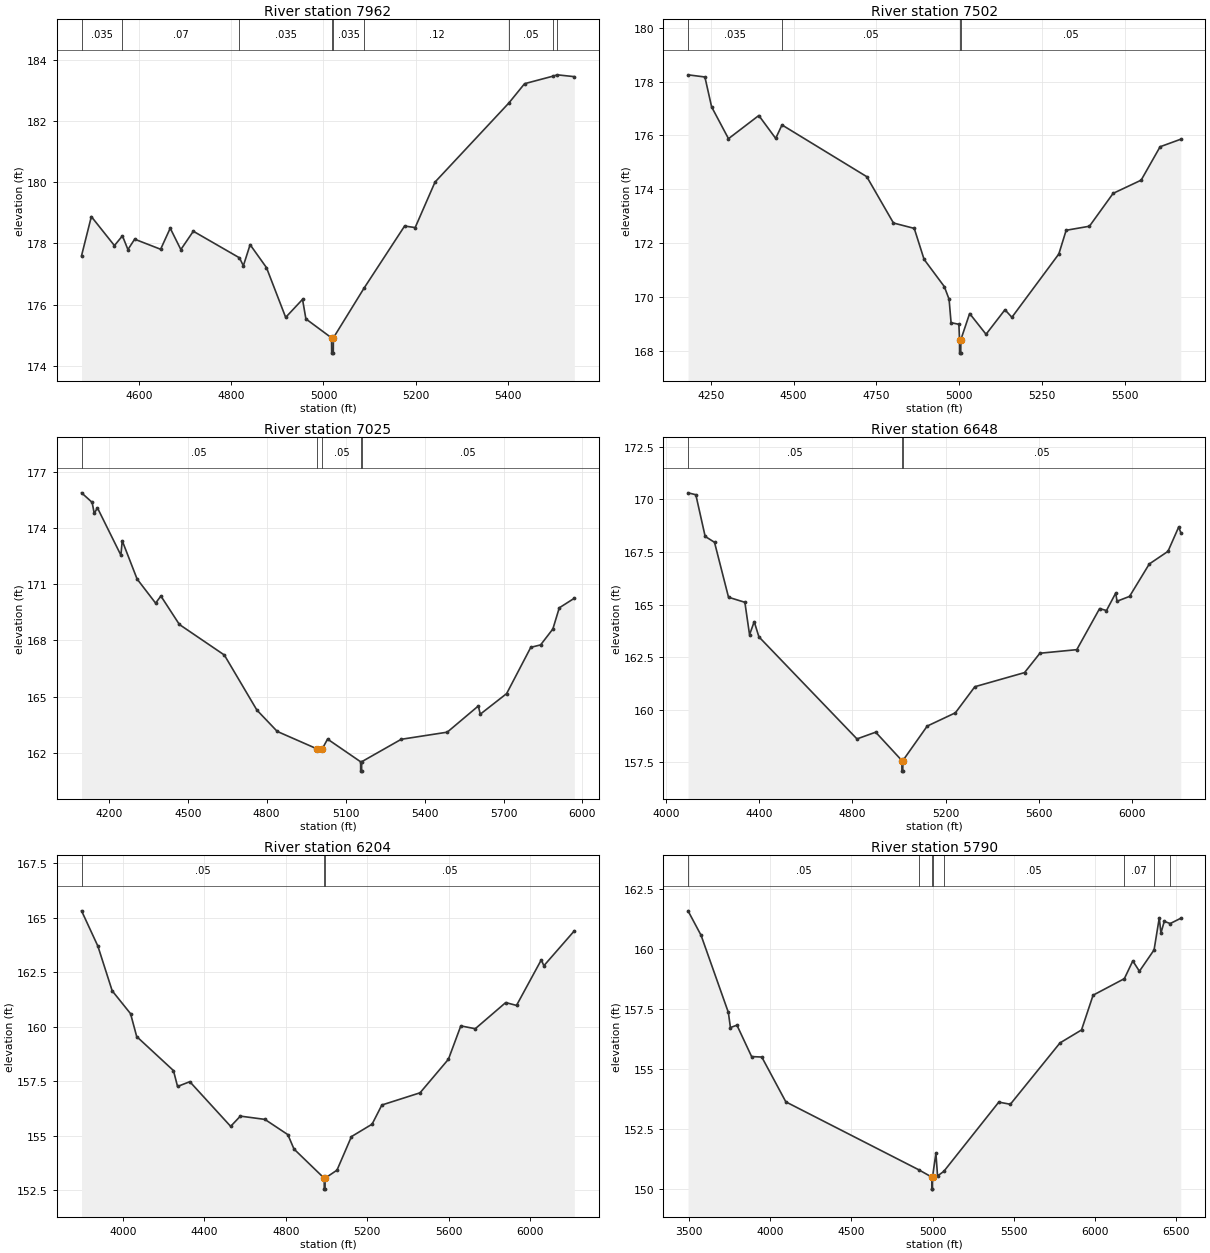
Type RM Length L Ch R = 1 ,7962    ,460,460,460
BEGIN DESCRIPTION:
TRIB 2 TO ROAD CREEK 14.0
END DESCRIPTION:
XS GIS Cut Line= 3
       2513092.1      13454647.8        2512775.       13454225.
      2512275.01       13454025.
#Sta/Elev= 30
  4476.2   177.6  4497.4  178.88  4547.4  177.93  4564.7  178.25  4576.6   177.8
  4591.2  178.14  4647.4  177.81  4668.2   178.5  4691.2   177.8  4718.2   178.4
  4818.1  177.53  4826.6  177.27  4841.2  177.96  4876.6  177.21  4918.2  175.58
  4954.7  176.17    4962  175.53  5017.5  174.91  5017.8  174.41  5021.3  174.41
  5021.5  174.91  5087.6  176.53  5175.7  178.57  5198.6  178.52  5241.6  180.01
  5401.6   182.6  5435.5  183.23  5497.9  183.48  5506.3  183.52  5543.2  183.46
#Mann= 9 ,-1 , 0
  4476.2    .035       0  4564.7     .07       0  4818.1    .035       0
  5017.5    .035       0  5021.5    .035       0  5087.6     .12       0
  5401.6     .05       0  5497.9     .07       0  5506.3     .05       0
Bank Sta=5017.5,5021.5
XS Rating Curve= 0 ,0
Exp/Cntr=0.3,0.1

Type RM Length L Ch R = 1 ,7502    ,477,477,477
BEGIN DESCRIPTION:
TRIB 2 TO ROAD CREEK 13.0
END DESCRIPTION:
XS GIS Cut Line= 3
        2513175.     13454674.99        2513025.       13453875.
      2512511.87     13453440.05
#Sta/Elev= 30
  4181.6  178.25  4232.5  178.17  4252.8  177.06  4303.7  175.88  4395.2  176.74
  4446.1  175.89  4465.1  176.39  4720.8  174.47  4801.4  172.75  4864.1  172.55
  4893.8   171.4  4954.8  170.39  4969.2  169.92  4975.2  169.05  4998.8  168.99
  5000.7  168.42  5000.9  167.92  5004.4  167.92  5004.7  168.42  5031.2  169.39
  5080.7  168.62  5137.8  169.53  5158.7  169.25  5300.3   171.6  5322.4  172.48
  5392.6  172.63  5464.1  173.85  5548.6  174.34  5605.8  175.58  5668.2  175.86
#Mann= 4 ,-1 , 0
  4181.6    .035       0  4465.1     .05       0  5000.7     .05       0
  5004.7     .05       0
Bank Sta=5000.7,5004.7
XS Rating Curve= 0 ,0
Exp/Cntr=0.3,0.1

Type RM Length L Ch R = 1 ,7025    ,377,377,377
BEGIN DESCRIPTION:
TRIB 2 TO ROAD CREEK 12.0
END DESCRIPTION:
XS GIS Cut Line= 4
        2513275.     13454475.01      2513340.89     13453804.65
      2513297.49      13453416.2      2512545.81     13453119.43
#Sta/Elev= 30
  4096.5  175.88  4136.7  175.37  4144.7  174.78  4156.8  175.08    4246  172.55
  4251.1  173.32  4307.5  171.28  4377.9  169.99    4398  170.37  4468.3  168.85
  4639.1  167.22  4762.8  164.28  4840.2  163.14  4991.1  162.21  5011.2  162.21
  5031.4  162.73    5157  161.52  5157.3  161.02  5160.8  161.02    5161  161.52
  5311.4  162.72  5486.2   163.1  5604.4   164.5  5611.7  164.06  5711.9  165.16
  5803.7  167.63    5841  167.76  5887.6  168.61    5912  169.74  5969.1  170.25
#Mann= 5 ,-1 , 0
  4096.5     .05       0  4991.1     .05       0  5011.2     .05       0
    5157     .05       0    5161     .05       0
Bank Sta=4991.1,5011.2
XS Rating Curve= 0 ,0
Exp/Cntr=0.3,0.1

Type RM Length L Ch R = 1 ,6648    ,444,444,444
BEGIN DESCRIPTION:
TRIB 2 TO ROAD CREEK 11.0
END DESCRIPTION:
XS GIS Cut Line= 3
      2513569.94      13454378.4        2513625.       13453475.
      2512524.98     13452974.99
#Sta/Elev= 30
  4094.7  170.31  4128.2  170.22  4168.2  168.24  4208.3  167.96  4268.4  165.35
  4338.5  165.11  4358.6  163.57  4378.6  164.19  4398.7  163.47  4819.4  158.62
  4899.6  158.94  5012.1  157.59  5012.3  157.09  5015.8  157.09  5016.1  157.59
  5120.6  159.23  5241.4  159.86  5324.9   161.1    5538  161.77  5603.9  162.69
  5762.1  162.86  5859.9  164.81  5889.5  164.72  5929.1  165.55  5934.6  165.16
  5988.4  165.39    6073  166.93  6153.2  167.53  6199.3  168.69  6208.1  168.42
#Mann= 3 ,-1 , 0
  4094.7     .05       0  5012.1     .05       0  5016.1     .05       0
Bank Sta=5012.1,5016.1
XS Rating Curve= 0 ,0
Exp/Cntr=0.3,0.1

Type RM Length L Ch R = 1 ,6204    ,414,414,414
BEGIN DESCRIPTION:
TRIB 2 TO ROAD CREEK 10.0
END DESCRIPTION:
XS GIS Cut Line= 3
        2513875.     13454424.97        2513975.       13453225.
      2512774.98       13453025.
#Sta/Elev= 30
  3796.2  165.31  3876.4  163.69  3946.7  161.64    4037  160.59  4067.1  159.54
  4247.7  157.98  4267.8  157.25    4328  157.47  4528.7  155.42  4576.4  155.89
  4696.8  155.74  4809.7  155.04  4839.8  154.38  4988.3  153.04  4988.5  152.54
    4992  152.54  4992.3  153.04    5051  153.41    5122  154.95  5223.4  155.52
  5271.5   156.4  5459.1  156.96  5598.5   158.5  5659.3  160.03  5730.3   159.9
  5879.8   161.1    5933  160.97  6054.7  163.06  6067.3  162.79  6216.9  164.39
#Mann= 3 ,-1 , 0
  3796.2     .05       0  4988.3     .05       0  4992.3     .05       0
Bank Sta=4988.3,4992.3
XS Rating Curve= 0 ,0
Exp/Cntr=0.3,0.1

Type RM Length L Ch R = 1 ,5790    ,234,234,234
BEGIN DESCRIPTION:
TRIB 2 TO ROAD CREEK 9.0
END DESCRIPTION:
XS GIS Cut Line= 3
        2514125.     13454474.96        2514275.       13452975.
      2512775.04     13452675.01
#Sta/Elev= 30
  3492.6  161.61    3573  160.59  3741.3  157.37  3753.9  156.74  3794.1  156.84
  3884.5  155.53  3947.3  155.51  4095.6  153.64  4913.9  150.81  4995.5   150.5
  4995.8     150  4999.3     150  4999.5   150.5  5020.4   151.5  5030.6  150.55
  5069.1  150.74    5408  153.63  5479.3  153.54  5785.3   156.1  5917.9  156.64
  5989.2  158.09  6181.9  158.78    6234  159.52  6274.8  159.09  6365.1  159.98
  6397.2  161.32  6407.4  160.68  6427.8  161.17  6464.7  161.08  6529.7   161.3
#Mann= 8 ,-1 , 0
  3492.6     .05       0  4913.9    .035       0  4995.5    .035       0
  4999.5    .035       0  5069.1     .05       0  6181.9     .07       0
  6365.1     .05       0  6464.7     .07       0
Bank Sta=4995.5,4999.5
XS Rating Curve= 0 ,0
Exp/Cntr=0.3,0.1

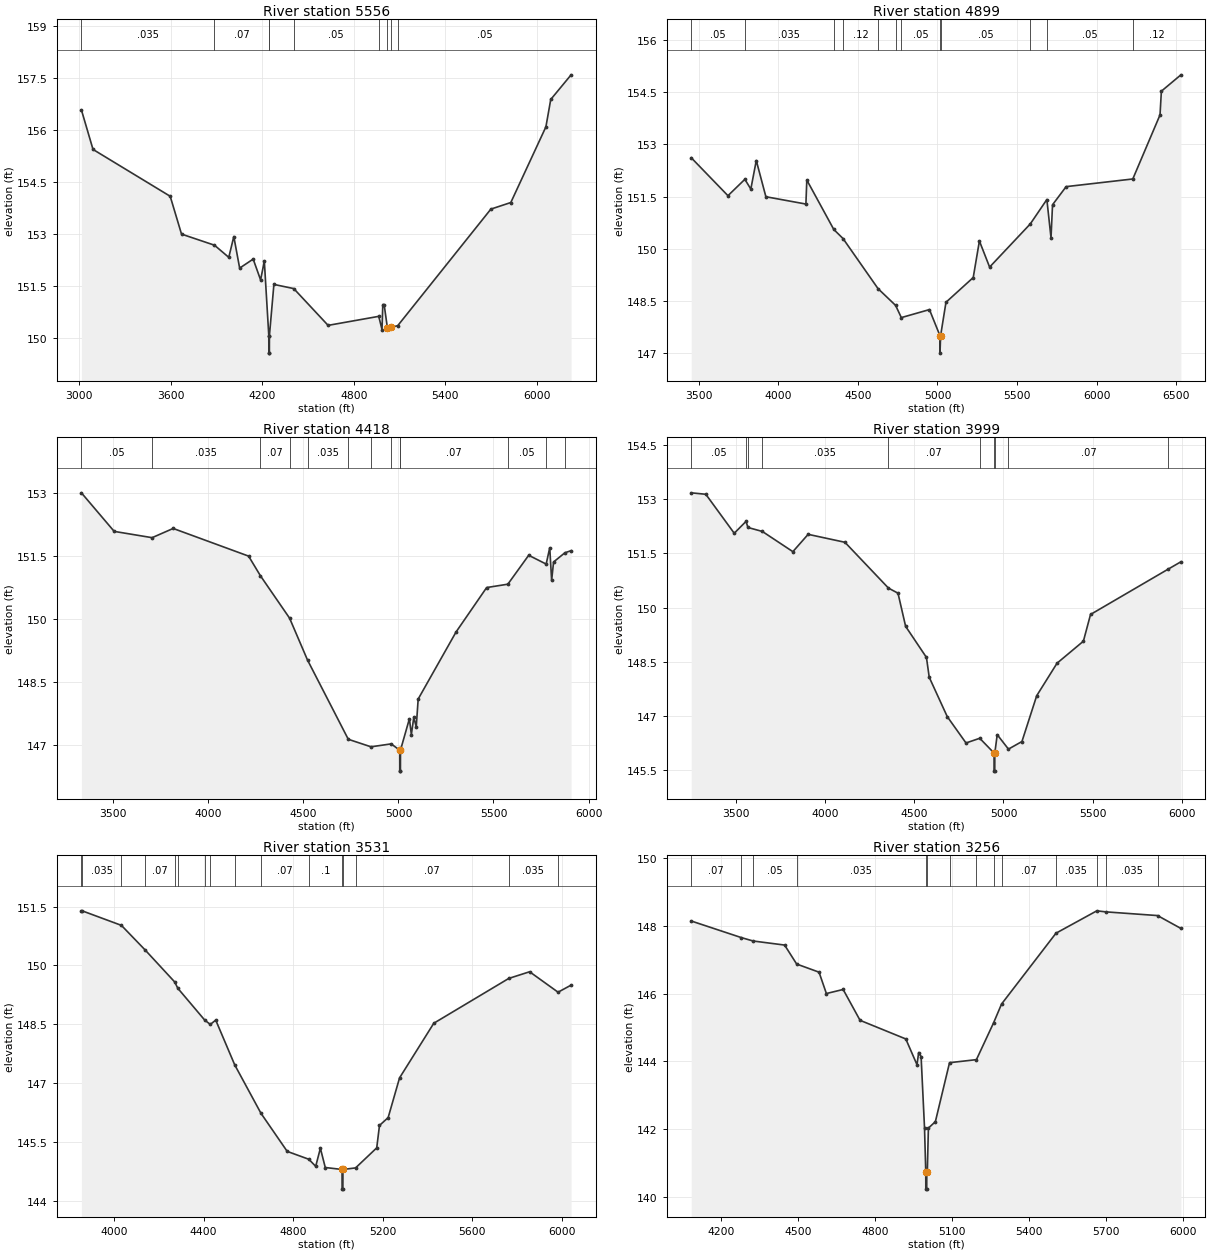
Type RM Length L Ch R = 1 ,5556    ,657,657,657
BEGIN DESCRIPTION:
Mapping XS 98986634
END DESCRIPTION:
XS GIS Cut Line= 4
      2515096.85     13454654.02      2514692.05     13453782.89
      2514398.06     13452807.18      2513239.19     13452397.75
#Sta/Elev= 30
  3015.4  156.58  3091.5  155.44  3597.2  154.09  3671.4     153  3887.4  152.68
  3981.1  152.33    4014  152.93  4052.3  152.02  4140.9  152.28  4189.5  151.68
    4214  152.22  4243.3  150.07  4243.6  149.57  4247.1  149.57  4247.3  150.07
  4276.7  151.55  4406.8  151.43  4631.8  150.37  4963.8  150.63    4985  150.25
  4990.2  150.97  4999.3  150.96  5020.7  150.29  5040.7  150.31  5087.9  150.36
  5698.3  153.72    5829  153.91  6058.9  156.09  6090.7  156.88  6224.1  157.59
#Mann= 9 ,-1 , 0
  3015.4    .035       0  3887.4     .07       0  4243.3    .035       0
  4247.3     .07       0  4406.8     .05       0  4963.8    .035       0
  5020.7    .035       0  5040.7    .035       0  5087.9     .05       0
Bank Sta=5020.7,5040.7
XS Rating Curve= 0 ,0
Exp/Cntr=0.3,0.1

Type RM Length L Ch R = 1 ,4899    ,481,481,481
BEGIN DESCRIPTION:
Mapping XS 7b467ffe
END DESCRIPTION:
XS GIS Cut Line= 4
      2516207.94     13453605.38      2515961.44     13453279.03
      2514960.56     13452737.73      2513529.99     13452203.01
#Sta/Elev= 30
  3454.3  152.62  3684.9  151.53    3791     152  3828.5  151.72  3862.7  152.54
    3923   151.5  4174.2  151.29  4179.9  151.98  4349.3  150.56  4407.2   150.3
  4627.3  148.86  4737.4  148.38  4773.2  148.03  4949.7  148.26  5015.8  147.51
    5016  147.01  5019.8  147.51  5053.5  148.47  5224.6  149.18  5263.3  150.23
  5327.4  149.48  5582.9  150.72  5686.8  151.42  5712.9  150.32  5722.4  151.27
  5807.8  151.79  6226.3  152.01  6397.2  153.85  6405.6  154.53  6528.4     155
#Mann= 12 ,-1 , 0
  3454.3     .05       0    3791    .035       0  4349.3     .07       0
  4407.2     .12       0  4627.3    .035       0  4737.4     .07       0
  4773.2     .05       0  5015.8     .05       0  5019.8     .05       0
  5582.9    .035       0  5686.8     .05       0  6226.3     .12       0
Bank Sta=5015.8,5019.8
XS Rating Curve= 0 ,0
Exp/Cntr=0.3,0.1

Type RM Length L Ch R = 1 ,4418    ,419,419,419
BEGIN DESCRIPTION:
Mapping XS ab38e68c
END DESCRIPTION:
XS GIS Cut Line= 5
      2516270.47     13453619.31      2516034.36      13453258.2
      2515266.12     13452411.34       2515106.4     13452321.07
       2514293.2     13452234.59
#Sta/Elev= 30
  3332.2  153.01  3504.6  152.09  3704.1  151.94    3815  152.16  4211.7   151.5
  4274.1  151.03  4427.3  150.02  4521.7  149.02  4736.1  147.13  4855.6  146.95
  4961.6  147.02  5006.7  146.87  5006.9  146.37  5010.4  146.37  5010.7  146.87
  5057.7  147.62  5067.9  147.24  5080.6  147.65  5093.7  147.43  5103.8  148.09
  5303.1  149.69    5464  150.75  5575.5  150.83  5685.2  151.52  5777.1  151.31
  5795.9   151.7  5805.9  150.92    5816  151.36  5875.7  151.58  5908.3  151.63
#Mann= 13 ,-1 , 0
  3332.2     .05       0  3704.1    .035       0  4274.1     .07       0
  4427.3     .12       0  4521.7    .035       0  4736.1     .07       0
  4855.6      .1       0  4961.6     .07       0  5006.7     .05       0
  5010.7     .07       0  5575.5     .05       0  5777.1    .035       0
  5875.7     .05       0
Bank Sta=5006.7,5010.7
XS Rating Curve= 0 ,0
Exp/Cntr=0.3,0.1

Type RM Length L Ch R = 1 ,3999    ,468,468,468
BEGIN DESCRIPTION:
TRIB 2 TO ROAD CREEK 7.0
END DESCRIPTION:
XS GIS Cut Line= 3
      2516325.01     13453625.02        2515425.       13452125.
      2514464.55      13451868.2
#Sta/Elev= 30
  3250.7  153.18  3332.4  153.14  3491.7  152.06  3557.9  152.39  3568.3  152.22
  3649.1  152.11  3820.2  151.55  3905.7  152.03  4111.8  151.81  4355.8  150.54
  4409.1   150.4  4451.9  149.48  4568.5  148.62  4584.1  148.07  4685.1  146.98
  4790.1  146.25  4867.1  146.38  4947.5  145.97  4947.7  145.47  4951.2  145.47
  4951.5  145.97    4965  146.48  5027.9  146.08  5103.5  146.29  5186.3  147.56
  5300.2  148.46  5447.8  149.07  5487.8  149.81  5924.2  151.07  5994.2  151.27
#Mann= 10 ,-1 , 0
  3250.7     .05       0  3557.9    .035       0  3568.3     .05       0
  3649.1    .035       0  4355.8     .07       0  4867.1      .1       0
  4947.5     .05       0  4951.5      .1       0  5027.9     .07       0
  5924.2    .035       0
Bank Sta=4947.5,4951.5
XS Rating Curve= 0 ,0
Exp/Cntr=0.3,0.1

Type RM Length L Ch R = 1 ,3531    ,275,275,275
BEGIN DESCRIPTION:
TRIB 2 TO ROAD CREEK 6.0
END DESCRIPTION:
XS GIS Cut Line= 3
       2516376.3     13452589.19        2515625.       13451725.
      2514603.42     13451525.44
#Sta/Elev= 30
  3854.6  151.39  3857.8  151.39  4033.2  151.02  4139.8  150.39  4271.1  149.58
  4284.9  149.42  4405.1  148.61    4430   148.5  4454.2  148.61  4539.1  147.47
  4656.1  146.24  4773.3  145.27  4869.7  145.07  4900.5  144.89  4921.4  145.35
  4943.2  144.86  5018.1  144.81  5018.3  144.31  5021.8  144.31  5022.1  144.81
  5078.5  144.85  5172.9  145.36  5185.2  145.93  5223.9  146.13  5274.8  147.14
  5427.6  148.53  5762.3  149.67  5855.4  149.84  5982.3  149.32  6040.6   149.5
#Mann= 16 ,-1 , 0
  3854.6     .07       0  3857.8    .035       0  4033.2     .05       0
  4139.8     .07       0  4271.1     .05       0  4284.9    .035       0
  4405.1     .05       0    4430     .07       0  4539.1    .035       0
  4656.1     .07       0  4869.7      .1       0  5018.1     .05       0
  5022.1      .1       0  5078.5     .07       0  5762.3    .035       0
  5982.3     .07       0
Bank Sta=5018.1,5022.1
XS Rating Curve= 0 ,0
Exp/Cntr=0.3,0.1

Type RM Length L Ch R = 1 ,3256    ,138,138,138
BEGIN DESCRIPTION:
TRIB 2 TO ROAD CREEK 5.0
END DESCRIPTION:
XS GIS Cut Line= 3
      2516611.26     13451984.17      2515808.02      13451541.6
      2514854.33     13451271.49
#Sta/Elev= 30
  4082.9  148.14  4278.3  147.65  4324.1  147.55  4446.8  147.43  4493.8  146.87
    4581  146.63  4609.6     146  4674.9  146.12  4740.8  145.21  4919.1  144.66
  4962.7   143.9  4969.2  144.26  4978.7  144.14    4992  142.04  4996.9  140.73
  4997.1  140.23  5000.6  140.23  5000.9  140.73  5002.9  140.73  5007.1  142.03
  5034.3  142.22  5089.5  143.96  5194.3  144.05  5261.4  145.14  5292.2  145.69
  5504.3  147.78  5663.5  148.44  5697.5  148.41  5900.2   148.3  5991.2  147.92
#Mann= 14 ,-1 , 0
  4082.9     .07       0  4278.3    .035       0  4324.1     .05       0
  4493.8    .035       0  4996.9    .035       0  5000.9    .035       0
  5089.5      .1       0  5194.3     .07       0  5261.4    .035       0
  5292.2     .07       0  5504.3    .035       0  5663.5     .07       0
  5697.5    .035       0  5900.2     .07       0
Bank Sta=4996.9,5000.9
XS Rating Curve= 0 ,0
Exp/Cntr=0.3,0.1

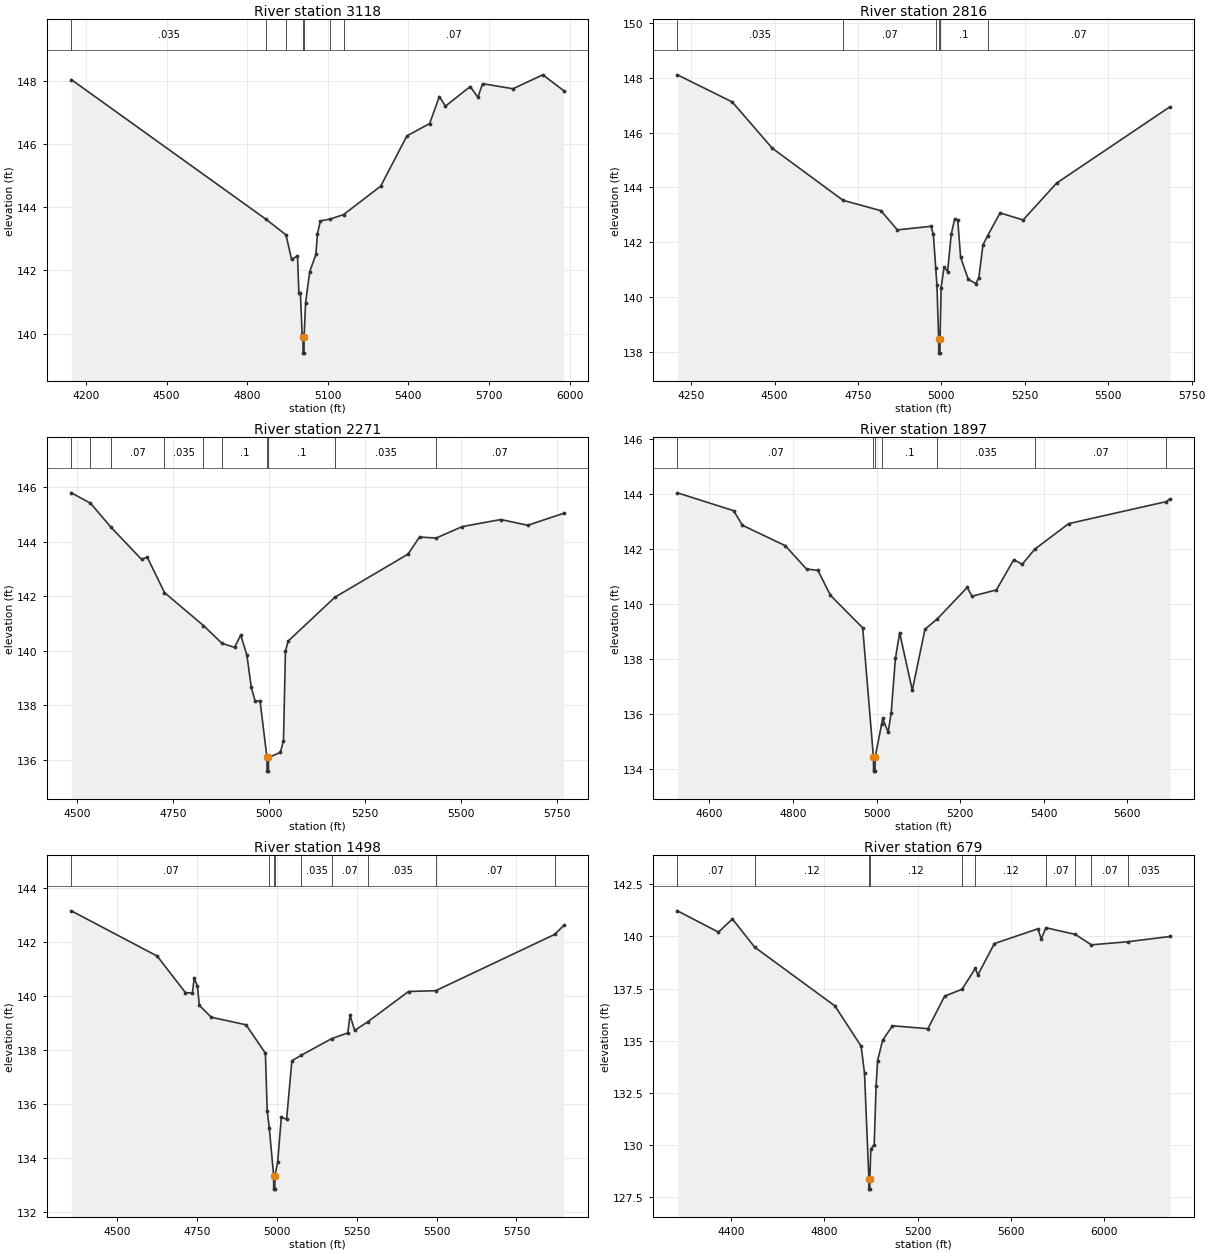
Type RM Length L Ch R = 1 ,3118    ,302,302,302
BEGIN DESCRIPTION:
Mapping XS 7d2a08c5
END DESCRIPTION:
XS GIS Cut Line= 4
      2516630.35     13451815.76      2515875.12     13451425.12
       2515237.1     13451133.46      2514957.52      13451099.8
#Sta/Elev= 30
    4145  148.03  4870.4  143.61  4944.3  143.12  4965.1  142.35  4987.2  142.45
  4992.5  141.27  4998.1  141.27  5004.3     140  5007.7  139.88    5008  139.38
  5011.5  139.38  5011.7  139.88  5017.4  140.98  5032.8  141.96  5055.7   142.5
  5061.4  143.15  5072.4  143.56  5109.1  143.62  5158.8  143.76    5297  144.66
  5394.6  146.25  5479.2  146.64  5515.2  147.49  5538.2  147.19  5630.3  147.81
  5658.8  147.47  5676.3   147.9  5789.6  147.74  5900.4  148.18  5978.4  147.68
#Mann= 7 ,-1 , 0
    4145    .035       0  4870.4     .07       0  4944.3      .1       0
  5007.7     .05       0  5011.7      .1       0  5109.1    .035       0
  5158.8     .07       0
Bank Sta=5007.7,5011.7
XS Rating Curve= 0 ,0
Exp/Cntr=0.3,0.1

Type RM Length L Ch R = 1 ,2816    ,545,545,545
BEGIN DESCRIPTION:
Mapping XS d4b87088
END DESCRIPTION:
XS GIS Cut Line= 4
      2516675.84     13451786.34      2516148.06      13451279.4
      2516036.95     13451237.73      2515442.84     13451042.31
#Sta/Elev= 30
  4208.7  148.11    4373  147.12  4493.1  145.43    4705  143.53  4818.6  143.15
    4868  142.45  4968.9  142.58  4975.8  142.29  4982.9  141.06  4986.5  140.43
  4991.8  138.45    4992  137.95  4995.5  137.95  4995.8  138.45  4999.1  140.34
  5007.9  141.09  5018.5  140.93  5029.4  142.29  5039.9  142.86    5049   142.8
  5057.5  141.45  5080.5  140.64  5103.3  140.49  5112.3  140.71  5124.4   141.9
  5138.2  142.23  5175.8  143.07  5244.7  142.81  5345.5  144.16  5684.6  146.94
#Mann= 6 ,-1 , 0
  4208.7    .035       0    4705     .07       0  4982.9      .1       0
  4991.8     .05       0  4995.8      .1       0  5138.2     .07       0
Bank Sta=4991.8,4995.8
XS Rating Curve= 0 ,0
Exp/Cntr=0.3,0.1

Type RM Length L Ch R = 1 ,2271    ,374,374,374
BEGIN DESCRIPTION:
TRIB 2 TO ROAD CREEK 3.0
END DESCRIPTION:
XS GIS Cut Line= 3
      2516824.98     13451124.99        2516375.       13450875.
      2515612.12      13450781.9
#Sta/Elev= 30
  4485.2   145.8  4535.2  145.42  4587.9  144.55  4668.2  143.36  4683.1  143.44
  4728.1  142.14  4829.6  140.93  4877.8  140.28  4910.7  140.13  4926.7  140.58
  4942.8  139.85  4954.2  138.67  4964.5  138.15  4977.1  138.17  4995.1  136.09
  4995.4  135.59  4998.9  135.59  4999.1  136.09  5030.2  136.28  5038.2  136.71
  5043.3  139.99  5050.3  140.36  5172.2  141.97  5362.6  143.55  5392.9  144.18
    5436  144.14  5503.7  144.56  5604.4  144.82  5674.9  144.61  5768.5  145.05
#Mann= 10 ,-1 , 0
  4485.2     .07       0  4535.2    .035       0  4587.9     .07       0
  4728.1    .035       0  4829.6     .07       0  4877.8      .1       0
  4995.1     .05       0  4999.1      .1       0  5172.2    .035       0
    5436     .07       0
Bank Sta=4995.1,4999.1
XS Rating Curve= 0 ,0
Exp/Cntr=0.3,0.1

Type RM Length L Ch R = 1 ,1897    ,399,399,399
BEGIN DESCRIPTION:
Mapping XS b04e05e3
END DESCRIPTION:
XS GIS Cut Line= 3
      2516982.85     13450813.83      2516614.82     13450570.79
      2515885.68      13450681.9
#Sta/Elev= 30
  4523.2  144.05  4657.8   143.4  4678.9  142.87  4781.2  142.13  4832.2  141.28
  4859.5  141.23  4889.6  140.32  4966.7  139.14  4992.4  134.43  4992.7  133.93
  4996.2  133.93  4996.4  134.43  5012.1  135.65  5014.6  135.85  5027.6  135.34
  5034.9  136.05    5045  138.03  5055.1  138.96  5085.4  136.87  5115.8  139.09
  5145.4  139.47  5216.9  140.61  5228.3  140.29  5286.8  140.52  5328.2  141.62
  5348.4  141.45  5378.5     142  5459.7  142.93  5693.2  143.73  5701.8  143.83
#Mann= 7 ,-1 , 0
  4523.2     .07       0  4992.4     .05       0  4996.4     .07       0
  5012.1      .1       0  5145.4    .035       0  5378.5     .07       0
  5693.2    .035       0
Bank Sta=4992.4,4996.4
XS Rating Curve= 0 ,0
Exp/Cntr=0.3,0.1

Type RM Length L Ch R = 1 ,1498    ,819,819,819
BEGIN DESCRIPTION:
Mapping XS 91b5f2cc
END DESCRIPTION:
XS GIS Cut Line= 4
      2517076.96     13450749.25      2516839.11     13450327.49
      2516574.31     13450190.19       2515908.7     13450557.25
#Sta/Elev= 30
  4355.5  143.14  4624.4  141.47  4713.1  140.12  4734.8   140.1  4740.5  140.65
  4750.7  140.36  4756.5  139.65    4794  139.21  4902.9  138.93  4963.6  137.88
  4969.2  135.76  4975.9   135.1  4989.4  133.36  4989.6  132.86  4993.1  132.86
  4993.4  133.36    5002  133.86  5013.5  135.52    5030  135.44  5046.5   137.6
  5076.6  137.81  5171.4  138.42  5221.6  138.63  5228.6  139.28  5243.4  138.72
  5285.4  139.05  5411.9  140.16  5497.2  140.19  5869.9  142.27  5898.1   142.6
#Mann= 9 ,-1 , 0
  4355.5     .07       0  4975.9      .1       0  4989.4     .05       0
  4993.4      .1       0  5076.6    .035       0  5171.4     .07       0
  5285.4    .035       0  5497.2     .07       0  5869.9    .035       0
Bank Sta=4989.4,4993.4
XS Rating Curve= 0 ,0
Exp/Cntr=0.3,0.1

Type RM Length L Ch R = 1 ,679     ,0,0,0
BEGIN DESCRIPTION:
Mapping XS 23f3435e
END DESCRIPTION:
XS GIS Cut Line= 4
      2517363.81       13450531.       2517358.9     13449846.93
      2517108.82     13449648.33      2516225.84     13450319.75
#Sta/Elev= 30
  4169.3  141.23  4345.3  140.21  4405.3  140.84  4500.7  139.49  4845.3  136.67
  4957.6  134.74    4972  133.45  4990.8  128.39  4991.1  127.89  4994.6  127.89
  4994.8  128.39  4999.2  129.81  5013.6  130.02  5021.7  132.81  5028.1  134.05
  5049.9  135.03  5092.1  135.72  5244.1  135.58  5315.7  137.14  5390.5  137.47
  5447.5  138.47  5458.3  138.16  5529.3  139.66  5716.1  140.37  5730.3  139.88
  5750.1  140.42  5876.3   140.1  5945.4   139.6  6102.5  139.75    6282     140
#Mann= 10 ,-1 , 0
  4169.3     .07       0  4500.7     .12       0  4990.8     .05       0
  4994.8     .12       0  5390.5     .07       0  5447.5     .12       0
  5750.1     .07       0  5876.3    .035       0  5945.4     .07       0
  6102.5    .035       0
Bank Sta=4990.8,4994.8
XS Rating Curve= 0 ,0
Exp/Cntr=0.3,0.1

Chan Stop Cuts=-1
Use User Specified Reach Order=0
Composite Channel Slope=5