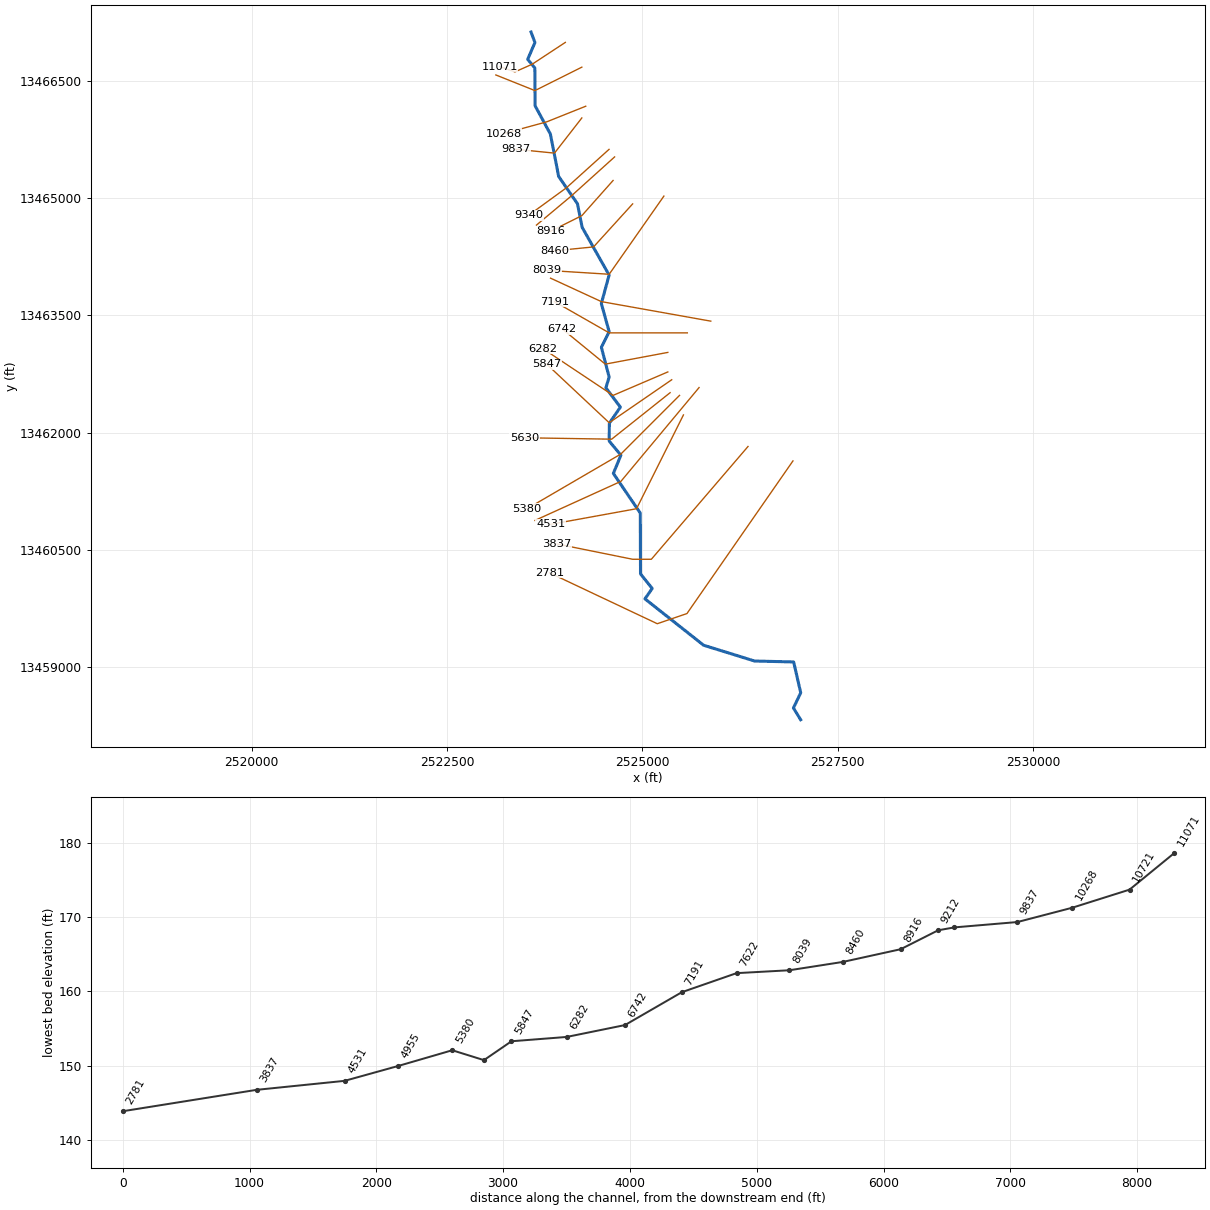
--- TRIB 2 TO SULPHUR CREEK.prj (project) ---

Proj Title=TRIB 2 TO SULPHUR CREEK Base Level Engineering
Current Plan=p01
Default Exp/Contr=0.3,0.1
English Units
Geom File=g01
Flow File=f01
Plan File=p01
Y Axis Title=Elevation
X Axis Title(PF)=Main Channel Distance
X Axis Title(XS)=Station
BEGIN DESCRIPTION:
TRIB 2 TO SULPHUR CREEK
END DESCRIPTION:
DSS Export Rating Curves= 0
DSS Export Rating Curve Sorted= 0
DSS Export Volume Flow Curves= 0
DXF OffsetX= 0
DXF OffsetY= 0
DXF ScaleX= 1
DXF ScaleY= 10

--- TRIB 2 TO SULPHUR CREEK.p01 (plan) ---

Plan Title=Multiple Run
Short Identifier=Multiple
Geom File=g01
Flow File=f01
Subcritical Flow
K Sum by GR= 0
Std Step Tol= 0.01
Critical Tol= 0.01
Num of Std Step Trials= 20
Max Error Tol= 0.3
Flow Tol Ratio= 0.001
Split Flow NTrial= 30
Split Flow Tol= 0.02
Split Flow Ratio= 0.02
Log Output Level= 0
Friction Slope Method= 1
Unsteady Friction Slope Method= 2
Unsteady Bridges Friction Slope Method= 1
Parabolic Critical Depth
Global Vel Dist=  1 , 1 , 1
Global Log Level= 0
CheckData=True
Encroach Param= -1, 0, 0, 0
BEGIN DESCRIPTION:
Multiple Run
END DESCRIPTION:

--- TRIB 2 TO SULPHUR CREEK.f01 (steady flow) ---

Flow Title=Multiple
Number of Profiles=7
Profile Names=10-year,25-year,50-year,1pct_min,100-year,1pct_plu,500-year
River Rch & RM= TRIB 2 TO SULPHU,Reach-1,11071
     391     599     777     488     974    1943    1512
River Rch & RM= TRIB 2 TO SULPHU,Reach-1,10721
     672    1067    1417     909    1814    3620    2943
River Rch & RM= TRIB 2 TO SULPHU,Reach-1,5630
     986    1597    2148    1396    2785    5556    4630
Boundary for River Rch & Prof#=TRIB 2 TO SULPHU,Reach-1,1
Up Type=0
Dn Type=3
Dn Slope=0.005
Boundary for River Rch & Prof#=TRIB 2 TO SULPHU,Reach-1,2
Up Type=0
Dn Type=3
Dn Slope=0.005
Boundary for River Rch & Prof#=TRIB 2 TO SULPHU,Reach-1,3
Up Type=0
Dn Type=3
Dn Slope=0.005
Boundary for River Rch & Prof#=TRIB 2 TO SULPHU,Reach-1,4
Up Type=0
Dn Type=3
Dn Slope=0.005
Boundary for River Rch & Prof#=TRIB 2 TO SULPHU,Reach-1,5
Up Type=0
Dn Type=3
Dn Slope=0.005
Boundary for River Rch & Prof#=TRIB 2 TO SULPHU,Reach-1,6
Up Type=0
Dn Type=3
Dn Slope=0.005
Boundary for River Rch & Prof#=TRIB 2 TO SULPHU,Reach-1,7
Up Type=0
Dn Type=3
Dn Slope=0.005

--- TRIB 2 TO SULPHUR CREEK.g01 (geometry) ---

Geom Title=Existing Conditions
Program Version=4.10

River Reach=TRIB 2 TO SULPHU,Reach-1
Reach XY= 30
        2523575.       13467125.      2523624.95     13466990.39
      2523532.33      13466774.9      2523623.94     13466664.57
      2523627.06     13466180.86      2523822.73     13465819.06
      2523928.62      13465276.5      2524169.16     13464927.29
      2524228.55     13464626.47      2524574.06     13464014.51
      2524474.69     13463650.04      2524574.92     13463290.39
      2524475.09      13463090.4      2524574.61     13462709.72
      2524532.81     13462571.59      2524717.91       13462325.
      2524577.24     13462119.07      2524575.38     13461890.16
      2524725.11     13461709.64      2524628.46      13461476.5
      2524972.94     13460969.14      2524975.92     13460190.94
      2525125.47     13460004.84       2525032.6     13459871.66
      2525783.35     13459278.19      2526435.55      13459076.1
      2526935.39     13459064.25      2527025.81     13458669.97
      2526932.48       13458475.        2527025.       13458325.

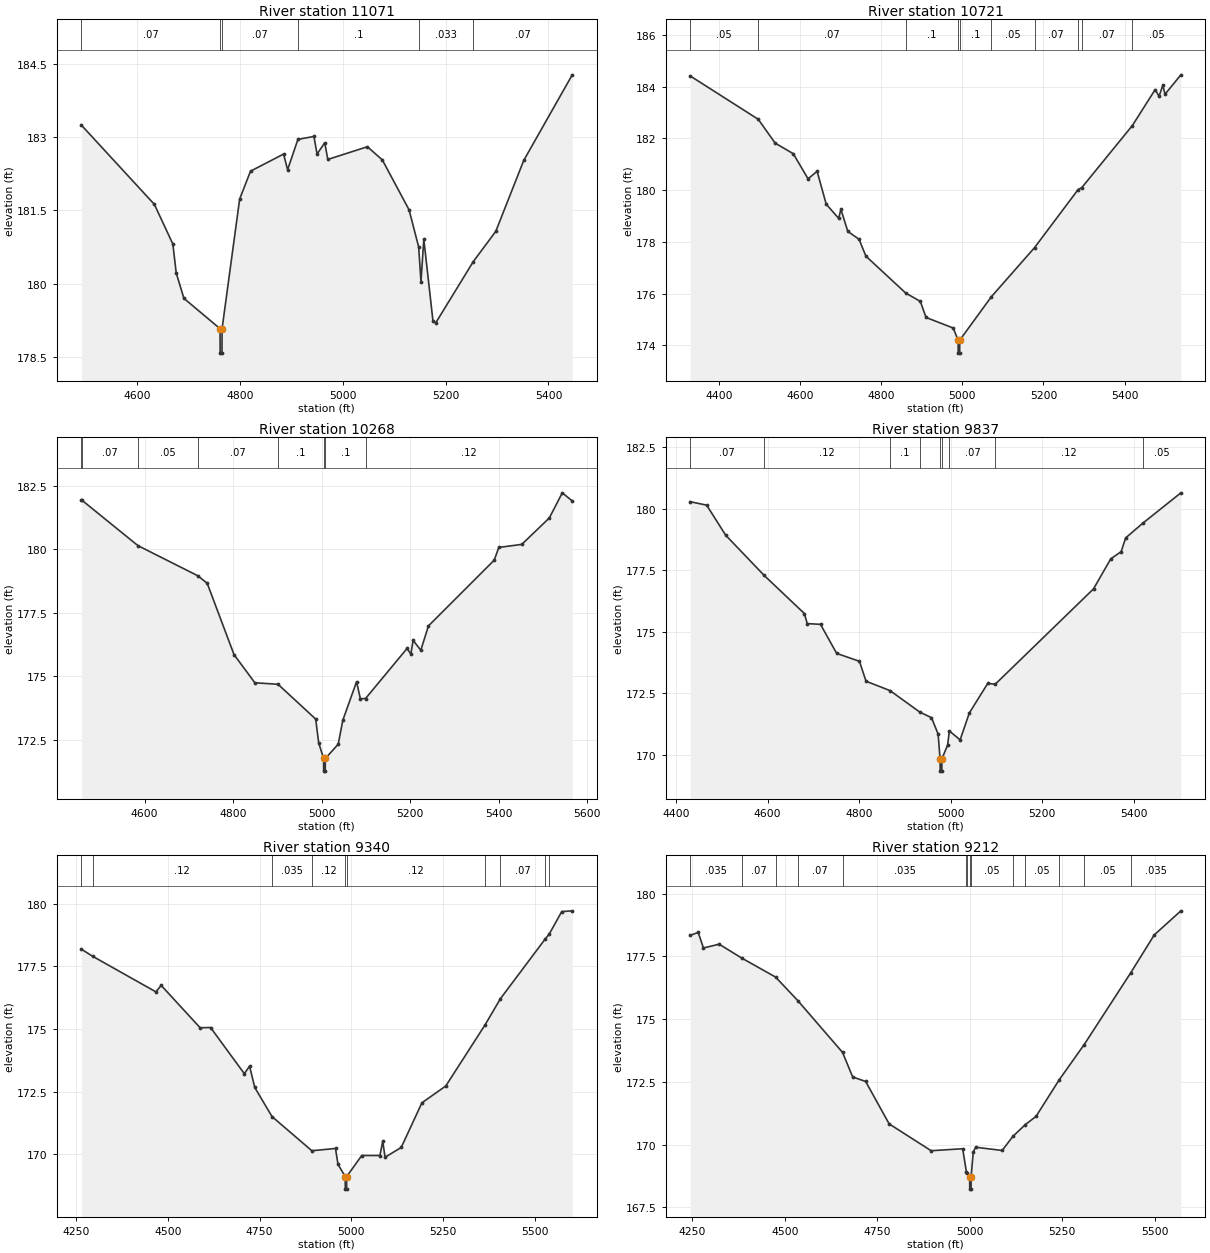
Type RM Length L Ch R = 1 ,11071   ,350,350,350
BEGIN DESCRIPTION:
TRIB 2 TO SULPHUR CREEK 17.0
END DESCRIPTION:
XS GIS Cut Line= 4
      2524013.62     13466991.61      2523588.52     13466711.84
      2523368.85     13466614.24       2523174.6     13466682.61
#Sta/Elev= 30
  4491.1  183.24  4633.1  181.62    4669  180.81  4675.5  180.22  4690.5   179.7
  4760.8  179.08  4761.1  178.58  4764.6  178.58  4764.8  179.08    4799  181.73
  4820.1   182.3  4884.5  182.65  4892.3  182.33  4912.4  182.95  4943.6  183.01
  4949.6  182.65  4964.6  182.88  4970.6  182.54  5047.6   182.8  5076.7  182.53
  5128.7  181.51  5147.4  180.75  5151.9  180.04  5157.4  180.91  5175.2  179.24
  5180.7   179.2  5253.6  180.45  5297.5  181.07  5351.9  182.52  5446.3  184.27
#Mann= 6 ,-1 , 0
  4491.1     .07       0  4760.8     .05       0  4764.8     .07       0
  4912.4      .1       0  5147.4    .033       0  5253.6     .07       0
Bank Sta=4760.8,4764.8
XS Rating Curve= 0 ,0
Exp/Cntr=0.3,0.1

Type RM Length L Ch R = 1 ,10721   ,453,453,453
BEGIN DESCRIPTION:
TRIB 2 TO SULPHUR CREEK 16.0
END DESCRIPTION:
XS GIS Cut Line= 3
      2524224.97     13466674.99        2523625.       13466375.
      2523125.01       13466575.
#Sta/Elev= 30
  4329.2  184.42  4497.2  182.74  4538.8  181.82  4583.5  181.41  4619.9  180.44
  4642.2  180.73  4664.6  179.46  4695.3  178.91  4700.9  179.26  4717.7  178.41
  4745.6   178.1  4762.4  177.45  4860.7  176.02  4896.6   175.7  4910.5  175.08
  4977.6  174.67  4989.6   174.2  4989.9   173.7  4993.4   173.7  4993.6   174.2
    5071  175.87    5178  177.78  5285.1  180.02  5294.4   180.1    5419   182.5
  5475.2  183.89  5484.7  183.63  5494.1  184.06  5499.5  183.71  5538.5  184.46
#Mann= 10 ,-1 , 0
  4329.2     .05       0  4497.2     .07       0  4860.7      .1       0
  4989.6     .05       0  4993.6      .1       0    5071     .05       0
    5178     .07       0  5285.1     .05       0  5294.4     .07       0
    5419     .05       0
Bank Sta=4989.6,4993.6
XS Rating Curve= 0 ,0
Exp/Cntr=0.3,0.1

Type RM Length L Ch R = 1 ,10268   ,431,431,431
BEGIN DESCRIPTION:
TRIB 2 TO SULPHUR CREEK 15.0
END DESCRIPTION:
XS GIS Cut Line= 3
      2524274.98     13466174.99        2523775.       13465975.
      2523224.98     13465824.99
#Sta/Elev= 30
  4457.3  181.92    4459  181.92  4584.9  180.14  4719.5  178.96  4741.3  178.66
  4801.9  175.85    4849  174.74  4901.3  174.68  4986.4  173.31  4993.1  172.38
  5004.2  171.76  5004.4  171.26  5007.9  171.26  5008.2  171.76  5037.3  172.32
  5047.6  173.26  5078.7  174.78  5087.3  174.11    5099  174.12  5192.7  176.09
  5201.4  175.87  5206.5  176.41  5223.8  176.02  5241.1  176.98  5389.7  179.57
    5400  180.07  5451.9  180.19  5514.1  181.23  5543.4  182.22  5565.9   181.9
#Mann= 8 ,-1 , 0
  4457.3     .12       0    4459     .07       0  4584.9     .05       0
  4719.5     .07       0  4901.3      .1       0  5004.2     .05       0
  5008.2      .1       0    5099     .12       0
Bank Sta=5004.2,5008.2
XS Rating Curve= 0 ,0
Exp/Cntr=0.3,0.1

Type RM Length L Ch R = 1 ,9837    ,497,497,497
BEGIN DESCRIPTION:
TRIB 2 TO SULPHUR CREEK 14.0
END DESCRIPTION:
XS GIS Cut Line= 3
      2524224.97     13466024.97        2523875.       13465575.
      2523375.04       13465625.
#Sta/Elev= 30
  4430.6  180.28  4466.8  180.14  4508.4  178.92  4592.3  177.29  4680.3  175.74
  4686.6  175.33  4715.6   175.3  4750.9  174.12  4800.7   173.8  4815.1  172.99
  4867.5  172.61  4932.4  171.74  4958.1  171.51  4972.6  170.85  4976.9  169.84
  4977.2  169.34  4980.7  169.34  4980.9  169.84  4993.4   170.4  4997.2  170.97
  5020.7  170.61  5040.8   171.7    5081   172.9  5097.5  172.87  5312.2  176.74
  5349.9  177.96  5372.5  178.25  5382.5  178.81  5420.1  179.41  5503.1  180.64
#Mann= 9 ,-1 , 0
  4430.6     .07       0  4592.3     .12       0  4867.5      .1       0
  4932.4     .12       0  4976.9     .05       0  4980.9     .12       0
  4997.2     .07       0  5097.5     .12       0  5420.1     .05       0
Bank Sta=4976.9,4980.9
XS Rating Curve= 0 ,0
Exp/Cntr=0.3,0.1

Type RM Length L Ch R = 1 ,9340    ,128,128,128
BEGIN DESCRIPTION:
TRIB 2 TO SULPHUR CREEK 13.0
END DESCRIPTION:
XS GIS Cut Line= 3
      2524573.21     13465623.28      2524027.71     13465131.12
      2523541.84     13464777.39
#Sta/Elev= 30
  4265.3  178.18  4295.6   177.9    4468  176.48  4482.2  176.74  4588.3  175.05
  4616.7  175.06  4708.6  173.22  4722.8  173.52    4737  172.67    4784  171.51
  4892.3  170.15  4956.7  170.24  4963.4  169.61  4983.1  169.12  4983.4  168.62
  4986.9  168.62  4987.1  169.12  5028.1  169.96  5077.6  169.96  5085.3  170.53
  5091.5  169.89  5135.5  170.28  5191.9  172.06  5256.8  172.73  5363.5  175.16
  5405.6  176.21    5528   178.6  5537.8  178.77  5572.4  179.68    5601  179.71
#Mann= 10 ,-1 , 0
  4265.3    .035       0  4295.6     .12       0    4784    .035       0
  4892.3     .12       0  4983.1     .05       0  4987.1     .12       0
  5363.5     .05       0  5405.6     .07       0    5528    .035       0
  5537.8     .12       0
Bank Sta=4983.1,4987.1
XS Rating Curve= 0 ,0
Exp/Cntr=0.3,0.1

Type RM Length L Ch R = 1 ,9212    ,296,296,296
BEGIN DESCRIPTION:
Mapping XS 667f0d93
END DESCRIPTION:
XS GIS Cut Line= 3
      2524644.38      13465526.4      2524087.12     13465023.82
      2523644.45     13464654.06
#Sta/Elev= 30
  4243.6  178.34  4265.5  178.46  4279.7  177.84  4322.3  177.99    4383  177.44
  4474.8  176.68    4535  175.74  4655.8  173.68  4683.3   172.7  4718.4  172.52
  4781.9  170.83  4895.5  169.76  4980.7  169.84  4990.8  168.92  4991.2  168.86
  4999.6  168.73  4999.9  168.23  5003.4  168.23  5003.6  168.73  5009.4  169.71
  5015.9   169.9  5087.5  169.77  5116.4  170.33  5150.1   170.8  5179.2  171.13
  5241.5  172.58  5309.3  173.99  5434.7  176.84  5498.8  178.36  5570.8  179.32
#Mann= 14 ,-1 , 0
  4243.6    .035       0    4383     .07       0  4474.8    .035       0
    4535     .07       0  4655.8    .035       0  4990.8     .07       0
  4991.2     .05       0  4999.6     .05       0  5003.6     .05       0
  5116.4    .035       0  5150.1     .05       0  5241.5    .035       0
  5309.3     .05       0  5434.7    .035       0
Bank Sta=4999.6,5003.6
XS Rating Curve= 0 ,0
Exp/Cntr=0.3,0.1

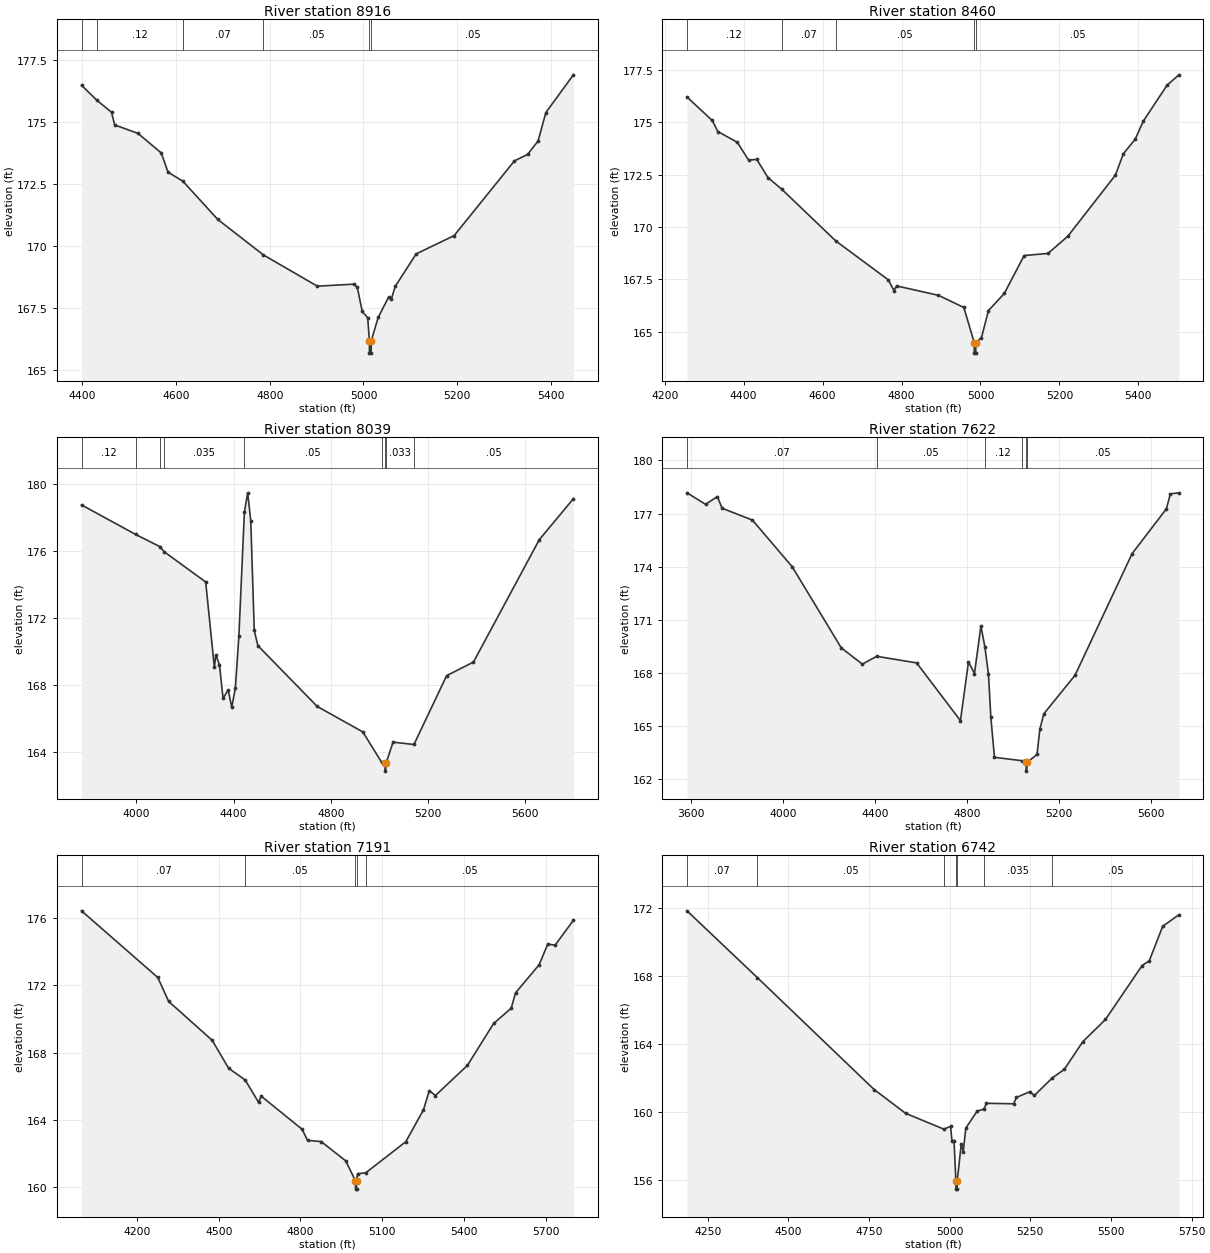
Type RM Length L Ch R = 1 ,8916    ,456,456,456
BEGIN DESCRIPTION:
TRIB 2 TO SULPHUR CREEK 12.0
END DESCRIPTION:
XS GIS Cut Line= 3
      2524625.02     13465225.02        2524225.       13464775.
      2523825.02     13464575.01
#Sta/Elev= 30
  4398.5  176.48  4431.5  175.87  4462.5  175.39  4469.2  174.88  4518.9  174.54
  4568.7  173.75  4582.9  172.98  4614.8  172.61  4689.1  171.07  4786.5  169.64
  4901.5  168.38  4979.3  168.46  4986.8  168.34  4997.3  167.36    5009  167.11
  5012.6  166.18  5012.8  165.68  5016.3  165.68  5016.6  166.18  5031.4  167.12
  5053.7  167.94  5059.3  167.85  5067.7  168.37  5112.4  169.68  5193.5  170.42
    5322  173.43    5350  173.69  5372.4  174.23  5389.1  175.38  5447.8   176.9
#Mann= 6 ,-1 , 0
  4398.5     .07       0  4431.5     .12       0  4614.8     .07       0
  4786.5     .05       0  5012.6     .05       0  5016.6     .05       0
Bank Sta=5012.6,5016.6
XS Rating Curve= 0 ,0
Exp/Cntr=0.3,0.1

Type RM Length L Ch R = 1 ,8460    ,421,421,421
BEGIN DESCRIPTION:
TRIB 2 TO SULPHUR CREEK 11.0
END DESCRIPTION:
XS GIS Cut Line= 3
      2524875.01     13464925.01        2524375.       13464375.
      2523875.01       13464325.
#Sta/Elev= 30
  4256.7   176.2  4320.6  175.08  4334.8  174.55  4384.1  174.04  4412.5  173.19
  4433.4  173.22  4461.8  172.35  4496.5   171.8  4633.3  169.33  4766.5  167.47
  4780.7  166.96  4787.5  167.18  4893.6  166.73  4957.8  166.15  4984.2  164.47
  4984.4  163.97  4987.9  163.97  4988.2  164.47  5002.5  164.71  5020.1     166
  5060.3  166.82  5110.6  168.63  5170.9  168.73  5221.1  169.55  5341.7  172.47
  5361.8  173.49    5392  174.19  5412.1  175.04  5472.4  176.76  5502.5  177.26
#Mann= 5 ,-1 , 0
  4256.7     .12       0  4496.5     .07       0  4633.3     .05       0
  4984.2     .05       0  4988.2     .05       0
Bank Sta=4984.2,4988.2
XS Rating Curve= 0 ,0
Exp/Cntr=0.3,0.1

Type RM Length L Ch R = 1 ,8039    ,417,417,417
BEGIN DESCRIPTION:
TRIB 2 TO SULPHUR CREEK 10.0
END DESCRIPTION:
XS GIS Cut Line= 3
      2525274.99     13465024.99        2524575.       13464025.
      2523775.01       13464075.
#Sta/Elev= 30
    3775  178.74    3997  176.98  4096.9  176.25  4115.1  175.94  4285.5  174.14
  4321.2  169.04  4327.3   169.8  4342.2  169.19    4357  167.19  4377.9   167.7
  4392.7  166.66  4407.6  167.82  4421.9  170.89  4444.6  178.29  4458.1  179.46
  4470.8   177.8  4485.2  171.25    4500  170.34  4744.1  166.71  4931.6  165.19
  5009.1  163.37  5023.7  163.35    5024  162.85  5027.7  163.35  5055.8  164.58
  5141.6  164.44  5276.2  168.55  5386.4  169.36  5656.9  176.66  5797.2  179.11
#Mann= 9 ,-1 , 0
    3775     .12       0    3997    .035       0  4096.9     .12       0
  4115.1    .035       0  4444.6     .05       0  5009.1    .033       0
  5023.7     .05       0  5027.7    .033       0  5141.6     .05       0
Bank Sta=5023.7,5027.7
XS Rating Curve= 0 ,0
Exp/Cntr=0.3,0.1

Type RM Length L Ch R = 1 ,7622    ,431,431,431
BEGIN DESCRIPTION:
TRIB 2 TO SULPHUR CREEK 9.0
END DESCRIPTION:
XS GIS Cut Line= 3
        2525875.       13463425.        2524475.       13463675.
      2523825.03     13463974.99
#Sta/Elev= 30
    3582  178.17  3662.8  177.52  3714.1  177.96  3734.4   177.3  3866.4  176.63
  4039.1     174  4252.4  169.42  4343.9   168.5  4406.6  168.94    4580  168.57
  4770.5  165.31  4805.5  168.63  4831.5  167.97  4859.4  170.65  4876.7  169.48
  4892.4  167.92  4902.6   165.5  4918.3  163.24  5036.7  163.05  5056.7  162.96
    5057  162.46  5060.8  162.96  5103.3   163.4  5115.7  164.83  5133.1   165.7
  5268.5  167.87  5516.7  174.74  5665.4  177.26  5682.9  178.11    5720  178.17
#Mann= 6 ,-1 , 0
    3582     .07       0  4406.6     .05       0  4876.7     .12       0
  5036.7     .05       0  5056.7     .05       0  5060.8     .05       0
Bank Sta=5056.7,5060.8
XS Rating Curve= 0 ,0
Exp/Cntr=0.3,0.1

Type RM Length L Ch R = 1 ,7191    ,449,449,449
BEGIN DESCRIPTION:
TRIB 2 TO SULPHUR CREEK 8.0
END DESCRIPTION:
XS GIS Cut Line= 3
      2525575.01       13463275.        2524575.       13463275.
      2523875.03     13463674.98
#Sta/Elev= 30
  3996.2   176.4  4276.2  172.45  4316.2  171.03  4476.2  168.72  4536.2  167.07
  4597.2  166.37  4646.2  165.05  4656.2  165.41  4806.2  163.45  4826.2  162.79
  4876.2  162.72  4966.2  161.58    5002   160.4  5002.3   159.9    5006   159.9
  5006.3   160.4  5009.9  160.81  5040.1  160.87    5187  162.71  5251.8   164.6
  5273.4  165.74  5295.7  165.45    5413  167.23  5509.5  169.72  5574.2  170.63
  5590.1  171.54  5676.5   173.2  5708.1  174.42  5735.5  174.37  5802.4  175.84
#Mann= 5 ,-1 , 0
  3996.2     .07       0  4597.2     .05       0    5002     .05       0
  5006.3     .05       0  5040.1     .05       0
Bank Sta=5002,5006.3
XS Rating Curve= 0 ,0
Exp/Cntr=0.3,0.1

Type RM Length L Ch R = 1 ,6742    ,460,460,460
BEGIN DESCRIPTION:
TRIB 2 TO SULPHUR CREEK 7.0
END DESCRIPTION:
XS GIS Cut Line= 3
      2525324.96     13463024.99        2524525.       13462875.
      2523975.02     13463324.98
#Sta/Elev= 30
    4186  171.84  4404.1  167.91  4765.9  161.33  4863.4  159.93  4981.8     159
  5003.1  159.16  5007.1   158.3  5013.5  158.33  5019.3  155.97  5019.6  155.47
  5023.3  155.47  5023.6  155.97  5035.8   158.1  5042.2  157.68  5050.1  159.06
  5085.3  160.06  5106.3  160.18    5114  160.52  5198.7  160.49  5206.6  160.86
  5248.3   161.2  5262.6  160.98  5318.6  162.02  5355.2  162.51  5412.6  164.14
    5483  165.45  5596.4  168.62  5618.7   168.9  5660.3  170.93  5710.5  171.61
#Mann= 7 ,-1 , 0
    4186     .07       0  4404.1     .05       0  4981.8      .1       0
  5019.3     .05       0  5023.6      .1       0  5106.3    .035       0
  5318.6     .05       0
Bank Sta=5019.3,5023.6
XS Rating Curve= 0 ,0
Exp/Cntr=0.3,0.1

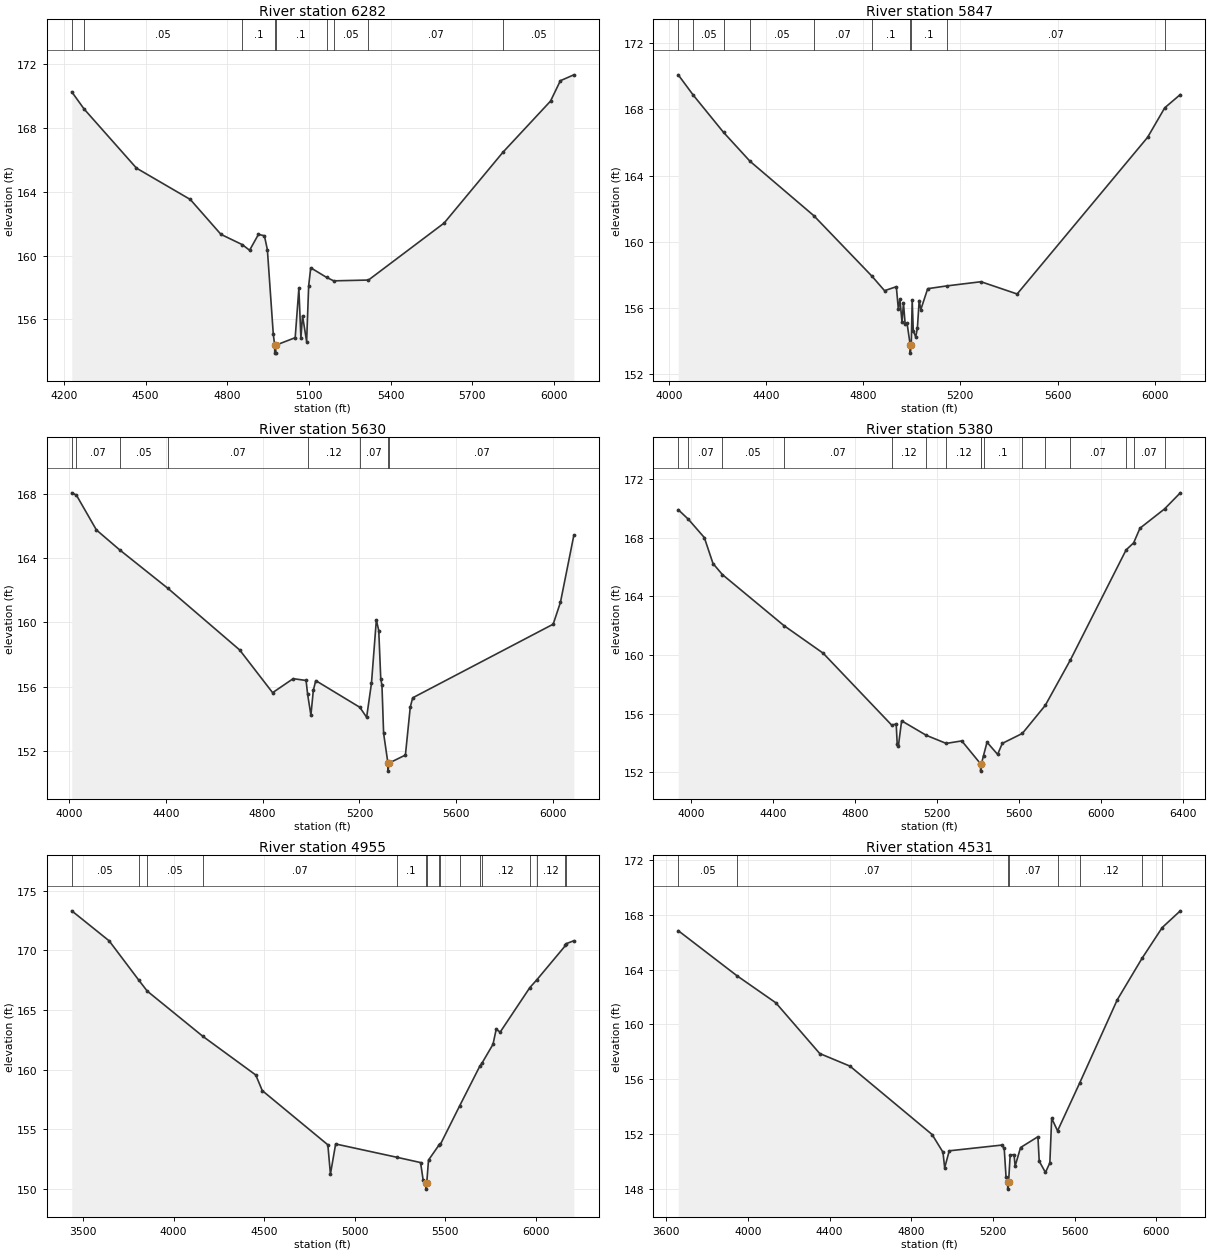
Type RM Length L Ch R = 1 ,6282    ,435,435,435
BEGIN DESCRIPTION:
TRIB 2 TO SULPHUR CREEK 6.0
END DESCRIPTION:
XS GIS Cut Line= 3
        2525325.       13462775.        2524625.       13462475.
      2523725.04     13463074.97
#Sta/Elev= 30
  4229.3  170.28  4274.7   169.2  4466.8  165.49  4664.5  163.52  4776.9  161.33
  4855.8  160.68  4882.1  160.33  4914.7  161.33  4936.5  161.24  4947.4  160.37
  4969.1  155.06  4974.2  154.37  4974.5  153.87  4978.2  153.87  4978.5  154.37
  5049.5  154.84    5063  157.93  5070.5  154.82  5076.5  156.22  5091.5   154.6
    5099   158.1  5106.6  159.23  5164.5  158.63  5190.9  158.41  5318.5  158.46
  5596.3  162.04  5812.3  166.49  5986.9   169.7    6023  170.98  6072.5  171.35
#Mann= 9 ,-1 , 0
  4229.3     .07       0  4274.7     .05       0  4855.8      .1       0
  4974.2     .05       0  4978.5      .1       0  5164.5     .07       0
  5190.9     .05       0  5318.5     .07       0  5812.3     .05       0
Bank Sta=4974.2,4978.5
XS Rating Curve= 0 ,0
Exp/Cntr=0.3,0.1

Type RM Length L Ch R = 1 ,5847    ,217,217,217
BEGIN DESCRIPTION:
TRIB 2 TO SULPHUR CREEK 5.0
END DESCRIPTION:
XS GIS Cut Line= 3
      2525374.99     13462674.99        2524575.       13462125.
        2523775.       13462875.
#Sta/Elev= 30
  4038.3  170.09  4099.9  168.87  4224.7  166.62    4334  164.87  4596.4  161.59
  4836.3  157.93  4887.8  157.06  4936.3   157.3  4944.8  155.93  4950.9  156.56
  4959.7  155.17  4965.8  156.31  4972.7  155.03  4980.7  155.08  4993.4  153.79
  4993.7  153.29  4997.8  153.79  5001.7   156.5  5006.1  154.64  5016.2  154.27
    5023  154.78  5030.4  156.46  5037.2  155.92  5065.5  157.18  5145.1  157.35
  5284.9   157.6  5433.8  156.86  5971.1  166.32  6041.6   168.1  6105.7   168.9
#Mann= 10 ,-1 , 0
  4038.3     .07       0  4099.9     .05       0  4224.7     .07       0
    4334     .05       0  4596.4     .07       0  4836.3      .1       0
  4993.4     .05       0  4997.8      .1       0  5145.1     .07       0
  6041.6     .05       0
Bank Sta=4993.4,4997.8
XS Rating Curve= 0 ,0
Exp/Cntr=0.3,0.1

Type RM Length L Ch R = 1 ,5630    ,250,250,250
BEGIN DESCRIPTION:
Mapping XS f1e24b2a
END DESCRIPTION:
XS GIS Cut Line= 3
      2525354.61     13462509.42       2524606.8     13461914.78
      2523489.76      13461932.8
#Sta/Elev= 30
  4012.3  168.06  4031.3  167.92  4114.1  165.75  4210.2  164.51  4409.9  162.11
  4705.2  158.29  4841.4  155.63  4926.2   156.5  4979.5  156.39    4986  155.52
  4999.5  154.23  5009.5  155.78  5019.5  156.38  5201.4  154.72  5229.5   154.1
  5249.5  156.22  5269.6  160.15  5279.6  159.49  5287.8   156.5  5292.8  156.08
  5299.6   153.1  5317.4  151.25  5317.7  150.75  5321.8  151.25  5389.6  151.75
  5409.6  154.73  5419.6  155.31  5999.6  159.89  6029.6  161.25  6084.9  165.42
#Mann= 8 ,-1 , 0
  4012.3     .05       0  4031.3     .07       0  4210.2     .05       0
  4409.9     .07       0    4986     .12       0  5201.4     .07       0
  5317.4     .05       0  5321.8     .07       0
Bank Sta=5317.4,5321.8
XS Rating Curve= 0 ,0
Exp/Cntr=0.3,0.1

Type RM Length L Ch R = 1 ,5380    ,425,425,425
BEGIN DESCRIPTION:
TRIB 2 TO SULPHUR CREEK 4.0
END DESCRIPTION:
XS GIS Cut Line= 3
      2525475.01     13462475.01        2524725.       13461725.
      2523525.01     13461025.01
#Sta/Elev= 30
  3935.8   169.9  3985.8  169.24  4063.1     168  4105.5  166.23  4151.1  165.48
  4451.6     162  4642.9  160.12  4977.1  155.22  4999.4  155.29  5004.3   153.9
  5010.1   153.8  5025.8  155.51  5146.3  154.52  5243.3  153.97  5319.4  154.14
    5411  152.58  5411.3  152.08  5415.4  152.58  5425.4  153.14  5442.6  154.05
  5494.3  153.22    5517  153.97  5614.9  154.65  5726.7  156.56  5849.4  159.66
  6121.2  167.16    6158  167.64  6188.9  168.64  6308.6  169.95  6385.7  171.05
#Mann= 16 ,-1 , 0
  3935.8     .05       0  3985.8     .07       0  4151.1     .05       0
  4451.6     .07       0  4977.1     .12       0  5146.3     .07       0
  5243.3     .12       0    5411     .05       0  5415.4     .12       0
  5425.4      .1       0  5614.9     .07       0  5726.7     .12       0
  5849.4     .07       0  6121.2     .12       0    6158     .07       0
  6308.6     .12       0
Bank Sta=5411,5415.4
XS Rating Curve= 0 ,0
Exp/Cntr=0.3,0.1

Type RM Length L Ch R = 1 ,4955    ,424,424,424
BEGIN DESCRIPTION:
TRIB 2 TO SULPHUR CREEK 3.0
END DESCRIPTION:
XS GIS Cut Line= 3
      2525725.01     13462575.01        2524725.       13461375.
      2523624.97     13460874.99
#Sta/Elev= 30
  3438.2  173.33  3644.5  170.81  3807.6  167.52  3854.8  166.59    4162  162.79
  4453.5  159.55  4489.3  158.24  4851.2  153.69  4865.5  151.23  4894.2  153.76
  5230.4  152.65  5362.8   152.2    5377  150.74  5392.4  150.47  5392.7  149.97
  5396.8  150.47  5406.7  152.41  5465.4  153.69  5471.9  153.72  5578.5  156.96
  5689.7  160.29  5701.8  160.55  5762.6  162.13  5780.2  163.39  5802.1  163.15
  5965.9  166.89  6004.9  167.55  6162.5  170.42    6168  170.58  6208.6  170.82
#Mann= 16 ,-1 , 0
  3438.2     .05       0  3807.6     .07       0  3854.8     .05       0
    4162     .07       0  5230.4      .1       0  5392.4     .05       0
  5396.8      .1       0  5465.4     .12       0  5471.9     .07       0
  5578.5     .12       0  5689.7     .07       0  5701.8     .12       0
  5965.9     .07       0  6004.9     .12       0  6162.5     .07       0
    6168     .12       0
Bank Sta=5392.4,5396.8
XS Rating Curve= 0 ,0
Exp/Cntr=0.3,0.1

Type RM Length L Ch R = 1 ,4531    ,694,694,694
BEGIN DESCRIPTION:
TRIB 2 TO SULPHUR CREEK 2.0
END DESCRIPTION:
XS GIS Cut Line= 3
        2525525.     13462224.99        2524925.       13461025.
      2523824.97     13460824.99
#Sta/Elev= 30
  3658.4  166.85  3945.7  163.56  4136.4  161.58  4351.6  157.87  4499.7  156.95
  4902.2  151.95  4955.3  150.66  4963.7  149.52  4986.1  150.76    5244  151.18
  5255.4  150.93  5264.3  148.85  5272.3  148.46  5272.6  147.96  5276.7  148.46
  5284.6  150.46  5303.7  150.48  5308.8  149.64  5335.4     151  5420.6  151.79
  5426.9     150  5457.4  149.18    5479  149.88  5487.9  153.14  5516.8  152.22
  5625.5  155.73  5809.3   161.8  5930.2  164.82  6029.6  167.08  6118.1   168.3
#Mann= 8 ,-1 , 0
  3658.4     .05       0  3945.7     .07       0  5272.3     .05       0
  5276.7     .07       0  5516.8     .07       0  5625.5     .12       0
  5930.2     .07       0  6029.6     .12       0
Bank Sta=5272.3,5276.7
XS Rating Curve= 0 ,0
Exp/Cntr=0.3,0.1

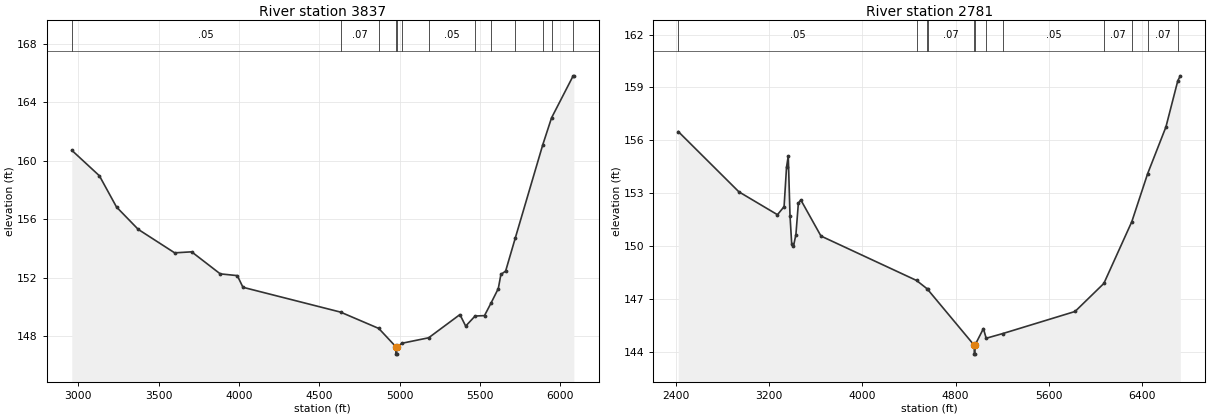
Type RM Length L Ch R = 1 ,3837    ,1056,1056,1056
BEGIN DESCRIPTION:
Mapping XS d63752e3
END DESCRIPTION:
XS GIS Cut Line= 4
      2526351.43     13461821.23      2525114.44     13460378.08
      2524875.73     13460378.08      2523910.04     13460573.38
#Sta/Elev= 30
  2959.8  160.72  3131.8  158.97  3238.3  156.83  3373.3   155.3  3600.2  153.69
  3705.9  153.76  3883.7  152.25  3990.1  152.13  4025.2  151.33  4632.4  149.63
  4870.5  148.51  4977.3  147.25  4977.7  146.75  4982.2  146.75  4982.6  147.25
  5016.9   147.5  5180.8  147.87  5375.5  149.46  5411.4  148.67  5469.7  149.36
  5528.5  149.39  5570.5  150.28  5614.3  151.24  5630.5  152.21  5659.9  152.44
  5720.7  154.73  5891.5  161.11  5945.7  162.94  6080.3  165.82  6084.5  165.82
#Mann= 13 ,-1 , 0
  2959.8     .05       0  4632.4     .07       0  4870.5     .05       0
  4977.3     .05       0  4982.6     .05       0  5016.9      .1       0
  5180.8     .05       0  5469.7     .07       0  5570.5     .12       0
  5720.7     .07       0  5891.5     .12       0  5945.7     .07       0
  6080.3     .12       0
Bank Sta=4977.3,4982.6
XS Rating Curve= 0 ,0
Exp/Cntr=0.3,0.1

Type RM Length L Ch R = 1 ,2781    ,0,0,0
BEGIN DESCRIPTION:
TRIB 2 TO SULPHUR CREEK 1.0
END DESCRIPTION:
XS GIS Cut Line= 4
      2526926.51     13461636.76      2525570.17     13459683.63
       2525190.4     13459553.42      2523812.32     13460204.48
#Sta/Elev= 30
  2422.5   156.5  2942.2  153.08  3273.1  151.78  3329.8  152.24  3350.8  154.48
  3365.6  155.11  3380.5  151.73  3395.3   150.1  3410.2  149.99  3431.1  150.65
  3452.1  152.43    3473  152.62  3645.9  150.57  4464.8  148.05  4557.3  147.57
  4560.6  147.54  4959.8  144.37  4960.2  143.87  4964.8  143.87  4965.2  144.37
  5038.4  145.32  5061.8  144.77  5205.8  145.04  5823.8  146.29  6070.6  147.88
    6310  151.38    6446  154.11  6602.7  156.76  6704.4  159.38    6726  159.66
#Mann= 12 ,-1 , 0
  2422.5     .05       0  4464.8     .07       0  4557.3     .05       0
  4560.6     .07       0  4959.8     .05       0  4965.2     .07       0
  5061.8      .1       0  5205.8     .05       0  6070.6     .07       0
    6310     .05       0    6446     .07       0  6704.4     .12       0
Bank Sta=4959.8,4965.2
XS Rating Curve= 0 ,0
Exp/Cntr=0.3,0.1

Chan Stop Cuts=-1
Use User Specified Reach Order=0
Composite Channel Slope=5