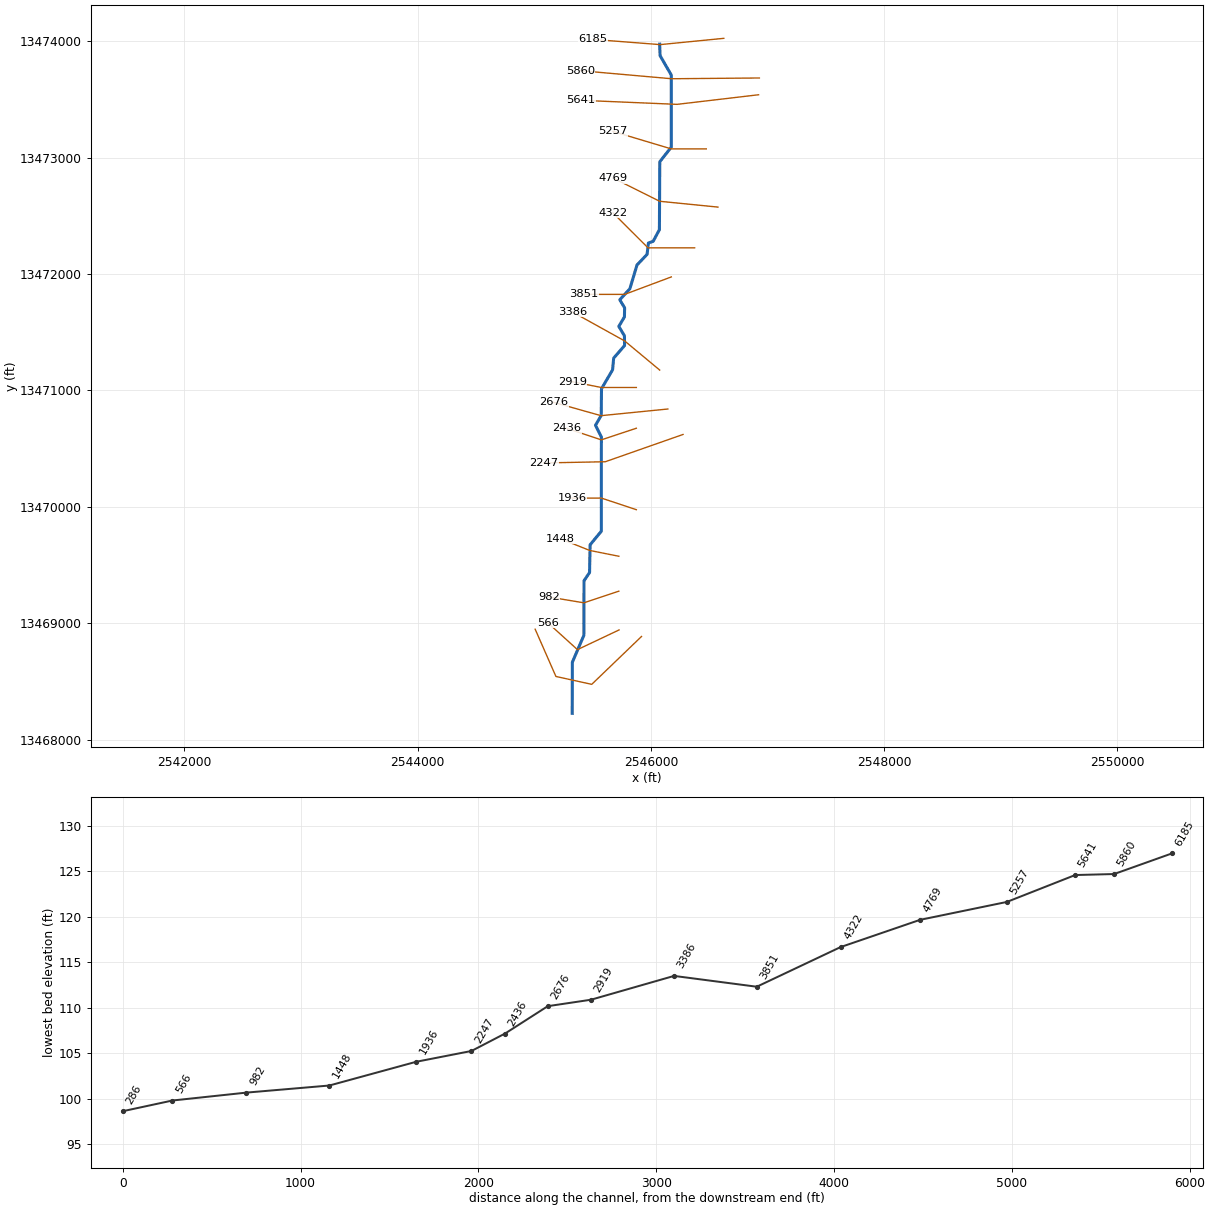
--- TRIB 2 TO TURKEY CREEK.prj (project) ---

Proj Title=TRIB 2 TO TURKEY CREEK Base Level Engineering
Current Plan=p01
Default Exp/Contr=0.3,0.1
English Units
Geom File=g01
Flow File=f01
Plan File=p01
Y Axis Title=Elevation
X Axis Title(PF)=Main Channel Distance
X Axis Title(XS)=Station
BEGIN DESCRIPTION:
TRIB 2 TO TURKEY CREEK
END DESCRIPTION:
DSS Export Rating Curves= 0
DSS Export Rating Curve Sorted= 0
DSS Export Volume Flow Curves= 0
DXF OffsetX= 0
DXF OffsetY= 0
DXF ScaleX= 1
DXF ScaleY= 10

--- TRIB 2 TO TURKEY CREEK.p01 (plan) ---

Plan Title=Multiple Run
Short Identifier=Multiple
Geom File=g01
Flow File=f01
Subcritical Flow
K Sum by GR= 0
Std Step Tol= 0.01
Critical Tol= 0.01
Num of Std Step Trials= 20
Max Error Tol= 0.3
Flow Tol Ratio= 0.001
Split Flow NTrial= 30
Split Flow Tol= 0.02
Split Flow Ratio= 0.02
Log Output Level= 0
Friction Slope Method= 1
Unsteady Friction Slope Method= 2
Unsteady Bridges Friction Slope Method= 1
Parabolic Critical Depth
Global Vel Dist=  1 , 1 , 1
Global Log Level= 0
CheckData=True
Encroach Param= -1, 0, 0, 0
BEGIN DESCRIPTION:
Multiple Run
END DESCRIPTION:

--- TRIB 2 TO TURKEY CREEK.f01 (steady flow) ---

Flow Title=Multiple
Number of Profiles=7
Profile Names=10-year,25-year,50-year,1pct_min,100-year,1pct_plu,500-year
River Rch & RM= TRIB 2 TO TURKEY,Reach-1,6185
     348     533     691     435     868    1732    1351
River Rch & RM= TRIB 2 TO TURKEY,Reach-1,4322
     650    1034    1375     885    1766    3524    2881
Boundary for River Rch & Prof#=TRIB 2 TO TURKEY,Reach-1,1
Up Type=0
Dn Type=3
Dn Slope=0.005
Boundary for River Rch & Prof#=TRIB 2 TO TURKEY,Reach-1,2
Up Type=0
Dn Type=3
Dn Slope=0.005
Boundary for River Rch & Prof#=TRIB 2 TO TURKEY,Reach-1,3
Up Type=0
Dn Type=3
Dn Slope=0.005
Boundary for River Rch & Prof#=TRIB 2 TO TURKEY,Reach-1,4
Up Type=0
Dn Type=3
Dn Slope=0.005
Boundary for River Rch & Prof#=TRIB 2 TO TURKEY,Reach-1,5
Up Type=0
Dn Type=3
Dn Slope=0.005
Boundary for River Rch & Prof#=TRIB 2 TO TURKEY,Reach-1,6
Up Type=0
Dn Type=3
Dn Slope=0.005
Boundary for River Rch & Prof#=TRIB 2 TO TURKEY,Reach-1,7
Up Type=0
Dn Type=3
Dn Slope=0.005

--- TRIB 2 TO TURKEY CREEK.g01 (geometry) ---

Geom Title=Existing Conditions
Program Version=4.10

River Reach=TRIB 2 TO TURKEY,Reach-1
Reach XY= 30
        2546075.       13473975.      2546078.63      13473876.5
      2546174.49     13473709.79      2546174.61     13473090.16
      2546076.06     13472964.56      2546072.77      13472380.9
      2546018.98     13472280.79       2545978.5     13472266.52
       2545967.1     13472168.88      2545880.54     13472077.42
      2545819.14      13471872.7      2545732.81     13471778.41
      2545774.48     13471709.78       2545772.8     13471630.97
       2545724.6       13471550.      2545772.81     13471469.03
      2545774.06     13471385.48      2545680.54     13471277.42
      2545671.17     13471176.59       2545576.2      13471014.5
      2545573.76      13470785.5       2545524.6       13470700.
      2545575.19     13470600.09      2545574.61     13469790.16
      2545478.55     13469673.53      2545473.78      13469435.5
      2545426.22      13469364.5      2545424.93     13468895.03
      2545326.22      13468664.5        2545325.       13468225.

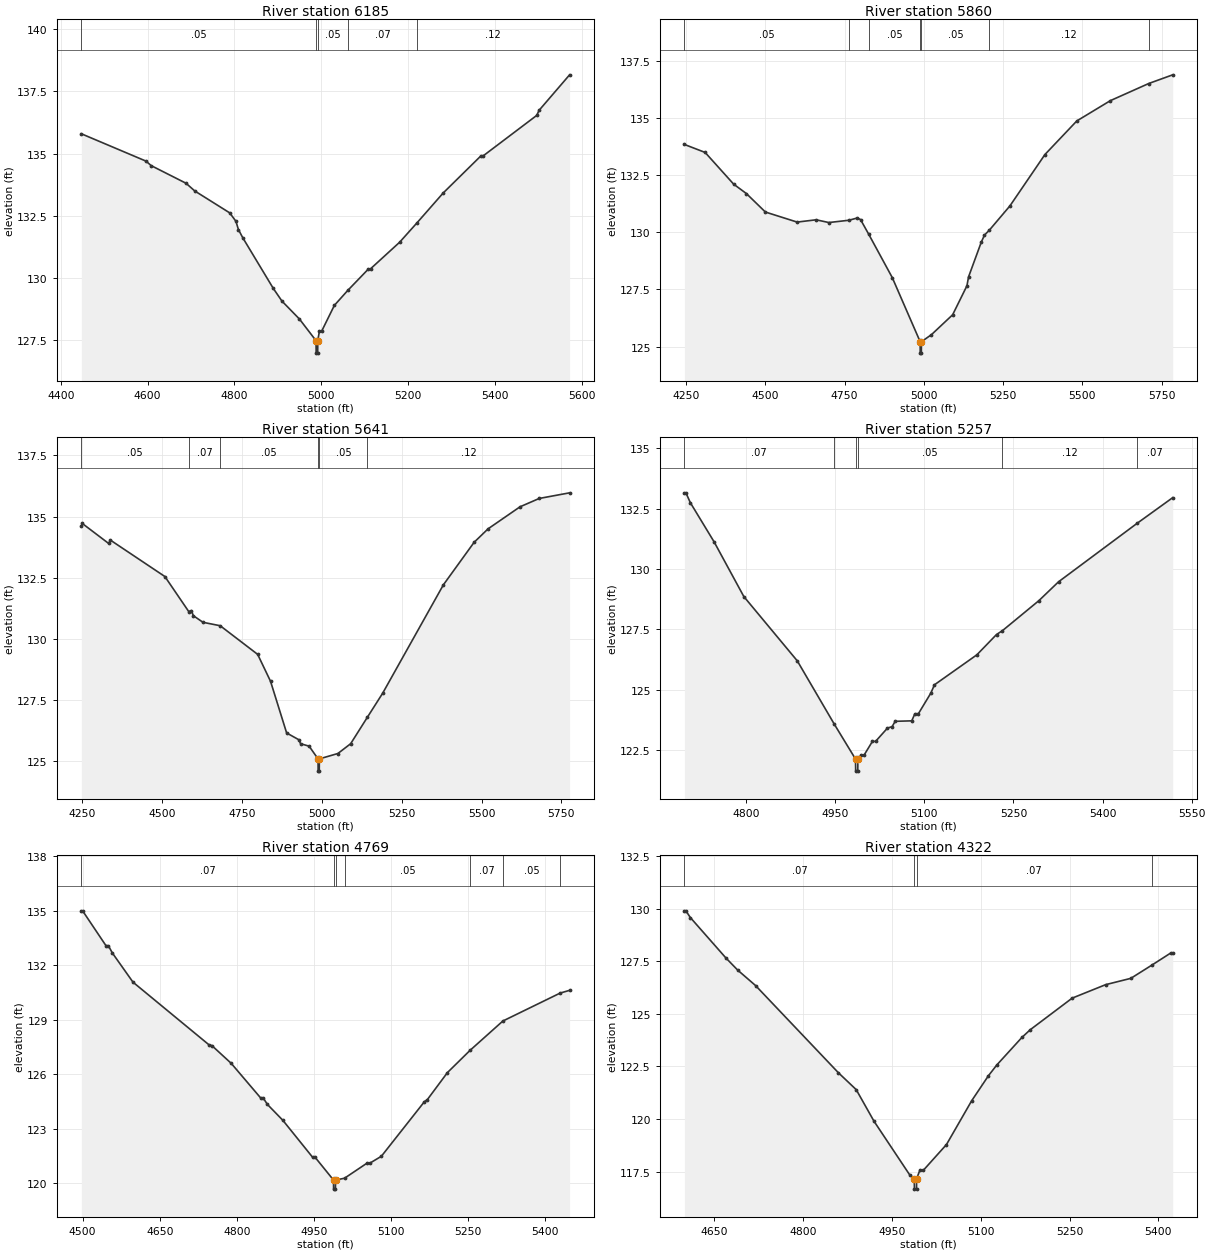
Type RM Length L Ch R = 1 ,6185    ,325,325,325
BEGIN DESCRIPTION:
TRIB 2 TO TURKEY CREEK 12.0
END DESCRIPTION:
XS GIS Cut Line= 3
        2546625.       13474025.      2546079.01     13473970.99
      2545504.82     13474015.91
#Sta/Elev= 30
  4447.3   135.8  4596.3   134.7  4608.1  134.52  4688.5  133.81  4708.6   133.5
    4789  132.62  4803.4  132.28  4809.1  131.95  4819.1  131.62  4889.5  129.58
  4909.5  129.07  4949.7  128.35  4987.9  127.48  4988.2  126.98  4991.7  126.98
  4991.9  127.48  4995.5  127.85  5000.5  127.85  5030.1   128.9  5060.9   129.5
  5108.4  130.36  5113.4  130.37  5180.5  131.44  5220.5  132.22  5280.8  133.42
    5367   134.9    5372   134.9  5496.3  136.54  5501.5  136.74  5571.9  138.17
#Mann= 5 ,-1 , 0
  4447.3     .05       0  4987.9     .05       0  4991.9     .05       0
  5060.9     .07       0  5220.5     .12       0
Bank Sta=4987.9,4991.9
XS Rating Curve= 0 ,0
Exp/Cntr=0.3,0.1

Type RM Length L Ch R = 1 ,5860    ,219,219,219
BEGIN DESCRIPTION:
Mapping XS 4b919191
END DESCRIPTION:
XS GIS Cut Line= 3
      2546930.27     13473684.35      2546177.21     13473677.84
      2545393.77     13473747.29
#Sta/Elev= 30
  4245.1  133.85  4310.4   133.5  4400.4  132.11  4440.4   131.7  4500.4  130.89
  4600.4  130.45  4660.4  130.55  4700.4  130.43  4763.7  130.53  4790.4  130.63
  4800.4  130.56  4825.7  129.93  4900.4  128.02  4988.4  125.21  4988.6  124.71
  4992.1  124.71  4992.4  125.21  5024.1  125.52  5090.8  126.39  5135.9  127.66
    5141  128.05  5181.1  129.57  5191.2  129.88  5206.8   130.1  5271.5  131.16
  5381.9  133.41  5482.3  134.88  5588.3  135.77  5709.2  136.52  5784.7   136.9
#Mann= 7 ,-1 , 0
  4245.1     .05       0  4763.7     .07       0  4825.7     .05       0
  4988.4     .05       0  4992.4     .05       0  5206.8     .12       0
  5709.2     .07       0
Bank Sta=4988.4,4992.4
XS Rating Curve= 0 ,0
Exp/Cntr=0.3,0.1

Type RM Length L Ch R = 1 ,5641    ,384,384,384
BEGIN DESCRIPTION:
Mapping XS b0f6e470
END DESCRIPTION:
XS GIS Cut Line= 3
      2546923.42     13473540.25      2546224.66     13473457.79
        2545400.     13473492.51
#Sta/Elev= 30
  4246.7   134.6  4249.5  134.72  4332.4   133.9  4337.5  134.04  4508.4  132.55
    4583  131.12  4591.3  131.16  4597.5  130.95  4627.7  130.68  4681.6  130.54
  4798.9  129.37  4839.2  128.27  4889.6  126.16  4928.1  125.88  4933.2  125.72
    4960  125.62    4988   125.1  4988.3   124.6  4991.8   124.6    4992   125.1
  5050.1  125.32  5090.1  125.72  5142.4   126.8  5190.2  127.78  5380.4  132.21
  5476.8  133.95  5520.5   134.5  5620.6   135.4  5680.6  135.74  5775.7  135.97
#Mann= 6 ,-1 , 0
  4246.7     .05       0    4583     .07       0  4681.6     .05       0
    4988     .05       0    4992     .05       0  5142.4     .12       0
Bank Sta=4988,4992
XS Rating Curve= 0 ,0
Exp/Cntr=0.3,0.1

Type RM Length L Ch R = 1 ,5257    ,488,488,488
BEGIN DESCRIPTION:
TRIB 2 TO TURKEY CREEK 11.0
END DESCRIPTION:
XS GIS Cut Line= 3
      2546475.01       13473075.        2546175.       13473075.
      2545675.03     13473224.99
#Sta/Elev= 30
  4696.1  133.15  4698.6  133.15  4706.1  132.74  4746.1  131.12  4796.1  128.86
  4886.1   126.2  4948.2  123.59  4984.1  122.14  4984.4  121.64  4987.9  121.64
  4988.1  122.14  4993.6  122.31  4998.7  122.31  5012.6  122.87  5017.9  122.87
  5037.9  123.42  5045.7  123.48  5050.9   123.7  5078.8  123.72    5084  124.01
  5090.1  124.02    5111  124.87    5117  125.21  5188.4  126.45  5221.5  127.29
  5231.5  127.45  5292.8  128.69  5325.9  129.47  5458.8   131.9  5518.1  132.95
#Mann= 6 ,-1 , 0
  4696.1     .07       0  4948.2     .05       0  4984.1     .05       0
  4988.1     .05       0  5231.5     .12       0  5458.8     .07       0
Bank Sta=4984.1,4988.1
XS Rating Curve= 0 ,0
Exp/Cntr=0.3,0.1

Type RM Length L Ch R = 1 ,4769    ,447,447,447
BEGIN DESCRIPTION:
TRIB 2 TO TURKEY CREEK 10.0
END DESCRIPTION:
XS GIS Cut Line= 3
      2546575.01       13472575.        2546075.       13472625.
      2545675.01     13472824.99
#Sta/Elev= 30
  4497.5     135    4500     135  4545.2  133.09  4550.3  133.07  4557.8  132.68
    4598  131.07  4746.2  127.61  4751.3  127.58    4789   126.6  4846.7  124.68
  4851.8  124.67  4859.3  124.34  4889.5  123.46  4947.2  121.43  4952.3  121.42
    4988  120.17  4988.2  119.67  4991.7  119.67    4992  120.17  5009.4  120.27
  5053.1   121.1  5058.7   121.1  5081.1  121.48  5164.9  124.49  5170.5   124.6
  5209.6  126.09  5253.8  127.32  5317.4  128.93  5428.9  130.47  5447.2  130.62
#Mann= 7 ,-1 , 0
  4497.5     .07       0    4988     .05       0    4992     .07       0
  5009.4     .05       0  5253.8     .07       0  5317.4     .05       0
  5428.9     .12       0
Bank Sta=4988,4992
XS Rating Curve= 0 ,0
Exp/Cntr=0.3,0.1

Type RM Length L Ch R = 1 ,4322    ,471,471,471
BEGIN DESCRIPTION:
TRIB 2 TO TURKEY CREEK 9.0
END DESCRIPTION:
XS GIS Cut Line= 3
      2546375.01       13472225.        2545975.       13472225.
      2545674.98     13472525.02
#Sta/Elev= 28
  4599.9   129.9  4602.4   129.9  4609.9  129.58  4669.9  127.66  4689.9  127.08
  4719.9  126.35  4859.9   122.2  4889.9   121.4  4919.9   119.9  4979.9  117.36
  4987.9  117.17  4988.2  116.67  4991.7  116.67  4991.9  117.17  4997.4  117.57
  5003.4  117.57  5042.3  118.79  5084.8  120.87  5113.1  122.06  5127.2  122.57
  5169.6  123.88  5183.8  124.25  5254.5  125.75    5311  126.39  5353.5  126.69
  5388.5  127.31  5420.6  127.89  5424.2  127.89
#Mann= 4 ,-1 , 0
  4599.9     .07       0  4987.9     .05       0  4991.9     .07       0
  5388.5     .12       0
Bank Sta=4987.9,4991.9
XS Rating Curve= 0 ,0
Exp/Cntr=0.3,0.1

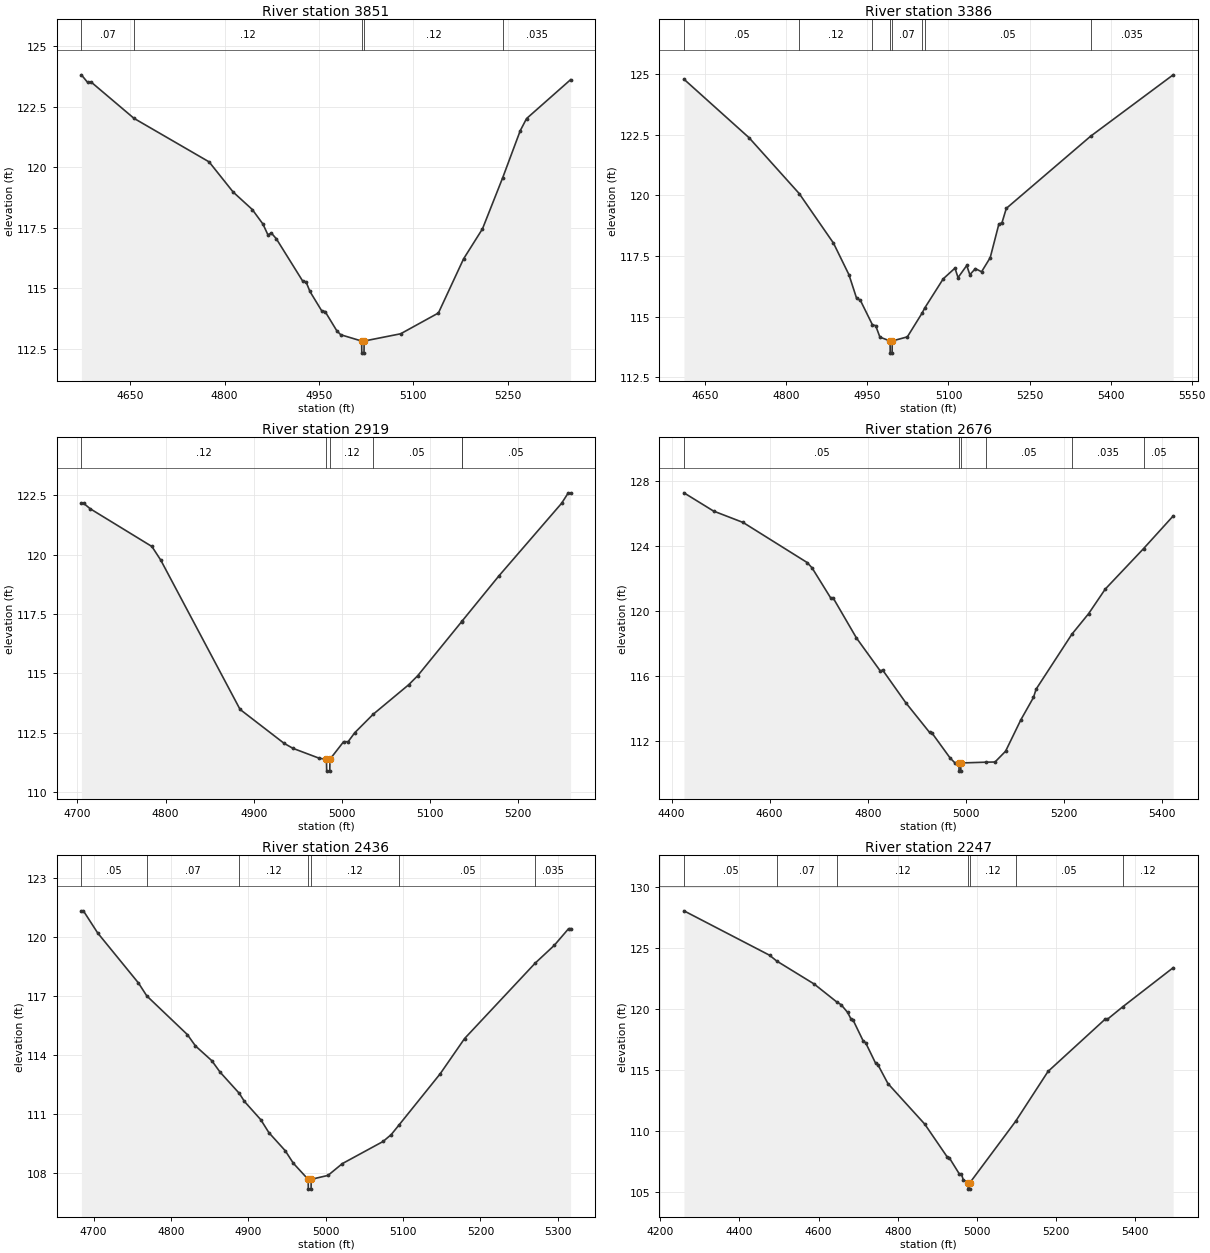
Type RM Length L Ch R = 1 ,3851    ,465,465,465
BEGIN DESCRIPTION:
TRIB 2 TO TURKEY CREEK 8.0
END DESCRIPTION:
XS GIS Cut Line= 3
      2546175.02     13471975.01        2545775.       13471825.
      2545425.02       13471825.
#Sta/Elev= 30
  4572.6  123.82  4582.4  123.51  4587.7  123.53  4656.2  122.02  4775.5  120.22
  4813.8  118.97  4844.1  118.25    4861  117.65    4869   117.2  4874.3  117.28
  4882.3  117.04  4924.2  115.29  4929.5  115.26  4935.7  114.86  4954.4  114.06
  4959.8  114.03  4978.5  113.23  4984.7  113.07  5017.8  112.81  5018.1  112.31
  5021.6  112.31  5021.8  112.81  5079.8  113.11  5139.8  113.97  5179.8  116.21
  5209.8  117.45    5242  119.57  5269.8  121.51  5279.8  122.01  5349.8  123.62
#Mann= 5 ,-1 , 0
  4572.6     .07       0  4656.2     .12       0  5017.8     .05       0
  5021.8     .12       0    5242    .035       0
Bank Sta=5017.8,5021.8
XS Rating Curve= 0 ,0
Exp/Cntr=0.3,0.1

Type RM Length L Ch R = 1 ,3386    ,467,467,467
BEGIN DESCRIPTION:
TRIB 2 TO TURKEY CREEK 7.0
END DESCRIPTION:
XS GIS Cut Line= 3
      2546075.04     13471174.97        2545775.       13471425.
      2545325.04     13471674.98
#Sta/Elev= 30
  4610.5  124.78    4731  122.37  4823.8  120.07  4887.2  118.03  4915.8  116.73
  4930.1  115.75  4936.6  115.69  4959.2  114.67  4965.3  114.63  4973.1  114.16
  4991.9     114  4992.2   113.5  4995.7   113.5  4995.9     114  5023.9  114.17
  5051.2  115.15  5056.1  115.36  5090.3  116.56    5112     117  5117.7  116.61
  5133.8  117.11  5139.5  116.73  5149.8  116.98  5161.2  116.85  5177.2  117.43
  5193.2  118.81    5199  118.87    5207  119.46  5362.9  122.43  5515.8  124.96
#Mann= 8 ,-1 , 0
  4610.5     .05       0  4823.8     .12       0  4959.2     .07       0
  4991.9     .05       0  4995.9     .07       0  5051.2     .12       0
  5056.1     .05       0  5362.9    .035       0
Bank Sta=4991.9,4995.9
XS Rating Curve= 0 ,0
Exp/Cntr=0.3,0.1

Type RM Length L Ch R = 1 ,2919    ,243,243,243
BEGIN DESCRIPTION:
TRIB 2 TO TURKEY CREEK 6.0
END DESCRIPTION:
XS GIS Cut Line= 3
      2545875.03       13471025.        2545575.       13471025.
      2545324.98       13471075.
#Sta/Elev= 25
  4704.5  122.16    4707  122.16  4714.5  121.93  4784.5  120.34  4794.5  119.77
  4884.5  113.48  4934.5  112.05  4944.5  111.84  4974.5  111.42  4982.5  111.38
  4982.8  110.88  4986.3  110.88  4986.5  111.38    5002  112.12  5007.1  112.12
  5014.7   112.5  5035.4  113.27  5075.9  114.52  5086.1   114.9  5135.8  117.17
  5136.2  117.19  5177.9  119.09  5249.3  122.16  5256.9   122.6  5259.5   122.6
#Mann= 6 ,-1 , 0
  4704.5     .12       0  4982.5     .05       0  4986.5     .12       0
  5035.4     .05       0  5135.8    .035       0  5136.2     .05       0
Bank Sta=4982.5,4986.5
XS Rating Curve= 0 ,0
Exp/Cntr=0.3,0.1

Type RM Length L Ch R = 1 ,2676    ,240,240,240
BEGIN DESCRIPTION:
Mapping XS 4209b3ff
END DESCRIPTION:
XS GIS Cut Line= 3
      2546145.13     13470840.17      2545572.18     13470782.87
      2545165.94     13470897.45
#Sta/Elev= 30
  4425.2  127.25  4485.6  126.13  4545.9  125.43  4676.6  122.97  4686.6  122.64
  4725.1  120.77  4730.1  120.77  4777.1  118.34  4825.6  116.32  4830.6  116.37
  4877.6  114.37  4926.1  112.55  4931.1  112.51    4968  110.98  4978.1  110.67
  4986.1  110.67  4986.4  110.17  4989.9  110.17  4990.1  110.67  5041.5  110.72
  5059.7  110.73  5081.2  111.39  5112.4  113.32  5138.1  114.69  5143.5   115.2
  5216.4  118.57  5250.5  119.83  5284.5  121.34  5362.8  123.83  5423.1  125.83
#Mann= 6 ,-1 , 0
  4425.2     .05       0  4986.1     .05       0  4990.1     .05       0
  5041.5     .05       0  5216.4    .035       0  5362.8     .05       0
Bank Sta=4986.1,4990.1
XS Rating Curve= 0 ,0
Exp/Cntr=0.3,0.1

Type RM Length L Ch R = 1 ,2436    ,189,189,189
BEGIN DESCRIPTION:
TRIB 2 TO TURKEY CREEK 5.0
END DESCRIPTION:
XS GIS Cut Line= 3
      2545874.97     13470674.99        2545575.       13470575.
      2545275.03     13470674.99
#Sta/Elev= 30
  4684.2  121.35  4686.8  121.35  4705.3  120.22    4758  117.67  4768.8  117.01
  4821.2  115.04  4831.7  114.46  4852.8  113.71  4863.4  113.13  4888.4  112.04
    4895  111.63  4916.1   110.7  4926.6  110.04  4947.7  109.12  4958.2  108.48
  4977.3  107.66  4977.6  107.16  4981.1  107.16  4981.3  107.66    5003  107.86
  5021.5  108.46  5074.2  109.59  5084.7  109.94  5095.2  110.45    5148  113.04
  5179.6  114.84    5271  118.69  5295.5  119.59    5314  120.44  5316.6  120.44
#Mann= 7 ,-1 , 0
  4684.2     .05       0  4768.8     .07       0  4888.4     .12       0
  4977.3     .05       0  4981.3     .12       0  5095.2     .05       0
    5271    .035       0
Bank Sta=4977.3,4981.3
XS Rating Curve= 0 ,0
Exp/Cntr=0.3,0.1

Type RM Length L Ch R = 1 ,2247    ,311,311,311
BEGIN DESCRIPTION:
Mapping XS 862c9358
END DESCRIPTION:
XS GIS Cut Line= 3
      2546275.31     13470621.42      2545608.63     13470387.04
      2545078.71     13470376.65
#Sta/Elev= 30
  4259.7  128.04  4476.2   124.4  4494.1  123.93  4588.6  122.05  4647.3  120.54
  4656.7  120.36  4673.4  119.72  4682.4  119.15  4687.7  119.06  4713.4  117.34
  4718.7  117.25  4744.4  115.54  4749.7  115.45  4775.3  113.89  4868.3  110.57
  4924.9  107.89  4930.2  107.82  4955.9  106.48  4961.2  106.47  4965.6  106.02
    4978  105.74  4978.3  105.24  4981.8  105.24    4982  105.74    5098  110.79
    5180  114.88  5325.3  119.19  5330.3  119.16  5368.6  120.17  5496.4  123.38
#Mann= 7 ,-1 , 0
  4259.7     .05       0  4494.1     .07       0  4647.3     .12       0
    4978     .05       0    4982     .12       0    5098     .05       0
  5368.6     .12       0
Bank Sta=4978,4982
XS Rating Curve= 0 ,0
Exp/Cntr=0.3,0.1

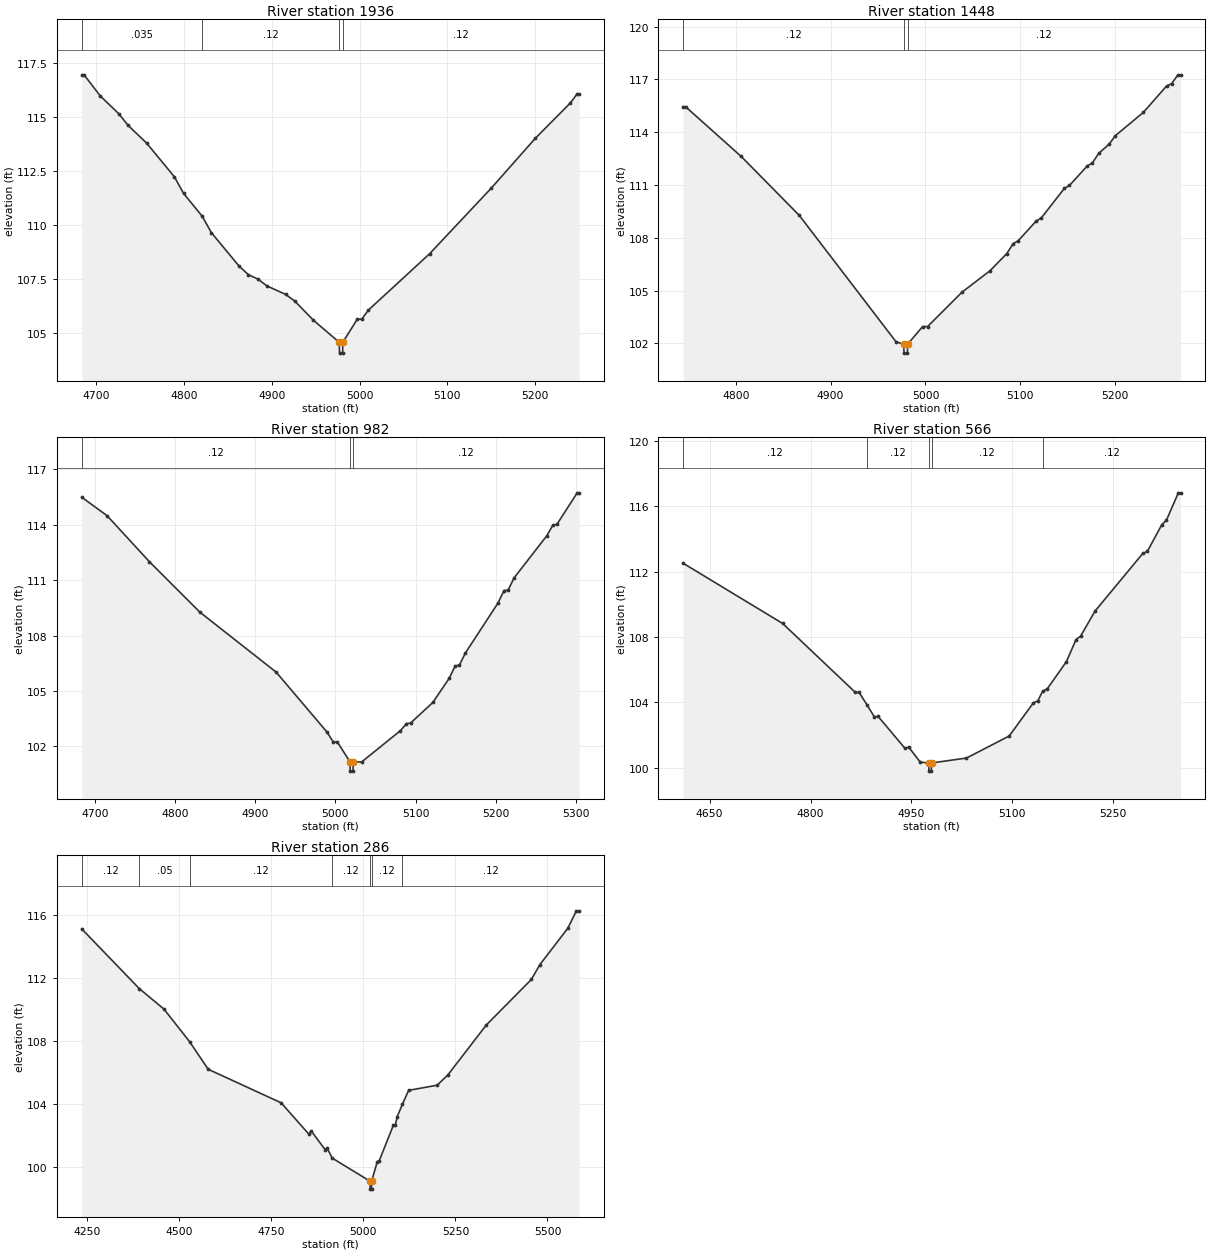
Type RM Length L Ch R = 1 ,1936    ,488,488,488
BEGIN DESCRIPTION:
TRIB 2 TO TURKEY CREEK 4.0
END DESCRIPTION:
XS GIS Cut Line= 3
      2545874.98     13469975.01        2545575.       13470075.
      2545325.01       13470075.
#Sta/Elev= 30
  4683.8  116.93  4686.4  116.93  4704.9  115.95  4725.9  115.13  4736.5  114.59
  4757.6  113.77  4789.2  112.21  4799.7  111.44  4820.8  110.39  4831.4  109.62
    4863  108.07  4873.5  107.68  4884.1  107.48  4894.6  107.16  4915.7  106.77
  4926.2  106.46  4947.3  105.58  4976.9  104.55  4977.2  104.05  4980.7  104.05
  4980.9  104.55  4997.4  105.62  5002.5  105.62    5010  106.04    5080  108.66
    5150  111.69    5200  113.99    5240  115.63  5247.5  116.04    5250  116.04
#Mann= 4 ,-1 , 0
  4683.8    .035       0  4820.8     .12       0  4976.9     .05       0
  4980.9     .12       0
Bank Sta=4976.9,4980.9
XS Rating Curve= 0 ,0
Exp/Cntr=0.3,0.1

Type RM Length L Ch R = 1 ,1448    ,466,466,466
BEGIN DESCRIPTION:
TRIB 2 TO TURKEY CREEK 3.0
END DESCRIPTION:
XS GIS Cut Line= 3
      2545724.98       13469575.        2545475.       13469625.
      2545224.99       13469725.
#Sta/Elev= 30
  4744.6  115.45  4747.1  115.45  4805.8  112.62    4867  109.27  4968.9  102.09
  4977.1  101.94  4977.4  101.44  4980.9  101.44  4981.1  101.94    4997  102.95
  5002.2  102.95  5038.6  104.91  5068.2  106.13  5085.7   107.1  5092.4  107.66
  5097.8  107.83  5116.7  108.95    5122  109.12  5146.3   110.8  5151.7  110.97
  5170.5  112.08  5175.9  112.25  5182.6   112.8  5193.4  113.31  5200.1   113.8
  5229.7  115.13    5254  116.62  5259.4  116.76  5266.1  117.26  5268.8  117.26
#Mann= 3 ,-1 , 0
  4744.6     .12       0  4977.1     .05       0  4981.1     .12       0
Bank Sta=4977.1,4981.1
XS Rating Curve= 0 ,0
Exp/Cntr=0.3,0.1

Type RM Length L Ch R = 1 ,982     ,416,416,416
BEGIN DESCRIPTION:
TRIB 2 TO TURKEY CREEK 2.0
END DESCRIPTION:
XS GIS Cut Line= 3
      2545724.97     13469274.99        2545425.       13469175.
      2545125.03       13469225.
#Sta/Elev= 30
  4683.8  115.49  4715.4  114.49  4768.1     112  4831.3  109.26  4926.2  106.02
  4989.5  102.78  4997.4  102.24  5002.5  102.24  5018.3  101.16  5018.5  100.66
    5022  100.66  5022.3  101.16  5032.9  101.16  5081.1  102.85  5088.7  103.23
  5093.8  103.26  5121.6  104.38  5141.9  105.68  5149.5  106.36  5154.6  106.39
  5162.2  107.06  5202.8  109.76  5210.4  110.44  5215.4  110.46    5223  111.13
  5263.6   113.4  5271.2  113.97  5276.3  114.02  5301.6  115.73  5304.1  115.73
#Mann= 3 ,-1 , 0
  4683.8     .12       0  5018.3     .05       0  5022.3     .12       0
Bank Sta=5018.3,5022.3
XS Rating Curve= 0 ,0
Exp/Cntr=0.3,0.1

Type RM Length L Ch R = 1 ,566     ,280,280,280
BEGIN DESCRIPTION:
Mapping XS fb0a7699
END DESCRIPTION:
XS GIS Cut Line= 3
      2545726.81     13468941.93      2545370.08     13468772.68
      2545114.86     13469004.46
#Sta/Elev= 30
  4610.6  112.52  4758.6  108.83  4866.7  104.61  4872.2  104.61  4883.8  103.86
    4895  103.11  4900.5  103.14  4940.4  101.19    4946  101.26  4963.2  100.34
  4975.9  100.29  4976.1   99.79  4979.6   99.79  4979.9  100.29  5031.9  100.59
  5095.4  101.94  5131.2  103.96    5138   104.1  5145.3  104.69  5152.2  104.84
  5180.6   106.5  5194.7  107.84  5201.5  108.05  5223.1  109.59  5294.1  113.12
  5300.8  113.24  5322.5  114.89  5329.2  115.15  5346.9  116.83  5350.2  116.83
#Mann= 5 ,-1 , 0
  4610.6     .12       0  4883.8     .12       0  4975.9     .05       0
  4979.9     .12       0  5145.3     .12       0
Bank Sta=4975.9,4979.9
XS Rating Curve= 0 ,0
Exp/Cntr=0.3,0.1

Type RM Length L Ch R = 1 ,286     ,0,0,0
BEGIN DESCRIPTION:
TRIB 2 TO TURKEY CREEK 1.0
END DESCRIPTION:
XS GIS Cut Line= 4
       2545919.6     13468885.94      2545492.52     13468474.48
      2545185.23     13468542.19       2545007.4     13468948.04
#Sta/Elev= 30
  4235.4  115.13  4391.6  111.34  4458.6  110.04  4528.2  107.97  4578.7  106.22
  4776.8  104.09  4852.8  102.08  4857.9  102.32  4896.5  101.11  4901.6  101.22
  4915.5  100.58  5018.5   99.11  5018.7   98.61  5022.2   98.61  5022.5   99.11
  5037.9  100.36    5043   100.4  5081.6  102.67  5086.7  102.65  5092.1  103.22
    5106  103.99  5122.9  104.88  5200.6  105.21  5229.5  105.86  5333.9  109.03
  5456.2  111.92  5479.6  112.87  5555.2  115.17  5578.6  116.28  5586.2  116.28
#Mann= 7 ,-1 , 0
  4235.4     .12       0  4391.6     .05       0  4528.2     .12       0
  4915.5     .12       0  5018.5     .05       0  5022.5     .12       0
    5106     .12       0
Bank Sta=5018.5,5022.5
XS Rating Curve= 0 ,0
Exp/Cntr=0.3,0.1

Chan Stop Cuts=-1
Use User Specified Reach Order=0
Composite Channel Slope=5