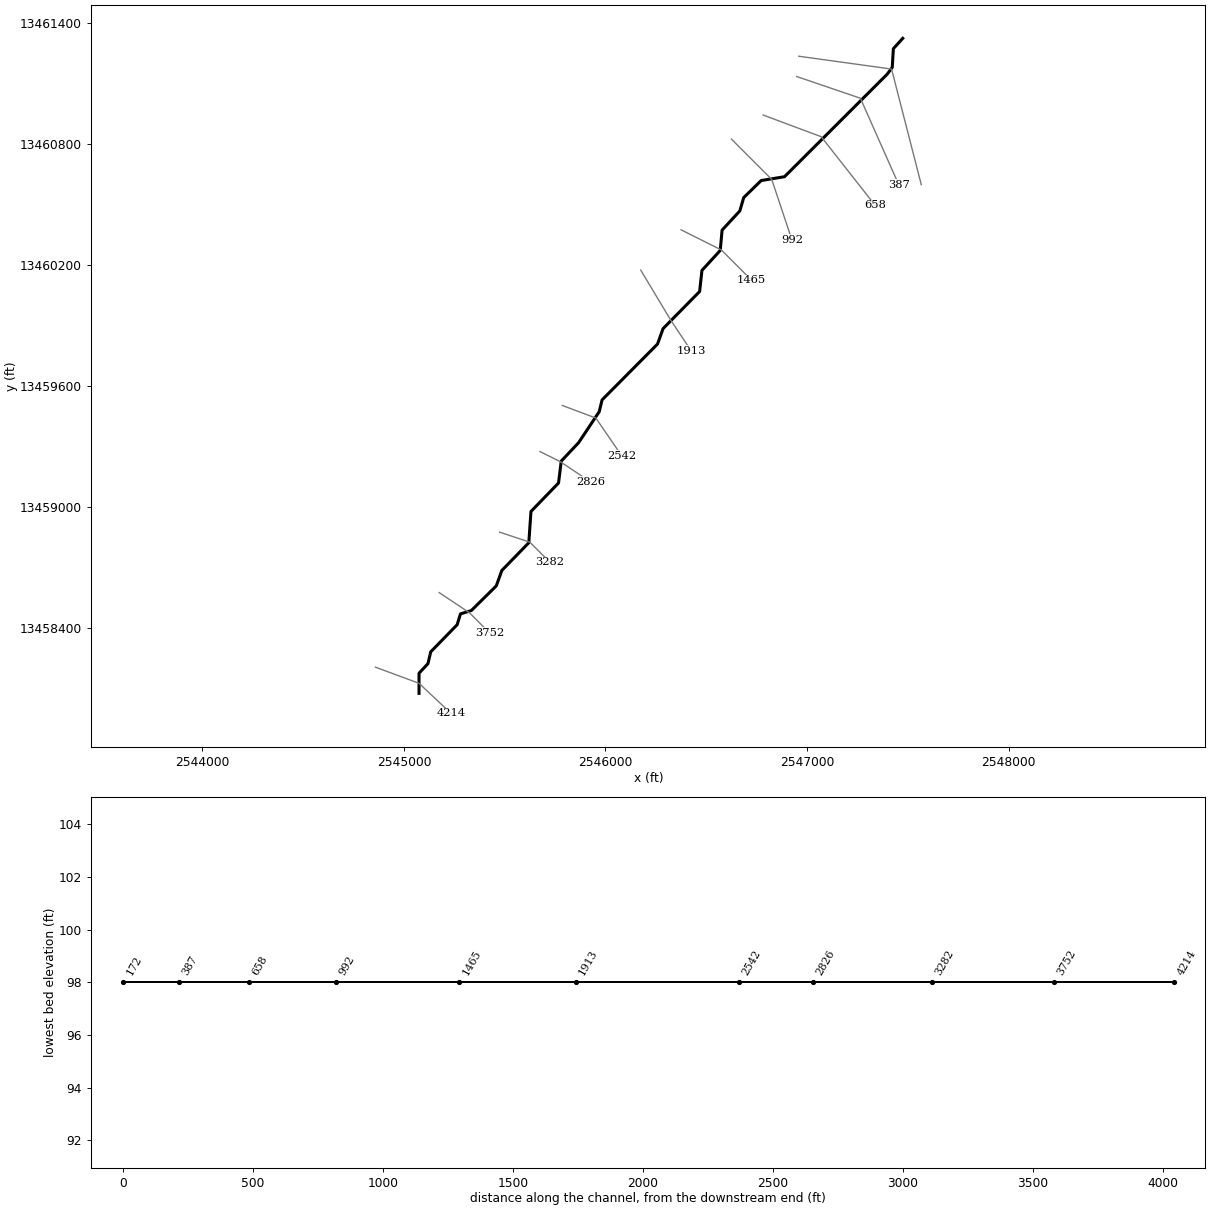
--- TRIB 3 TO COLETO CREEK RESERVOIR.prj (project) ---

Proj Title=TRIB 3 TO COLETO CREEK RESERVOIR Base Level Engineering
Current Plan=p01
Default Exp/Contr=0.3,0.1
English Units
Geom File=g01
Flow File=f01
Plan File=p01
Y Axis Title=Elevation
X Axis Title(PF)=Main Channel Distance
X Axis Title(XS)=Station
BEGIN DESCRIPTION:
TRIB 3 TO COLETO CREEK RESERVOIR
END DESCRIPTION:
DSS Export Rating Curves= 0
DSS Export Rating Curve Sorted= 0
DSS Export Volume Flow Curves= 0
DXF OffsetX= 0
DXF OffsetY= 0
DXF ScaleX= 1
DXF ScaleY= 10

--- TRIB 3 TO COLETO CREEK RESERVOIR.p01 (plan) ---

Plan Title=Multiple Run
Program Version=4.10
Short Identifier=Multiple
Geom File=g01
Flow File=f01
Subcritical Flow
K Sum by GR= 0
Std Step Tol= 0.01
Critical Tol= 0.01
Num of Std Step Trials= 20
Max Error Tol= 0.3
Flow Tol Ratio= 0.001
Split Flow NTrial= 30
Split Flow Tol= 0.02
Split Flow Ratio= 0.02
Log Output Level= 0
Friction Slope Method= 1
Unsteady Friction Slope Method= 2
Unsteady Bridges Friction Slope Method= 1
Parabolic Critical Depth
Global Vel Dist= 1 , 1 , 1
Global Log Level= 0
CheckData=True
Encroach Param=-1 ,0,0, 0
BEGIN DESCRIPTION:
Multiple Run
END DESCRIPTION:
Computation Interval=1HOUR
Output Interval=1HOUR
Run HTab= 0
Run UNet= 0
Run PostProcess= 0
Run WQNet= 0
UNET Theta= 1
UNET Theta Warmup= 1
UNET ZTol= 0.02
UNET ZSATol= 0.05
UNET MxIter= 20
UNET MaxInSteps= 0
UNET DtIC= 0
UNET DtMin= 0
UNET MaxCRTS= 20
UNET WFStab= 2
UNET SFStab= 1
UNET WFX= 1
UNET SFX= 1
UNET DSS MLevel= 4
UNET DZMax Abort= 100
UNET Convert EG Bridges= 0
UNET Use Existing IB Tables=-1
UNET Froude Reduction=False
UNET Froude Limit= 1
UNET Froude Power= 10
UNET Time Slicing=0,0, 5
UNET Junction Losses=0
Instantaneous Interval=1HOUR
Write IC File= 0
Write IC File at Sim End=0
Echo Input=False
Echo Parameters=False
Echo Output=False
Write Detailed= 0
WQ AD Non Conservative
WQ ULTIMATE=-1
WQ Max Comp Step=1HOUR
WQ Output Interval=15MIN
WQ Output Selected Increments= 0
WQ Output face flow=0
WQ Output face velocity=0
WQ Output face area=0
WQ Output face dispersion=0
WQ Output cell volume=0
WQ Output cell surface area=0
WQ Output cell continuity=0
WQ Output cumulative cell continuity=0
WQ Output face conc=0
WQ Output face dconc_dx=0
WQ Output face courant=0
WQ Output face peclet=0
WQ Output face adv mass=0
WQ Output face disp mass=0
WQ Output cell mass=0
WQ Output cell source sink temp=0
WQ Output cell source sink nsm=0
WQ Output MaxMinRange=-1
WQ Daily Max Min Mean=-1
WQ Daily Range=0
WQ Daily Time=0
WQ Create Restart=0
WQ Fixed Restart=0
WQ System Summary=0
WQ Use Fixed Temperature=0
Sorting and Armoring Iterations= 10
XS Update Threshold= 0.02
Hydraulics Update Threshold= 0.02
Energy Slope Method= 1
Volume Change Method= 0
XS Weighting Method= 0
Number of US Weighted Cross Sections= 1
Number of DS Weighted Cross Sections= 1
Upstream XS Weight=0.25
Main XS Weight=0.5
Downstream XS Weight=0.25
Number of DS XS's Weighted with US Boundary= 1
Upstream Boundary Weight= 1
Weight of XSs Associated with US Boundary= 0
Number of US XS's Weighted with DS Boundary= 1
Downstream Boundary Weight= 0.5
Weight of XSs Associated with DS Boundary= 0.5
Sediment Output Level= 4
Mass or Volume Output= 0
Output Increment Type= 1
Profile and TS Output Increment= 10
XS Output Flag= 0
XS Output Increment= 10
Disregard all LS=0
Disregard all Conn=0
Disregard all Breaches=0
Disregard all Pumps=0

--- TRIB 3 TO COLETO CREEK RESERVOIR.f01 (steady flow) ---

Flow Title=Multiple
Program Version=4.10
Number of Profiles= 7
Profile Names=10-year,25-year,50-year,1pct_min,100-year,1pct_plu,500-year
River Rch & RM=TRIB 3 TO COLETO,Reach-1         ,4214
     282     422     539     334     667    1330    1005
Boundary for River Rch & Prof#=TRIB 3 TO COLETO,Reach-1         , 1
Up Type= 0
Dn Type= 3
Dn Slope=0.00035
Boundary for River Rch & Prof#=TRIB 3 TO COLETO,Reach-1         , 2
Up Type= 0
Dn Type= 3
Dn Slope=0.00035
Boundary for River Rch & Prof#=TRIB 3 TO COLETO,Reach-1         , 3
Up Type= 0
Dn Type= 3
Dn Slope=0.00035
Boundary for River Rch & Prof#=TRIB 3 TO COLETO,Reach-1         , 4
Up Type= 0
Dn Type= 3
Dn Slope=0.00035
Boundary for River Rch & Prof#=TRIB 3 TO COLETO,Reach-1         , 5
Up Type= 0
Dn Type= 3
Dn Slope=0.00035
Boundary for River Rch & Prof#=TRIB 3 TO COLETO,Reach-1         , 6
Up Type= 0
Dn Type= 3
Dn Slope=0.00035
Boundary for River Rch & Prof#=TRIB 3 TO COLETO,Reach-1         , 7
Up Type= 0
Dn Type= 3
Dn Slope=0.00035
DSS Import GetInterval= 0
DSS Import GetPeak= 0
DSS Import FillOption= 0

--- TRIB 3 TO COLETO CREEK RESERVOIR.g01 (geometry) ---

Geom Title=Existing Conditions
Program Version=4.10

River Reach=TRIB 3 TO COLETO,Reach-1
Reach XY= 30
        2545075.       13458075.        2545075.       13458175.
      2545119.29     13458222.65      2545133.06     13458281.09
      2545264.11     13458415.58      2545280.62     13458469.38
      2545334.42     13458485.89      2545458.35     13458608.33
      2545485.78     13458684.68      2545619.69     13458822.48
      2545630.35      13458977.5      2545767.14     13459118.83
      2545780.54     13459227.42      2545866.82     13459318.96
      2545969.13     13459472.72      2545983.16     13459531.05
      2546258.35     13459808.33      2546285.78     13459884.68
      2546467.14     13460068.83      2546478.63      13460173.5
      2546569.46     13460272.58      2546578.63      13460373.5
      2546666.82     13460468.96      2546685.77      13460534.7
      2546772.56     13460619.48       2546888.3      13460638.4
      2547398.82     13461148.13      2547422.89     13461180.88
      2547428.39     13461273.59        2547475.       13461325.

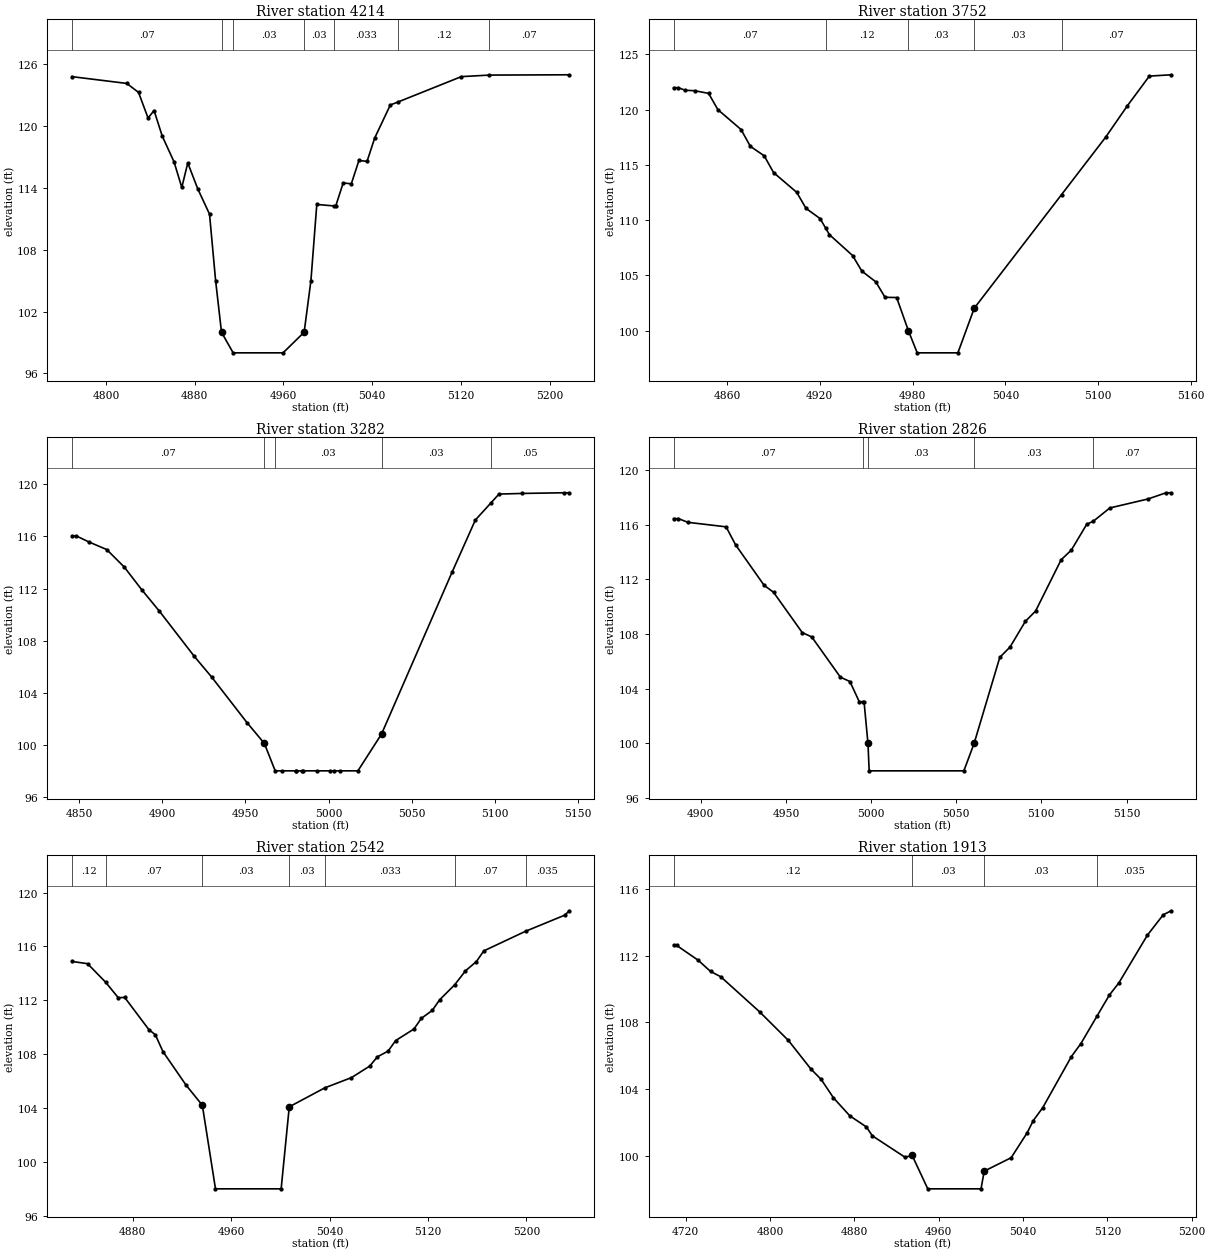
Type RM Length L Ch R = 1 ,4214    ,462,462,462
BEGIN DESCRIPTION:
TRIB 3 TO COLETO CREEK RESERVOIR 9.0
END DESCRIPTION:
XS GIS Cut Line= 3
      2544858.59     13458204.94        2545075.       13458125.
      2545233.62     13457975.75
#Sta/Elev= 30
  4769.3  124.82  4818.8  124.16  4829.4  123.29    4838   120.8  4843.4  121.53
  4850.8  119.04  4861.4  116.55  4868.4  114.06  4873.8  116.44  4882.7  113.95
  4893.4  111.47  4898.9     105  4904.2     100  4914.7      98  4959.7      98
  4978.7     100  4984.8     105  4990.1  112.41  5005.9  112.26  5007.1  112.23
  5013.9   114.5  5021.2  114.41  5028.1  116.68  5035.4  116.59  5042.3  118.86
  5056.4  122.07  5062.9  122.34  5120.4  124.82  5145.7  124.97  5217.8     125
#Mann= 7 ,-1 , 0
  4769.3     .07       0  4904.2     .03       0  4914.7     .03       0
  4978.7     .03       0  5005.9    .033       0  5062.9     .12       0
  5145.7     .07       0
Bank Sta=4904.2,4978.7
XS Rating Curve= 0 ,0
Exp/Cntr=0.3,0.1

Type RM Length L Ch R = 1 ,3752    ,470,470,470
BEGIN DESCRIPTION:
TRIB 3 TO COLETO CREEK RESERVOIR 8.0
END DESCRIPTION:
XS GIS Cut Line= 3
      2545174.99     13458575.01        2545325.       13458475.
      2545424.99     13458375.01
#Sta/Elev= 29
  4825.5  121.97  4828.5  121.97    4833  121.74    4839   121.7  4848.1  121.46
  4854.1  119.99  4869.1  118.19  4875.1  116.67  4884.1  115.81  4890.1   114.3
  4905.1  112.51  4911.1  111.06  4920.2  110.14  4923.9  109.25  4926.2  108.69
  4941.2   106.8  4947.2  105.39  4956.2  104.42  4962.2  103.02  4969.7     103
  4977.3     100    4983      98  5009.3      98  5019.9  102.04  5076.3   112.3
  5104.8  117.49  5118.9  120.34  5133.1  123.02  5147.2  123.14
#Mann= 5 ,-1 , 0
  4825.5     .07       0  4923.9     .12       0  4977.3     .03       0
  5019.9     .03       0  5076.3     .07       0
Bank Sta=4977.3,5019.9
XS Rating Curve= 0 ,0
Exp/Cntr=0.3,0.1

Type RM Length L Ch R = 1 ,3282    ,456,456,456
BEGIN DESCRIPTION:
TRIB 3 TO COLETO CREEK RESERVOIR 7.0
END DESCRIPTION:
XS GIS Cut Line= 3
      2545475.04     13458874.99        2545625.       13458825.
        2545725.       13458725.
#Sta/Elev= 30
  4845.5  116.04  4848.1  116.04    4856  115.56  4866.5  114.99  4877.1  113.64
  4887.6   111.9  4898.2  110.26  4919.2  106.79  4929.8  105.18  4950.9  101.71
  4961.4   100.1  4967.9      98    4972      98  4980.5      98  4980.7      98
  4984.2      98  4984.5      98    4993      98  5000.9      98  5003.6      98
  5007.1      98  5017.7      98  5031.9  100.82  5074.3  113.23  5088.4  117.26
  5097.7  118.56  5102.6  119.25  5116.7   119.3  5141.5  119.35    5145  119.35
#Mann= 5 ,-1 , 0
  4845.5     .07       0  4961.4     .03       0  4967.9     .03       0
  5031.9     .03       0  5097.7     .05       0
Bank Sta=4961.4,5031.9
XS Rating Curve= 0 ,0
Exp/Cntr=0.3,0.1

Type RM Length L Ch R = 1 ,2826    ,284,284,284
BEGIN DESCRIPTION:
TRIB 3 TO COLETO CREEK RESERVOIR 6.0
END DESCRIPTION:
XS GIS Cut Line= 3
      2545674.97     13459275.02        2545775.       13459225.
      2545924.98     13459125.01
#Sta/Elev= 30
  4884.1  116.44  4886.9  116.44  4892.5  116.17  4914.9  115.84  4920.5  114.52
  4937.2  111.57  4942.8  111.05  4959.6  108.11  4965.2  107.79    4982  104.85
  4987.6  104.53  4993.1  103.05  4995.1  103.05  4995.9  103.05  4998.2     100
  4998.9      98  5054.5      98  5060.5     100  5075.6   106.3  5081.6  107.05
  5090.6  108.93  5096.6  109.68  5111.6  113.43  5117.6  114.14  5126.6  116.02
  5130.6  116.26  5140.2  117.22  5162.7  117.88  5173.2  118.33  5176.2  118.33
#Mann= 5 ,-1 , 0
  4884.1     .07       0  4995.1     .12       0  4998.2     .03       0
  5060.5     .03       0  5130.6     .07       0
Bank Sta=4998.2,5060.5
XS Rating Curve= 0 ,0
Exp/Cntr=0.3,0.1

Type RM Length L Ch R = 1 ,2542    ,629,629,629
BEGIN DESCRIPTION:
Mapping XS b49e3a42
END DESCRIPTION:
XS GIS Cut Line= 3
      2545785.64     13459503.57      2545952.34     13459441.06
       2546080.4     13459254.16
#Sta/Elev= 30
  4830.4  114.89  4843.2  114.72  4857.8  113.35  4868.1   112.2  4873.4  112.21
    4893  109.83  4898.3  109.44  4904.5  108.19  4923.3   105.7  4936.5  104.21
  4947.2      98  5000.6      98  5007.2  104.09  5036.1   105.5  5057.8  106.26
  5072.7  107.12  5078.8   107.8  5087.6  108.23  5093.7  109.01  5108.6  109.87
  5114.6  110.66  5123.5  111.25  5129.5  112.04  5141.7  113.15  5150.5  114.19
  5159.4  114.88  5165.4  115.67  5199.4  117.13  5231.1  118.32    5235  118.65
#Mann= 7 ,-1 , 0
  4830.4     .12       0  4857.8     .07       0  4936.5     .03       0
  5007.2     .03       0  5036.1    .033       0  5141.7     .07       0
  5199.4    .035       0
Bank Sta=4936.5,5007.2
XS Rating Curve= 0 ,0
Exp/Cntr=0.3,0.1

Type RM Length L Ch R = 1 ,1913    ,448,448,448
BEGIN DESCRIPTION:
TRIB 3 TO COLETO CREEK RESERVOIR 4.0
END DESCRIPTION:
XS GIS Cut Line= 3
      2546175.01     13460174.99        2546325.       13459925.
      2546424.99     13459775.01
#Sta/Elev= 30
  4708.7  112.61  4711.6  112.61    4732  111.72  4743.7  111.05  4753.4  110.73
  4790.3  108.62  4817.5  106.91  4838.9  105.19  4848.6  104.57  4860.3  103.46
  4875.8  102.38  4891.4  101.72  4897.2  101.18  4928.3   99.89  4934.8  100.02
  4949.7      98  5000.2      98  5003.2   99.06  5028.8   99.87  5043.8  101.35
  5049.8   102.1  5058.8  102.88  5085.9  105.94  5094.9  106.72  5110.1  108.36
  5121.9  109.63  5130.9  110.36    5158  113.23    5173  114.45  5180.5  114.69
#Mann= 4 ,-1 , 0
  4708.7     .12       0  4934.8     .03       0  5003.2     .03       0
  5110.1    .035       0
Bank Sta=4934.8,5003.2
XS Rating Curve= 0 ,0
Exp/Cntr=0.3,0.1

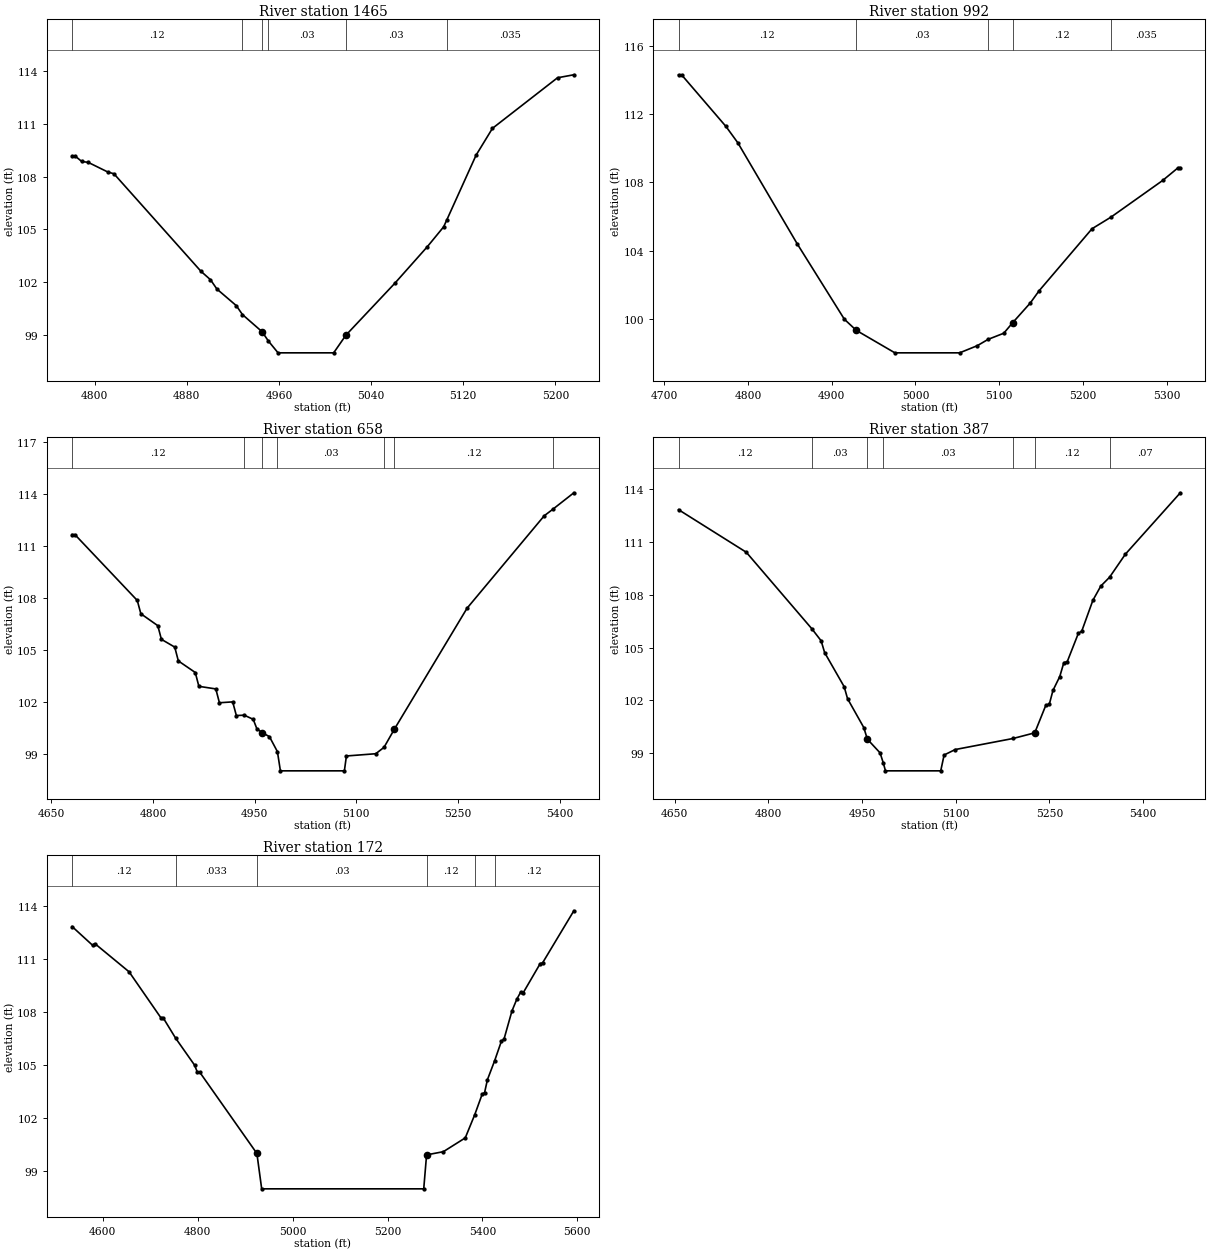
Type RM Length L Ch R = 1 ,1465    ,473,473,473
BEGIN DESCRIPTION:
TRIB 3 TO COLETO CREEK RESERVOIR 3.0
END DESCRIPTION:
XS GIS Cut Line= 3
      2546374.96     13460375.02        2546575.       13460275.
      2546725.01     13460124.99
#Sta/Elev= 24
  4780.3  109.16  4783.1  109.16  4788.7  108.86  4794.3  108.81  4811.1  108.27
  4816.7  108.16  4892.2  102.63  4900.5  102.15  4906.1  101.62  4922.9  100.68
  4928.3  100.17  4945.3    99.2  4950.8   98.67  4959.2      98  5007.5      98
  5018.1      99  5060.5  101.94  5088.8  104.02    5103  105.15  5105.8  105.55
  5131.2  109.22  5145.4  110.74  5201.9  113.61  5216.1  113.78
#Mann= 6 ,-1 , 0
  4780.3     .12       0  4928.3    .033       0  4945.3    .033       0
  4950.8     .03       0  5018.1     .03       0  5105.8    .035       0
Bank Sta=4945.3,5018.1
XS Rating Curve= 0 ,0
Exp/Cntr=0.3,0.1

Type RM Length L Ch R = 1 ,992     ,334,334,334
BEGIN DESCRIPTION:
TRIB 3 TO COLETO CREEK RESERVOIR 2.0
END DESCRIPTION:
XS GIS Cut Line= 3
      2546624.97     13460825.03        2546825.       13460625.
        2546925.     13460325.01
#Sta/Elev= 20
  4717.1  114.31  4720.7  114.31  4773.7  111.28  4787.9  110.32  4858.6  104.41
  4915.1   99.97  4929.3   99.32  4975.4      98  5052.7      98  5073.8   98.42
  5086.7   98.79  5105.4   99.15  5115.9   99.76    5137  100.92  5147.6  101.64
  5210.8  105.28  5233.4  105.96  5295.1  108.11  5313.6  108.86  5316.2  108.86
#Mann= 5 ,-1 , 0
  4717.1     .12       0  4929.3     .03       0  5086.7     .03       0
  5115.9     .12       0  5233.4    .035       0
Bank Sta=4929.3,5115.9
XS Rating Curve= 0 ,0
Exp/Cntr=0.3,0.1

Type RM Length L Ch R = 1 ,658     ,271,271,271
BEGIN DESCRIPTION:
Mapping XS 556f9f79
END DESCRIPTION:
XS GIS Cut Line= 3
       2546782.2     13460944.53       2547070.4     13460836.89
      2547337.77      13460496.6
#Sta/Elev= 30
  4680.6  111.67  4684.8  111.67  4776.8  107.86  4782.1  107.09  4807.1   106.4
  4812.4  105.61  4832.1  105.16  4837.4  104.36  4862.4  103.69  4867.7  102.89
  4892.7  102.74    4898  101.94  4917.6  101.99    4923   101.2  4934.7  101.22
  4947.9  100.98  4953.3  100.43  4961.1  100.21  4971.8   99.98  4983.6   99.11
    4988      98  5082.4      98  5085.4   98.86  5128.7   98.99  5140.9   99.36
    5156   100.4  5263.4  107.41  5377.3  112.76  5390.1  113.14    5421  114.09
#Mann= 7 ,-1 , 0
  4680.6     .12       0  4934.7     .03       0  4961.1     .03       0
  4983.6     .03       0  5140.9     .03       0    5156     .12       0
  5390.1     .07       0
Bank Sta=4961.1,5156
XS Rating Curve= 0 ,0
Exp/Cntr=0.3,0.1

Type RM Length L Ch R = 1 ,387     ,215,215,215
BEGIN DESCRIPTION:
Mapping XS 9420a86a
END DESCRIPTION:
XS GIS Cut Line= 3
      2546948.85     13461135.51      2547264.84     13461027.86
      2547455.24     13460598.61
#Sta/Elev= 30
  4656.3  112.84  4764.8  110.42  4869.8  106.07  4884.6  105.39  4890.2  104.72
  4921.5  102.78  4926.9   102.1  4952.9  100.46  4958.6    99.8    4979   99.02
  4984.2   98.44  4987.6      98  5076.1      98  5081.5    98.9  5099.3   99.21
  5192.1   99.84  5226.6  100.16  5244.4  101.73  5249.9  101.78  5255.8  102.57
  5266.7  103.36  5273.2  104.15  5278.6   104.2  5296.4  105.81  5301.9  105.94
  5319.7  107.69  5332.4   108.5  5346.4     109  5371.7  110.31  5459.7   113.8
#Mann= 7 ,-1 , 0
  4656.3     .12       0  4869.8     .03       0  4958.6     .03       0
  4984.2     .03       0  5192.1     .03       0  5226.6     .12       0
  5346.4     .07       0
Bank Sta=4958.6,5226.6
XS Rating Curve= 0 ,0
Exp/Cntr=0.3,0.1

Type RM Length L Ch R = 1 ,172     ,0,0,0
BEGIN DESCRIPTION:
TRIB 3 TO COLETO CREEK RESERVOIR 1.0
END DESCRIPTION:
XS GIS Cut Line= 3
      2546959.28      13461236.2       2547419.5     13461172.56
        2547567.     13460598.62
#Sta/Elev= 30
  4535.4  112.83  4578.6  111.77  4583.6  111.86  4655.5  110.27  4722.3  107.68
  4727.3  107.67  4753.5  106.52  4793.6  104.99  4799.1  104.61  4804.2   104.6
  4924.8     100  4934.9      98  5276.3      98  5282.3   99.92  5317.6   100.1
  5363.8  100.88  5383.9   102.2  5399.4  103.35  5404.5  103.44  5410.5  104.17
  5425.8  105.25  5440.1  106.36  5445.3  106.45  5462.1  108.05  5472.4  108.72
  5480.9  109.14    5486  109.09  5521.6  110.73  5526.8  110.78  5592.6  113.72
#Mann= 6 ,-1 , 0
  4535.4     .12       0  4753.5    .033       0  4924.8     .03       0
  5282.3     .12       0  5383.9     .07       0  5425.8     .12       0
Bank Sta=4924.8,5282.3
XS Rating Curve= 0 ,0
Exp/Cntr=0.3,0.1

Chan Stop Cuts=-1
Use User Specified Reach Order=0
Composite Channel Slope=5