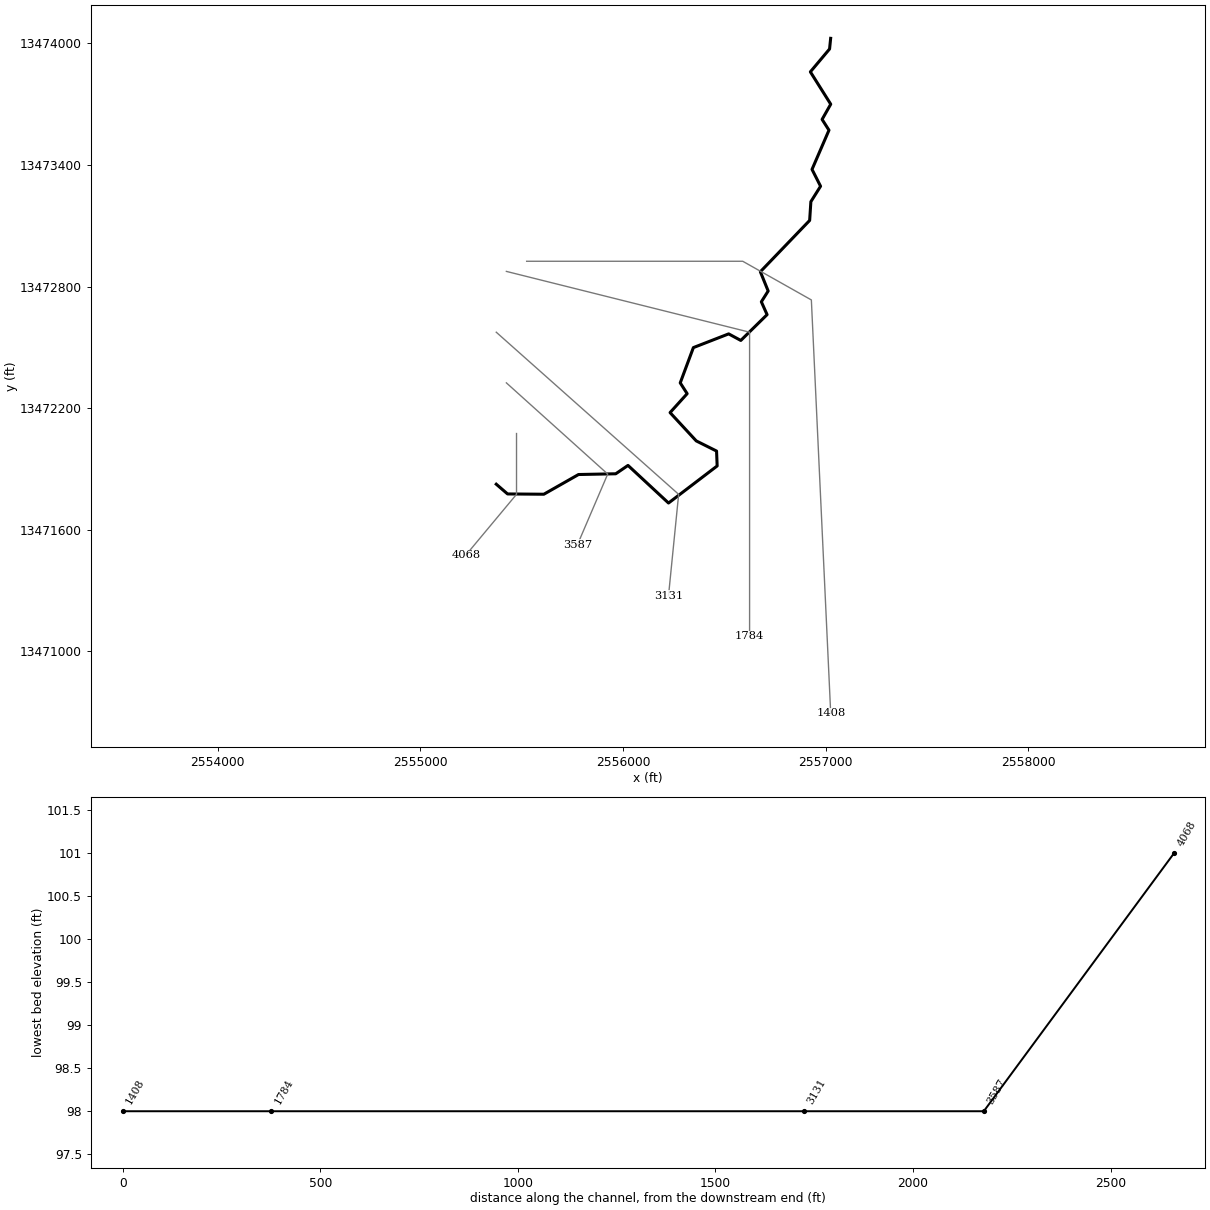
--- TRIB 3 TO COLETO CREEK.prj (project) ---

Proj Title=TRIB 3 TO COLETO CREEK Base Level Engineering
Current Plan=p01
Default Exp/Contr=0.3,0.1
English Units
Geom File=g01
Flow File=f01
Plan File=p01
Y Axis Title=Elevation
X Axis Title(PF)=Main Channel Distance
X Axis Title(XS)=Station
BEGIN DESCRIPTION:
TRIB 3 TO COLETO CREEK
END DESCRIPTION:
DSS Export Rating Curves= 0
DSS Export Rating Curve Sorted= 0
DSS Export Volume Flow Curves= 0
DXF OffsetX= 0
DXF OffsetY= 0
DXF ScaleX= 1
DXF ScaleY= 10

--- TRIB 3 TO COLETO CREEK.p01 (plan) ---

Plan Title=Multiple Run
Short Identifier=Multiple
Geom File=g01
Flow File=f01
Subcritical Flow
K Sum by GR= 0
Std Step Tol= 0.01
Critical Tol= 0.01
Num of Std Step Trials= 20
Max Error Tol= 0.3
Flow Tol Ratio= 0.001
Split Flow NTrial= 30
Split Flow Tol= 0.02
Split Flow Ratio= 0.02
Log Output Level= 0
Friction Slope Method= 1
Unsteady Friction Slope Method= 2
Unsteady Bridges Friction Slope Method= 1
Parabolic Critical Depth
Global Vel Dist=  1 , 1 , 1
Global Log Level= 0
CheckData=True
Encroach Param= -1, 0, 0, 0
BEGIN DESCRIPTION:
Multiple Run
END DESCRIPTION:

--- TRIB 3 TO COLETO CREEK.f01 (steady flow) ---

Flow Title=Multiple
Program Version=4.10
Number of Profiles= 7
Profile Names=10-year,25-year,50-year,1pct_min,100-year,1pct_plu,500-year
River Rch & RM=TRIB 3 TO COLETO,Reach-1         ,4068
     303     456     584     364     725    1447    1102
Boundary for River Rch & Prof#=TRIB 3 TO COLETO,Reach-1         , 1
Up Type= 0
Dn Type= 3
Dn Slope=0.0005
Boundary for River Rch & Prof#=TRIB 3 TO COLETO,Reach-1         , 2
Up Type= 0
Dn Type= 3
Dn Slope=0.0005
Boundary for River Rch & Prof#=TRIB 3 TO COLETO,Reach-1         , 3
Up Type= 0
Dn Type= 3
Dn Slope=0.0005
Boundary for River Rch & Prof#=TRIB 3 TO COLETO,Reach-1         , 4
Up Type= 0
Dn Type= 3
Dn Slope=0.0005
Boundary for River Rch & Prof#=TRIB 3 TO COLETO,Reach-1         , 5
Up Type= 0
Dn Type= 3
Dn Slope=0.0005
Boundary for River Rch & Prof#=TRIB 3 TO COLETO,Reach-1         , 6
Up Type= 0
Dn Type= 3
Dn Slope=0.0005
Boundary for River Rch & Prof#=TRIB 3 TO COLETO,Reach-1         , 7
Up Type= 0
Dn Type= 3
Dn Slope=0.0005
DSS Import GetInterval= 0
DSS Import GetPeak= 0
DSS Import FillOption= 0

--- TRIB 3 TO COLETO CREEK.g01 (geometry) ---

Geom Title=Existing Conditions
Program Version=4.10

River Reach=TRIB 3 TO COLETO,Reach-1
Reach XY= 30
        2555375.       13471825.      2555430.78     13471776.89
      2555609.79      13471775.5      2555780.93     13471872.76
      2555964.57     13471876.39       2556025.1     13471917.68
        2556225.     13471732.07      2556464.97     13471915.02
      2556462.04     13471988.55       2556361.8     13472038.64
      2556232.62     13472178.33      2556316.98     13472271.66
       2556282.8      13472324.9      2556347.67     13472499.01
      2556521.78     13472566.71      2556581.67      13472534.3
      2556711.36     13472661.66      2556683.04       13472725.
      2556716.69     13472778.23      2556678.16     13472873.35
      2556921.39      13473126.5      2556927.38     13473219.03
      2556975.21     13473295.21       2556933.1     13473378.29
      2557016.73     13473571.78      2556982.83     13473624.92
      2557025.41       13473700.      2556924.89     13473859.64
      2557019.67     13473972.49        2557025.       13474025.

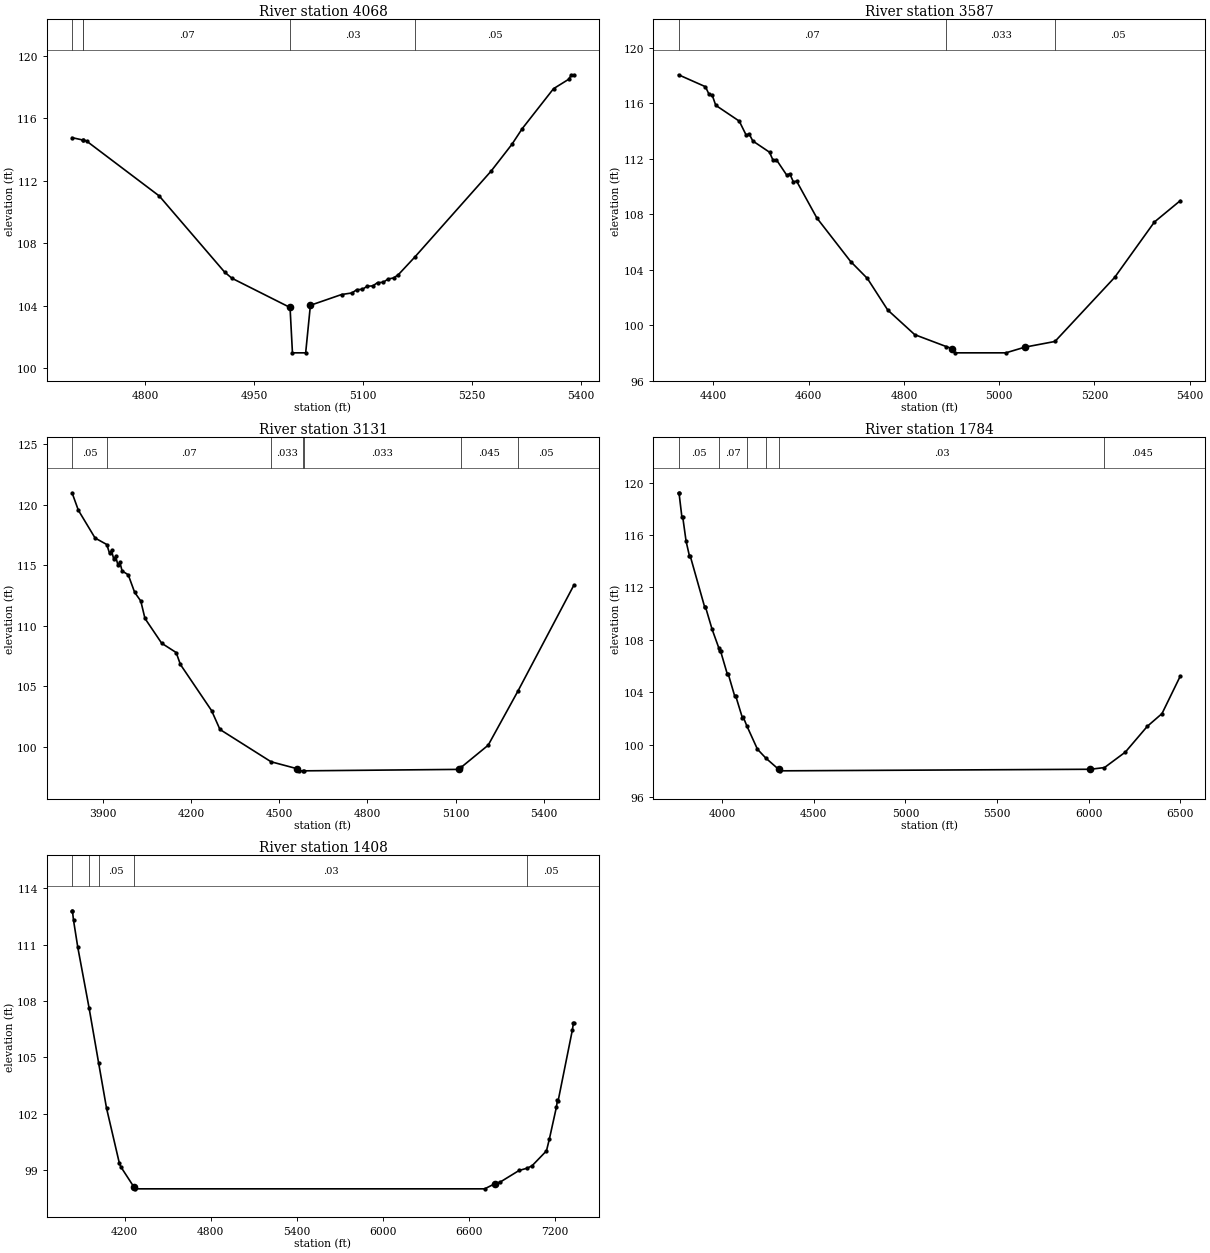
Type RM Length L Ch R = 1 ,4068    ,481,481,481
BEGIN DESCRIPTION:
TRIB 3 TO COLETO CREEK 6.0
END DESCRIPTION:
XS GIS Cut Line= 3
        2555475.     13472075.04        2555475.       13471775.
      2555224.97     13471474.96
#Sta/Elev= 30
  4699.5  114.76  4714.1  114.61  4714.9   114.6  4719.5  114.54  4819.5  111.03
  4909.5  106.16  4919.5  105.77  4999.5   103.9  5002.8     101    5021     101
  5027.5  104.04  5070.5  104.73  5084.8  104.83  5091.3  105.04  5099.1  105.06
  5105.6  105.26  5113.4  105.28  5119.9  105.49  5127.8  105.51  5134.3  105.72
  5142.1  105.79  5148.6     106  5171.5  107.14  5276.2  112.62  5304.8  114.33
  5319.1  115.34  5362.1  117.89  5382.9  118.49  5386.8  118.78  5390.1  118.78
#Mann= 5 ,-1 , 0
  4699.5     .07       0  4714.1     .12       0  4714.9     .07       0
  4999.5     .03       0  5171.5     .05       0
Bank Sta=4999.5,5027.5
XS Rating Curve= 0 ,0
Exp/Cntr=0.3,0.1

Type RM Length L Ch R = 1 ,3587    ,456,456,456
BEGIN DESCRIPTION:
TRIB 3 TO COLETO CREEK 5.0
END DESCRIPTION:
XS GIS Cut Line= 3
      2555424.98     13472325.01        2555925.       13471875.
        2555775.     13471524.99
#Sta/Elev= 30
  4326.9  118.04  4383.4  117.18  4390.8  116.64  4397.6  116.57    4405  115.84
  4454.4   114.7  4468.6  113.71  4475.3  113.77  4482.8  113.27  4517.9  112.46
  4525.4  111.87  4532.1  111.93  4553.8  110.82  4560.5   110.9    4568  110.32
  4574.7  110.38  4617.3  107.72  4688.3  104.58  4723.4  103.36    4766  101.09
  4822.8   99.31  4889.1   98.45  4900.6   98.31  4907.3      98  5014.1      98
    5054   98.41  5117.2   98.82  5242.6  103.44    5326  107.43  5380.4  108.97
#Mann= 3 ,-1 , 0
  4326.9     .07       0  4889.1    .033       0  5117.2     .05       0
Bank Sta=4900.6,5054
XS Rating Curve= 0 ,0
Exp/Cntr=0.3,0.1

Type RM Length L Ch R = 1 ,3131    ,1347,1347,1347
BEGIN DESCRIPTION:
TRIB 3 TO COLETO CREEK 4.0
END DESCRIPTION:
XS GIS Cut Line= 3
      2555375.03     13472574.98        2556275.       13471775.
        2556225.     13471275.02
#Sta/Elev= 30
  3795.3  120.99  3816.6  119.55  3873.5  117.25  3913.5  116.71  3922.8  115.98
  3929.5  116.22    3937   115.5  3943.7  115.73  3951.2  115.01  3957.9  115.25
  3965.4  114.53  3986.3  114.21  4008.1  112.76    4029  112.04  4043.2   110.6
  4100.1  108.55  4149.4  107.78  4163.6   106.8  4269.8  102.98  4298.3  101.42
  4472.1   98.75    4560   98.18  4567.5      98  4579.7      98  4583.7      98
    5110   98.12  5118.1   98.28  5210.5  100.12  5311.8   104.6  5501.9  113.35
#Mann= 7 ,-1 , 0
  3795.3     .05       0  3913.5     .07       0  4472.1    .033       0
  4579.7    .033       0  4583.7    .033       0  5118.1    .045       0
  5311.8     .05       0
Bank Sta=4560,5110
XS Rating Curve= 0 ,0
Exp/Cntr=0.3,0.1

Type RM Length L Ch R = 1 ,1784    ,376,376,376
BEGIN DESCRIPTION:
TRIB 3 TO COLETO CREEK 3.0
END DESCRIPTION:
XS GIS Cut Line= 3
      2555424.96     13472875.01        2556625.       13472575.
        2556625.     13471074.97
#Sta/Elev= 30
  3762.5  119.23  3765.1  119.23  3780.6   117.4  3785.7  117.35  3803.8  115.52
  3821.8  114.42    3827  114.37  3904.3  110.54  3909.4  110.52  3945.5  108.81
  3981.5  107.41  3986.7  107.12  3991.9  107.14    4028  105.41  4033.1  105.42
  4069.2  103.69  4074.3  103.72  4110.4  102.07  4115.6   102.1  4134.2  101.46
  4192.9   99.65  4238.8   98.97  4308.9   98.11  4314.6      98  6009.5   98.12
  6085.9   98.25  6199.5   99.43  6319.5   101.4  6399.5  102.37  6499.5  105.24
#Mann= 6 ,-1 , 0
  3762.5     .05       0  3981.5     .07       0  4134.2     .05       0
  4238.8     .07       0  4308.9     .03       0  6085.9    .045       0
Bank Sta=4308.9,6009.5
XS Rating Curve= 0 ,0
Exp/Cntr=0.3,0.1

Type RM Length L Ch R = 1 ,1408    ,0,0,0
BEGIN DESCRIPTION:
TRIB 3 TO COLETO CREEK 2.0
END DESCRIPTION:
XS GIS Cut Line= 4
        2555525.       13472925.      2556591.28       13472925.
      2556929.82     13472734.13       2557025.3     13470694.18
#Sta/Elev= 25
  3832.8   112.8  3835.3   112.8  3842.8   112.3  3872.8  110.85  3951.8  107.61
  4017.7  104.71  4072.8   102.3  4162.8   99.35  4172.8   99.17  4262.8   98.11
  4270.8      98  6708.4      98  6778.5   98.27  6818.5   98.37  6948.7   98.98
    7005    99.1  7038.8   99.23  7138.9  100.02  7158.9  100.64  7208.9  102.37
  7215.2  102.71  7220.2  102.68  7319.1  106.44    7327  106.82  7329.9  106.82
#Mann= 5 ,-1 , 0
  3832.8     .05       0  3951.8     .07       0  4017.7     .05       0
  4262.8     .03       0    7005     .05       0
Bank Sta=4262.8,6778.5
XS Rating Curve= 0 ,0
Exp/Cntr=0.3,0.1

Chan Stop Cuts=-1
Use User Specified Reach Order=0
Composite Channel Slope=5