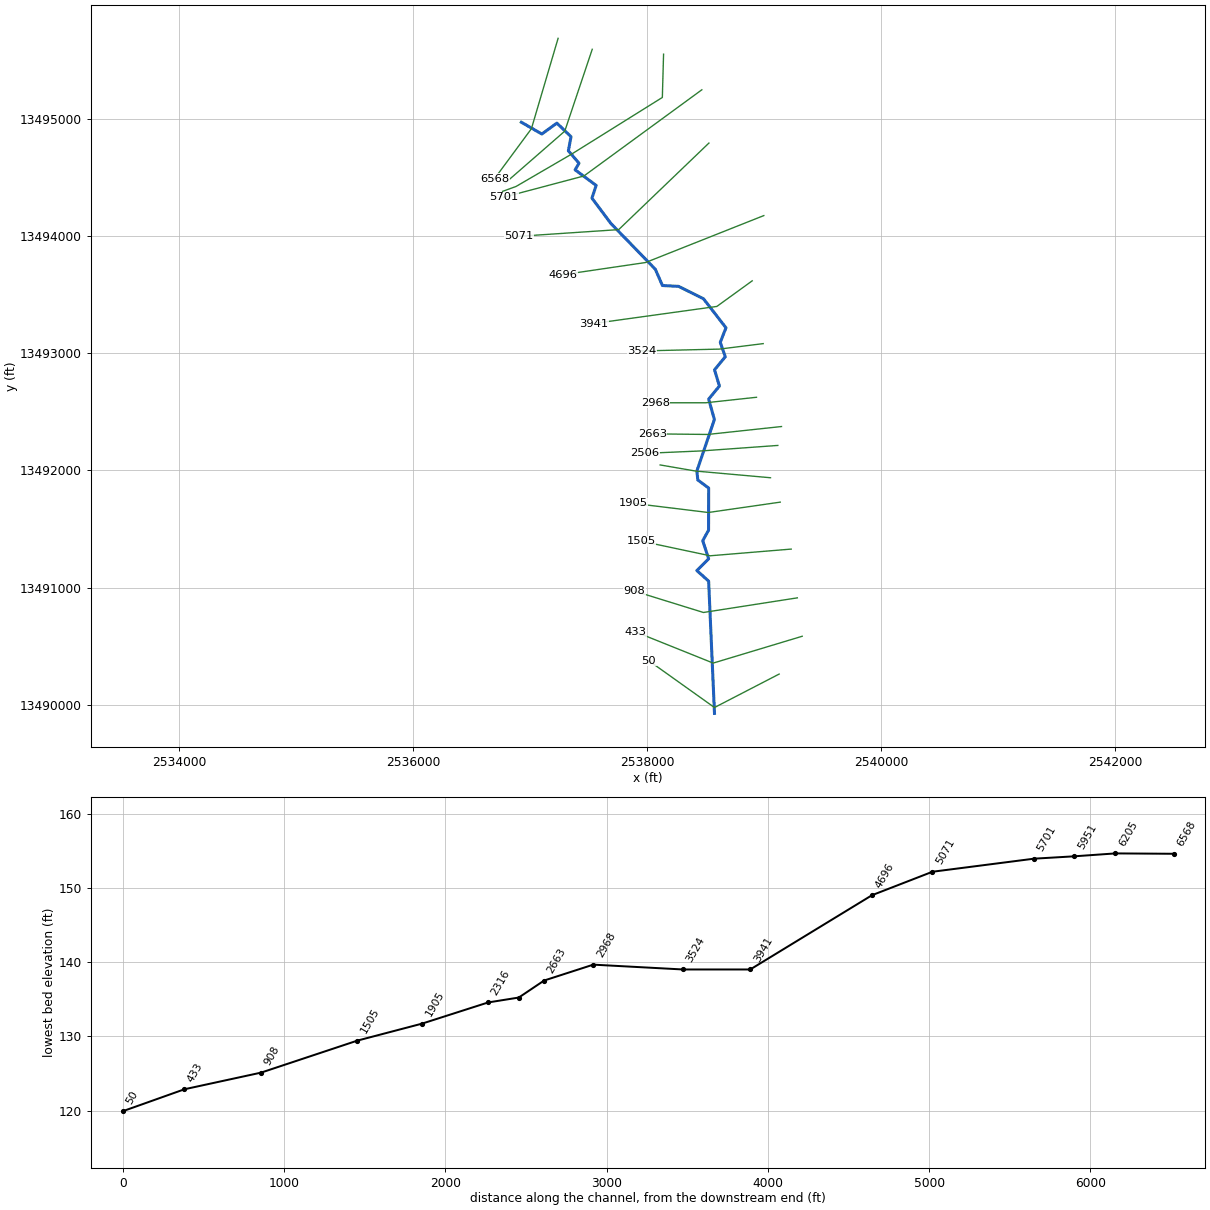
--- TRIB 3 TO HOG THIEF CREEK.prj (project) ---

Proj Title=TRIB 3 TO HOG THIEF CREEK Base Level Engineering
Current Plan=p01
Default Exp/Contr=0.3,0.1
English Units
Geom File=g01
Flow File=f01
Plan File=p01
Y Axis Title=Elevation
X Axis Title(PF)=Main Channel Distance
X Axis Title(XS)=Station
BEGIN DESCRIPTION:
TRIB 3 TO HOG THIEF CREEK
END DESCRIPTION:
DSS Export Rating Curves= 0
DSS Export Rating Curve Sorted= 0
DSS Export Volume Flow Curves= 0
DXF OffsetX= 0
DXF OffsetY= 0
DXF ScaleX= 1
DXF ScaleY= 10

--- TRIB 3 TO HOG THIEF CREEK.p01 (plan) ---

Plan Title=Multiple Run
Short Identifier=Multiple
Geom File=g01
Flow File=f01
Subcritical Flow
K Sum by GR= 0
Std Step Tol= 0.01
Critical Tol= 0.01
Num of Std Step Trials= 20
Max Error Tol= 0.3
Flow Tol Ratio= 0.001
Split Flow NTrial= 30
Split Flow Tol= 0.02
Split Flow Ratio= 0.02
Log Output Level= 0
Friction Slope Method= 1
Unsteady Friction Slope Method= 2
Unsteady Bridges Friction Slope Method= 1
Parabolic Critical Depth
Global Vel Dist=  1 , 1 , 1
Global Log Level= 0
CheckData=True
Encroach Param= -1, 0, 0, 0
BEGIN DESCRIPTION:
Multiple Run
END DESCRIPTION:

--- TRIB 3 TO HOG THIEF CREEK.f01 (steady flow) ---

Flow Title=Multiple
Number of Profiles=7
Profile Names=10-year,25-year,50-year,1pct_min,100-year,1pct_plu,500-year
River Rch & RM= TRIB 3 TO HOG TH,Reach-1,6568
     288     430     548     339     677    1351    1018
River Rch & RM= TRIB 3 TO HOG TH,Reach-1,3524
     443     684     892     563    1124    2243    1764
Boundary for River Rch & Prof#=TRIB 3 TO HOG TH,Reach-1,1
Up Type=0
Dn Type=3
Dn Slope=0.005
Boundary for River Rch & Prof#=TRIB 3 TO HOG TH,Reach-1,2
Up Type=0
Dn Type=3
Dn Slope=0.005
Boundary for River Rch & Prof#=TRIB 3 TO HOG TH,Reach-1,3
Up Type=0
Dn Type=3
Dn Slope=0.005
Boundary for River Rch & Prof#=TRIB 3 TO HOG TH,Reach-1,4
Up Type=0
Dn Type=3
Dn Slope=0.005
Boundary for River Rch & Prof#=TRIB 3 TO HOG TH,Reach-1,5
Up Type=0
Dn Type=3
Dn Slope=0.005
Boundary for River Rch & Prof#=TRIB 3 TO HOG TH,Reach-1,6
Up Type=0
Dn Type=3
Dn Slope=0.005
Boundary for River Rch & Prof#=TRIB 3 TO HOG TH,Reach-1,7
Up Type=0
Dn Type=3
Dn Slope=0.005

--- TRIB 3 TO HOG THIEF CREEK.g01 (geometry) ---

Geom Title=Existing Conditions
Program Version=4.10

River Reach=TRIB 3 TO HOG TH,Reach-1
Reach XY= 30
        2536925.       13494975.      2537100.04      13494874.5
      2537228.34      13494967.4      2537349.28     13494851.69
      2537326.68     13494731.05      2537417.43       13494625.
       2537384.3     13494568.32      2537564.02     13494435.37
      2537528.16     13494326.65      2537688.63     13494111.79
      2538069.38     13493719.37      2538130.42     13493580.18
      2538269.06     13493572.75      2538481.06     13493466.86
       2538673.2     13493218.89      2538624.43     13493095.05
      2538667.19     13492971.59      2538575.26     13492859.78
      2538617.19     13492721.59      2538525.25     13492609.78
      2538574.23     13492435.69      2538424.39     13491995.03
      2538432.69     13491918.57      2538525.32      13491850.2
      2538524.46     13491490.21       2538474.6       13491400.
      2538525.11     13491245.27      2538424.47     13491145.13
      2538524.94      13491054.8        2538575.       13489925.

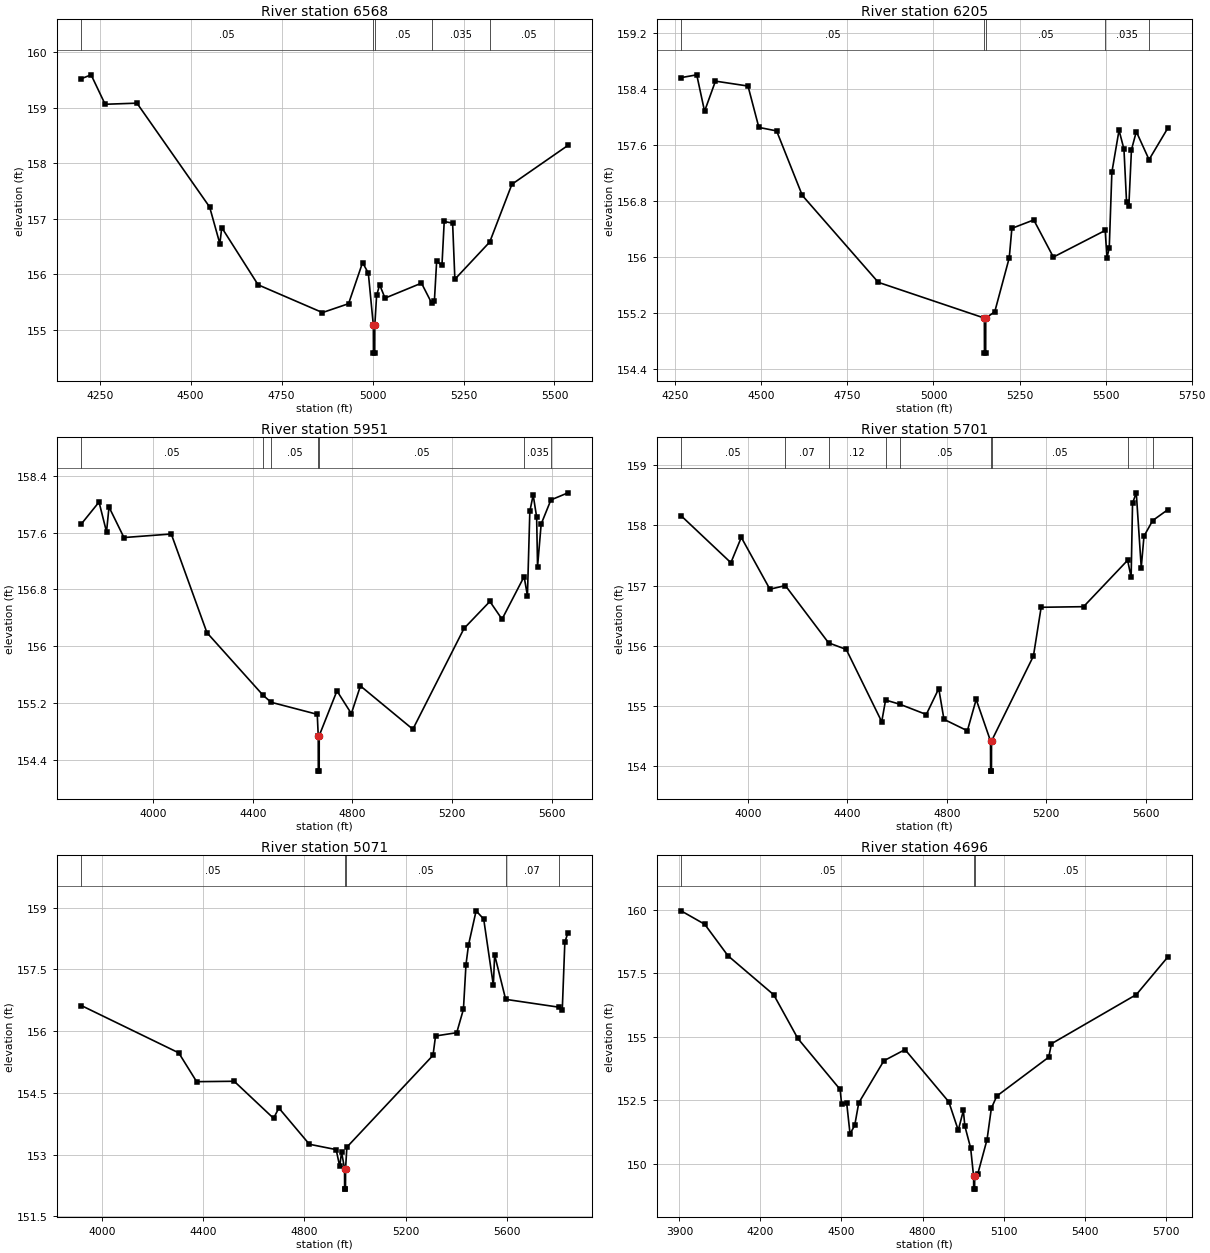
Type RM Length L Ch R = 1 ,6568    ,363,363,363
BEGIN DESCRIPTION:
TRIB 3 TO HOG THIEF CREEK 13.0
END DESCRIPTION:
XS GIS Cut Line= 3
      2537238.91     13495691.83      2537010.95     13494919.66
      2536694.51     13494491.03
#Sta/Elev= 30
  4199.2  159.52  4226.3  159.59  4264.8  159.06  4352.3  159.08  4552.1  157.21
  4580.2  156.55  4585.4  156.84  4685.3  155.81  4862.2  155.31    4934  155.47
  4972.5  156.21  4988.3  156.02  5002.1  155.08  5002.4  154.58  5005.9  154.58
  5006.1  155.08  5011.1  155.62  5019.5  155.81  5034.2  155.57  5134.4  155.84
  5162.5  155.48  5169.9  155.52  5176.1  156.23  5190.7  156.16  5196.9  156.95
    5220  156.92  5226.2  155.91    5322  156.58    5383  157.62  5537.1  158.32
#Mann= 5 ,-1 , 0
  4199.2     .05       0  5002.1     .05       0  5006.1     .05       0
  5162.5    .035       0    5322     .05       0
Bank Sta=5002.1,5006.1
XS Rating Curve= 0 ,0
Exp/Cntr=0.3,0.1

Type RM Length L Ch R = 1 ,6205    ,254,254,254
BEGIN DESCRIPTION:
Mapping XS 36f1a2d8
END DESCRIPTION:
XS GIS Cut Line= 3
      2537530.58     13495598.09      2537295.89     13494898.91
      2536786.05     13494454.44
#Sta/Elev= 30
  4266.8  158.56  4312.3   158.6    4335  158.08  4366.6  158.51  4461.2  158.44
  4492.7  157.85  4544.3   157.8  4618.9  156.88  4839.7  155.64  5147.8  155.13
  5148.1  154.63  5151.6  154.63  5151.8  155.13    5178  155.22  5220.1  155.99
  5227.7  156.41  5291.3  156.53  5348.2     156  5498.8  156.38  5503.9  155.99
  5510.6  156.13  5518.2  157.21    5539  157.81  5553.3  157.54  5560.9  156.78
  5567.5  156.73  5575.1  157.53  5589.2  157.79  5626.2  157.39  5680.7  157.84
#Mann= 5 ,-1 , 0
  4266.8     .05       0  5147.8     .05       0  5151.8     .05       0
  5498.8    .035       0  5626.2     .05       0
Bank Sta=5147.8,5151.8
XS Rating Curve= 0 ,0
Exp/Cntr=0.3,0.1

Type RM Length L Ch R = 1 ,5951    ,250,250,250
BEGIN DESCRIPTION:
Mapping XS 4f2f3f4d
END DESCRIPTION:
XS GIS Cut Line= 5
      2538139.96     13495556.42      2538129.54     13495186.65
       2537353.5     13494702.28      2536879.54     13494426.24
      2536764.98     13494384.58
#Sta/Elev= 30
  3710.6  157.72    3782  158.03  3812.1  157.61  3822.1  157.96  3882.1  157.53
  4072.2  157.58  4215.5  156.19  4440.6  155.31  4473.1  155.21  4658.6  155.04
  4662.5  154.74  4662.8  154.24  4666.3  154.24  4666.5  154.74  4737.7  155.37
  4795.5  155.05    4832  155.44  5042.6  154.83  5248.2  156.25    5352  156.63
  5400.8  156.38  5489.5  156.98  5502.8  156.71  5512.5   157.9  5525.9  158.13
  5539.8  157.82  5543.5  157.12    5558  157.72  5597.1  158.06  5665.7  158.16
#Mann= 7 ,-1 , 0
  3710.6     .05       0  4440.6     .07       0  4473.1     .05       0
  4662.5     .05       0  4666.5     .05       0  5489.5    .035       0
  5597.1     .05       0
Bank Sta=4662.5,4666.5
XS Rating Curve= 0 ,0
Exp/Cntr=0.3,0.1

Type RM Length L Ch R = 1 ,5701    ,630,630,630
BEGIN DESCRIPTION:
Mapping XS 69fb1dd1
END DESCRIPTION:
XS GIS Cut Line= 3
      2538466.78     13495252.17      2537459.84     13494516.09
       2536772.3     13494333.79
#Sta/Elev= 30
  3730.9  158.16  3931.3  157.38  3973.2   157.8  4088.3  156.94  4150.5     157
  4324.3  156.05  4395.6  155.94  4538.3  154.74  4553.8   155.1  4611.5  155.03
  4717.6  154.86  4767.8  155.29  4788.7  154.78  4882.9  154.59  4918.4  155.11
  4976.1  154.42  4976.4  153.92  4979.9  153.92  4980.1  154.42  5148.7  155.83
  5179.8  156.64  5350.5  156.65  5527.7  157.42  5541.9  157.14  5547.6  158.37
  5562.6  158.54  5582.6   157.3  5593.6  157.82  5628.6  158.08  5689.5  158.26
#Mann= 9 ,-1 , 0
  3730.9     .05       0  4150.5     .07       0  4324.3     .12       0
  4553.8     .07       0  4611.5     .05       0  4976.1     .05       0
  4980.1     .05       0  5527.7    .035       0  5628.6     .05       0
Bank Sta=4976.1,4980.1
XS Rating Curve= 0 ,0
Exp/Cntr=0.3,0.1

Type RM Length L Ch R = 1 ,5071    ,375,375,375
BEGIN DESCRIPTION:
Mapping XS 4b38db04
END DESCRIPTION:
XS GIS Cut Line= 3
      2538527.55     13494797.34      2537756.71     13494057.75
       2536902.6     13494000.47
#Sta/Elev= 30
    3918  156.62  4303.4  155.47  4374.2  154.77  4522.6  154.78  4678.3  153.88
  4699.3  154.13  4819.8  153.25  4925.8  153.12  4939.9  152.71  4947.1  153.06
    4959  152.66  4959.2  152.16  4962.7  152.16    4963  152.66  4968.2  153.18
  5308.7  155.41  5318.7  155.88  5402.5  155.96    5429  156.53    5439  157.61
    5449  158.09  5479.1  158.92  5509.1  158.72  5547.3  157.11  5552.3  157.85
  5595.9  156.77  5805.7  156.58  5819.8  156.52  5829.9  158.16  5842.3  158.39
#Mann= 5 ,-1 , 0
    3918     .05       0    4959     .05       0    4963     .05       0
  5595.9     .07       0  5805.7    .035       0
Bank Sta=4959,4963
XS Rating Curve= 0 ,0
Exp/Cntr=0.3,0.1

Type RM Length L Ch R = 1 ,4696    ,755,755,755
BEGIN DESCRIPTION:
Mapping XS e6c0e187
END DESCRIPTION:
XS GIS Cut Line= 3
      2538996.29     13494177.55      2537985.88      13493776.5
      2537278.78     13493672.52
#Sta/Elev= 30
  3906.3  159.97  3993.8  159.44  4079.8   158.2  4249.3  156.66  4338.4  154.94
    4495  152.93  4500.4  152.37  4519.3   152.4  4531.7  151.18    4549  151.51
    4564   152.4    4657  154.06  4735.4   154.5  4897.4  152.44  4932.4  151.32
  4951.3   152.1  4956.7  151.49  4978.2  150.62  4989.2   149.5  4989.4     149
  4992.9     149  4993.2   149.5  5004.4  149.59  5038.9  150.95  5054.9  152.19
  5075.1  152.67  5267.2   154.2  5277.3  154.73  5591.8  156.67  5708.1  158.15
#Mann= 3 ,-1 , 0
  3906.3     .05       0  4989.2     .05       0  4993.2     .05       0
Bank Sta=4989.2,4993.2
XS Rating Curve= 0 ,0
Exp/Cntr=0.3,0.1

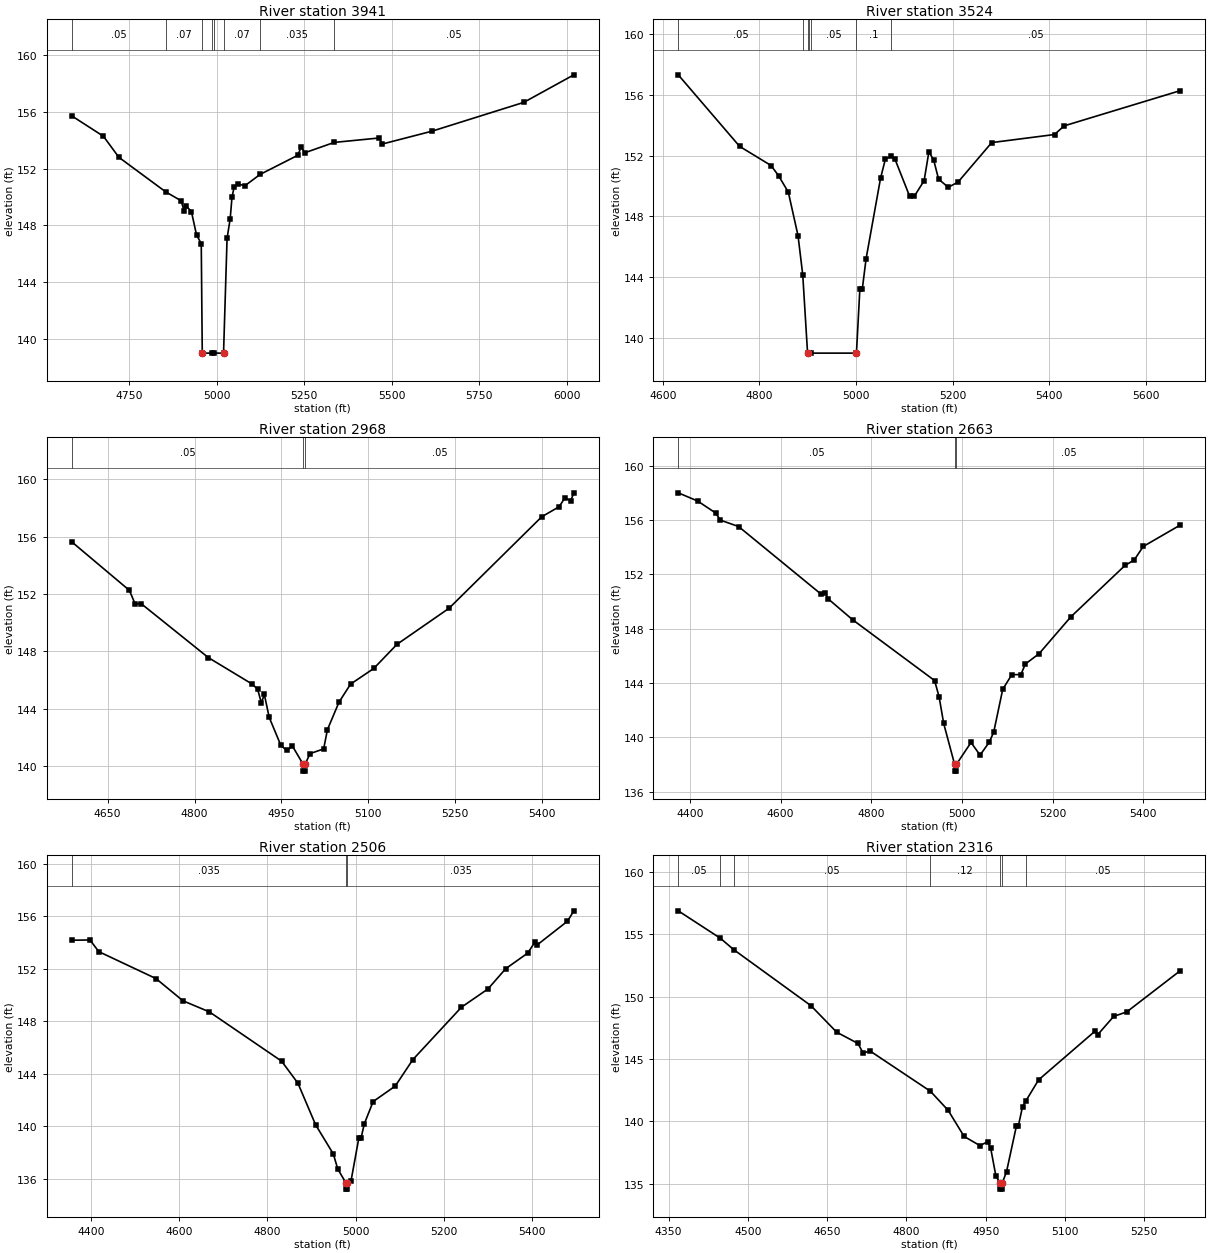
Type RM Length L Ch R = 1 ,3941    ,417,417,417
BEGIN DESCRIPTION:
Mapping XS 7c444f26
END DESCRIPTION:
XS GIS Cut Line= 3
      2538897.36     13493620.27      2538595.25      13493401.5
      2537543.21     13493255.68
#Sta/Elev= 30
  4585.7  155.71  4676.3  154.27  4720.4  152.79  4854.1  150.36  4898.3  149.73
  4906.8  149.01    4913  149.35  4927.7  148.97  4942.4  147.31  4955.8  146.72
  4958.7     139  4987.2     139  4991.2     139  5019.5     139  5029.6  147.08
  5038.6  148.48  5043.6  149.97  5049.8   150.7  5059.9  150.93  5080.1  150.78
  5124.3  151.59  5231.5  152.93  5241.6  153.52  5251.7  153.11  5335.9  153.84
  5463.7  154.15  5473.8  153.73  5615.2  154.63  5877.7  156.66  6020.8   158.6
#Mann= 8 ,-1 , 0
  4585.7     .05       0  4854.1     .07       0  4958.7     .05       0
  4987.2     .05       0  4991.2     .05       0  5019.5     .07       0
  5124.3    .035       0  5335.9     .05       0
Bank Sta=4958.7,5019.5
XS Rating Curve= 0 ,0
Exp/Cntr=0.3,0.1

Type RM Length L Ch R = 1 ,3524    ,556,556,556
BEGIN DESCRIPTION:
Mapping XS ca582538
END DESCRIPTION:
XS GIS Cut Line= 3
      2538991.11      13493083.8      2538616.09     13493036.92
      2537954.61      13493021.3
#Sta/Elev= 30
  4631.9  157.32    4759  152.61  4824.1  151.35  4839.6  150.68  4859.8   149.6
  4879.9  146.74  4889.7  144.16  4899.7     139  4902.8     139  4906.8     139
  5000.9     139  5007.9  143.19  5012.9  143.19  5020.9  145.22  5050.9  150.53
  5060.9  151.78  5073.1  151.95  5080.9  151.75    5111  149.33    5121  149.34
    5141  150.35    5151  152.27    5161  151.69    5171  150.45    5191  149.92
    5211  150.25    5281  152.86    5411  153.39    5431  153.96  5671.5  156.28
#Mann= 7 ,-1 , 0
  4631.9     .05       0  4889.7      .1       0  4899.7     .05       0
  4902.8     .05       0  4906.8     .05       0  5000.9      .1       0
  5073.1     .05       0
Bank Sta=4899.7,5000.9
XS Rating Curve= 0 ,0
Exp/Cntr=0.3,0.1

Type RM Length L Ch R = 1 ,2968    ,305,305,305
BEGIN DESCRIPTION:
Mapping XS 96db03b2
END DESCRIPTION:
XS GIS Cut Line= 3
      2538933.81     13492625.46       2538501.5     13492578.59
      2538069.64     13492578.59
#Sta/Elev= 30
    4588  155.64  4687.4  152.26  4697.4  151.31  4707.5  151.34  4823.7  147.57
  4898.6  145.74  4908.7  145.38  4915.3  144.41  4920.4     145  4928.8   143.4
  4948.9  141.45    4959  141.09    4969  141.39  4987.1  140.15  4987.4  139.65
  4990.9  139.65  4991.1  140.15  4999.2  140.87  5022.8   141.2  5029.3  142.54
  5049.3  144.46  5069.3  145.72  5109.3  146.81  5149.3  148.49  5239.3  151.01
  5399.3  157.39  5429.3  158.09  5439.3  158.71  5449.3  158.51  5454.7  159.06
#Mann= 3 ,-1 , 0
    4588     .05       0  4987.1     .05       0  4991.1     .05       0
Bank Sta=4987.1,4991.1
XS Rating Curve= 0 ,0
Exp/Cntr=0.3,0.1

Type RM Length L Ch R = 1 ,2663    ,157,157,157
BEGIN DESCRIPTION:
Mapping XS 1bbcc020
END DESCRIPTION:
XS GIS Cut Line= 3
      2539147.35     13492375.46      2538517.13     13492307.75
      2538043.21     13492312.96
#Sta/Elev= 30
  4374.2     158  4416.8   157.4    4457  156.51  4467.1  155.99  4507.3  155.52
  4688.3  150.57  4698.4  150.65  4704.8   150.2  4758.8  148.66  4939.8  144.18
  4949.8  142.98  4959.9  141.02    4984  138.01  4984.3  137.51  4987.8  137.51
    4988  138.01  5020.2  139.62  5040.2  138.69  5060.2  139.63  5070.2  140.37
  5090.2  143.54  5110.2  144.61  5130.2  144.62  5140.2   145.4  5170.2  146.15
  5240.2  148.86  5360.2  152.66  5380.2  153.05  5400.2  154.05    5482  155.63
#Mann= 3 ,-1 , 0
  4374.2     .05       0    4984     .05       0    4988     .05       0
Bank Sta=4984,4988
XS Rating Curve= 0 ,0
Exp/Cntr=0.3,0.1

Type RM Length L Ch R = 1 ,2506    ,190,190,190
BEGIN DESCRIPTION:
Mapping XS ef0116be
END DESCRIPTION:
XS GIS Cut Line= 3
       2539116.1     13492214.01      2538465.05     13492167.13
      2537980.63     13492146.29
#Sta/Elev= 30
    4357  154.18  4398.2   154.2  4418.3  153.31  4547.8  151.26  4608.8  149.57
  4668.9  148.72  4832.4  144.97  4869.4  143.29  4909.5  140.12  4949.6   137.9
  4959.7  136.75  4977.7  135.72    4978  135.22  4981.5  135.22  4981.7  135.72
  4989.7  135.84  5007.3  139.09  5012.3  139.09  5019.8  140.19  5039.8  141.89
  5089.9  143.07  5129.9  145.09    5240  149.08  5300.1  150.47  5340.1  152.01
  5390.1   153.2  5406.8  154.06  5411.8  153.83  5480.2  155.63  5494.6  156.42
#Mann= 3 ,-1 , 0
    4357    .035       0  4977.7    .035       0  4981.7    .035       0
Bank Sta=4977.7,4981.7
XS Rating Curve= 0 ,0
Exp/Cntr=0.3,0.1

Type RM Length L Ch R = 1 ,2316    ,411,411,411
BEGIN DESCRIPTION:
Mapping XS 5c3135d7
END DESCRIPTION:
XS GIS Cut Line= 3
      2539053.57     13491937.96      2538412.96     13491995.25
      2538110.88     13492047.34
#Sta/Elev= 30
  4368.3  156.89    4448  154.69  4473.1  153.78  4619.3  149.28  4668.1  147.15
  4708.2  146.25  4718.3  145.46  4730.6  145.66  4845.4  142.41  4878.9  140.88
    4909  138.79  4939.1  138.05  4953.3  138.36  4959.2  137.87  4969.3  135.58
  4977.3  135.06  4977.5  134.56    4981  134.56  4981.3  135.06  4989.3  135.96
  5007.9  139.61  5011.5  139.61  5019.5  141.16  5025.3   141.6    5050  143.33
  5156.8  147.24  5161.9  146.96    5192  148.42  5216.7  148.78    5318  152.09
#Mann= 7 ,-1 , 0
  4368.3     .05       0    4448     .12       0  4473.1     .05       0
  4845.4     .12       0  4977.3     .05       0  4981.3     .12       0
  5025.3     .05       0
Bank Sta=4977.3,4981.3
XS Rating Curve= 0 ,0
Exp/Cntr=0.3,0.1

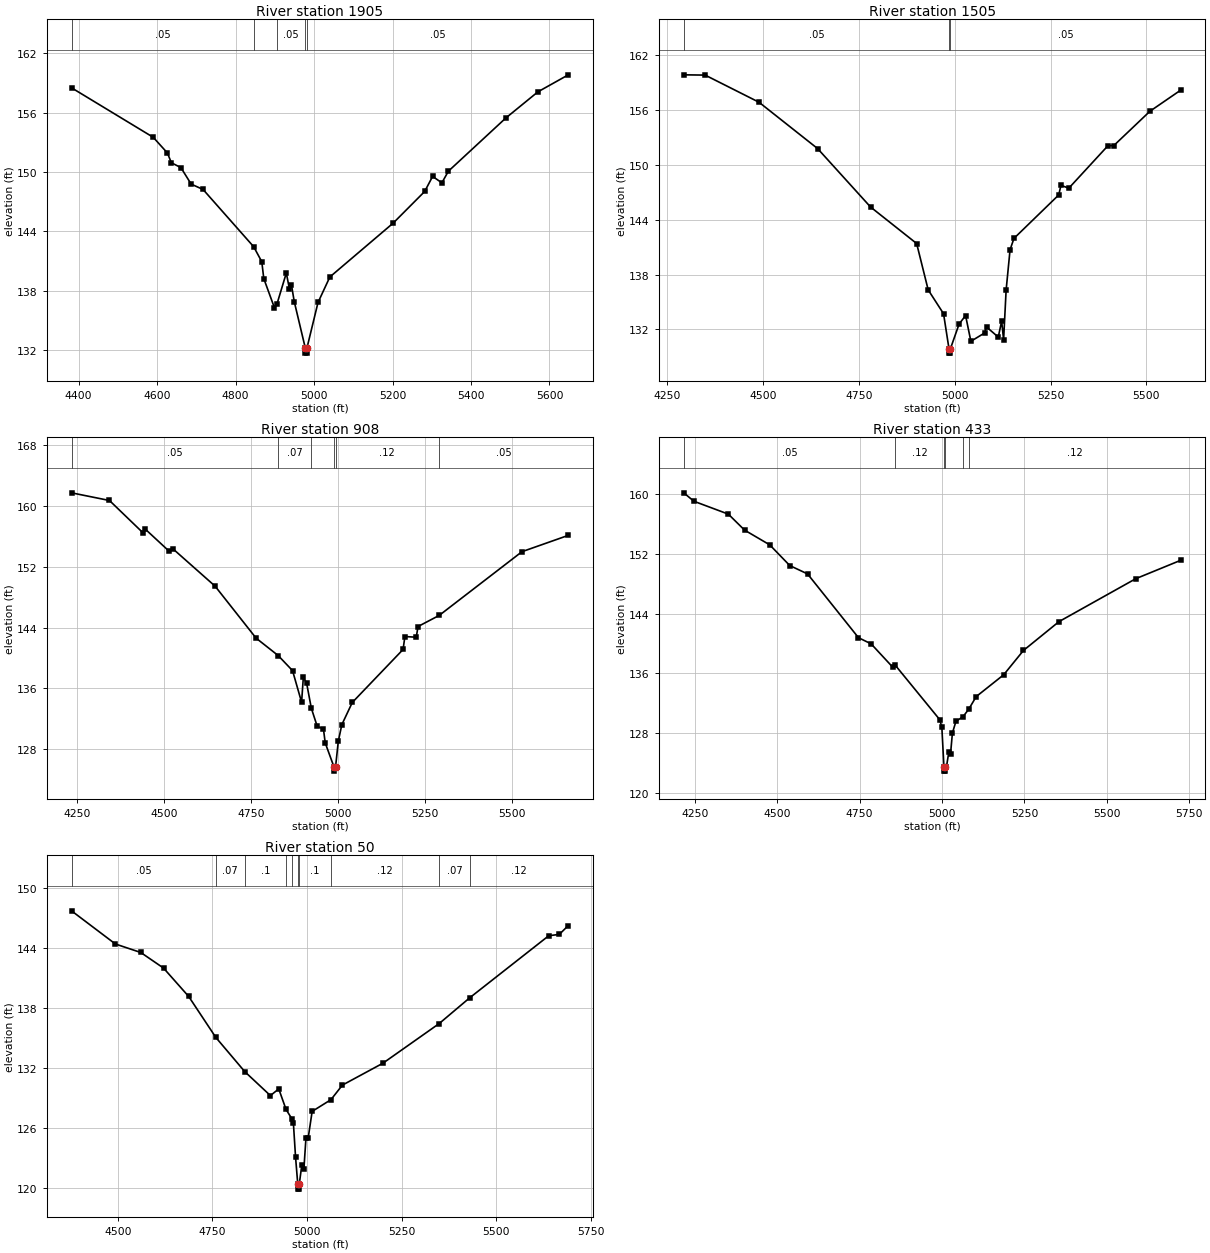
Type RM Length L Ch R = 1 ,1905    ,400,400,400
BEGIN DESCRIPTION:
Mapping XS b5800ef9
END DESCRIPTION:
XS GIS Cut Line= 3
       2539136.9     13491729.63      2538522.34     13491641.09
      2537881.69     13491719.22
#Sta/Elev= 30
  4381.8  158.53  4590.2  153.52  4626.2  151.94  4636.3  150.95  4660.6  150.46
  4686.8  148.79  4717.1  148.25  4846.3  142.45  4866.8  140.94  4871.9  139.24
    4899  136.29  4905.3  136.64  4929.3   139.8  4937.3  138.19  4942.3  138.62
  4949.5  136.92  4977.8   132.2  4978.1   131.7  4981.6   131.7  4981.8   132.2
  5010.1  136.82  5040.3   139.4  5201.5  144.84  5282.1  148.05  5302.2  149.57
  5325.8  148.92  5342.5   150.1    5489  155.48  5570.6  158.12  5648.1  159.84
#Mann= 5 ,-1 , 0
  4381.8     .05       0  4846.3     .12       0  4905.3     .05       0
  4977.8     .05       0  4981.8     .05       0
Bank Sta=4977.8,4981.8
XS Rating Curve= 0 ,0
Exp/Cntr=0.3,0.1

Type RM Length L Ch R = 1 ,1505    ,597,597,597
BEGIN DESCRIPTION:
Mapping XS 49a069ae
END DESCRIPTION:
XS GIS Cut Line= 3
      2539230.63     13491328.58      2538537.96      13491271.3
      2537949.72     13491396.23
#Sta/Elev= 30
  4292.7  159.79  4348.5  159.76    4489   156.8    4642  151.74    4780  145.37
  4900.4  141.38  4930.5  136.32  4970.6  133.72  4984.7  129.92    4985  129.42
  4988.5  129.42  4988.7  129.92  5011.2   132.6  5028.1  133.52  5041.9  130.71
  5077.7  131.62  5082.8  132.27  5113.4  131.17  5122.2  132.91  5127.3  130.89
  5133.9  136.31  5144.1  140.69  5154.3  141.94  5271.1  146.68    5277  147.73
  5297.5  147.42  5399.7  152.06  5414.9  152.07    5509  155.81  5589.1  158.11
#Mann= 3 ,-1 , 0
  4292.7     .05       0  4984.7     .05       0  4988.7     .05       0
Bank Sta=4984.7,4988.7
XS Rating Curve= 0 ,0
Exp/Cntr=0.3,0.1

Type RM Length L Ch R = 1 ,908     ,475,475,475
BEGIN DESCRIPTION:
Mapping XS 980d0a2b
END DESCRIPTION:
XS GIS Cut Line= 3
      2539282.76     13490911.92      2538480.67     13490786.92
      2537892.12     13490969.21
#Sta/Elev= 30
  4233.1  161.75  4342.2  160.74  4439.4  156.45  4444.4     157  4514.2  154.04
  4524.3  154.39  4645.8  149.46  4763.6  142.62    4827  140.33  4868.4  138.34
  4894.4  134.18  4899.4  137.45  4908.9  136.68  4922.4  133.39  4939.3  131.01
  4957.2  130.66  4962.3  128.83  4987.9  125.61  4988.1  125.11  4991.9  125.61
    5000  129.08  5010.1  131.23  5040.1  134.15  5186.1  141.13  5191.3  142.83
  5223.9  142.74  5229.1  144.15  5289.9  145.61  5527.8     154    5661  156.15
#Mann= 6 ,-1 , 0
  4233.1     .05       0    4827     .07       0  4922.4     .12       0
  4987.9     .05       0  4991.9     .12       0  5289.9     .05       0
Bank Sta=4987.9,4991.9
XS Rating Curve= 0 ,0
Exp/Cntr=0.3,0.1

Type RM Length L Ch R = 1 ,433     ,383,383,383
BEGIN DESCRIPTION:
Mapping XS 8a78d70b
END DESCRIPTION:
XS GIS Cut Line= 3
      2539324.43      13490583.8        2538564.     13490354.63
      2537902.83     13490620.14
#Sta/Elev= 30
  4216.8  160.21  4247.5  159.08    4352  157.35  4401.1  155.21  4477.5  153.23
  4538.3  150.45  4592.2  149.33  4746.7  140.77  4784.9  139.95  4850.9   136.8
  4857.1  137.14  4993.4  129.76  4999.5  128.75  5005.9  123.37  5006.1  122.87
  5009.6  122.87  5009.9  123.37  5013.2  123.37  5020.4  125.37  5025.8  125.15
  5031.5  127.98  5042.3  129.56  5063.4  130.16  5080.8  131.16  5103.7  132.87
  5187.1   135.8    5247  139.06  5354.8  142.93  5587.7  148.69  5723.5  151.15
#Mann= 6 ,-1 , 0
  4216.8     .05       0  4857.1     .12       0  5005.9     .05       0
  5009.9     .12       0  5063.4      .1       0  5080.8     .12       0
Bank Sta=5005.9,5009.9
XS Rating Curve= 0 ,0
Exp/Cntr=0.3,0.1

Type RM Length L Ch R = 1 ,50      ,0,0,0
BEGIN DESCRIPTION:
TRIB 3 TO HOG THIEF CREEK 1.0
END DESCRIPTION:
XS GIS Cut Line= 3
      2539127.53     13490260.87        2538575.       13489975.
      2538012.98     13490375.45
#Sta/Elev= 30
  4377.9  147.76  4493.8  144.44  4560.9  143.59    4621  142.03  4687.4  139.19
  4759.1  135.09  4835.5  131.67  4903.2  129.27  4925.3  129.94  4944.6  127.88
  4960.9  126.89    4964   126.5  4969.6  123.15  4975.5  120.41  4975.7  119.91
  4979.2  119.91  4979.5  120.41  4986.1  122.29  4991.7  121.94  4997.2  125.05
  5003.1  125.05  5013.5  127.69  5063.1  128.86  5093.4  130.32  5200.4  132.51
  5349.1  136.48  5430.1  139.07  5638.5  145.27  5666.3   145.4  5690.1  146.29
#Mann= 10 ,-1 , 0
  4377.9     .05       0  4759.1     .07       0  4835.5      .1       0
  4944.6     .12       0  4960.9      .1       0  4975.5     .05       0
  4979.5      .1       0  5063.1     .12       0  5349.1     .07       0
  5430.1     .12       0
Bank Sta=4975.5,4979.5
XS Rating Curve= 0 ,0
Exp/Cntr=0.3,0.1

Chan Stop Cuts=-1
Use User Specified Reach Order=0
Composite Channel Slope=5