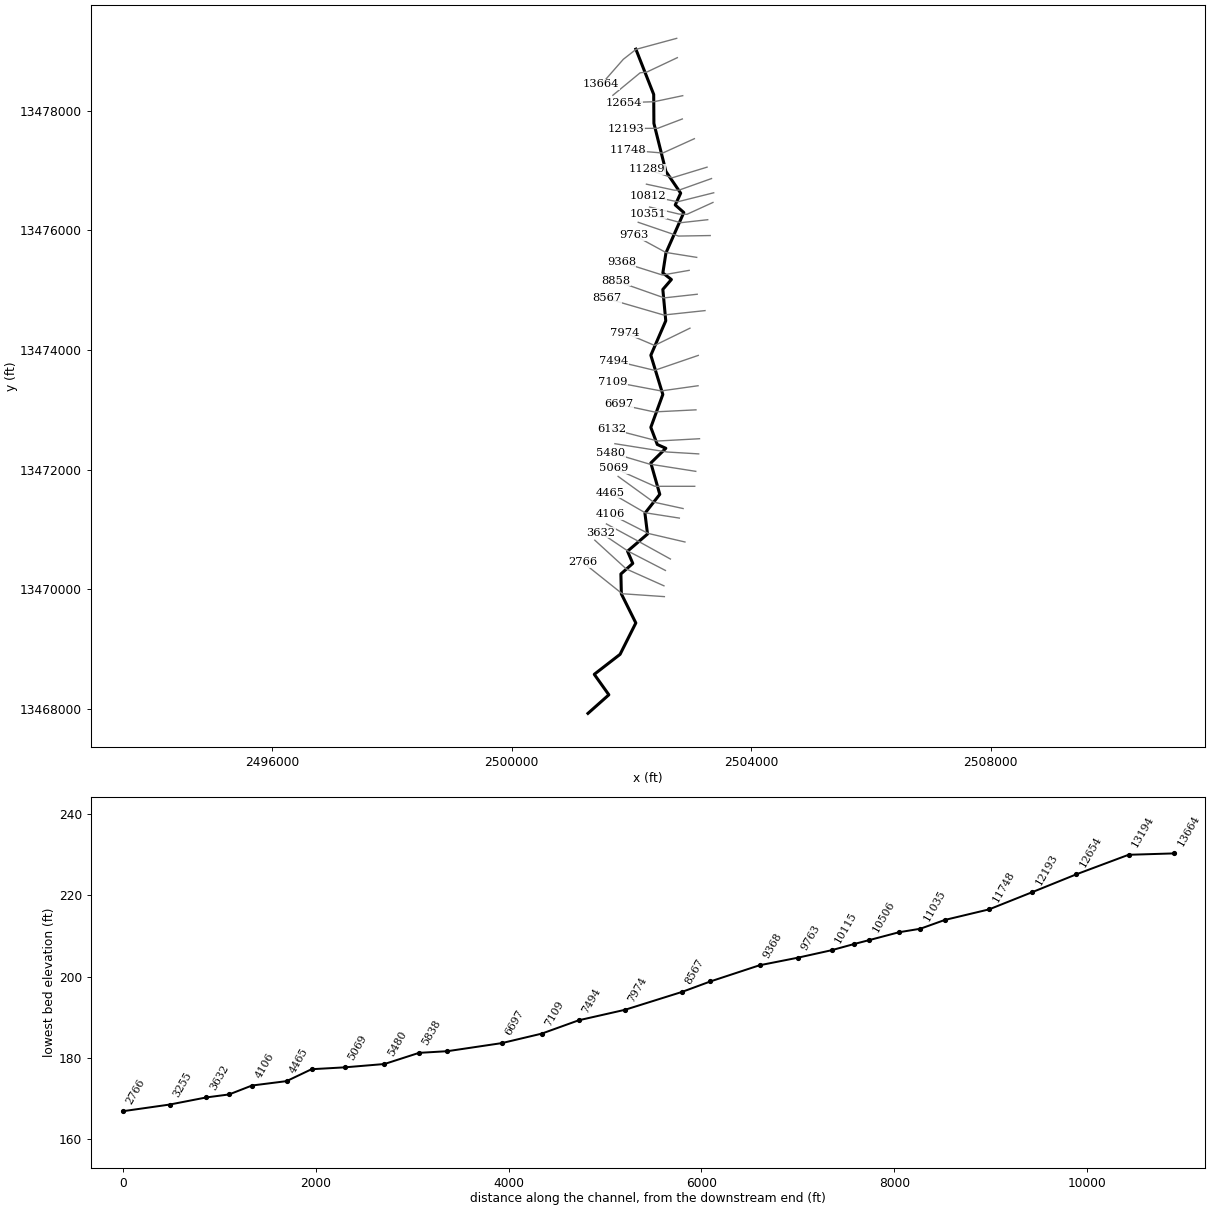
--- TRIB 3 TO PERDIDO CREEK.prj (project) ---

Proj Title=TRIB 3 TO PERDIDO CREEK Base Level Engineering
Current Plan=p01
Default Exp/Contr=0.3,0.1
English Units
Geom File=g01
Flow File=f01
Plan File=p01
Y Axis Title=Elevation
X Axis Title(PF)=Main Channel Distance
X Axis Title(XS)=Station
BEGIN DESCRIPTION:
TRIB 3 TO PERDIDO CREEK
END DESCRIPTION:
DSS Export Rating Curves= 0
DSS Export Rating Curve Sorted= 0
DSS Export Volume Flow Curves= 0
DXF OffsetX= 0
DXF OffsetY= 0
DXF ScaleX= 1
DXF ScaleY= 10

--- TRIB 3 TO PERDIDO CREEK.p01 (plan) ---

Plan Title=Multiple Run
Short Identifier=Multiple
Geom File=g01
Flow File=f01
Subcritical Flow
K Sum by GR= 0
Std Step Tol= 0.01
Critical Tol= 0.01
Num of Std Step Trials= 20
Max Error Tol= 0.3
Flow Tol Ratio= 0.001
Split Flow NTrial= 30
Split Flow Tol= 0.02
Split Flow Ratio= 0.02
Log Output Level= 0
Friction Slope Method= 1
Unsteady Friction Slope Method= 2
Unsteady Bridges Friction Slope Method= 1
Parabolic Critical Depth
Global Vel Dist=  1 , 1 , 1
Global Log Level= 0
CheckData=True
Encroach Param= -1, 0, 0, 0
BEGIN DESCRIPTION:
Multiple Run
END DESCRIPTION:

--- TRIB 3 TO PERDIDO CREEK.f01 (steady flow) ---

Flow Title=Multiple
Number of Profiles=7
Profile Names=10-year,25-year,50-year,1pct_min,100-year,1pct_plu,500-year
River Rch & RM= TRIB 3 TO PERDID,Reach-1,13664
     506     799    1058     679    1354    2702    2194
River Rch & RM= TRIB 3 TO PERDID,Reach-1,7494
     802    1301    1752    1141    2277    4544    3808
Boundary for River Rch & Prof#=TRIB 3 TO PERDID,Reach-1,1
Up Type=0
Dn Type=3
Dn Slope=0.005
Boundary for River Rch & Prof#=TRIB 3 TO PERDID,Reach-1,2
Up Type=0
Dn Type=3
Dn Slope=0.005
Boundary for River Rch & Prof#=TRIB 3 TO PERDID,Reach-1,3
Up Type=0
Dn Type=3
Dn Slope=0.005
Boundary for River Rch & Prof#=TRIB 3 TO PERDID,Reach-1,4
Up Type=0
Dn Type=3
Dn Slope=0.005
Boundary for River Rch & Prof#=TRIB 3 TO PERDID,Reach-1,5
Up Type=0
Dn Type=3
Dn Slope=0.005
Boundary for River Rch & Prof#=TRIB 3 TO PERDID,Reach-1,6
Up Type=0
Dn Type=3
Dn Slope=0.005
Boundary for River Rch & Prof#=TRIB 3 TO PERDID,Reach-1,7
Up Type=0
Dn Type=3
Dn Slope=0.005

--- TRIB 3 TO PERDIDO CREEK.g01 (geometry) ---

Geom Title=Existing Conditions
Program Version=4.10

River Reach=TRIB 3 TO PERDID,Reach-1
Reach XY= 30
        2502075.       13479025.      2502372.76     13478269.07
      2502376.22      13477785.5      2502577.07     13476980.86
      2502823.21     13476618.89      2502732.67     13476421.34
      2502875.39     13476295.28      2502577.06     13475619.15
      2502525.54     13475285.47      2502668.02     13475175.21
      2502525.38     13475009.84      2502574.23     13474485.69
      2502324.96     13473909.66      2502525.29     13473254.82
      2502324.66      13472704.8      2502432.68     13472418.48
      2502575.22     13472354.95      2502324.89     13472109.79
      2502474.44     13471585.64      2502226.54     13471269.15
      2502269.64      13470922.3      2501936.08     13470635.05
      2502023.39     13470431.03      2501825.02      13470254.8
       2501832.8     13469921.58       2502074.3      13469435.7
      2501811.38     13468911.78      2501380.06     13468577.29
      2501624.14     13468235.34        2501275.       13467925.

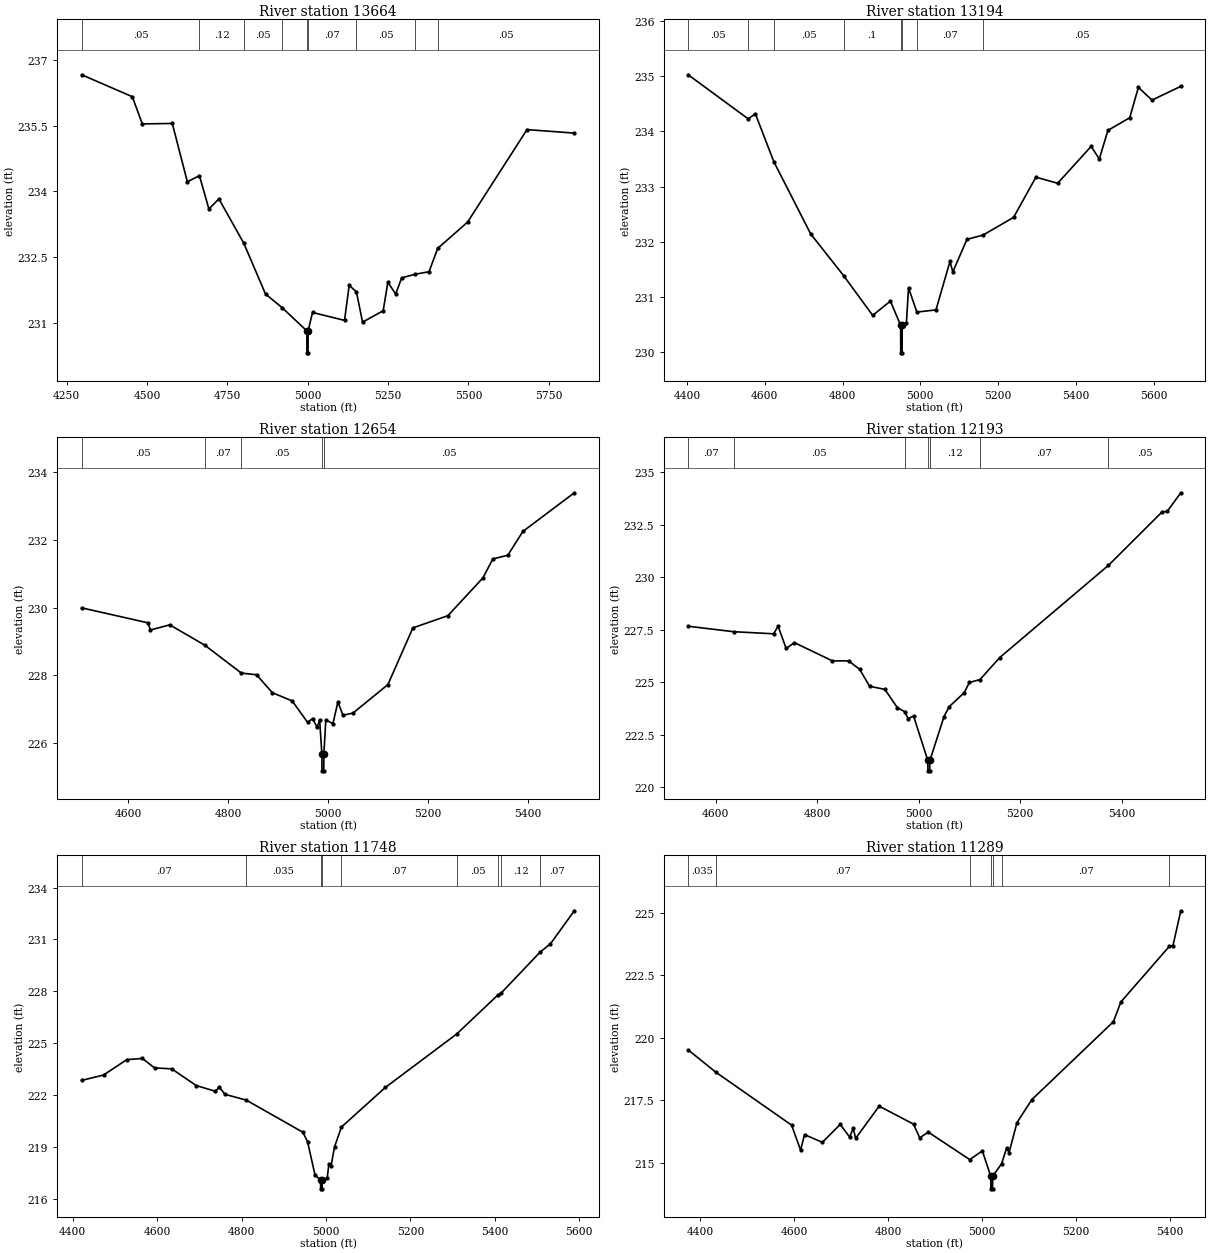
Type RM Length L Ch R = 1 ,13664   ,470,470,470
BEGIN DESCRIPTION:
TRIB 3 TO PERDIDO CREEK 29.0
END DESCRIPTION:
XS GIS Cut Line= 4
      2502756.95     13479206.05      2502078.07     13479021.95
       2501865.7     13478856.06      2501496.52     13478435.23
#Sta/Elev= 30
  4296.6  236.66    4454  236.16  4485.1  235.54  4578.4  235.55  4625.2  234.22
  4662.8  234.36  4692.3   233.6  4723.4  233.83  4800.8  232.82  4868.5  231.66
  4920.2  231.35    4997  230.82  4997.3  230.32  5000.8  230.32    5001  230.82
  5014.8  231.24  5114.3  231.06  5128.8  231.86  5151.3  231.71  5170.4  231.02
  5234.6  231.28  5249.1  231.93  5273.5  231.66  5292.1  232.03  5332.8  232.11
  5377.3  232.17    5404   232.7  5497.1   233.3  5682.1  235.41  5829.3  235.33
#Mann= 9 ,-1 , 0
  4296.6     .05       0  4662.8     .12       0  4800.8     .05       0
  4920.2     .07       0    4997     .05       0    5001     .07       0
  5151.3     .05       0  5332.8     .07       0    5404     .05       0
Bank Sta=4997,5001
XS Rating Curve= 0 ,0
Exp/Cntr=0.3,0.1

Type RM Length L Ch R = 1 ,13194   ,540,540,540
BEGIN DESCRIPTION:
Mapping XS 1ef0e79f
END DESCRIPTION:
XS GIS Cut Line= 4
      2502767.33     13478883.13      2502260.38     13478643.54
       2502145.8     13478629.65      2501690.97     13478254.68
#Sta/Elev= 30
  4403.5  235.03  4557.5  234.23  4576.1  234.32  4623.6  233.45  4718.2  232.14
    4803  231.38  4877.5  230.66    4923  230.92  4949.3  230.48  4949.6  229.98
  4953.1  229.98  4953.3  230.48  4964.2  230.53  4969.6  231.16    4991  230.72
  5040.1  230.76  5076.1  231.64  5083.4  231.45  5119.6  232.04  5161.3  232.12
  5239.5  232.44  5296.8  233.17  5352.8  233.06  5438.9  233.73  5459.7   233.5
  5481.9  234.02  5537.9  234.25  5560.1   234.8  5595.2  234.57  5669.1  234.82
#Mann= 8 ,-1 , 0
  4403.5     .05       0  4557.5     .07       0  4623.6     .05       0
    4803      .1       0  4949.3     .05       0  4953.3      .1       0
    4991     .07       0  5161.3     .05       0
Bank Sta=4949.3,4953.3
XS Rating Curve= 0 ,0
Exp/Cntr=0.3,0.1

Type RM Length L Ch R = 1 ,12654   ,461,461,461
BEGIN DESCRIPTION:
Mapping XS 36079bec
END DESCRIPTION:
XS GIS Cut Line= 3
      2502857.56      13478247.7      2502378.44     13478147.01
      2501881.93     13478129.65
#Sta/Elev= 30
    4507  229.99  4639.5  229.55  4644.6  229.34  4683.3  229.49  4753.5  228.89
  4826.6  228.07    4857  228.02  4888.8  227.49  4928.4  227.25  4959.2  226.62
  4969.4  226.73  4978.3  226.47  4983.4  226.69  4987.9  225.69  4988.1  225.19
  4991.6  225.19  4991.9  225.69  4995.8  226.69    5010  226.58    5020  227.22
    5030  226.83  5050.1  226.89  5120.1  227.73  5170.1   229.4  5240.2  229.76
  5310.2  230.87  5330.2  231.43  5360.2  231.54  5390.3  232.24  5493.4  233.38
#Mann= 5 ,-1 , 0
    4507     .05       0  4753.5     .07       0  4826.6     .05       0
  4987.9     .05       0  4991.9     .05       0
Bank Sta=4987.9,4991.9
XS Rating Curve= 0 ,0
Exp/Cntr=0.3,0.1

Type RM Length L Ch R = 1 ,12193   ,445,445,445
BEGIN DESCRIPTION:
Mapping XS 1131fa3a
END DESCRIPTION:
XS GIS Cut Line= 3
      2502850.66     13477858.82      2502440.94     13477702.57
      2501908.16     13477699.11
#Sta/Elev= 30
  4545.6  227.66  4635.1   227.4  4714.1   227.3  4722.9  227.66  4738.8   226.6
    4755  226.88  4829.9  226.01    4862  226.01  4883.9   225.6  4903.3   224.8
  4933.4  224.65  4958.1  223.78  4972.4  223.59  4979.3  223.26    4990  223.38
    5018  221.27  5018.3  220.77  5021.8  220.77    5022  221.27  5022.6   221.3
    5050  223.35    5060  223.82    5090   224.5    5100  224.98  5120.9  225.12
    5160  226.17  5374.2  230.56  5480.1  233.11  5490.1  233.13  5516.9  234.02
#Mann= 8 ,-1 , 0
  4545.6     .07       0  4635.1     .05       0  4972.4     .07       0
    5018     .05       0    5022     .07       0  5022.6     .12       0
  5120.9     .07       0  5374.2     .05       0
Bank Sta=5018,5022
XS Rating Curve= 0 ,0
Exp/Cntr=0.3,0.1

Type RM Length L Ch R = 1 ,11748   ,459,459,459
BEGIN DESCRIPTION:
Mapping XS 0c870e03
END DESCRIPTION:
XS GIS Cut Line= 3
      2503052.07     13477528.97      2502524.27     13477289.37
      2501938.71     13477337.88
#Sta/Elev= 30
  4421.3  222.84    4473  223.15  4527.9  224.04  4565.1  224.11  4593.8  223.56
  4634.4  223.51  4692.6  222.54  4737.7  222.21  4747.5  222.44  4760.8  222.03
    4811   221.7  4945.2  219.84  4956.4  219.29    4974  217.37  4987.2  217.06
  4987.4  216.56  4990.9  216.56  4991.2  217.06  5003.1   217.2  5006.9     218
  5011.9  217.86  5020.3  218.99  5036.8  220.14  5140.7  222.43  5309.5  225.52
  5408.6  227.81  5414.5  227.88  5507.2  230.26    5532  230.75  5588.5  232.66
#Mann= 9 ,-1 , 0
  4421.3     .07       0    4811    .035       0  4987.2    .035       0
  4991.2    .035       0  5036.8     .07       0  5309.5     .05       0
  5408.6     .07       0  5414.5     .12       0  5507.2     .07       0
Bank Sta=4987.2,4991.2
XS Rating Curve= 0 ,0
Exp/Cntr=0.3,0.1

Type RM Length L Ch R = 1 ,11289   ,254,254,254
BEGIN DESCRIPTION:
Mapping XS ee5fe3a3
END DESCRIPTION:
XS GIS Cut Line= 3
      2503263.85     13477053.26      2502683.99     13476876.18
      2502263.85     13477015.07
#Sta/Elev= 30
  4374.8  219.52  4433.6  218.63  4594.9  216.51  4614.1  215.51  4622.5  216.13
  4660.5  215.82  4698.5  216.54  4718.6  216.03  4726.1  216.39  4731.3  215.98
  4781.4  217.27  4854.6  216.55  4867.8     216  4885.9  216.23  4974.3  215.13
  5001.1  215.48    5019  214.46  5019.3  213.96  5022.8  213.96    5023  214.46
  5042.2  214.97  5052.7  215.59    5058  215.41  5074.8  216.61  5106.4  217.53
  5280.1  220.65    5296  221.44  5399.4  223.67    5407   223.7  5423.6  225.09
#Mann= 7 ,-1 , 0
  4374.8    .035       0  4433.6     .07       0  4974.3     .05       0
    5019     .05       0    5023     .05       0  5042.2     .07       0
  5399.4     .05       0
Bank Sta=5019,5023
XS Rating Curve= 0 ,0
Exp/Cntr=0.3,0.1

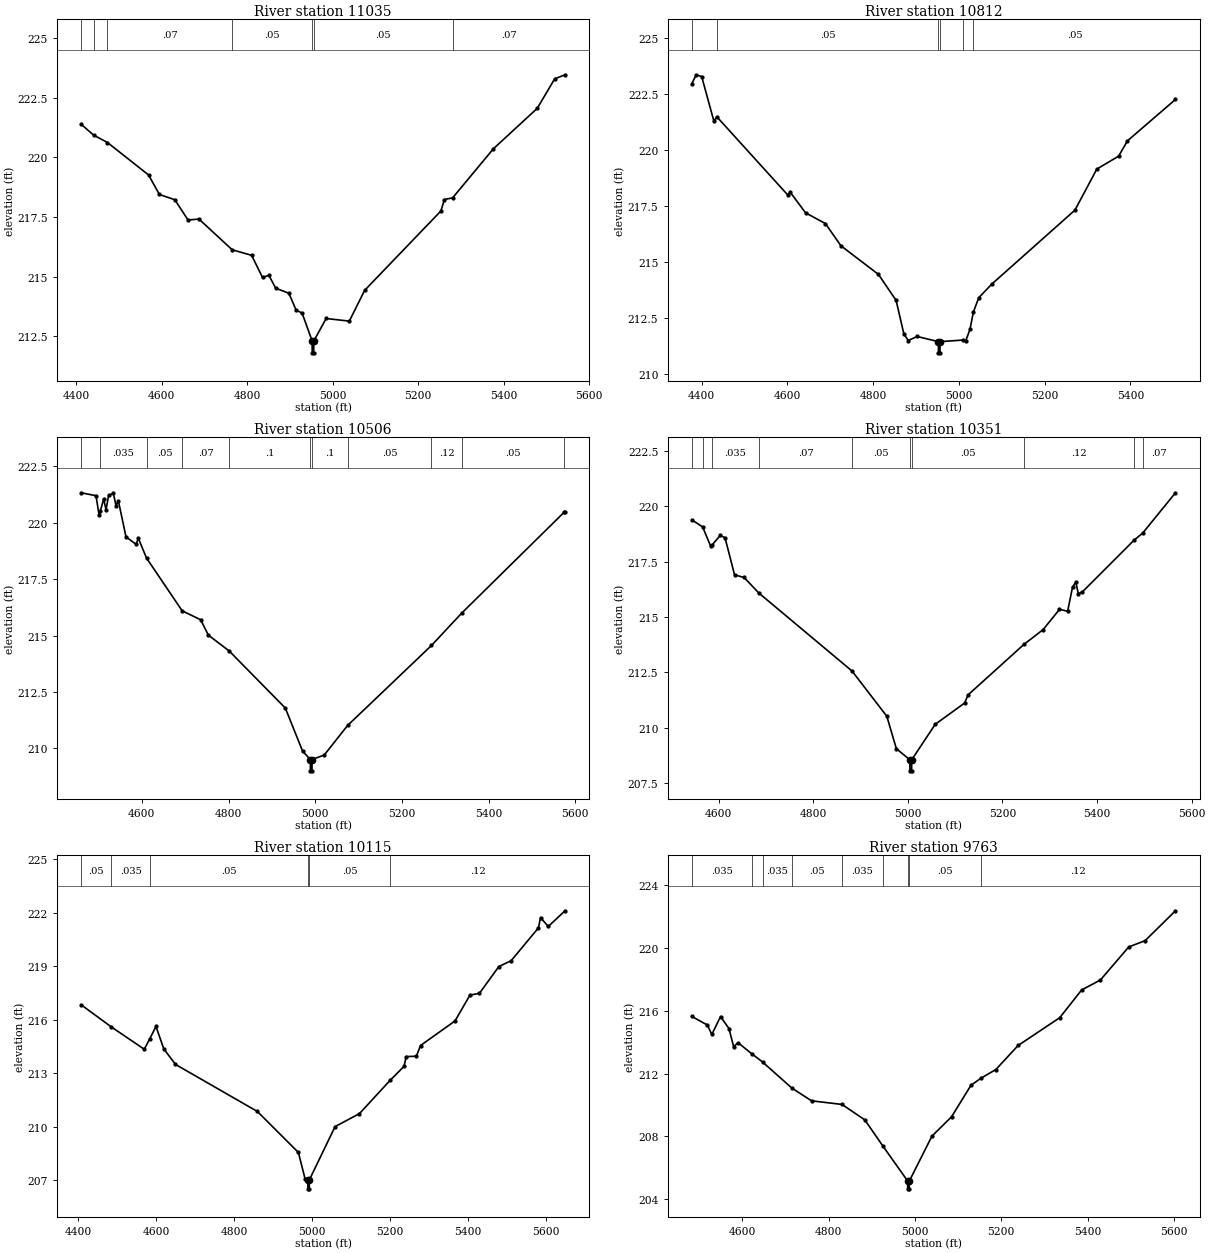
Type RM Length L Ch R = 1 ,11035   ,223,223,223
BEGIN DESCRIPTION:
Mapping XS 9727eeb2
END DESCRIPTION:
XS GIS Cut Line= 4
      2503338.16     13476862.76      2502793.01     13476668.31
      2502716.62     13476668.31      2502251.37       13476769.
#Sta/Elev= 30
  4412.3  221.38  4441.1  220.93  4473.5  220.62  4569.5  219.26    4595  218.44
  4631.1  218.22  4661.9  217.37  4687.4  217.41  4765.3  216.12  4810.6  215.89
  4836.1  214.96    4851  215.05  4866.9  214.51  4897.7   214.3  4914.7  213.59
  4928.6  213.47  4952.1   212.3  4952.3   211.8  4955.8   211.8  4956.1   212.3
  4984.9  213.24  5039.1  213.13  5074.9  214.42  5253.3  217.75  5261.5  218.23
  5280.7   218.3  5376.1  220.36  5478.4  222.05  5519.3  223.29  5543.5  223.46
#Mann= 7 ,-1 , 0
  4412.3    .035       0  4441.1     .05       0  4473.5     .07       0
  4765.3     .05       0  4952.1     .05       0  4956.1     .05       0
  5280.7     .07       0
Bank Sta=4952.1,4956.1
XS Rating Curve= 0 ,0
Exp/Cntr=0.3,0.1

Type RM Length L Ch R = 1 ,10812   ,306,306,306
BEGIN DESCRIPTION:
TRIB 3 TO PERDIDO CREEK 23.0
END DESCRIPTION:
XS GIS Cut Line= 3
      2503374.97     13476624.99        2502775.       13476475.
      2502275.04     13476574.99
#Sta/Elev= 30
  4376.7  222.93    4387  223.34  4399.9  223.26  4428.2  221.28  4435.5  221.46
  4600.9  217.97    4606  218.11  4642.1  217.18  4688.5   216.7  4724.6  215.71
  4812.2  214.43  4853.4  213.27  4871.4  211.78  4881.7  211.48  4902.4  211.66
  4951.9  211.43  4952.2  210.93  4955.7  210.93  4955.9  211.43  5009.6   211.5
  5015.5  211.45  5025.7  211.98  5033.6  212.75  5046.1  213.39  5076.7     214
  5270.5   217.3  5321.5  219.13  5372.5  219.71  5392.9  220.39    5505  222.24
#Mann= 6 ,-1 , 0
  4376.7    .035       0  4435.5     .05       0  4951.9     .05       0
  4955.9     .05       0  5009.6      .1       0  5033.6     .05       0
Bank Sta=4951.9,4955.9
XS Rating Curve= 0 ,0
Exp/Cntr=0.3,0.1

Type RM Length L Ch R = 1 ,10506   ,155,155,155
BEGIN DESCRIPTION:
Mapping XS 3ad2c5cf
END DESCRIPTION:
XS GIS Cut Line= 4
      2503362.44     13476463.44      2502928.43     13476265.53
      2502796.49       13476269.      2502303.41     13476387.06
#Sta/Elev= 30
  4460.3  221.32  4494.3  221.19  4501.4  220.32  4504.1  220.51  4511.9  221.04
  4517.4  220.57  4523.4  221.21  4534.4  221.29  4540.4  220.75  4545.9  220.96
  4563.4  219.37  4586.5  219.04    4592   219.3  4610.8  218.43  4693.2  216.09
  4735.7   215.7  4753.3  215.02  4801.3  214.32    4931  211.79  4970.7  209.89
  4988.7  209.51    4989  209.01  4992.5  209.01  4992.7  209.51  5020.8  209.71
  5074.8  211.02  5268.2  214.56  5338.3     216  5574.9  220.47  5576.3  220.47
#Mann= 11 ,-1 , 0
  4460.3     .05       0  4504.1    .035       0  4610.8     .05       0
  4693.2     .07       0  4801.3      .1       0  4988.7     .05       0
  4992.7      .1       0  5074.8     .05       0  5268.2     .12       0
  5338.3     .05       0  5574.9     .07       0
Bank Sta=4988.7,4992.7
XS Rating Curve= 0 ,0
Exp/Cntr=0.3,0.1

Type RM Length L Ch R = 1 ,10351   ,236,236,236
BEGIN DESCRIPTION:
TRIB 3 TO PERDIDO CREEK 22.0
END DESCRIPTION:
XS GIS Cut Line= 3
      2503274.99       13476175.        2502825.       13476125.
      2502275.04     13476274.99
#Sta/Elev= 30
    4543  219.38  4566.1  219.06  4583.2  218.18  4586.2  218.25  4603.4  218.68
  4613.4  218.57  4633.5   216.9  4653.7  216.78  4684.8  216.08    4882  212.56
  4955.5  210.52  4975.6  209.06  5004.1  208.56  5004.4  208.06  5007.9  208.06
  5008.1  208.56  5057.9  210.16  5120.1  211.12    5127  211.48  5245.3  213.76
    5286  214.43  5320.5  215.34  5337.8  215.26  5348.2  216.35  5355.1  216.57
  5360.3  216.05  5368.9  216.13  5478.1  218.46  5496.4  218.78  5565.8   220.6
#Mann= 10 ,-1 , 0
    4543    .035       0  4566.1     .05       0  4586.2    .035       0
  4684.8     .07       0    4882     .05       0  5004.1     .05       0
  5008.1     .05       0  5245.3     .12       0  5478.1     .05       0
  5496.4     .07       0
Bank Sta=5004.1,5008.1
XS Rating Curve= 0 ,0
Exp/Cntr=0.3,0.1

Type RM Length L Ch R = 1 ,10115   ,352,352,352
BEGIN DESCRIPTION:
Mapping XS 2ebe0aa3
END DESCRIPTION:
XS GIS Cut Line= 3
      2503316.59     13475910.31      2502787.03     13475901.63
       2502114.3     13476131.66
#Sta/Elev= 30
  4408.2  216.84  4485.4   215.6  4569.8  214.35  4583.6  214.93  4599.8  215.63
  4619.8  214.37  4649.8   213.5  4859.8  210.86    4965  208.56  4982.2  207.07
  4989.1  207.02  4989.3  206.52  4992.8  206.52  4993.1  207.02    5059  210.01
  5121.6  210.74  5201.2  212.63  5235.9  213.39  5241.5  213.94  5267.5  213.96
  5278.2  214.56  5366.7  215.94    5405  217.39  5429.4  217.49    5479  218.99
  5510.7  219.32  5580.6  221.16  5585.9  221.74  5605.8  221.24  5648.8  222.12
#Mann= 6 ,-1 , 0
  4408.2     .05       0  4485.4    .035       0  4583.6     .05       0
  4989.1     .05       0  4993.1     .05       0  5201.2     .12       0
Bank Sta=4989.1,4993.1
XS Rating Curve= 0 ,0
Exp/Cntr=0.3,0.1

Type RM Length L Ch R = 1 ,9763    ,395,395,395
BEGIN DESCRIPTION:
Mapping XS d0c56261
END DESCRIPTION:
XS GIS Cut Line= 3
      2503090.89     13475545.72      2502574.36     13475628.19
      2502049.61     13475914.42
#Sta/Elev= 30
    4483  215.64  4519.3  215.09  4529.5  214.49  4549.7  215.63  4569.2  214.87
  4580.1  213.71  4590.2  213.97  4622.6  213.25  4647.1  212.74    4715  211.08
  4760.6  210.27  4831.1  210.04  4883.9  209.06  4925.2  207.42  4983.2  205.17
  4983.4  204.67  4986.9  204.67  4987.2  205.17  5039.5  208.02  5085.1  209.26
    5130  211.26  5153.8  211.72  5187.6  212.26  5239.2  213.79  5335.7  215.56
  5386.3  217.32    5430  217.96  5495.5  220.06  5533.5  220.46  5603.8  222.36
#Mann= 9 ,-1 , 0
    4483    .035       0  4622.6     .05       0  4647.1    .035       0
    4715     .05       0  4831.1    .035       0  4925.2     .05       0
  4983.2     .05       0  4987.2     .05       0  5153.8     .12       0
Bank Sta=4983.2,4987.2
XS Rating Curve= 0 ,0
Exp/Cntr=0.3,0.1

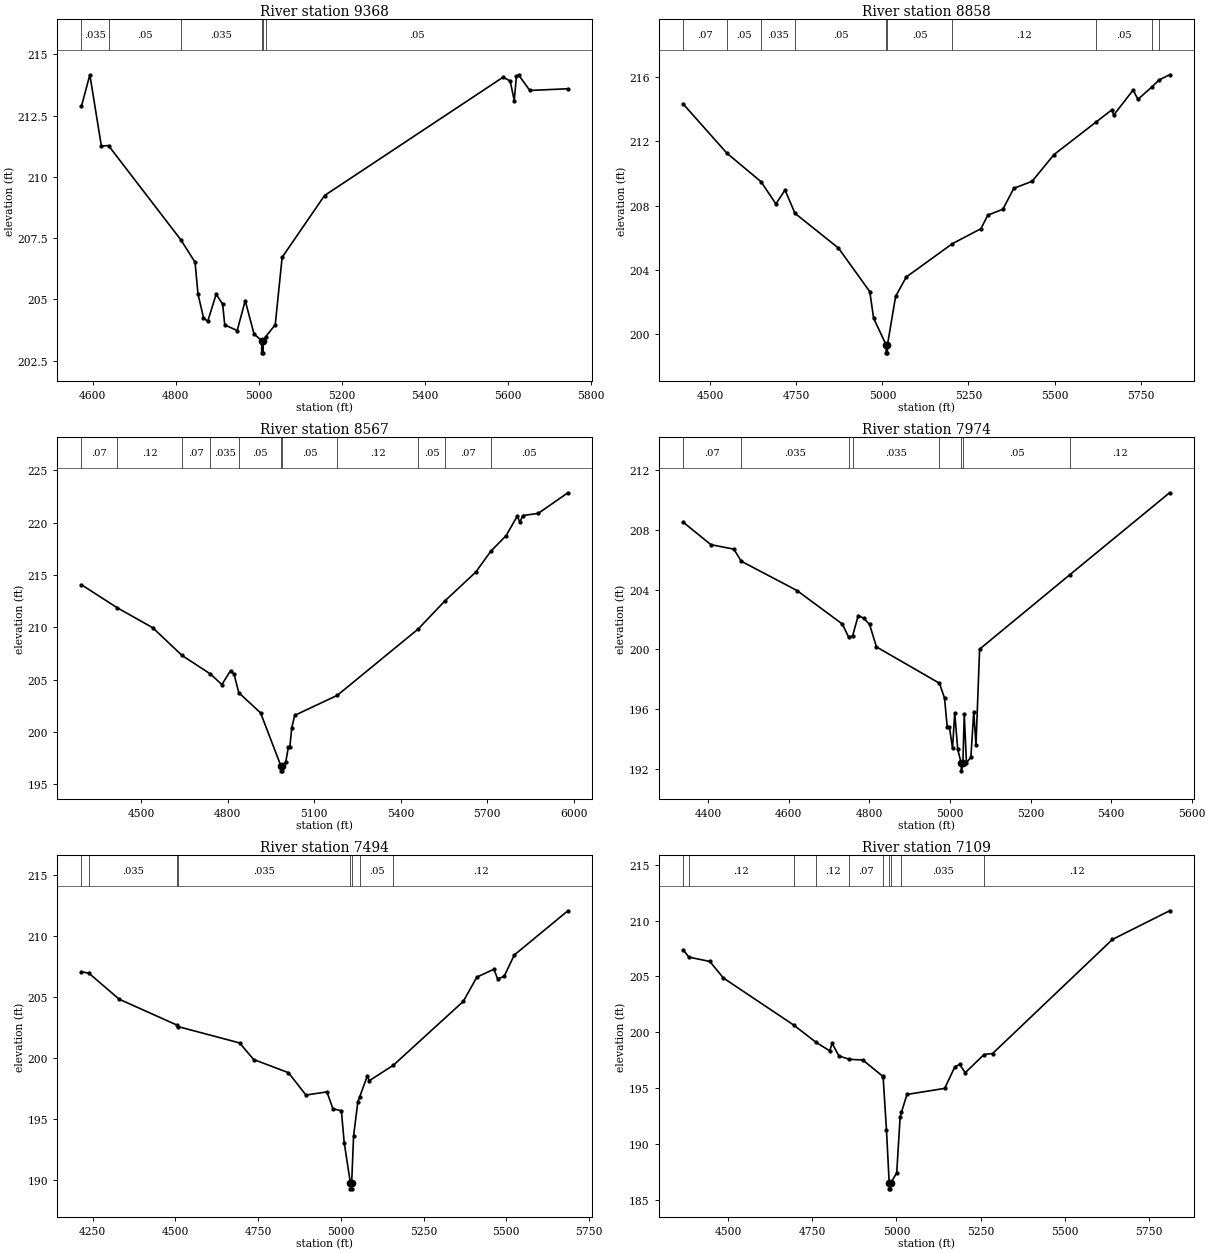
Type RM Length L Ch R = 1 ,9368    ,510,510,510
BEGIN DESCRIPTION:
Mapping XS 823609ee
END DESCRIPTION:
XS GIS Cut Line= 3
      2502964.95     13475328.71      2502517.93     13475250.59
      2501832.15     13475467.61
#Sta/Elev= 30
  4572.4  212.88  4592.7  214.17  4620.5  211.26  4637.7  211.28  4811.8  207.44
  4846.4  206.52  4853.4  205.23  4866.7  204.26  4876.9   204.1  4897.2  205.21
  4912.9  204.81    4918  203.96    4948  203.73  4967.4  204.95  4988.6  203.59
  5006.9  203.32  5007.1  202.82  5010.6  202.82  5010.9  203.32  5016.5  203.47
  5039.8  203.97  5056.4  206.72  5158.6  209.24  5589.1  214.07  5606.2  213.92
  5616.1  213.12  5621.4  214.12  5627.1  214.15  5653.7  213.53  5745.5   213.6
#Mann= 6 ,-1 , 0
  4572.4    .035       0  4637.7     .05       0  4811.8    .035       0
  5006.9    .035       0  5010.9    .035       0  5016.5     .05       0
Bank Sta=5006.9,5010.9
XS Rating Curve= 0 ,0
Exp/Cntr=0.3,0.1

Type RM Length L Ch R = 1 ,8858    ,291,291,291
BEGIN DESCRIPTION:
Mapping XS 758b06fc
END DESCRIPTION:
XS GIS Cut Line= 3
      2503099.52     13474929.41      2502548.32     13474868.64
      2501738.33     13475154.52
#Sta/Elev= 30
  4420.7  214.34  4548.4  211.26    4647   209.5  4690.5  208.11    4717  208.98
  4745.6  207.53  4872.3  205.36  4963.2  202.65  4974.4  200.99  5010.6  199.34
  5010.9  198.84  5014.4  198.84  5014.6  199.34  5038.2  202.35  5069.2  203.56
  5202.8  205.63  5286.3  206.57    5306  207.41  5349.9  207.78  5381.7  209.08
    5435  209.52  5498.4  211.18  5619.6  213.19  5666.6  213.97  5671.9  213.64
  5728.4   215.2  5742.3  214.62  5782.8  215.39  5803.3  215.82  5834.2  216.15
#Mann= 10 ,-1 , 0
  4420.7     .07       0  4548.4     .05       0    4647    .035       0
  4745.6     .05       0  5010.6     .05       0  5014.6     .05       0
  5202.8     .12       0  5619.6     .05       0  5782.8    .035       0
  5803.3     .07       0
Bank Sta=5010.6,5014.6
XS Rating Curve= 0 ,0
Exp/Cntr=0.3,0.1

Type RM Length L Ch R = 1 ,8567    ,593,593,593
BEGIN DESCRIPTION:
Mapping XS 463323f5
END DESCRIPTION:
XS GIS Cut Line= 3
      2503229.75     13474655.97      2502539.64     13474582.19
      2501584.77     13474859.96
#Sta/Elev= 30
  4291.9  214.06  4416.3  211.86  4539.6  209.95    4641  207.31  4739.5  205.54
  4779.4  204.53  4809.6  205.86  4821.5  205.53  4838.1  203.75  4913.8  201.82
  4983.8  196.79    4984  196.29  4987.5  196.29  4987.8  196.79  5001.2  197.13
  5010.2  198.57  5015.4   198.6    5022  200.42  5032.4  201.59    5180   203.5
  5460.7  209.83  5553.6  212.52  5660.4  215.26  5712.8  217.26  5765.7  218.74
  5804.9  220.62  5813.5  220.02  5823.9  220.67  5877.2  220.87  5980.4  222.84
#Mann= 11 ,-1 , 0
  4291.9     .07       0  4416.3     .12       0    4641     .07       0
  4739.5    .035       0  4838.1     .05       0  4983.8     .05       0
  4987.8     .05       0    5180     .12       0  5460.7     .05       0
  5553.6     .07       0  5712.8     .05       0
Bank Sta=4983.8,4987.8
XS Rating Curve= 0 ,0
Exp/Cntr=0.3,0.1

Type RM Length L Ch R = 1 ,7974    ,480,480,480
BEGIN DESCRIPTION:
Mapping XS b8731a45
END DESCRIPTION:
XS GIS Cut Line= 3
      2502978.18     13474362.12      2502387.94     13474073.94
      2501880.99     13474289.22
#Sta/Elev= 30
  4337.5  208.52  4406.5  207.01  4463.5  206.71  4482.1   205.9  4620.3  203.94
  4732.9   201.7  4748.2  200.84  4758.1  200.89  4772.4  202.27  4786.2  202.08
  4800.5  201.67  4817.5  200.17  4973.9  197.74  4986.5  196.75  4993.2  194.82
  4998.6  194.82  5006.4  193.38  5011.8  195.76  5019.3  193.31  5028.1  192.38
  5028.3  191.88  5032.1  192.38  5035.5  195.65    5041  192.41  5051.9  192.79
  5059.1  195.84  5064.6  193.58  5073.6  200.02  5298.1  205.01  5545.1  210.48
#Mann= 8 ,-1 , 0
  4337.5     .07       0  4482.1    .035       0  4748.2     .12       0
  4758.1    .035       0  4973.9     .05       0  5028.1     .05       0
  5032.1     .05       0  5298.1     .12       0
Bank Sta=5028.1,5032.1
XS Rating Curve= 0 ,0
Exp/Cntr=0.3,0.1

Type RM Length L Ch R = 1 ,7494    ,385,385,385
BEGIN DESCRIPTION:
Mapping XS 8efc7a4c
END DESCRIPTION:
XS GIS Cut Line= 3
      2503117.12     13473907.28      2502387.94     13473657.27
      2501707.38     13473820.47
#Sta/Elev= 30
  4215.7  207.08  4238.6  206.95  4329.8  204.83  4505.3   202.7  4508.8  202.58
  4693.7  201.25  4736.4  199.89  4841.7  198.81  4894.5  196.98  4957.9  197.24
    4976  195.86  5001.6  195.69  5010.1  193.09  5028.7   189.8    5029   189.3
  5032.5   189.3  5032.7   189.8  5038.5  193.63  5051.3  196.42  5056.8  196.83
  5080.5  198.57  5085.6  198.15  5158.6  199.42  5370.1  204.65  5411.2  206.64
  5462.6  207.28    5474   206.5  5493.5  206.69  5524.3  208.45  5686.4  212.07
#Mann= 8 ,-1 , 0
  4215.7     .12       0  4238.6    .035       0  4505.3     .07       0
  4508.8    .035       0  5028.7    .035       0  5032.7    .035       0
  5056.8     .05       0  5158.6     .12       0
Bank Sta=5028.7,5032.7
XS Rating Curve= 0 ,0
Exp/Cntr=0.3,0.1

Type RM Length L Ch R = 1 ,7109    ,412,412,412
BEGIN DESCRIPTION:
Mapping XS 8a9cc51f
END DESCRIPTION:
XS GIS Cut Line= 3
      2503113.66     13473400.33      2502495.58     13473313.52
       2501688.3     13473465.97
#Sta/Elev= 30
    4366   207.4    4383  206.73  4445.4  206.34  4485.8  204.86  4695.4  200.64
  4761.5   199.1  4801.8  198.35    4809  199.01  4829.2  197.89  4860.3  197.59
  4899.9  197.53  4959.2  196.08  4960.4  196.05  4970.5  191.25  4978.6  186.51
  4978.9  186.01  4982.4  186.01  4982.6  186.51  5000.9  187.44  5011.1  192.46
  5015.1  192.87  5031.4  194.45  5143.4  194.99  5173.9  196.93    5188  197.13
  5204.5  196.39  5260.4  198.02  5285.9  198.11  5642.1  208.31  5811.7  210.87
#Mann= 10 ,-1 , 0
    4366     .07       0    4383     .12       0  4695.4     .07       0
  4761.5     .12       0  4860.3     .07       0  4959.2      .1       0
  4978.6     .05       0  4982.6      .1       0  5015.1    .035       0
  5260.4     .12       0
Bank Sta=4978.6,4982.6
XS Rating Curve= 0 ,0
Exp/Cntr=0.3,0.1

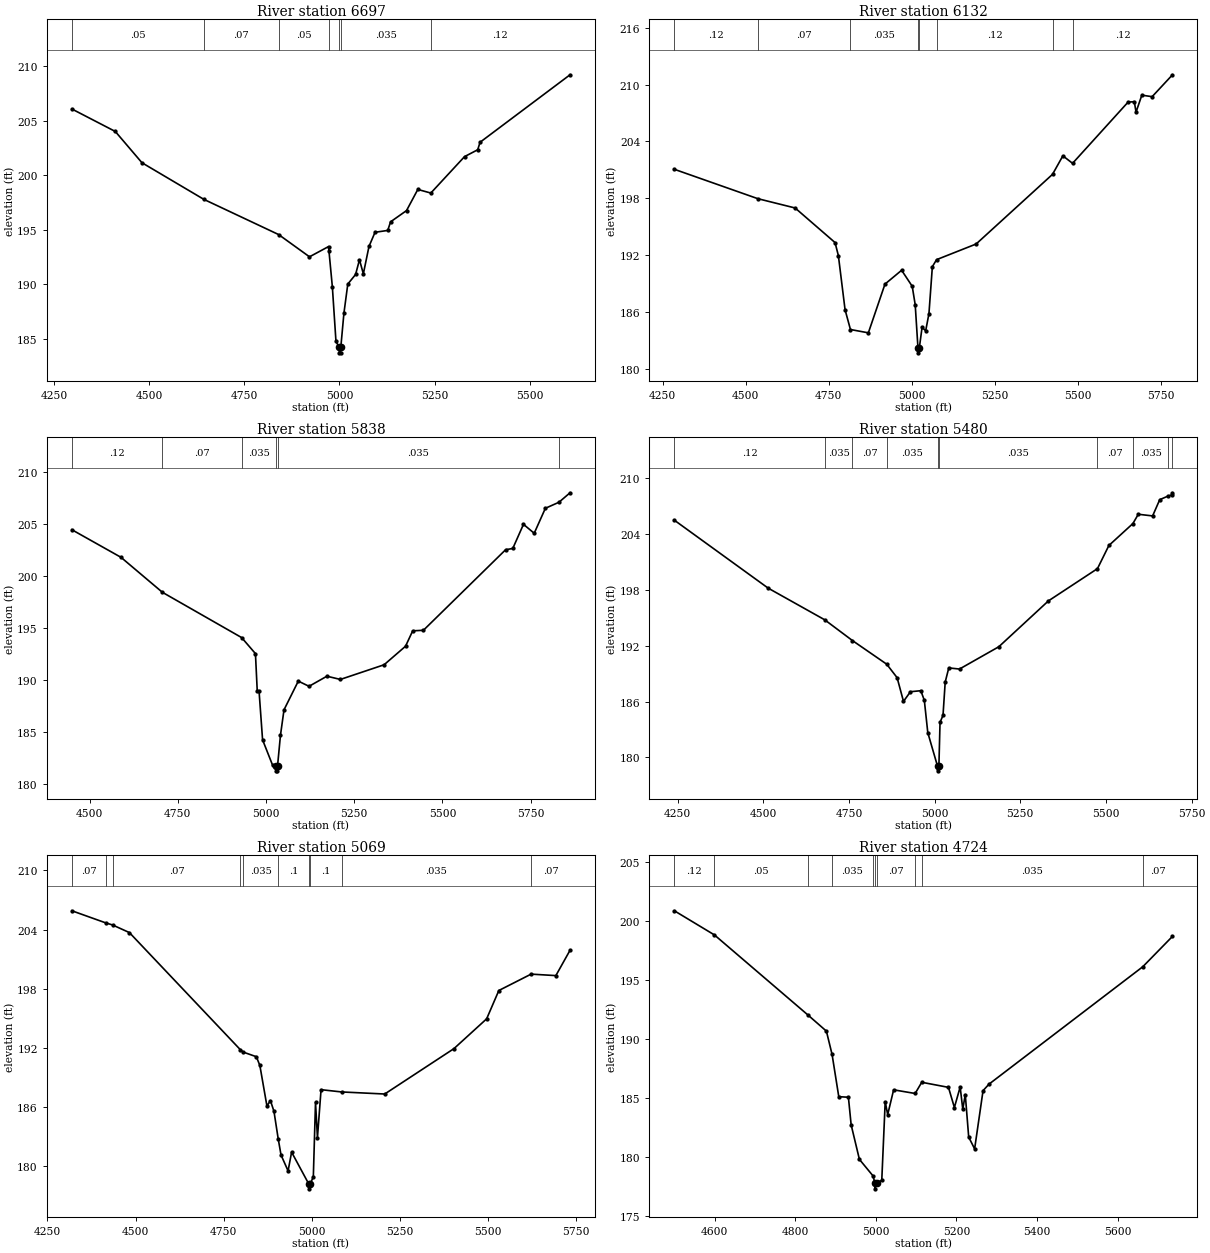
Type RM Length L Ch R = 1 ,6697    ,565,565,565
BEGIN DESCRIPTION:
Mapping XS 270e64e3
END DESCRIPTION:
XS GIS Cut Line= 3
      2503078.96     13472997.55        2502381.     13472962.83
      2501783.78      13473091.3
#Sta/Elev= 30
  4296.6  206.06  4410.7     204  4480.8  201.13  4643.6  197.77  4840.2  194.54
  4921.3   192.5  4971.4  193.44  4972.5  193.03  4981.4  189.75  4990.9  184.74
  4999.6  184.19  4999.8  183.69  5003.3  183.69  5003.6  184.19  5011.8  187.32
    5022     190  5042.5  190.88  5052.7  192.23  5062.9  190.94  5077.7  193.45
  5093.6  194.75    5127  194.92  5134.5  195.71  5176.4  196.74  5206.1  198.68
  5240.3  198.35  5328.9  201.69  5363.5  202.32  5369.8  203.01  5606.3   209.2
#Mann= 7 ,-1 , 0
  4296.6     .05       0  4643.6     .07       0  4840.2     .05       0
  4972.5    .035       0  4999.6    .035       0  5003.6    .035       0
  5240.3     .12       0
Bank Sta=4999.6,5003.6
XS Rating Curve= 0 ,0
Exp/Cntr=0.3,0.1

Type RM Length L Ch R = 1 ,6132    ,294,294,294
BEGIN DESCRIPTION:
Mapping XS c58fb462
END DESCRIPTION:
XS GIS Cut Line= 3
      2503137.89     13472514.91      2502440.03     13472476.72
       2501665.7     13472678.11
#Sta/Elev= 30
  4285.3  201.06  4536.6  197.96  4648.7  196.98  4768.9  193.33  4778.9  191.95
    4799  186.25  4815.2  184.16  4869.1  183.81  4919.1  188.95  4969.2  190.41
  5001.1  188.72  5010.1  186.77  5018.4   182.2  5018.7   181.7  5022.4   182.2
  5030.7  184.38  5041.6  184.03  5051.4  185.83  5061.7  190.79  5074.4  191.53
  5193.4  193.18  5423.3  200.53  5454.4  202.48  5483.6  201.69  5650.7  208.15
  5669.4  208.19  5674.6  207.09    5692  208.88    5723  208.72  5784.3  211.03
#Mann= 8 ,-1 , 0
  4285.3     .12       0  4536.6     .07       0  4815.2    .035       0
  5018.4    .035       0  5022.4    .035       0  5074.4     .12       0
  5423.3    .035       0  5483.6     .12       0
Bank Sta=5018.4,5022.4
XS Rating Curve= 0 ,0
Exp/Cntr=0.3,0.1

Type RM Length L Ch R = 1 ,5838    ,358,358,358
BEGIN DESCRIPTION:
Mapping XS 64169331
END DESCRIPTION:
XS GIS Cut Line= 3
      2503124.08     13472261.44      2502599.75     13472292.69
      2501724.77     13472431.58
#Sta/Elev= 30
  4450.1  204.45  4589.2   201.8  4706.5  198.44    4931  194.09  4970.1  192.55
  4975.2  188.96  4980.3  188.96  4990.3  184.27  5018.8  181.82  5028.8  181.79
    5029  181.29  5032.5  181.29  5032.8  181.79  5040.9  184.69    5051  187.15
  5091.5  189.91  5121.9  189.41  5172.6  190.38  5210.7  190.07  5334.6  191.48
  5395.3  193.26  5415.6  194.74  5445.9  194.79  5678.8  202.53  5699.1  202.65
  5729.4  204.97  5759.8  204.11  5791.4  206.51  5829.9  207.09  5861.3     208
#Mann= 6 ,-1 , 0
  4450.1     .12       0  4706.5     .07       0    4931    .035       0
  5028.8    .035       0  5032.8    .035       0  5829.9     .12       0
Bank Sta=5028.8,5032.8
XS Rating Curve= 0 ,0
Exp/Cntr=0.3,0.1

Type RM Length L Ch R = 1 ,5480    ,411,411,411
BEGIN DESCRIPTION:
Mapping XS b3e42538
END DESCRIPTION:
XS GIS Cut Line= 3
      2503075.45     13471969.77      2502301.14      13472091.3
      2501659.38     13472282.09
#Sta/Elev= 30
  4240.8  205.51  4514.6   198.2  4679.3   194.8  4760.5  192.56  4860.4  190.02
  4890.7  188.57  4909.3  186.02  4929.6  187.06  4959.9  187.17  4970.1  186.13
  4980.2  182.66  5008.6  179.05  5008.8  178.55  5012.6  179.05  5015.9  183.76
  5024.6  184.52    5031   188.1  5041.4  189.62  5072.7   189.5  5187.5   191.9
  5332.1  196.83  5475.2   200.3  5508.5  202.79  5578.6  205.15  5594.3  206.15
  5636.1  205.97  5656.9  207.72    5682  208.12  5691.6  208.22  5694.1  208.46
#Mann= 10 ,-1 , 0
  4240.8     .12       0  4679.3    .035       0  4760.5     .07       0
  4860.4    .035       0  5008.6    .035       0  5012.6    .035       0
  5475.2     .07       0  5578.6    .035       0    5682     .07       0
  5691.6     .12       0
Bank Sta=5008.6,5012.6
XS Rating Curve= 0 ,0
Exp/Cntr=0.3,0.1

Type RM Length L Ch R = 1 ,5069    ,345,345,345
BEGIN DESCRIPTION:
Mapping XS 6d081b5a
END DESCRIPTION:
XS GIS Cut Line= 3
       2503058.1     13471719.77      2502391.41     13471719.77
      2501710.85     13472025.33
#Sta/Elev= 30
  4319.4  205.91  4414.9  204.69  4434.9  204.47  4482.5   203.7  4796.9  191.84
  4805.1  191.59  4842.5  191.12  4852.5  190.23  4872.5  186.13  4882.5  186.67
  4892.5  185.58  4904.4  182.82  4912.5  181.16  4932.5  179.55  4942.5  181.45
  4991.1  178.23  4991.4  177.73  4995.2  178.23  5004.1  178.94  5010.3   186.5
  5015.8  182.93    5026  187.78  5084.1  187.55  5206.6  187.34  5402.9  191.94
  5495.6  194.96  5530.2  197.83  5621.7  199.49  5691.9  199.34  5732.1  201.91
#Mann= 10 ,-1 , 0
  4319.4     .07       0  4414.9     .12       0  4434.9     .07       0
  4796.9     .12       0  4805.1    .035       0  4904.4      .1       0
  4991.1     .05       0  4995.2      .1       0  5084.1    .035       0
  5621.7     .07       0
Bank Sta=4991.1,4995.2
XS Rating Curve= 0 ,0
Exp/Cntr=0.3,0.1

Type RM Length L Ch R = 1 ,4724    ,259,259,259
BEGIN DESCRIPTION:
Mapping XS 4d3ba68c
END DESCRIPTION:
XS GIS Cut Line= 3
      2502863.63     13471348.25      2502370.58     13471455.88
      2501778.45     13471885.27
#Sta/Elev= 30
    4500  200.86  4599.5  198.81  4830.4  192.05  4877.3  190.65  4891.4  188.67
    4908  185.09  4931.9  185.04  4938.7   182.7  4959.2  179.77  4992.7  178.38
  4997.8  177.77    4998  177.27  5001.9  177.77  5014.7  177.99  5023.2  184.66
  5029.4  183.57  5044.1  185.67  5097.5  185.36  5113.9  186.31  5180.2  185.88
  5194.9  184.17  5209.2  185.91  5215.7  184.03  5221.9  185.27  5230.4  181.66
  5245.1  180.66    5266   185.6  5280.7  186.15  5662.3  196.11  5736.1  198.69
#Mann= 10 ,-1 , 0
    4500     .12       0  4599.5     .05       0  4830.4     .07       0
  4891.4    .035       0  4992.7     .07       0  4997.8     .05       0
  5001.9     .07       0  5097.5      .1       0  5113.9    .035       0
  5662.3     .07       0
Bank Sta=4997.8,5001.9
XS Rating Curve= 0 ,0
Exp/Cntr=0.3,0.1

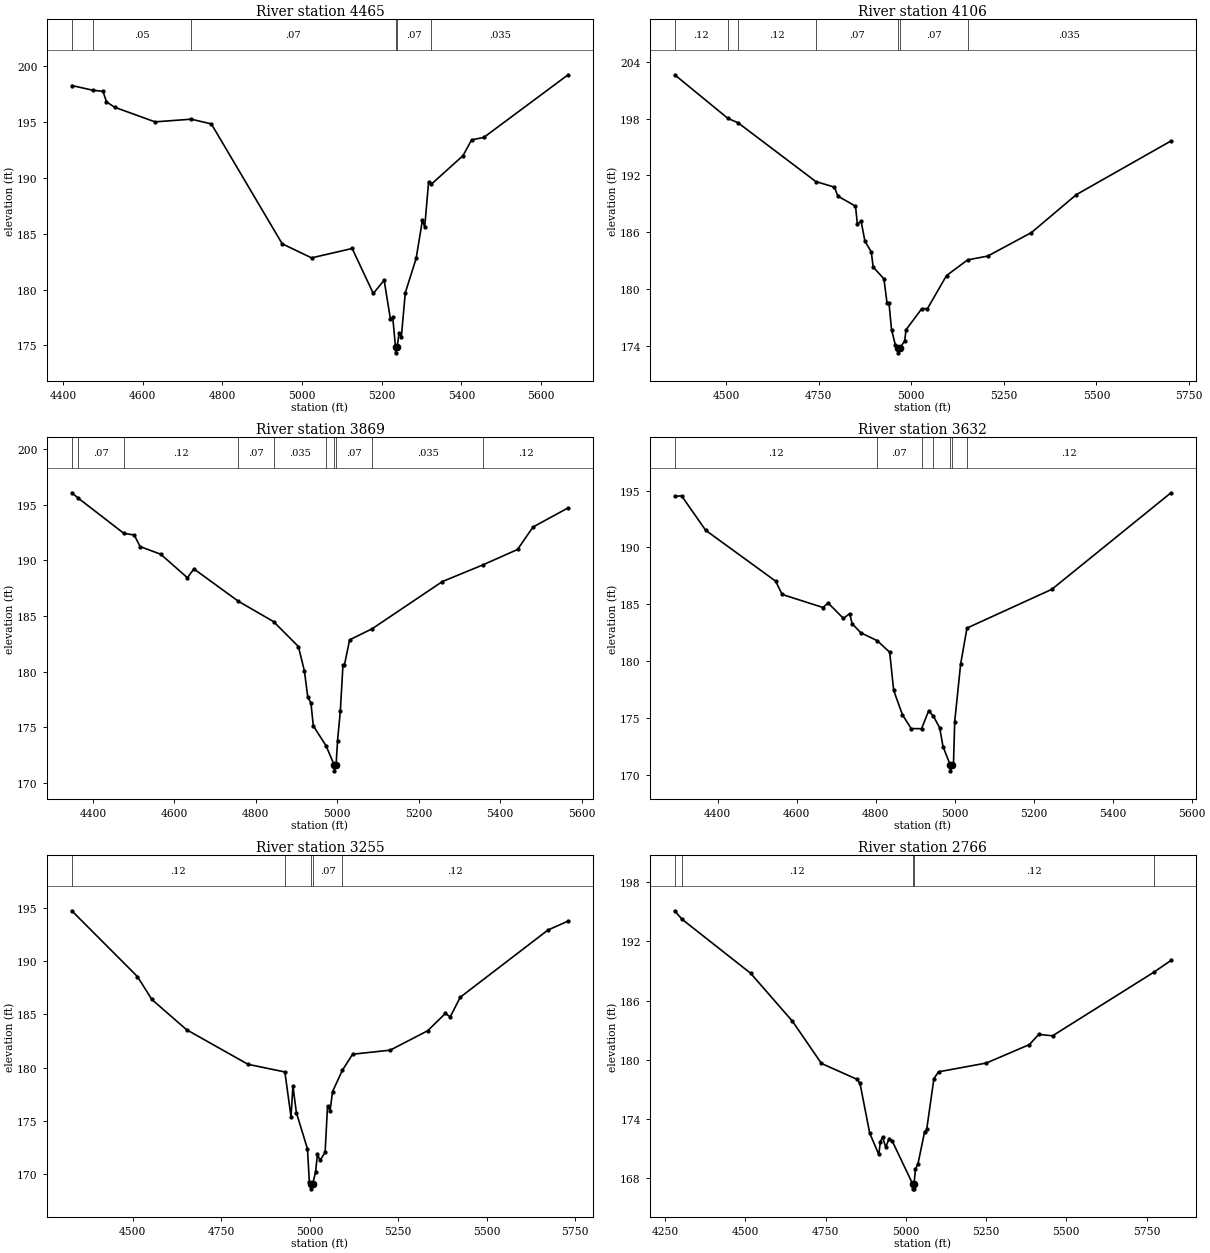
Type RM Length L Ch R = 1 ,4465    ,359,359,359
BEGIN DESCRIPTION:
Mapping XS 65c3b037
END DESCRIPTION:
XS GIS Cut Line= 3
      2502801.09     13471188.53      2502229.99     13471277.55
       2501651.9     13471612.27
#Sta/Elev= 30
    4422  198.24  4474.6  197.82  4500.3  197.72  4509.1  196.78  4529.4   196.3
    4631  194.99  4721.6  195.23  4772.3  194.81  4950.2  184.09    5024  182.83
  5125.9  183.67  5178.9  179.65  5206.2  180.83    5222  177.34  5227.8  177.51
  5234.8  174.84  5235.1  174.34  5238.9  174.84  5243.5  176.09  5249.3  175.75
  5259.3  179.71  5286.6  182.79  5302.3   186.2  5308.1   185.6  5317.8  189.61
  5324.8  189.42  5404.2  191.97  5425.8  193.38  5456.4   193.6    5668   199.2
#Mann= 6 ,-1 , 0
    4422     .12       0  4474.6     .05       0  4721.6     .07       0
  5234.8     .05       0  5238.9     .07       0  5324.8    .035       0
Bank Sta=5234.8,5238.9
XS Rating Curve= 0 ,0
Exp/Cntr=0.3,0.1

Type RM Length L Ch R = 1 ,4106    ,237,237,237
BEGIN DESCRIPTION:
Mapping XS 01719d5e
END DESCRIPTION:
XS GIS Cut Line= 3
      2502894.85     13470789.23      2502283.78     13470931.58
      2501649.16     13471254.09
#Sta/Elev= 30
  4361.8  202.63  4505.5  198.02  4532.4  197.57  4742.7  191.35  4792.9  190.76
    4802  189.82  4849.7  188.75  4854.8  186.85  4864.8  187.18    4875  185.07
  4892.3  183.92  4897.4  182.32  4926.4  181.08  4934.9  178.49    4940  178.56
  4946.9  175.71  4957.2  174.11  4965.3  173.76  4965.6  173.26  4969.6  173.76
  4982.6  174.54    4986  175.69  5028.5  177.92  5043.9  177.93  5095.3  181.42
  5152.4  183.08  5206.5  183.48  5324.4  185.96  5445.7  189.97  5701.1  195.64
#Mann= 7 ,-1 , 0
  4361.8     .12       0  4505.5     .07       0  4532.4     .12       0
  4742.7     .07       0  4965.3     .05       0  4969.6     .07       0
  5152.4    .035       0
Bank Sta=4965.3,4969.6
XS Rating Curve= 0 ,0
Exp/Cntr=0.3,0.1

Type RM Length L Ch R = 1 ,3869    ,237,237,237
BEGIN DESCRIPTION:
Mapping XS bcac69bc
END DESCRIPTION:
XS GIS Cut Line= 3
       2502651.8     13470504.51       2502068.5     13470827.41
      2501583.55     13471090.67
#Sta/Elev= 30
  4348.3  196.08  4364.1   195.6  4476.1  192.43  4501.6  192.28  4516.1  191.24
  4566.8  190.55  4632.1  188.44  4648.1  189.23  4757.4  186.32  4843.8  184.49
  4904.7  182.25  4919.5  180.04  4927.6  177.72  4935.5  177.17  4941.2  175.12
  4972.5  173.33  4992.9  171.57  4993.2  171.07  4997.2  171.57  5000.8  173.79
  5007.6  176.45  5014.1  180.59  5017.7  180.59  5030.4  182.85  5086.3  183.86
  5257.9  188.09  5357.4  189.59  5442.7  190.98  5480.7     193  5566.8  194.72
#Mann= 10 ,-1 , 0
  4348.3     .12       0  4364.1     .07       0  4476.1     .12       0
  4757.4     .07       0  4843.8    .035       0  4972.5     .07       0
  4992.9     .05       0  4997.2     .07       0  5086.3    .035       0
  5357.4     .12       0
Bank Sta=4992.9,4997.2
XS Rating Curve= 0 ,0
Exp/Cntr=0.3,0.1

Type RM Length L Ch R = 1 ,3632    ,377,377,377
BEGIN DESCRIPTION:
Mapping XS fbc7eec4
END DESCRIPTION:
XS GIS Cut Line= 3
      2502568.51     13470313.52       2501943.5     13470636.44
      2501485.15     13470945.47
#Sta/Elev= 30
  4291.4   194.5  4308.9  194.54  4369.7  191.51  4546.9  187.03  4563.4  185.86
  4666.8  184.71  4679.8  185.11  4718.4  183.75  4734.3  184.17  4740.6  183.28
  4762.7  182.48  4804.1  181.79  4835.6  180.77  4845.7  177.41  4867.9  175.27
    4890  174.05  4916.4  174.04  4934.3  175.62  4946.2  175.15  4962.1  174.12
  4970.7  172.46  4989.1  170.83  4989.4  170.33  4993.4  170.83    4997  170.83
  5000.2  174.66  5015.2  179.73  5031.3   182.9    5246  186.31  5547.7  194.81
#Mann= 7 ,-1 , 0
  4291.4     .12       0  4804.1     .07       0  4916.4     .12       0
  4946.2     .07       0  4989.1     .05       0  4993.4     .07       0
  5031.3     .12       0
Bank Sta=4989.1,4993.4
XS Rating Curve= 0 ,0
Exp/Cntr=0.3,0.1

Type RM Length L Ch R = 1 ,3255    ,489,489,489
BEGIN DESCRIPTION:
Mapping XS 75093375
END DESCRIPTION:
XS GIS Cut Line= 3
      2502544.19     13470056.58      2501915.72     13470337.83
      2501389.21     13470819.31
#Sta/Elev= 30
  4328.4  194.76  4513.8  188.57  4554.6  186.41  4652.9  183.56  4826.2  180.31
  4930.3  179.59  4947.7  175.37  4953.1  178.27  4962.9  175.75  4994.1  172.36
  4999.5  169.28  5004.6  169.09  5004.9  168.59    5009  169.09  5016.9  170.13
  5022.4  171.85  5029.8  171.27    5044  172.03  5050.8  176.34  5058.2  175.96
    5065  177.74  5092.8  179.75  5121.7  181.26  5227.8  181.64  5333.8  183.47
  5383.8   185.1  5397.4  184.77  5425.7  186.62  5673.6  192.95  5730.4  193.79
#Mann= 5 ,-1 , 0
  4328.4     .12       0  4930.3     .07       0  5004.6     .05       0
    5009     .07       0  5092.8     .12       0
Bank Sta=5004.6,5009
XS Rating Curve= 0 ,0
Exp/Cntr=0.3,0.1

Type RM Length L Ch R = 1 ,2766    ,373,373,373
BEGIN DESCRIPTION:
Mapping XS 7e573e4c
END DESCRIPTION:
XS GIS Cut Line= 3
      2502551.18     13469876.02      2501846.28     13469924.63
      2501189.99     13470448.97
#Sta/Elev= 30
  4279.5   195.1    4302  194.25  4516.2  188.77  4646.5  183.91  4736.8  179.64
    4847  178.04    4857  177.61  4887.1  172.59  4915.5  170.42  4920.5  171.72
  4927.2  172.18  4937.2  171.16  4947.3     172  4957.3  171.79    5021  167.44
  5021.3  166.94  5025.1  166.94  5025.4  167.44  5029.6  168.93  5037.6  169.47
  5058.4  172.74  5064.8  172.95  5087.3  178.11  5101.7  178.79  5250.6  179.68
    5385  181.55  5413.9  182.58  5457.1  182.44  5772.2  188.87  5826.1  190.07
#Mann= 5 ,-1 , 0
  4279.5     .07       0    4302     .12       0    5021     .05       0
  5025.4     .12       0  5772.2     .05       0
Bank Sta=5021,5025.4
XS Rating Curve= 0 ,0
Exp/Cntr=0.3,0.1