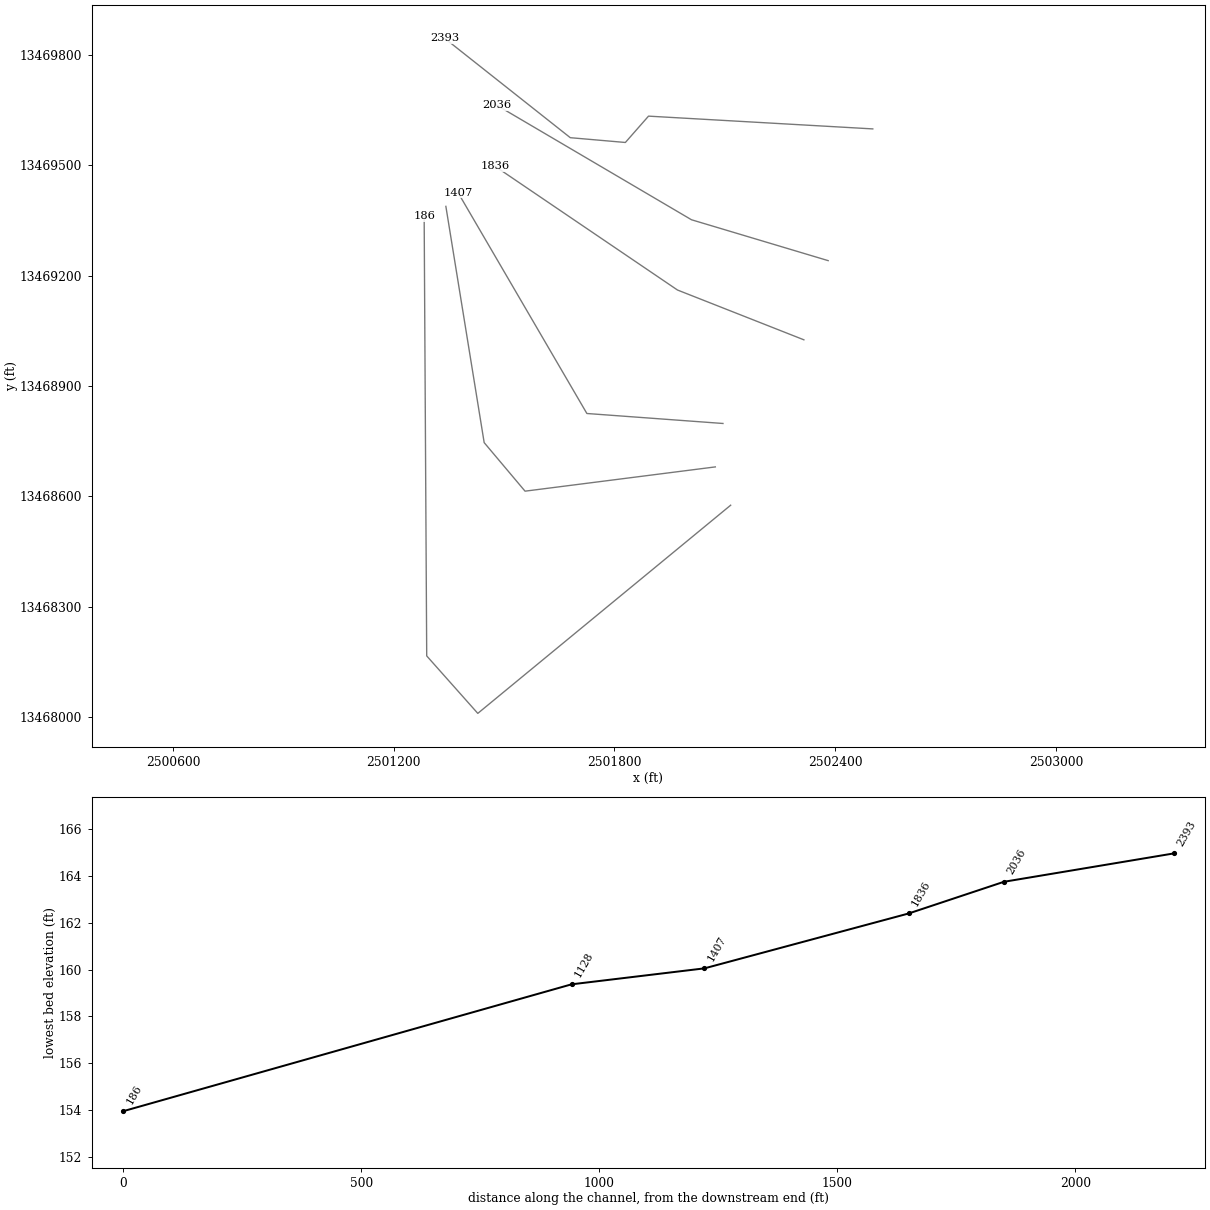
HEC-RAS study TRIB 3 TO PERDIDO CREEK.prj: TRIB 3 TO PERDIDO CREEK Base Level Engineering

--- TRIB 3 TO PERDIDO CREEK.g01 (geometry) --- (continued)

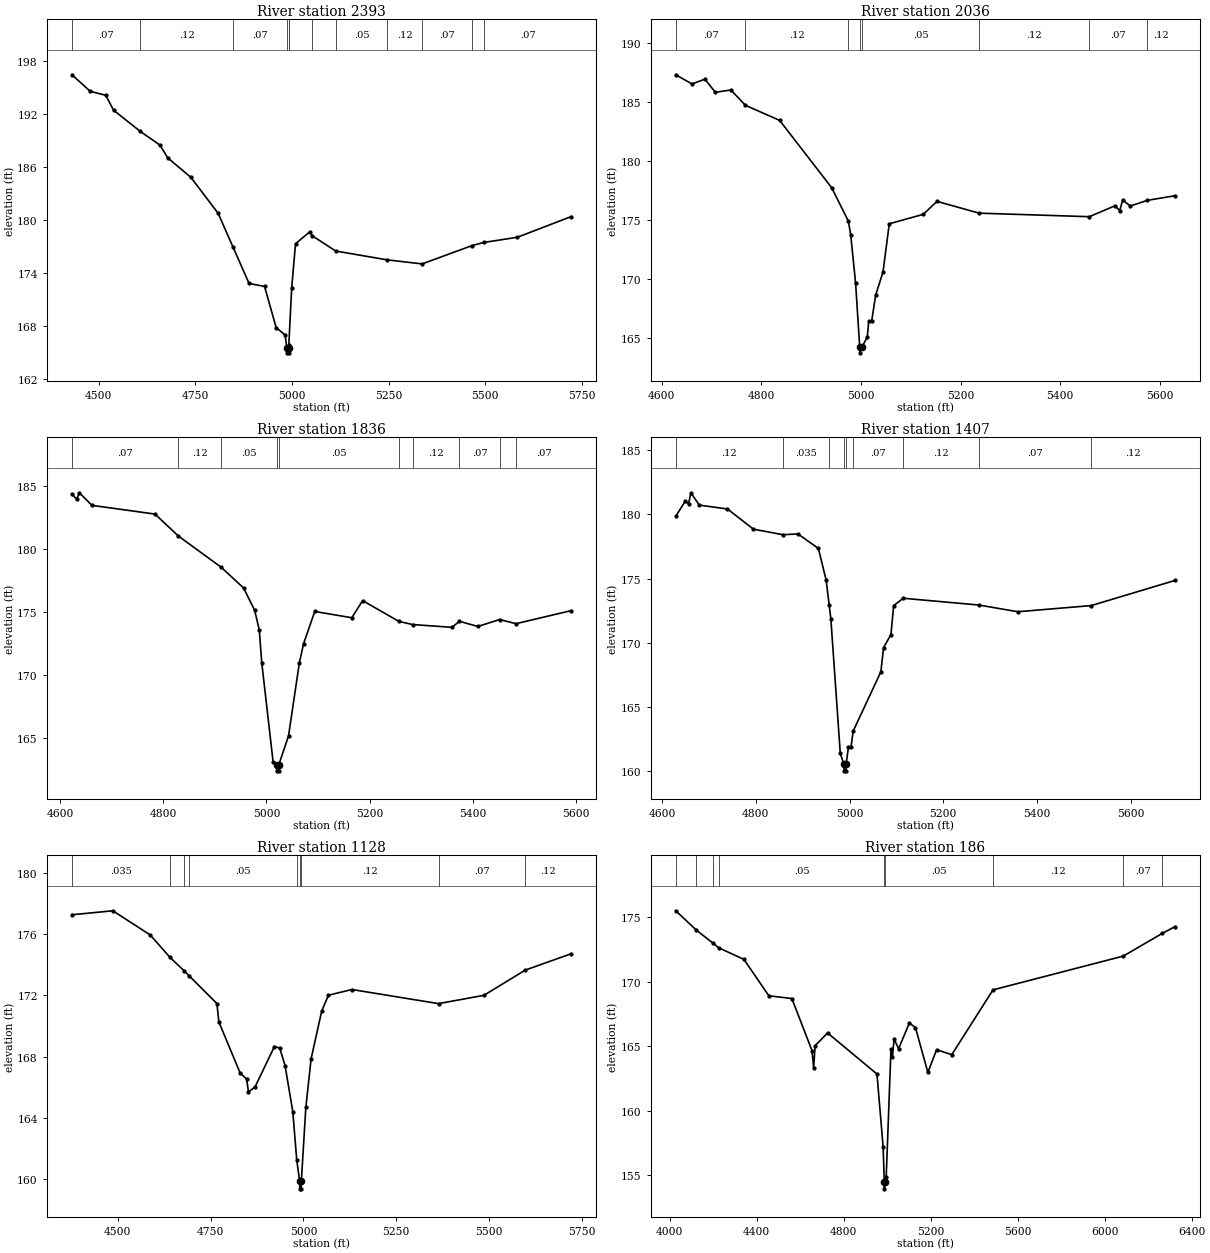
Type RM Length L Ch R = 1 ,2393    ,357,357,357
BEGIN DESCRIPTION:
Mapping XS bd8341ea
END DESCRIPTION:
XS GIS Cut Line= 5
      2502502.39     13469598.76      2501892.58     13469633.48
      2501829.65     13469561.87      2501679.91     13469574.89
      2501338.48     13469845.01
#Sta/Elev= 30
  4430.8  196.44  4478.3  194.56  4518.3  194.12  4538.4  192.43  4607.2  190.04
  4658.6  188.47  4678.6  187.03  4738.7  184.81  4809.1  180.74  4846.8  176.99
  4888.9  172.81    4929  172.47    4959  167.81  4982.2  166.97  4986.8  165.45
  4987.2  164.95    4991  164.95  4991.3  165.45  4991.8  165.89  4999.1  172.24
  5009.1  177.31  5045.9  178.65  5052.9  178.19    5113  176.48  5246.4  175.48
  5336.5  175.02    5466   177.1  5496.1  177.45    5583  178.04  5722.6  180.39
#Mann= 12 ,-1 , 0
  4430.8     .07       0  4607.2     .12       0  4846.8     .07       0
  4986.8     .05       0  4991.3     .07       0  4991.8     .05       0
  5052.9     .07       0    5113     .05       0  5246.4     .12       0
  5336.5     .07       0    5466     .12       0  5496.1     .07       0
Bank Sta=4986.8,4991.3
XS Rating Curve= 0 ,0
Exp/Cntr=0.3,0.1

Type RM Length L Ch R = 1 ,2036    ,200,200,200
BEGIN DESCRIPTION:
Mapping XS 7657a786
END DESCRIPTION:
XS GIS Cut Line= 3
      2502381.04     13469240.59      2502009.47     13469351.72
      2501479.14     13469663.67
#Sta/Elev= 30
  4628.1  187.33  4660.7  186.55  4686.6  186.96  4707.5  185.84  4738.8  186.04
  4767.9  184.74  4836.7  183.46  4941.2  177.75  4974.8  174.91  4979.5  173.73
  4989.3  169.63  4997.5  164.24  4997.8  163.74    5002  164.24  5012.7  165.07
  5015.6   166.4  5021.4   166.4  5029.6  168.64  5044.3   170.6  5056.9  174.69
  5125.3  175.49  5152.6  176.59  5237.4  175.59  5458.7  175.29  5509.9  176.21
  5519.8  175.81  5525.6  176.69  5541.2   176.2  5575.5  176.68  5631.2  177.07
#Mann= 8 ,-1 , 0
  4628.1     .07       0  4767.9     .12       0  4974.8     .05       0
  4997.5     .05       0    5002     .05       0  5237.4     .12       0
  5458.7     .07       0  5575.5     .12       0
Bank Sta=4997.5,5002
XS Rating Curve= 0 ,0
Exp/Cntr=0.3,0.1

Type RM Length L Ch R = 1 ,1836    ,429,429,429
BEGIN DESCRIPTION:
Mapping XS 8c1e799f
END DESCRIPTION:
XS GIS Cut Line= 3
      2502315.02     13469025.33      2501971.28     13469160.74
      2501474.78     13469497.53
#Sta/Elev= 30
  4622.4  184.37  4631.5  183.94  4636.8  184.46  4661.2  183.46  4783.6  182.77
  4828.6  181.04  4912.4  178.54  4955.6   176.9  4977.1  175.13  4986.1  173.56
  4990.8  170.98  5012.9  163.09  5019.6  162.89  5019.9  162.39  5023.8  162.39
  5024.1  162.89  5042.8  165.16  5063.8  170.96  5071.9  172.47  5093.7  175.04
  5165.6  174.54  5186.6   175.9  5257.2  174.25    5284     174  5360.3  173.78
  5374.4  174.26  5410.3  173.85  5452.6   174.4  5484.3  174.07  5591.8  175.11
#Mann= 10 ,-1 , 0
  4622.4     .07       0  4828.6     .12       0  4912.4     .05       0
  5019.6     .05       0  5024.1     .05       0  5257.2     .07       0
    5284     .12       0  5374.4     .07       0  5452.6     .12       0
  5484.3     .07       0
Bank Sta=5019.6,5024.1
XS Rating Curve= 0 ,0
Exp/Cntr=0.3,0.1

Type RM Length L Ch R = 1 ,1407    ,279,279,279
BEGIN DESCRIPTION:
TRIB 3 TO PERDIDO CREEK 2.0
END DESCRIPTION:
XS GIS Cut Line= 3
      2502095.04     13468797.85        2501725.       13468825.
      2501374.98     13469425.04
#Sta/Elev= 30
  4629.3  179.85  4649.4  181.01  4656.5  180.82  4661.5  181.67  4679.5  180.71
  4739.6  180.41    4795  178.84  4857.9  178.41    4890  178.47  4933.6  177.34
  4950.2  174.87  4956.6  172.94  4960.2  171.86  4980.3  161.41  4988.1  160.55
  4988.4  160.05  4992.3  160.05  4992.6  160.55  4997.8   161.9  5003.2   161.9
  5007.8  163.14  5066.9  167.75  5072.7  169.63  5088.4  170.65  5094.2  172.89
  5114.6  173.47  5276.5  172.94  5359.2  172.42  5515.9   172.9    5695  174.86
#Mann= 9 ,-1 , 0
  4629.3     .12       0  4857.9    .035       0  4956.6     .05       0
  4988.1     .05       0  4992.6     .05       0  5007.8     .07       0
  5114.6     .12       0  5276.5     .07       0  5515.9     .12       0
Bank Sta=4988.1,4992.6
XS Rating Curve= 0 ,0
Exp/Cntr=0.3,0.1

Type RM Length L Ch R = 1 ,1128    ,942,942,942
BEGIN DESCRIPTION:
Mapping XS 9927cccd
END DESCRIPTION:
XS GIS Cut Line= 4
      2502074.23     13468679.79      2501556.89     13468613.82
      2501445.78     13468745.77      2501341.61     13469388.15
#Sta/Elev= 30
  4376.6  177.26  4486.7  177.52  4587.5  175.94  4640.1  174.49  4679.6  173.58
  4691.5  173.29  4767.1  171.46  4772.1  170.27  4829.5  166.93  4846.9  166.54
    4852  165.69  4869.8  166.03  4921.8  168.66  4936.1  168.56  4950.4  167.42
  4971.3  164.41  4981.9  161.26  4989.8  159.87  4990.1  159.37    4994  159.37
  4994.3  159.87  5006.4  164.69  5020.7  167.87  5049.3  170.99  5067.4  172.01
  5130.6  172.38  5363.7  171.46  5485.9     172  5597.4  173.65  5721.4  174.72
#Mann= 9 ,-1 , 0
  4376.6    .035       0  4640.1     .12       0  4679.6    .035       0
  4691.5     .05       0  4981.9     .12       0  4989.8     .05       0
  4994.3     .12       0  5363.7     .07       0  5597.4     .12       0
Bank Sta=4989.8,4994.3
XS Rating Curve= 0 ,0
Exp/Cntr=0.3,0.1

Type RM Length L Ch R = 1 ,186     ,0,0,0
BEGIN DESCRIPTION:
TRIB 3 TO PERDIDO CREEK 1.0
END DESCRIPTION:
XS GIS Cut Line= 4
      2502115.94     13468575.65      2501428.42     13468009.66
      2501289.53     13468165.91      2501282.59     13469361.91
#Sta/Elev= 30
  4028.6  175.51  4121.1  174.04  4199.5     173  4226.2  172.64  4341.8  171.74
  4456.5  168.92    4562  168.71  4654.6  164.68  4662.4  163.33  4668.9  165.05
  4726.3  166.04  4953.3  162.86  4981.7  157.21    4987  154.46  4987.3  153.96
  4991.5  154.46  4995.9  154.91  5017.7  164.78  5024.4  164.17  5031.9  165.57
  5052.8  164.82  5102.1  166.81  5130.2  166.46  5187.3  162.98  5227.3  164.74
  5297.3  164.36  5486.7  169.38  6085.9     172  6263.7  173.75  6324.2  174.29
#Mann= 9 ,-1 , 0
  4028.6    .035       0  4121.1     .05       0  4199.5    .035       0
  4226.2     .05       0    4987     .05       0  4991.5     .05       0
  5486.7     .12       0  6085.9     .07       0  6263.7     .12       0
Bank Sta=4987,4991.5
XS Rating Curve= 0 ,0
Exp/Cntr=0.3,0.1

Chan Stop Cuts=-1
Use User Specified Reach Order=0
Composite Channel Slope=5