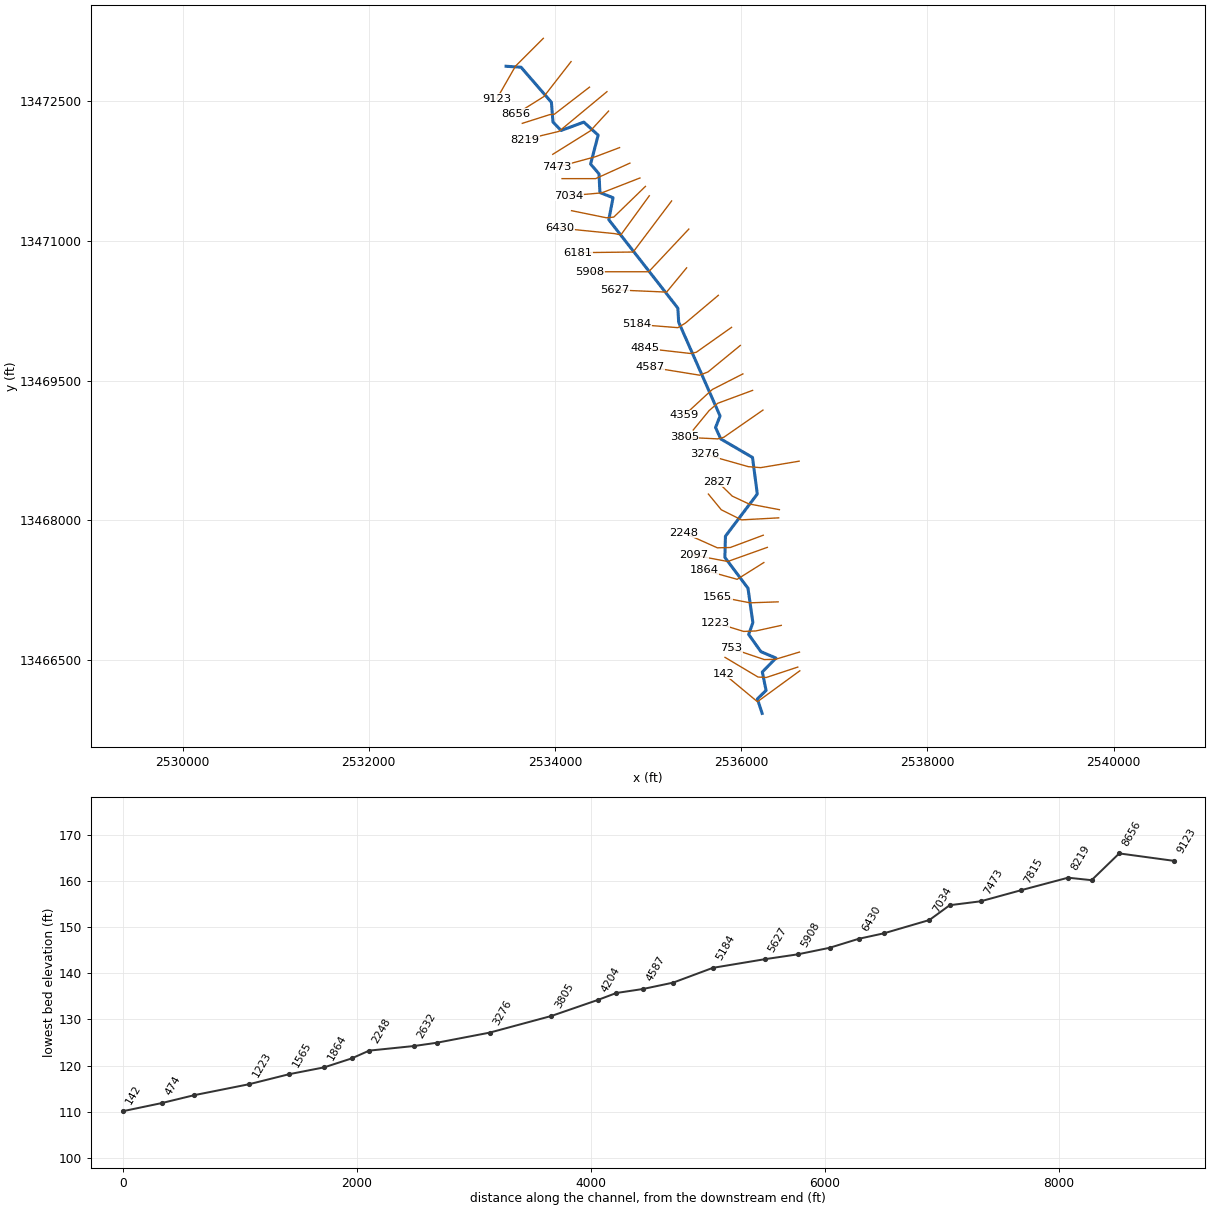
--- TRIB 3 TO TURKEY CREEK.prj (project) ---

Proj Title=TRIB 3 TO TURKEY CREEK Base Level Engineering
Current Plan=p01
Default Exp/Contr=0.3,0.1
English Units
Geom File=g01
Flow File=f01
Plan File=p01
Y Axis Title=Elevation
X Axis Title(PF)=Main Channel Distance
X Axis Title(XS)=Station
BEGIN DESCRIPTION:
TRIB 3 TO TURKEY CREEK
END DESCRIPTION:
DSS Export Rating Curves= 0
DSS Export Rating Curve Sorted= 0
DSS Export Volume Flow Curves= 0
DXF OffsetX= 0
DXF OffsetY= 0
DXF ScaleX= 1
DXF ScaleY= 10

--- TRIB 3 TO TURKEY CREEK.p01 (plan) ---

Plan Title=Multiple Run
Short Identifier=Multiple
Geom File=g01
Flow File=f01
Subcritical Flow
K Sum by GR= 0
Std Step Tol= 0.01
Critical Tol= 0.01
Num of Std Step Trials= 20
Max Error Tol= 0.3
Flow Tol Ratio= 0.001
Split Flow NTrial= 30
Split Flow Tol= 0.02
Split Flow Ratio= 0.02
Log Output Level= 0
Friction Slope Method= 1
Unsteady Friction Slope Method= 2
Unsteady Bridges Friction Slope Method= 1
Parabolic Critical Depth
Global Vel Dist=  1 , 1 , 1
Global Log Level= 0
CheckData=True
Encroach Param= -1, 0, 0, 0
BEGIN DESCRIPTION:
Multiple Run
END DESCRIPTION:

--- TRIB 3 TO TURKEY CREEK.f01 (steady flow) ---

Flow Title=Multiple
Number of Profiles=7
Profile Names=10-year,25-year,50-year,1pct_min,100-year,1pct_plu,500-year
River Rch & RM= TRIB 3 TO TURKEY,Reach-1,9123
     367     562     729     458     914    1824    1420
River Rch & RM= TRIB 3 TO TURKEY,Reach-1,5184
     606     958    1269     814    1625    3243    2632
Boundary for River Rch & Prof#=TRIB 3 TO TURKEY,Reach-1,1
Up Type=0
Dn Type=3
Dn Slope=0.005
Boundary for River Rch & Prof#=TRIB 3 TO TURKEY,Reach-1,2
Up Type=0
Dn Type=3
Dn Slope=0.005
Boundary for River Rch & Prof#=TRIB 3 TO TURKEY,Reach-1,3
Up Type=0
Dn Type=3
Dn Slope=0.005
Boundary for River Rch & Prof#=TRIB 3 TO TURKEY,Reach-1,4
Up Type=0
Dn Type=3
Dn Slope=0.005
Boundary for River Rch & Prof#=TRIB 3 TO TURKEY,Reach-1,5
Up Type=0
Dn Type=3
Dn Slope=0.005
Boundary for River Rch & Prof#=TRIB 3 TO TURKEY,Reach-1,6
Up Type=0
Dn Type=3
Dn Slope=0.005
Boundary for River Rch & Prof#=TRIB 3 TO TURKEY,Reach-1,7
Up Type=0
Dn Type=3
Dn Slope=0.005

--- TRIB 3 TO TURKEY CREEK.g01 (geometry) ---

Geom Title=Existing Conditions
Program Version=4.10

River Reach=TRIB 3 TO TURKEY,Reach-1
Reach XY= 30
        2533475.       13472875.      2533635.13     13472864.67
      2533961.63     13472488.32      2533978.53     13472276.45
      2534065.29     13472185.18      2534309.66     13472275.05
       2534463.9     13472135.06      2534382.33      13471824.9
      2534472.92     13471719.15      2534482.68     13471518.48
      2534623.51     13471463.46      2534578.14     13471226.64
      2535319.53     13470277.45      2535328.55     13470126.47
       2535773.2     13469118.89      2535724.71     13468995.18
      2535780.72     13468872.45      2536121.47     13468673.55
      2536173.04     13468280.89      2535830.69     13467827.39
      2535824.79     13467599.91      2536072.94     13467269.15
      2536125.39       13466900.      2536080.11     13466772.71
      2536211.35     13466588.26      2536373.52     13466519.12
      2536226.97     13466369.32      2536267.27     13466171.35
      2536173.99     13466080.44        2536225.       13465925.

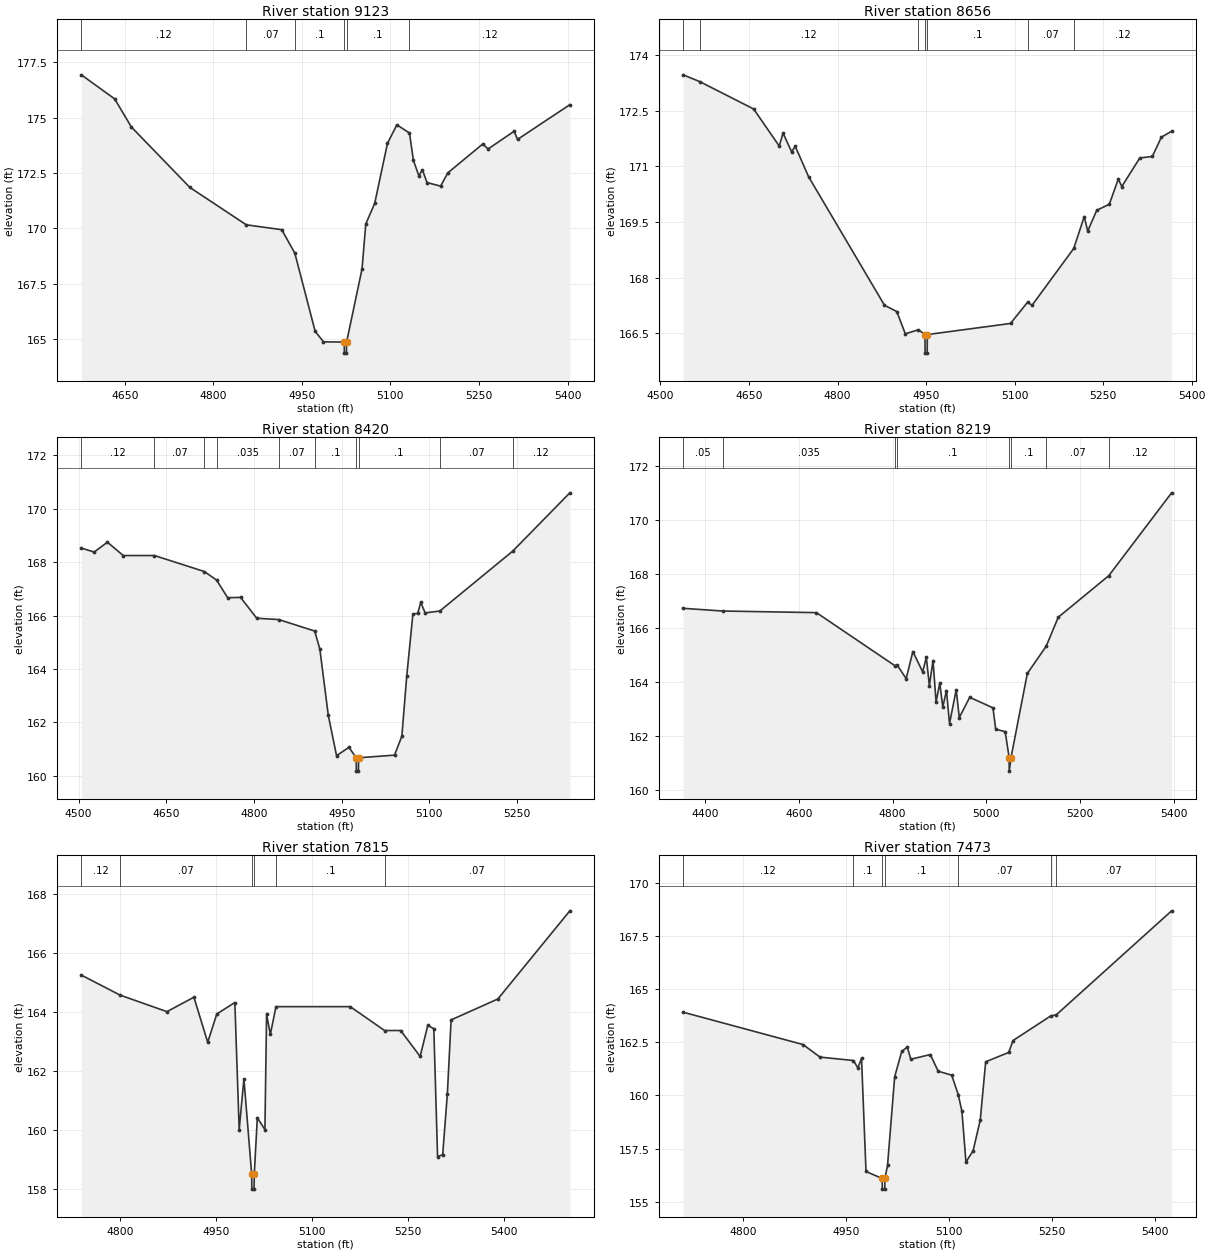
Type RM Length L Ch R = 1 ,9123    ,467,467,467
BEGIN DESCRIPTION:
TRIB 3 TO TURKEY CREEK 20.0
END DESCRIPTION:
XS GIS Cut Line= 3
      2533874.99     13473174.99        2533575.       13472875.
      2533374.98     13472524.96
#Sta/Elev= 30
  4576.5  176.94    4633  175.85  4661.3  174.58  4760.3  171.85  4855.9  170.16
  4915.9  169.94  4938.1  168.88  4972.5  165.35  4986.6  164.87  5021.8  164.86
    5022  164.36  5025.5  164.36  5025.8  164.86  5051.9  168.16  5058.3   170.2
  5073.4  171.13    5095  173.84  5110.9  174.68  5132.3  174.31    5139  173.07
  5148.3  172.37  5154.1  172.65    5162  172.07    5185  171.91  5197.3  172.51
  5256.3  173.81  5265.6  173.59  5309.6  174.39  5315.3  174.02  5403.9  175.59
#Mann= 6 ,-1 , 0
  4576.5     .12       0  4855.9     .07       0  4938.1      .1       0
  5021.8     .05       0  5025.8      .1       0  5132.3     .12       0
Bank Sta=5021.8,5025.8
XS Rating Curve= 0 ,0
Exp/Cntr=0.3,0.1

Type RM Length L Ch R = 1 ,8656    ,236,236,236
BEGIN DESCRIPTION:
Mapping XS 0c9ef8ed
END DESCRIPTION:
XS GIS Cut Line= 3
      2534172.82     13472925.01      2533881.18     13472550.05
      2533582.59     13472362.56
#Sta/Elev= 30
  4538.4  173.47  4566.2  173.29  4657.9  172.55  4701.3  171.55  4707.7   171.9
  4722.1   171.4  4728.5  171.54  4751.1  170.72  4879.6  167.26  4900.4  167.09
  4914.9  166.49  4937.1   166.6  4948.2  166.47  4948.4  165.97  4951.9  165.97
  4952.2  166.47  5093.1  166.77  5121.9  167.34  5129.6  167.26  5200.2  168.79
    5218  169.65  5223.9  169.26  5239.2  169.82  5260.4  169.98  5275.7  170.66
  5281.6  170.46  5312.2  171.23  5333.4  171.27  5348.7  171.79    5366  171.95
#Mann= 7 ,-1 , 0
  4538.4    .035       0  4566.2     .12       0  4937.1      .1       0
  4948.2     .05       0  4952.2      .1       0  5121.9     .07       0
  5200.2     .12       0
Bank Sta=4948.2,4952.2
XS Rating Curve= 0 ,0
Exp/Cntr=0.3,0.1

Type RM Length L Ch R = 1 ,8420    ,201,201,201
BEGIN DESCRIPTION:
Mapping XS 4f75714d
END DESCRIPTION:
XS GIS Cut Line= 4
      2534370.76     13472650.74      2533992.29     13472359.08
      2533943.68      13472355.6      2533649.22     13472262.07
#Sta/Elev= 30
  4504.7  168.53  4526.6  168.38  4549.3  168.75  4576.4  168.25  4629.7  168.25
  4715.1  167.65  4736.1  167.33  4754.9  166.67  4777.1  166.68  4804.7   165.9
  4842.5  165.85  4903.8  165.42  4912.6  164.75  4927.1  162.26  4941.2  160.75
  4962.4  161.06  4974.9  160.67  4975.1  160.17  4978.6  160.17  4978.9  160.67
  5040.4  160.77  5052.9  161.48  5061.3  163.74  5071.8  166.06  5079.9  166.08
  5085.2  166.49  5092.8   166.1  5117.8  166.17  5242.8  168.42  5340.2   170.6
#Mann= 10 ,-1 , 0
  4504.7     .12       0  4629.7     .07       0  4715.1     .12       0
  4736.1    .035       0  4842.5     .07       0  4903.8      .1       0
  4974.9     .05       0  4978.9      .1       0  5117.8     .07       0
  5242.8     .12       0
Bank Sta=4974.9,4978.9
XS Rating Curve= 0 ,0
Exp/Cntr=0.3,0.1

Type RM Length L Ch R = 1 ,8219    ,404,404,404
BEGIN DESCRIPTION:
Mapping XS af093b38
END DESCRIPTION:
XS GIS Cut Line= 4
      2534558.25     13472602.13      2534092.98     13472216.72
       2534040.9     13472175.05      2533679.85     13472088.26
#Sta/Elev= 30
  4353.1  166.73  4437.2  166.63  4637.6  166.57  4804.8  164.61  4809.6  164.64
    4829  164.13  4843.3  165.13  4864.2  164.38    4872  164.92  4878.5  163.87
  4886.3   164.8  4892.8  163.27  4900.7  163.97  4907.1  163.08    4915  163.69
  4921.5  162.47  4935.8  163.72  4942.3  162.69  4964.6  163.44  5014.2  163.05
    5020  162.26  5040.3  162.17  5048.7  161.21  5048.9  160.71  5052.7  161.21
  5087.5  164.32  5127.8  165.33  5153.5   166.4  5261.5  167.94  5395.3     171
#Mann= 8 ,-1 , 0
  4353.1     .05       0  4437.2    .035       0  4804.8     .07       0
  4809.6      .1       0  5048.7     .05       0  5052.7      .1       0
  5127.8     .07       0  5261.5     .12       0
Bank Sta=5048.7,5052.7
XS Rating Curve= 0 ,0
Exp/Cntr=0.3,0.1

Type RM Length L Ch R = 1 ,7815    ,342,342,342
BEGIN DESCRIPTION:
Mapping XS 2587249e
END DESCRIPTION:
XS GIS Cut Line= 3
      2534575.63     13472393.81      2534381.18     13472181.99
       2533976.1     13471929.25
#Sta/Elev= 30
  4738.7  165.24  4799.5  164.56  4872.8     164    4915  164.49  4936.6  162.96
  4950.8  163.92  4979.1  164.31  4985.9     160  4993.3  161.72  5005.5  158.48
  5005.7  157.98  5009.2  157.98  5009.5  158.48  5014.3   160.4  5026.2     160
  5028.8  163.91  5034.7  163.23  5043.5  164.17  5159.8  164.17  5213.6  163.36
  5238.8  163.36  5269.3  162.48  5281.3  163.54  5290.7  163.42  5296.6  159.08
  5304.6  159.15  5311.9  161.21  5317.8  163.72    5391  164.43  5503.7  167.42
#Mann= 6 ,-1 , 0
  4738.7     .12       0  4799.5     .07       0  5005.5     .05       0
  5009.5     .07       0  5043.5      .1       0  5213.6     .07       0
Bank Sta=5005.5,5009.5
XS Rating Curve= 0 ,0
Exp/Cntr=0.3,0.1

Type RM Length L Ch R = 1 ,7473    ,265,265,265
BEGIN DESCRIPTION:
Mapping XS a911048f
END DESCRIPTION:
XS GIS Cut Line= 3
      2534693.65     13472001.43      2534436.73     13471904.22
      2534016.57     13471789.63
#Sta/Elev= 30
  4713.3  163.91  4887.6  162.39  4912.4   161.8    4961  161.64  4967.4  161.29
  4972.7  161.75  4979.2  156.43  5002.7   156.1  5002.9   155.6  5006.4   155.6
  5006.7   156.1  5010.5  156.71  5020.9  160.88  5031.2  162.07  5039.2  162.27
  5044.4   161.7  5072.7  161.92  5084.1  161.14  5103.8  160.95  5113.3  160.04
  5118.7  159.25  5124.5  156.87  5134.9   157.4  5145.3  158.84  5153.2  161.58
  5186.7  162.02    5193  162.58  5247.6  163.73    5256  163.79  5423.5  168.67
#Mann= 7 ,-1 , 0
  4713.3     .12       0    4961      .1       0  5002.7     .05       0
  5006.7      .1       0  5113.3     .07       0  5247.6      .1       0
    5256     .07       0
Bank Sta=5002.7,5006.7
XS Rating Curve= 0 ,0
Exp/Cntr=0.3,0.1

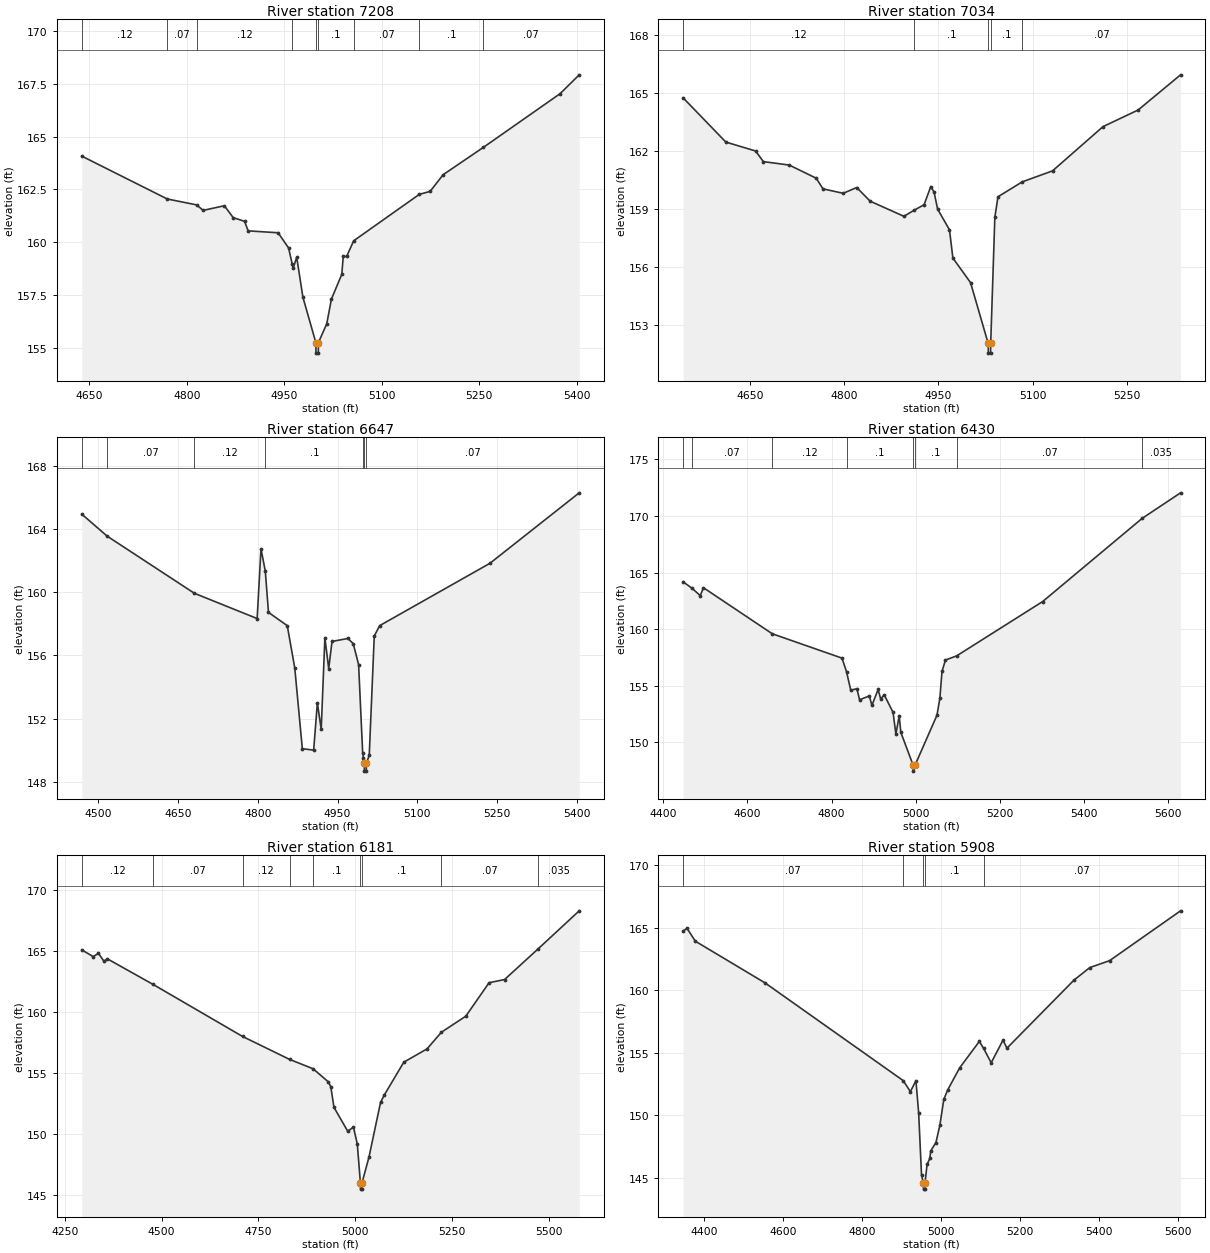
Type RM Length L Ch R = 1 ,7208    ,174,174,174
BEGIN DESCRIPTION:
Mapping XS 1aed2feb
END DESCRIPTION:
XS GIS Cut Line= 3
      2534804.78     13471834.77      2534436.73      13471668.1
      2534075.65      13471668.1
#Sta/Elev= 30
  4638.5  164.08    4770  162.05  4815.2  161.77  4825.1  161.51  4857.8  161.73
  4871.3  161.17  4888.9  160.99  4894.4  160.54  4940.5  160.45  4956.6  159.73
    4962  158.99  4963.6  158.77  4969.1  159.29  4978.6   157.4  4998.5  155.25
  4998.8  154.75  5002.3  154.75  5002.5  155.25  5015.3  156.14  5022.5  157.31
  5038.4  158.48  5040.7  159.33  5045.9  159.33  5056.7  160.07  5157.7  162.27
  5174.3  162.41  5194.3   163.2    5256  164.49  5374.3  167.04  5403.6  167.93
#Mann= 9 ,-1 , 0
  4638.5     .12       0    4770     .07       0  4815.2     .12       0
    4962      .1       0  4998.5     .05       0  5002.5      .1       0
  5056.7     .07       0  5157.7      .1       0    5256     .07       0
Bank Sta=4998.5,5002.5
XS Rating Curve= 0 ,0
Exp/Cntr=0.3,0.1

Type RM Length L Ch R = 1 ,7034    ,387,387,387
BEGIN DESCRIPTION:
Mapping XS d9fd89c3
END DESCRIPTION:
XS GIS Cut Line= 3
      2534912.42     13471675.05       2534502.7     13471515.33
      2534152.04     13471484.08
#Sta/Elev= 30
  4543.6  164.75  4611.6  162.46  4658.9     162  4671.3  161.45  4712.6  161.27
  4755.5  160.59  4766.2  160.04  4798.4  159.81  4819.9  160.11  4841.4   159.4
    4895  158.62  4911.7  158.94  4927.2  159.22  4937.8  160.16  4943.1  159.87
  4948.7  158.99  4967.6  157.92    4973  156.46  5001.1  155.19  5029.2  152.04
  5029.5  151.54    5033  151.54  5033.2  152.04  5039.8  158.57  5044.8  159.63
  5083.3   160.4  5131.6  160.97    5212  163.26  5267.9  164.12  5335.4  165.94
#Mann= 5 ,-1 , 0
  4543.6     .12       0  4911.7      .1       0  5029.2     .05       0
  5033.2      .1       0  5083.3     .07       0
Bank Sta=5029.2,5033.2
XS Rating Curve= 0 ,0
Exp/Cntr=0.3,0.1

Type RM Length L Ch R = 1 ,6647    ,217,217,217
BEGIN DESCRIPTION:
Mapping XS f37e6f58
END DESCRIPTION:
XS GIS Cut Line= 4
      2534971.45     13471584.77      2534631.18     13471254.91
      2534551.32     13471247.97      2534178.16     13471323.98
#Sta/Elev= 30
  4469.2  164.94  4516.8  163.55  4680.8  159.93  4798.8  158.33    4806  162.74
  4814.1  161.34  4820.1  158.72  4855.4  157.88  4869.5   155.2  4883.7  150.09
    4905     150    4912  152.99  4919.2  151.31  4926.1  157.12  4933.3  155.16
  4939.5  156.88  4969.4  157.07  4979.4  156.74  4989.5  155.41  4997.1  149.83
  4998.5  149.53  5000.2  149.17  5000.4  148.67  5003.9  148.67  5004.2  149.17
  5009.5  149.68  5018.9  157.22    5029  157.88  5236.4  161.83  5404.1  166.29
#Mann= 7 ,-1 , 0
  4469.2     .12       0  4516.8     .07       0  4680.8     .12       0
  4814.1      .1       0  4998.5     .07       0  5000.2     .05       0
  5004.2     .07       0
Bank Sta=5000.2,5004.2
XS Rating Curve= 0 ,0
Exp/Cntr=0.3,0.1

Type RM Length L Ch R = 1 ,6430    ,249,249,249
BEGIN DESCRIPTION:
Mapping XS 147ae204
END DESCRIPTION:
XS GIS Cut Line= 4
      2535013.13     13471484.08      2534707.57     13471063.94
      2534638.12     13471077.83      2534048.89     13471136.75
#Sta/Elev= 30
  4447.2  164.19  4467.7  163.64  4487.9  162.97  4495.5  163.67  4659.2   159.6
  4824.9  157.45  4835.6  156.25  4845.7  154.62  4860.4  154.75  4866.6  153.77
  4889.8  154.11    4896  153.27  4910.7  154.68  4916.8  153.85  4925.3  154.21
  4946.2  152.66    4953  150.74  4960.9  152.37  4964.6  150.91  4994.2  147.97
  4994.5  147.47  4998.2  147.97  5050.7  152.41  5057.6  153.93  5062.6  156.27
  5070.8  157.28  5097.5  157.65    5302  162.45  5538.3  169.79  5629.7  172.05
#Mann= 8 ,-1 , 0
  4447.2     .12       0  4467.7     .07       0  4659.2     .12       0
  4835.6      .1       0  4994.2     .05       0  4998.2      .1       0
  5097.5     .07       0  5538.3    .035       0
Bank Sta=4994.2,4998.2
XS Rating Curve= 0 ,0
Exp/Cntr=0.3,0.1

Type RM Length L Ch R = 1 ,6181    ,273,273,273
BEGIN DESCRIPTION:
Mapping XS d3122df4
END DESCRIPTION:
XS GIS Cut Line= 3
      2535252.71     13471428.53      2534839.51     13470879.91
      2534242.27     13470872.96
#Sta/Elev= 30
    4294  165.12  4323.5  164.57    4337  164.84  4351.6  164.17  4359.9  164.39
  4478.1  162.29  4708.9  158.03  4830.3  156.15  4891.2  155.38  4930.4  154.31
  4936.9   153.9    4945  152.22  4980.4  150.27  4995.3  150.59  5005.3  149.21
  5013.3  146.02  5013.6  145.52  5017.1  145.52  5017.3  146.02  5035.3  148.13
  5065.3  152.63  5075.3  153.25  5125.3  155.92  5185.3  157.01  5222.2  158.37
  5285.4  159.69  5345.4  162.43  5385.4  162.69  5470.9  165.17  5578.1  168.32
#Mann= 9 ,-1 , 0
    4294     .12       0  4478.1     .07       0  4708.9     .12       0
  4830.3     .07       0  4891.2      .1       0  5013.3     .05       0
  5017.3      .1       0  5222.2     .07       0  5470.9    .035       0
Bank Sta=5013.3,5017.3
XS Rating Curve= 0 ,0
Exp/Cntr=0.3,0.1

Type RM Length L Ch R = 1 ,5908    ,281,281,281
BEGIN DESCRIPTION:
Mapping XS cc915e34
END DESCRIPTION:
XS GIS Cut Line= 3
      2535437.46     13471126.47      2535006.87      13470668.1
      2534374.96      13470668.1
#Sta/Elev= 30
  4346.3  164.75  4356.2  164.97  4377.2  163.94  4554.1   160.6  4904.3  152.78
  4922.3   151.9  4936.4  152.78  4943.3   150.2  4950.6   145.2  4955.4   144.6
  4955.7   144.1  4959.2   144.1  4959.4   144.6  4964.7  146.08  4971.6  146.56
  4973.9  147.16  4987.1  147.83  4997.1  149.22  5007.1  151.29  5017.1  152.05
  5047.1   153.8  5097.1  155.92    5108  155.36  5127.1  154.21  5157.1  156.02
  5167.1  155.38  5337.1  160.83  5377.1  161.83  5427.1  162.38  5607.1  166.37
#Mann= 5 ,-1 , 0
  4346.3     .07       0  4904.3      .1       0  4955.4     .05       0
  4959.4      .1       0    5108     .07       0
Bank Sta=4955.4,4959.4
XS Rating Curve= 0 ,0
Exp/Cntr=0.3,0.1

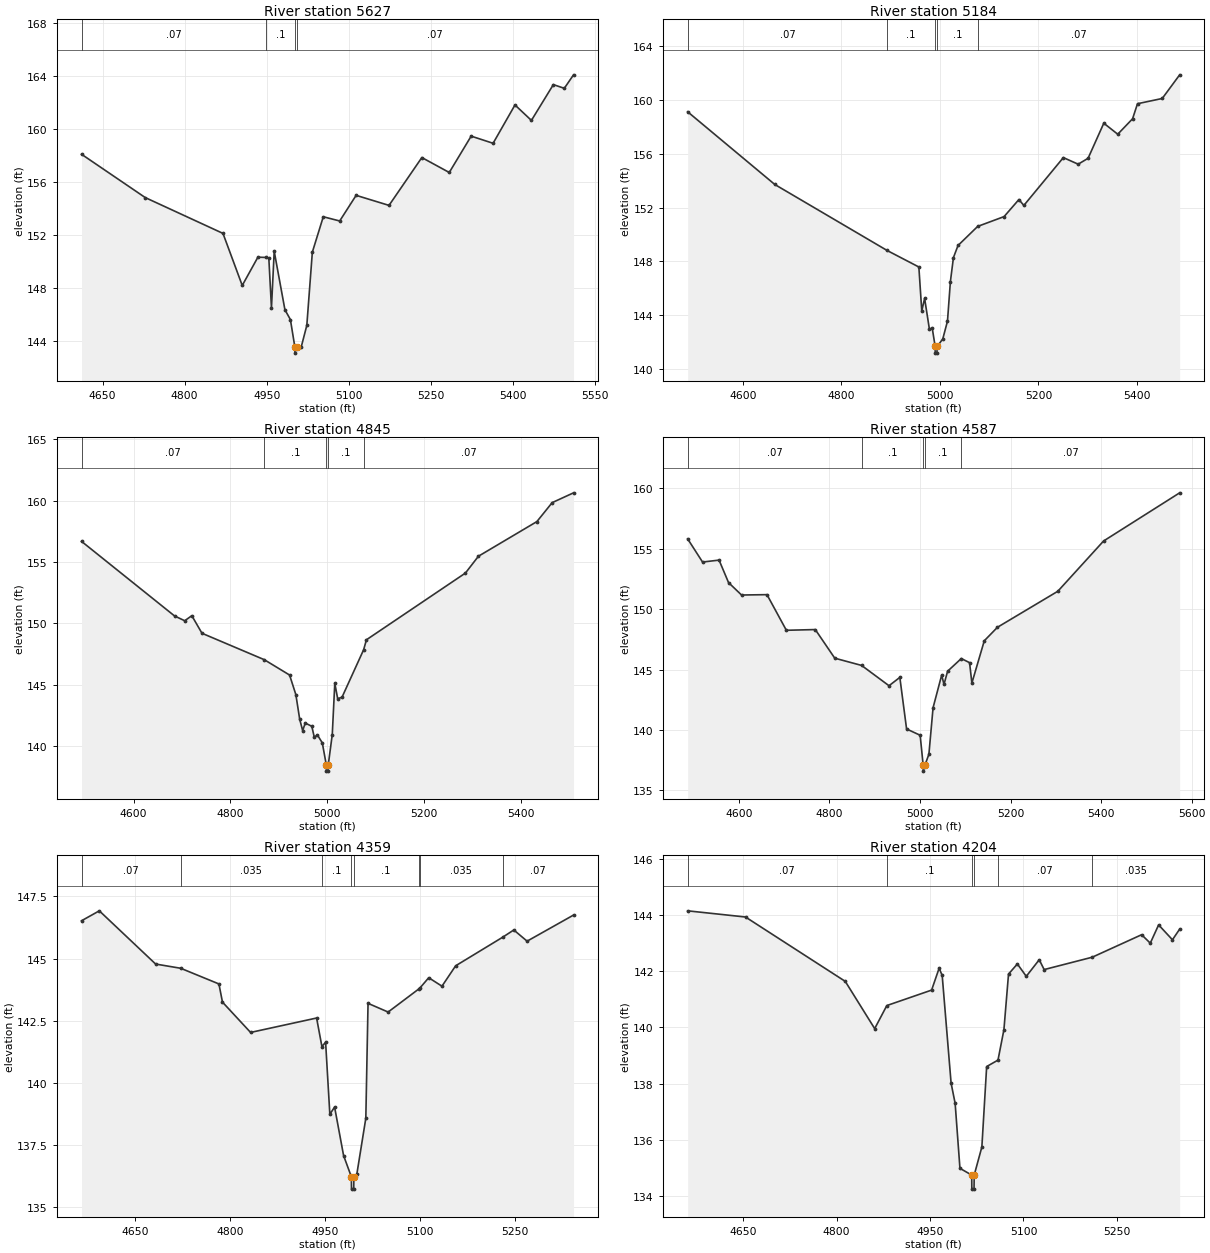
Type RM Length L Ch R = 1 ,5627    ,443,443,443
BEGIN DESCRIPTION:
Mapping XS 3cd6628c
END DESCRIPTION:
XS GIS Cut Line= 3
      2535414.06     13470710.02      2535198.77     13470449.59
       2534638.1     13470473.81
#Sta/Elev= 30
  4611.5   158.1    4728  154.82    4870  152.11  4905.2  148.17  4933.8  150.31
  4949.1  150.29  4953.8  150.22  4958.6  146.47  4963.6  150.76  4983.2  146.33
  4993.2  145.59  5001.2  143.55  5001.5  143.05  5005.2  143.55  5013.2  143.55
  5023.2  145.15  5033.3  150.69  5053.3  153.37  5083.3  153.05  5113.3  154.99
  5173.4  154.23  5233.4  157.85  5283.5  156.72  5323.5  159.47  5363.6  158.93
  5403.6  161.83  5433.6  160.66  5473.7  163.37  5493.7  163.09  5510.6  164.11
#Mann= 4 ,-1 , 0
  4611.5     .07       0  4949.1      .1       0  5001.2     .05       0
  5005.2     .07       0
Bank Sta=5001.2,5005.2
XS Rating Curve= 0 ,0
Exp/Cntr=0.3,0.1

Type RM Length L Ch R = 1 ,5184    ,339,339,339
BEGIN DESCRIPTION:
Mapping XS 08fee6d7
END DESCRIPTION:
XS GIS Cut Line= 4
       2535754.3     13470414.84      2535400.16     13470116.25
       2535320.3     13470067.64      2534879.67     13470102.34
#Sta/Elev= 30
  4488.1  159.14    4665  153.73  4892.9  148.82  4957.4  147.59  4963.3  144.32
  4969.1  145.25  4978.7  142.99  4984.6  143.03  4990.5  141.68  4990.7  141.18
  4994.2  141.18  4994.5  141.68  5005.9  142.23  5015.5  143.56  5021.4   146.5
  5027.6  148.29  5036.9  149.19  5076.8  150.61  5130.4  151.34  5160.5  152.61
  5170.5  152.17  5250.7  155.73  5280.8  155.24  5300.9  155.68  5332.8  158.29
  5361.1  157.47  5391.2  158.62  5401.2  159.74  5451.4  160.13  5486.8  161.89
#Mann= 5 ,-1 , 0
  4488.1     .07       0  4892.9      .1       0  4990.5     .05       0
  4994.5      .1       0  5076.8     .07       0
Bank Sta=4990.5,4994.5
XS Rating Curve= 0 ,0
Exp/Cntr=0.3,0.1

Type RM Length L Ch R = 1 ,4845    ,258,258,258
BEGIN DESCRIPTION:
Mapping XS 93f16a3c
END DESCRIPTION:
XS GIS Cut Line= 4
      2535896.72     13470071.14      2535518.21     13469803.75
      2535459.19     13469789.86      2534969.79      13469845.4
#Sta/Elev= 30
  4492.4  156.68  4684.6  150.61  4705.6  150.22  4720.3  150.63  4741.3   149.2
    4870  147.05  4922.3   145.8  4935.3   144.2  4943.2   142.2  4949.3  141.28
  4954.7  141.89  4968.2  141.63  4973.4  140.73  4979.7  140.93  4989.9  140.28
  4998.2  138.48  4998.5  137.98    5002  137.98  5002.2  138.48  5010.5  140.96
  5015.7  145.13  5021.7  143.87  5030.7     144  5075.3  147.86  5081.1  148.67
  5285.6   154.1  5312.5  155.47  5433.3  158.29  5464.8  159.83    5509  160.63
#Mann= 5 ,-1 , 0
  4492.4     .07       0    4870      .1       0  4998.2     .05       0
  5002.2      .1       0  5075.3     .07       0
Bank Sta=4998.2,5002.2
XS Rating Curve= 0 ,0
Exp/Cntr=0.3,0.1

Type RM Length L Ch R = 1 ,4587    ,228,228,228
BEGIN DESCRIPTION:
Mapping XS a334040a
END DESCRIPTION:
XS GIS Cut Line= 4
      2535990.46     13469876.69      2535643.21     13469591.95
      2535552.94     13469557.22      2535019.11     13469643.88
#Sta/Elev= 30
    4487  155.83  4519.9  153.91  4556.4  154.07  4577.3  152.21    4606  151.18
  4662.2  151.21    4705  148.26  4768.9  148.32  4811.9  145.95  4871.2  145.35
  4931.7  143.67  4955.6  144.36  4970.5  140.09  5000.5  139.57  5007.1   137.1
  5007.4   136.6  5011.1   137.1  5019.8     138    5029  141.85    5048  144.55
  5053.1  143.78  5061.1  144.87  5091.3  145.92  5109.6  145.58  5114.7  143.89
  5142.1  147.39  5171.2  148.51  5304.5  151.49  5405.5  155.65  5573.6  159.64
#Mann= 5 ,-1 , 0
    4487     .07       0  4871.2      .1       0  5007.1     .05       0
  5011.1      .1       0  5091.3     .07       0
Bank Sta=5007.1,5011.1
XS Rating Curve= 0 ,0
Exp/Cntr=0.3,0.1

Type RM Length L Ch R = 1 ,4359    ,155,155,155
BEGIN DESCRIPTION:
Mapping XS e21eb781
END DESCRIPTION:
XS GIS Cut Line= 4
      2536018.25     13469571.13      2535691.82     13469404.45
      2535625.85     13469345.42       2535389.9     13469126.81
#Sta/Elev= 30
  4565.5  146.52  4593.6  146.92  4682.5  144.78  4722.1  144.61  4782.4  143.98
    4788  143.25  4832.4  142.03  4936.6  142.61    4945  141.46  4950.8  141.64
  4957.5  138.74    4965  139.03  4979.2  137.08  4991.4  136.23  4991.7  135.73
  4995.2  135.73  4995.4  136.23  5000.1  136.33  5014.3  138.58  5017.8   143.2
  5049.5  142.85  5097.5  143.77  5099.8  143.82  5113.6  144.23  5134.5  143.89
  5156.1  144.71  5230.4  145.86  5247.9  146.15  5268.9   145.7  5342.2  146.75
#Mann= 8 ,-1 , 0
  4565.5     .07       0  4722.1    .035       0    4945      .1       0
  4991.4     .05       0  4995.4      .1       0  5097.5     .07       0
  5099.8    .035       0  5230.4     .07       0
Bank Sta=4991.4,4995.4
XS Rating Curve= 0 ,0
Exp/Cntr=0.3,0.1

Type RM Length L Ch R = 1 ,4204    ,399,399,399
BEGIN DESCRIPTION:
Mapping XS b6c8d8c1
END DESCRIPTION:
XS GIS Cut Line= 4
      2536122.34     13469394.01      2535747.38     13469255.14
       2535657.1     13469178.75      2535484.74     13468968.47
#Sta/Elev= 30
  4560.8  144.15  4653.7  143.93  4813.9  141.64  4861.1  139.96  4880.6  140.78
  4952.5  141.33  4964.6  142.11  4969.5  141.85  4983.8  138.02  4990.3   137.3
    4998  134.99  5016.9  134.75  5017.1  134.25  5020.6  134.25  5020.9  134.75
  5033.2  135.75  5040.9  138.61  5059.1  138.84  5068.6  139.92    5076   141.9
  5090.2  142.26  5104.5  141.82  5125.3  142.41  5133.2  142.06  5210.4   142.5
  5289.7   143.3  5303.6     143    5317  143.65  5339.2  143.12  5350.8   143.5
#Mann= 6 ,-1 , 0
  4560.8     .07       0  4880.6      .1       0  5016.9     .05       0
  5020.9      .1       0  5059.1     .07       0  5210.4    .035       0
Bank Sta=5016.9,5020.9
XS Rating Curve= 0 ,0
Exp/Cntr=0.3,0.1

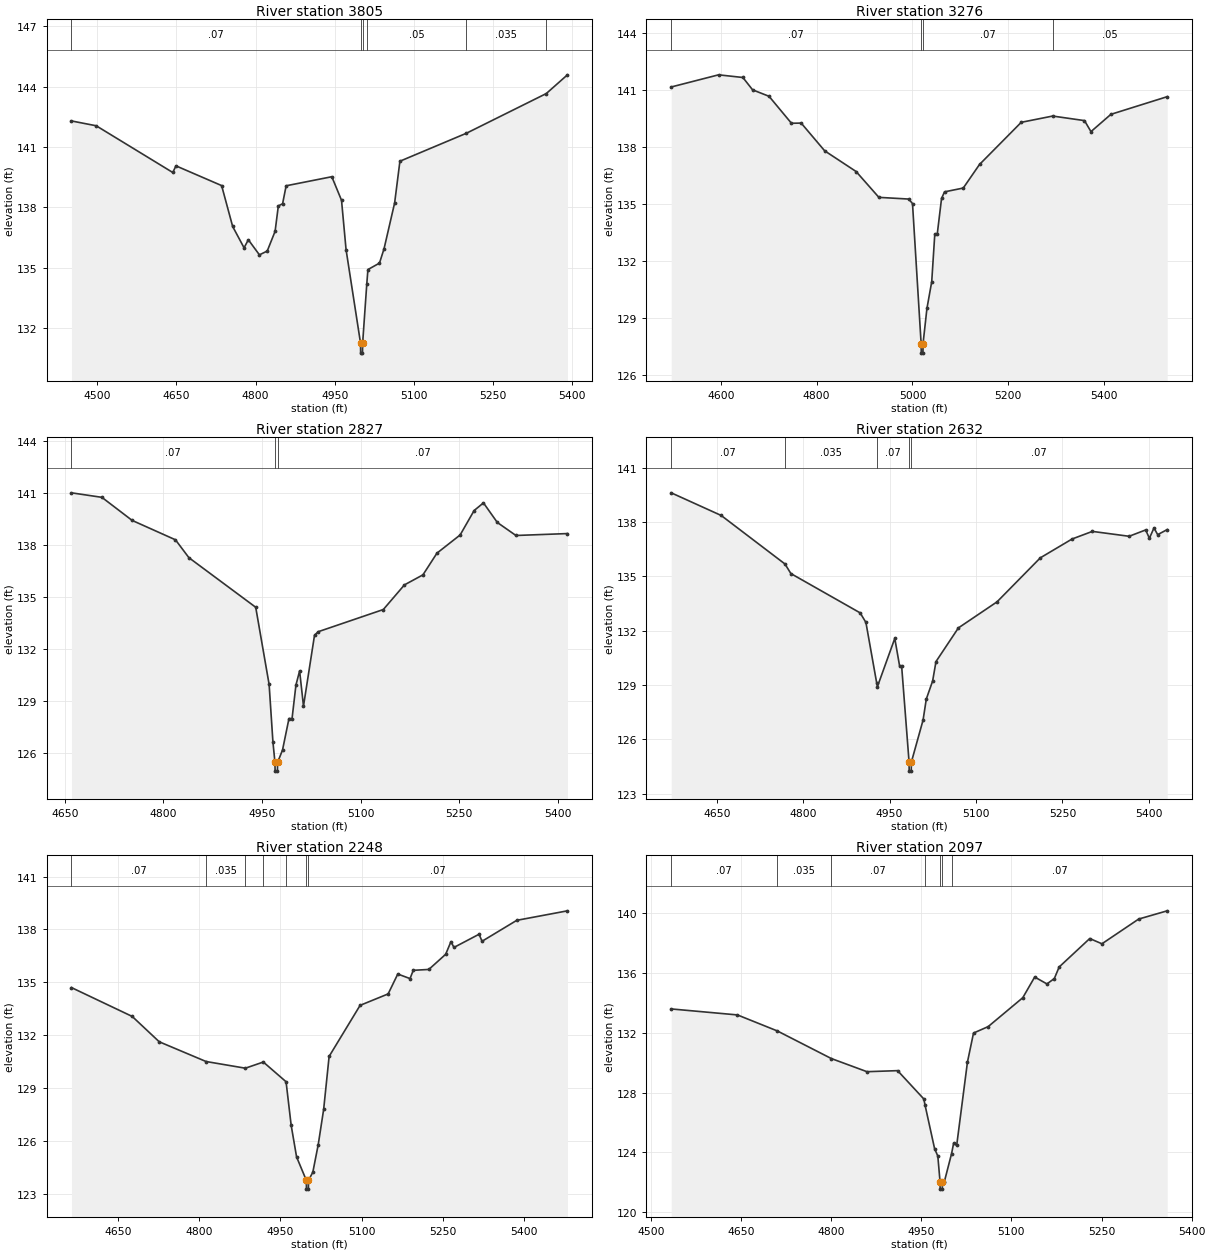
Type RM Length L Ch R = 1 ,3805    ,529,529,529
BEGIN DESCRIPTION:
Mapping XS 591da009
END DESCRIPTION:
XS GIS Cut Line= 4
      2536233.52     13469182.24      2535813.35     13468890.56
      2535747.38      13468873.2       2535388.1     13468890.47
#Sta/Elev= 30
  4451.3  142.29  4498.2  142.05  4643.2  139.73  4649.2  140.06  4735.7  139.08
  4756.6  137.05  4778.2  135.99  4786.3  136.39  4807.3  135.64  4822.1  135.83
    4837  136.81  4843.1  138.07  4851.2  138.18  4857.9  139.07  4944.4  139.52
  4962.8  138.35  4971.4   135.9  4998.8  131.26    4999  130.76  5002.5  130.76
  5002.8  131.26  5010.6  134.18  5012.8  134.91  5034.7  135.23  5043.4  135.95
  5063.4  138.22  5073.4  140.29  5199.4  141.68  5350.6  143.65  5390.7  144.58
#Mann= 6 ,-1 , 0
  4451.3     .07       0  4998.8     .05       0  5002.8     .07       0
  5010.6     .05       0  5199.4    .035       0  5350.6     .05       0
Bank Sta=4998.8,5002.8
XS Rating Curve= 0 ,0
Exp/Cntr=0.3,0.1

Type RM Length L Ch R = 1 ,3276    ,449,449,449
BEGIN DESCRIPTION:
Mapping XS a53d4d69
END DESCRIPTION:
XS GIS Cut Line= 4
      2536622.42     13468633.62      2536209.19     13468564.17
      2536077.24     13468574.59      2535611.97     13468706.53
#Sta/Elev= 30
  4496.6  141.15  4595.4  141.79  4646.1  141.65  4666.4     141  4700.7  140.66
  4747.5  139.24  4767.8  139.25  4816.8  137.79  4882.4   136.7  4929.9  135.34
  4992.4  135.25  5000.1  135.01  5018.1  127.64  5018.4  127.14  5021.9  127.14
  5022.1  127.64  5030.2  129.49  5040.2   130.9  5046.6   133.4  5051.7   133.4
  5060.7  135.28  5066.9  135.63    5106  135.83  5139.9  137.07    5227  139.29
  5292.6  139.62    5359  139.38  5372.5   138.8  5414.1  139.71  5531.6  140.64
#Mann= 4 ,-1 , 0
  4496.6     .07       0  5018.1     .05       0  5022.1     .07       0
  5292.6     .05       0
Bank Sta=5018.1,5022.1
XS Rating Curve= 0 ,0
Exp/Cntr=0.3,0.1

Type RM Length L Ch R = 1 ,2827    ,195,195,195
BEGIN DESCRIPTION:
Mapping XS 26230f27
END DESCRIPTION:
XS GIS Cut Line= 4
      2536410.54     13468112.79      2536080.71     13468175.28
      2535903.63     13468258.61      2535743.94     13468414.83
#Sta/Elev= 30
    4660  141.01  4706.3  140.75  4752.3  139.42  4818.3   138.3  4838.7  137.27
  4940.4  134.41  4960.8  129.96  4966.6  126.64  4969.7  125.46  4969.9  124.96
  4973.4  124.96  4973.7  125.46  4981.2  126.18    4991  127.99  4995.7  127.99
  5001.6  129.92  5007.2  130.74  5013.1  128.71  5029.9   132.8  5035.5     133
  5134.6  134.28  5166.7   135.7  5194.9  136.28  5216.2  137.53  5251.5  138.58
  5272.8  139.99    5287  140.43  5308.1   139.3  5336.4  138.55  5414.8  138.66
#Mann= 3 ,-1 , 0
    4660     .07       0  4969.7     .05       0  4973.7     .07       0
Bank Sta=4969.7,4973.7
XS Rating Curve= 0 ,0
Exp/Cntr=0.3,0.1

Type RM Length L Ch R = 1 ,2632    ,384,384,384
BEGIN DESCRIPTION:
Mapping XS aeb479ae
END DESCRIPTION:
XS GIS Cut Line= 4
      2536402.39     13468024.93      2536003.08     13468003.23
      2535786.06     13468111.73      2535647.61     13468280.47
#Sta/Elev= 30
  4571.1  139.62  4657.8  138.37  4768.5  135.69  4778.8  135.16    4899  132.99
    4909  132.46  4927.8   129.1    4929  128.92  4959.1  131.58  4967.5  130.05
    4971  130.05  4983.9  124.75  4984.1  124.25  4987.6  124.25  4987.9  124.75
  5008.2  127.07  5013.8  128.23  5024.8  129.23  5030.6   130.3  5069.5  132.16
  5136.6   133.6  5211.7  136.03  5266.8  137.07    5302  137.49  5365.8  137.22
  5394.5  137.57    5401  137.11  5408.9  137.68  5415.4  137.31  5431.9  137.59
#Mann= 5 ,-1 , 0
  4571.1     .07       0  4768.5    .035       0  4927.8     .07       0
  4983.9     .05       0  4987.9     .07       0
Bank Sta=4983.9,4987.9
XS Rating Curve= 0 ,0
Exp/Cntr=0.3,0.1

Type RM Length L Ch R = 1 ,2248    ,151,151,151
BEGIN DESCRIPTION:
Mapping XS 3ca5ad7b
END DESCRIPTION:
XS GIS Cut Line= 4
      2536236.94     13467838.47       2535882.8     13467706.53
      2535743.91     13467703.06      2535379.69     13467866.09
#Sta/Elev= 30
  4564.2   134.7  4676.4  133.06  4726.3  131.62  4812.7   130.5  4885.3  130.12
  4918.5  130.47  4960.5  129.35  4969.9  126.88  4979.9  125.08  4997.9  123.75
  4998.2  123.25  5001.7  123.25  5001.9  123.75  5009.9  124.21  5019.9  125.78
  5029.9  127.78    5040  130.79  5097.2  133.69    5149  134.34  5166.8  135.47
  5189.4  135.21  5195.4  135.68  5224.1  135.73  5255.2  136.59    5265  137.31
  5270.5  136.98  5316.9  137.73  5322.4  137.33  5386.5  138.52  5480.1  139.06
#Mann= 7 ,-1 , 0
  4564.2     .07       0  4812.7    .035       0  4885.3     .07       0
  4918.5    .035       0  4960.5     .07       0  4997.9     .05       0
  5001.9     .07       0
Bank Sta=4997.9,5001.9
XS Rating Curve= 0 ,0
Exp/Cntr=0.3,0.1

Type RM Length L Ch R = 1 ,2097    ,233,233,233
BEGIN DESCRIPTION:
Mapping XS de3b4882
END DESCRIPTION:
XS GIS Cut Line= 3
      2536280.85     13467708.08      2535855.51     13467556.18
      2535488.31      13467625.3
#Sta/Elev= 30
    4534  133.58  4644.2  133.18  4710.6  132.11  4800.3  130.27  4859.7  129.39
  4910.7  129.46  4954.3  127.57  4956.4  127.15  4972.3  124.24  4977.6  123.76
  4981.3  122.05  4981.5  121.55    4985  121.55  4985.3  122.05  4988.5  122.05
  5000.5  123.92  5003.9  124.61    5009  124.47  5026.9  130.03    5037  131.97
  5061.4   132.4    5119  134.33  5138.8  135.71  5159.2  135.25  5171.5  135.61
  5179.5  136.38  5230.4  138.28  5250.7  137.93  5311.8  139.58  5359.3  140.13
#Mann= 7 ,-1 , 0
    4534     .07       0  4710.6    .035       0  4800.3     .07       0
  4956.4    .035       0  4981.3    .035       0  4985.3    .035       0
  5000.5     .07       0
Bank Sta=4981.3,4985.3
XS Rating Curve= 0 ,0
Exp/Cntr=0.3,0.1

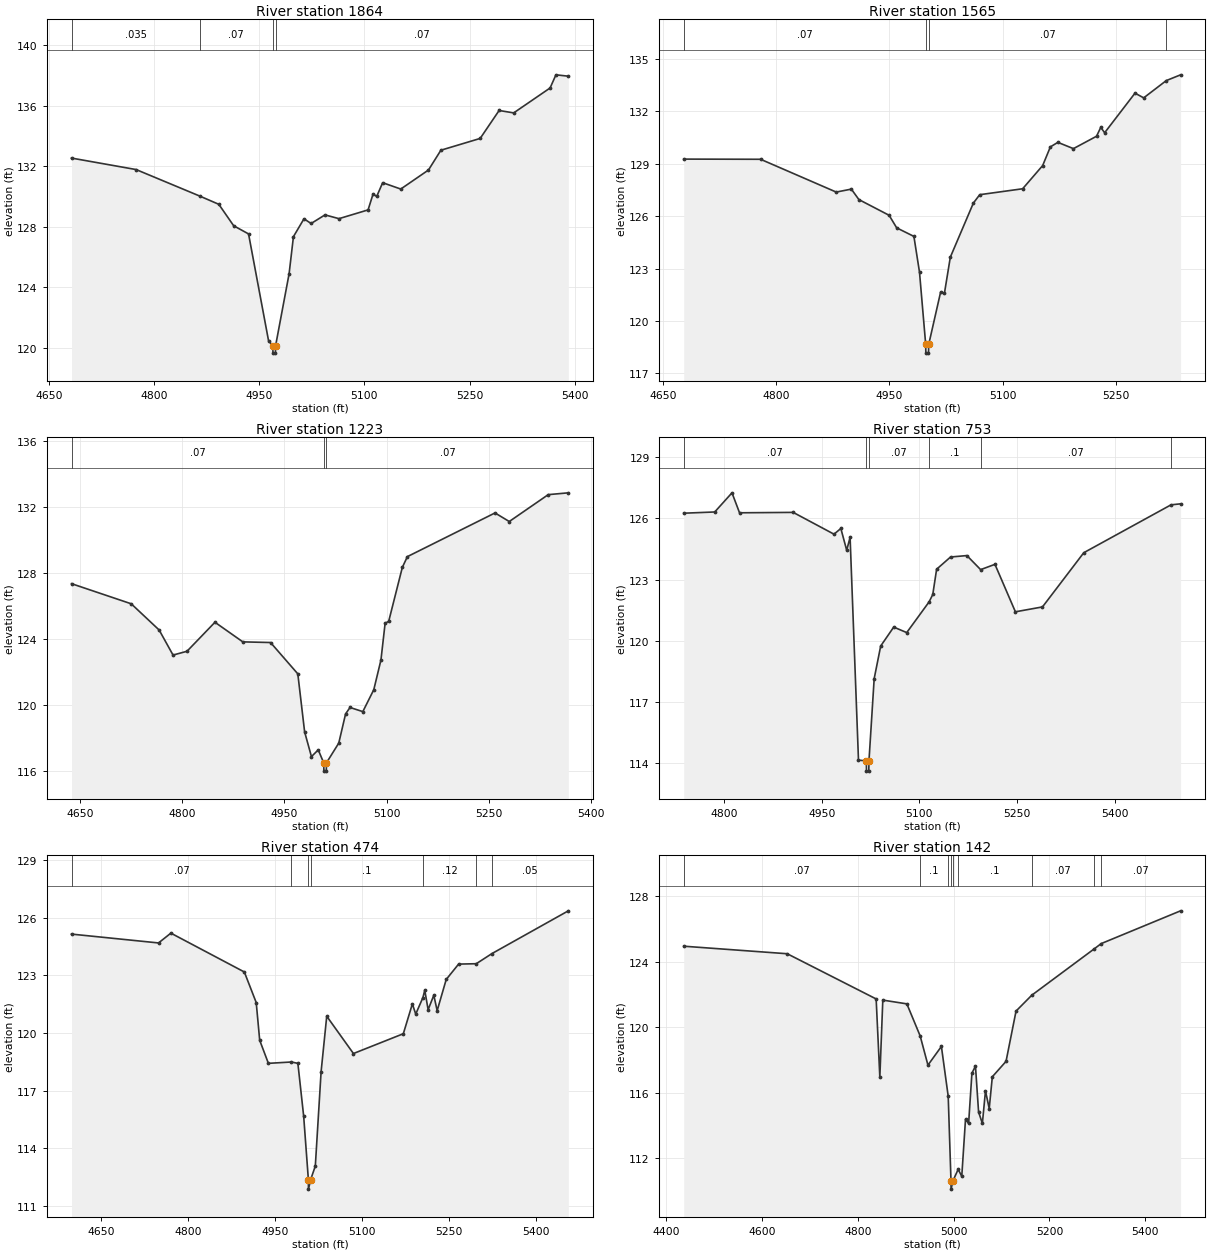
Type RM Length L Ch R = 1 ,1864    ,299,299,299
BEGIN DESCRIPTION:
Mapping XS 2c84130e
END DESCRIPTION:
XS GIS Cut Line= 3
      2536243.05     13467544.64      2535956.58     13467364.95
      2535599.91     13467463.88
#Sta/Elev= 30
  4682.5  132.54  4774.6  131.78  4865.1  130.03  4892.5  129.48  4913.7  128.06
  4934.9  127.52  4963.5  120.43  4969.5  120.13  4969.7  119.63  4973.2  119.63
  4973.5  120.13  4992.7  124.88  4998.9  127.34  5013.9  128.52  5024.1  128.21
  5043.9  128.78  5063.8  128.53  5105.3  129.11  5112.4  130.16  5117.6     130
  5126.1  130.91  5151.9  130.49  5191.4  131.75  5209.1  133.06  5265.1  133.84
  5292.1  135.69  5312.9  135.53  5364.8  137.18  5373.1  138.05  5390.8  137.96
#Mann= 4 ,-1 , 0
  4682.5    .035       0  4865.1     .07       0  4969.5     .05       0
  4973.5     .07       0
Bank Sta=4969.5,4973.5
XS Rating Curve= 0 ,0
Exp/Cntr=0.3,0.1

Type RM Length L Ch R = 1 ,1565    ,342,342,342
BEGIN DESCRIPTION:
Mapping XS 4ee0f488
END DESCRIPTION:
XS GIS Cut Line= 3
      2536396.65     13467122.76       2536094.6     13467112.35
      2535745.83     13467180.02
#Sta/Elev= 30
  4677.8  129.27  4779.5  129.26  4879.6  127.38  4899.6  127.55  4909.6  126.95
  4949.6  126.05  4959.6  125.33  4982.4  124.84  4989.8  122.79    4998  118.65
  4998.2  118.15  5001.7  118.15    5002  118.65  5017.7  121.64  5022.8  121.58
  5030.6  123.65  5061.1  126.75  5069.5  127.23  5126.3  127.57  5152.8   128.9
    5163  129.97  5172.9  130.23  5193.5  129.87  5224.1  130.58  5229.7  131.09
  5234.8  130.78    5275  133.05  5286.5  132.78  5316.4  133.77  5335.3   134.1
#Mann= 4 ,-1 , 0
  4677.8     .07       0    4998     .05       0    5002     .07       0
  5316.4     .05       0
Bank Sta=4998,5002
XS Rating Curve= 0 ,0
Exp/Cntr=0.3,0.1

Type RM Length L Ch R = 1 ,1223    ,470,470,470
BEGIN DESCRIPTION:
Mapping XS 61e238f7
END DESCRIPTION:
XS GIS Cut Line= 4
      2536430.58     13466870.17       2536157.1     13466810.26
      2536026.89     13466805.05      2535722.17     13466898.82
#Sta/Elev= 30
  4637.7  127.35  4725.3  126.13  4766.3  124.54  4786.7  123.02  4807.2  123.25
  4848.2  125.01  4889.1  123.82  4929.8  123.78  4969.8  121.88  4979.8  118.36
  4989.8  116.86  4999.8  117.27  5007.8  116.48  5008.1  115.98  5011.6  115.98
  5011.8  116.48  5029.9  117.68  5039.9  119.45  5046.4  119.84  5065.2  119.59
  5081.3  120.92  5091.8  122.72  5097.9  124.94  5103.2  125.07  5123.2  128.34
  5130.6  128.99  5259.2  131.64  5280.1  131.12  5337.3  132.75  5366.8  132.86
#Mann= 3 ,-1 , 0
  4637.7     .07       0  5007.8     .05       0  5011.8     .07       0
Bank Sta=5007.8,5011.8
XS Rating Curve= 0 ,0
Exp/Cntr=0.3,0.1

Type RM Length L Ch R = 1 ,753     ,279,279,279
BEGIN DESCRIPTION:
Mapping XS 924ddcec
END DESCRIPTION:
XS GIS Cut Line= 4
      2536625.88     13466583.71      2536368.04     13466505.58
      2536248.25     13466502.97       2535894.1     13466622.76
#Sta/Elev= 30
  4738.2  126.26  4785.8  126.32  4812.3  127.26  4823.9  126.28  4906.3   126.3
    4969  125.23  4979.5  125.51  4988.5  124.44  4993.7  125.08  5006.6  114.14
  5018.7   114.1  5018.9   113.6  5022.4   113.6  5022.7   114.1  5030.7  118.14
  5040.7  119.74  5060.7  120.67  5080.7   120.4  5115.1  121.91  5120.7  122.27
  5126.6  123.51    5148  124.11  5173.1  124.18  5194.2  123.49  5216.2  123.75
  5247.6  121.42  5289.2  121.66  5352.6  124.32  5486.6  126.67  5501.3  126.72
#Mann= 6 ,-1 , 0
  4738.2     .07       0  5018.7     .05       0  5022.7     .07       0
  5115.1      .1       0  5194.2     .07       0  5486.6     .05       0
Bank Sta=5018.7,5022.7
XS Rating Curve= 0 ,0
Exp/Cntr=0.3,0.1

Type RM Length L Ch R = 1 ,474     ,332,332,332
BEGIN DESCRIPTION:
Mapping XS 54ce4c20
END DESCRIPTION:
XS GIS Cut Line= 4
      2536607.63     13466422.24      2536269.08     13466310.26
      2536180.54     13466315.47      2535826.38      13466526.4
#Sta/Elev= 30
  4598.8  125.14    4749  124.68  4770.3  125.19  4897.1  123.17  4917.6  121.58
  4923.6  119.62  4938.6  118.42  4978.3  118.49  4989.5  118.42  4999.5  115.67
  5007.6  112.38  5007.8  111.88  5011.6  112.38  5019.6  113.08  5029.6  117.99
  5039.3  120.87  5085.4  118.93  5171.5  119.96  5187.1  121.51  5192.9  120.98
  5205.3  121.84  5208.5  122.22  5214.3  121.21  5224.1  121.96  5229.9  121.16
  5245.5  122.78  5266.9  123.58  5297.4   123.6  5324.6  124.13  5456.3  126.35
#Mann= 7 ,-1 , 0
  4598.8     .07       0  4978.3      .1       0  5007.6     .05       0
  5011.6      .1       0  5205.3     .12       0  5297.4     .07       0
  5324.6     .05       0
Bank Sta=5007.6,5011.6
XS Rating Curve= 0 ,0
Exp/Cntr=0.3,0.1

Type RM Length L Ch R = 1 ,142     ,0,0,0
BEGIN DESCRIPTION:
TRIB 3 TO TURKEY CREEK 1.0
END DESCRIPTION:
XS GIS Cut Line= 3
      2536629.47     13466382.09      2536174.47     13466050.19
      2535810.01     13466352.93
#Sta/Elev= 30
  4436.8  124.95  4652.8  124.49  4838.4  121.73  4846.1  116.96  4852.3  121.66
  4902.5  121.43  4930.3  119.47  4946.5  117.69  4974.6  118.83  4988.8  115.79
  4994.6  110.62  4994.8  110.12  4998.6  110.62  5009.6  111.33  5017.1   110.9
  5024.9  114.38  5031.4  114.13  5038.3   117.2  5045.7  117.63  5052.2  114.83
  5060.1  114.13  5066.6  116.12  5074.4  115.04  5080.9  116.98  5109.5  117.92
  5130.4  120.99  5163.3  121.96  5294.1   124.8  5308.2  125.11  5473.8  127.11
#Mann= 9 ,-1 , 0
  4436.8     .07       0  4930.3      .1       0  4988.8    .035       0
  4994.6    .035       0  4998.6    .035       0  5009.6      .1       0
  5163.3     .07       0  5294.1     .12       0  5308.2     .07       0
Bank Sta=4994.6,4998.6
XS Rating Curve= 0 ,0
Exp/Cntr=0.3,0.1

Chan Stop Cuts=-1
Use User Specified Reach Order=0
Composite Channel Slope=5