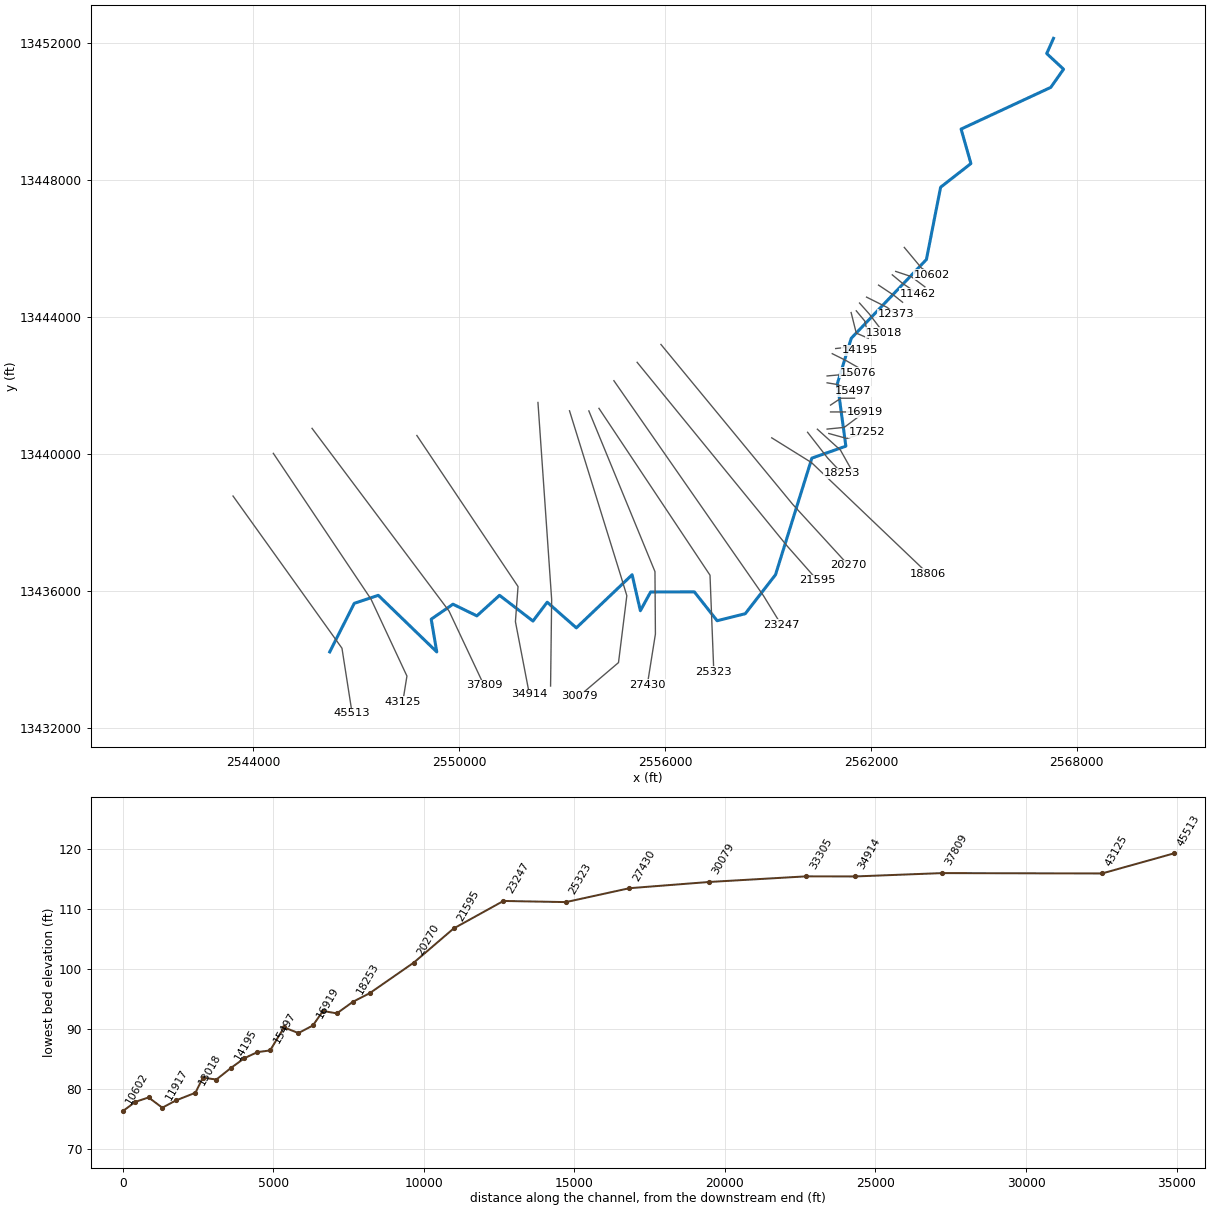
--- TRIB 3A TO COLETO CREEK.prj (project) ---

Proj Title=TRIB 3A TO COLETO CREEK Base Level Engineering
Current Plan=p01
Default Exp/Contr=0.3,0.1
English Units
Geom File=g01
Flow File=f01
Plan File=p01
Y Axis Title=Elevation
X Axis Title(PF)=Main Channel Distance
X Axis Title(XS)=Station
BEGIN DESCRIPTION:
TRIB 3A TO COLETO CREEK
END DESCRIPTION:
DSS Export Rating Curves= 0
DSS Export Rating Curve Sorted= 0
DSS Export Volume Flow Curves= 0
DXF OffsetX= 0
DXF OffsetY= 0
DXF ScaleX= 1
DXF ScaleY= 10

--- TRIB 3A TO COLETO CREEK.p01 (plan) ---

Plan Title=Multiple Run
Short Identifier=Multiple
Geom File=g01
Flow File=f01
Subcritical Flow
K Sum by GR= 0
Std Step Tol= 0.01
Critical Tol= 0.01
Num of Std Step Trials= 20
Max Error Tol= 0.3
Flow Tol Ratio= 0.001
Split Flow NTrial= 30
Split Flow Tol= 0.02
Split Flow Ratio= 0.02
Log Output Level= 0
Friction Slope Method= 1
Unsteady Friction Slope Method= 2
Unsteady Bridges Friction Slope Method= 1
Parabolic Critical Depth
Global Vel Dist=  1 , 1 , 1
Global Log Level= 0
CheckData=True
Encroach Param= -1, 0, 0, 0
BEGIN DESCRIPTION:
Multiple Run
END DESCRIPTION:

--- TRIB 3A TO COLETO CREEK.f01 (steady flow) ---

Flow Title=Multiple
Number of Profiles=7
Profile Names=10-year,25-year,50-year,1pct_min,100-year,1pct_plu,500-year
River Rch & RM= TRIB 3A TO COLET,Reach-1,45513
     568     868    1122     700    1396    2785    2138
River Rch & RM= TRIB 3A TO COLET,Reach-1,37809
     673    1033    1338     836    1667    3327    2561
River Rch & RM= TRIB 3A TO COLET,Reach-1,34914
     958    1490    1948    1225    2445    4878    3813
River Rch & RM= TRIB 3A TO COLET,Reach-1,30079
     966    1496    1950    1223    2440    4869    3781
River Rch & RM= TRIB 3A TO COLET,Reach-1,23247
    1085    1695    2222    1402    2797    5580    4383
River Rch & RM= TRIB 3A TO COLET,Reach-1,21595
    1271    2004    2644    1678    3348    6679    5310
River Rch & RM= TRIB 3A TO COLET,Reach-1,20270
    1464    2336    3108    1988    3967    7916    6399
River Rch & RM= TRIB 3A TO COLET,Reach-1,18253
    1676    2692    3599    2314    4618    9214    7521
River Rch & RM= TRIB 3A TO COLET,Reach-1,13712
    1898    3072    4128    2667    5322   10618    8753
River Rch & RM= TRIB 3A TO COLET,Reach-1,12373
    2069    3360    4527    2932    5850   11672    9666
River Rch & RM= TRIB 3A TO COLET,Reach-1,9672
    2329    3818    5178    3376    6736   13441   11282
River Rch & RM= TRIB 3A TO COLET,Reach-1,3497
    2635    4347    5920    3876    7734   15431   13056
Boundary for River Rch & Prof#=TRIB 3A TO COLET,Reach-1,1
Up Type=0
Dn Type=3
Dn Slope=0.005
Boundary for River Rch & Prof#=TRIB 3A TO COLET,Reach-1,2
Up Type=0
Dn Type=3
Dn Slope=0.005
Boundary for River Rch & Prof#=TRIB 3A TO COLET,Reach-1,3
Up Type=0
Dn Type=3
Dn Slope=0.005
Boundary for River Rch & Prof#=TRIB 3A TO COLET,Reach-1,4
Up Type=0
Dn Type=3
Dn Slope=0.005
Boundary for River Rch & Prof#=TRIB 3A TO COLET,Reach-1,5
Up Type=0
Dn Type=3
Dn Slope=0.005
Boundary for River Rch & Prof#=TRIB 3A TO COLET,Reach-1,6
Up Type=0
Dn Type=3
Dn Slope=0.005
Boundary for River Rch & Prof#=TRIB 3A TO COLET,Reach-1,7
Up Type=0
Dn Type=3
Dn Slope=0.005

--- TRIB 3A TO COLETO CREEK.g01 (geometry) ---

Geom Title=Existing Conditions
Program Version=4.10

River Reach=TRIB 3A TO COLET,Reach-1
Reach XY= 30
        2546225.       13434225.      2546941.13     13435642.08
      2547640.42     13435874.99      2549345.31     13434224.52
      2549182.88     13435178.62      2549817.99     13435616.01
       2550514.3      13435275.7        2551175.       13435875.
      2552149.92     13435124.37      2552564.36     13435674.45
       2553414.3      13434925.7      2555040.36     13436475.11
      2555281.05     13435426.59      2555581.12     13435973.24
      2556855.09     13435975.41      2557518.32     13435133.95
      2558338.41     13435338.34      2559221.18     13436476.58
      2560280.52     13439877.44      2561271.39      13440226.5
       2561024.6     13442054.87      2561428.45     13443373.75
      2563619.59     13445672.58      2564034.13     13447781.74
      2564917.17     13448471.77      2564630.73     13449477.55
      2567245.54     13450694.42      2567618.03     13451224.75
      2567126.61     13451681.03        2567325.       13452125.

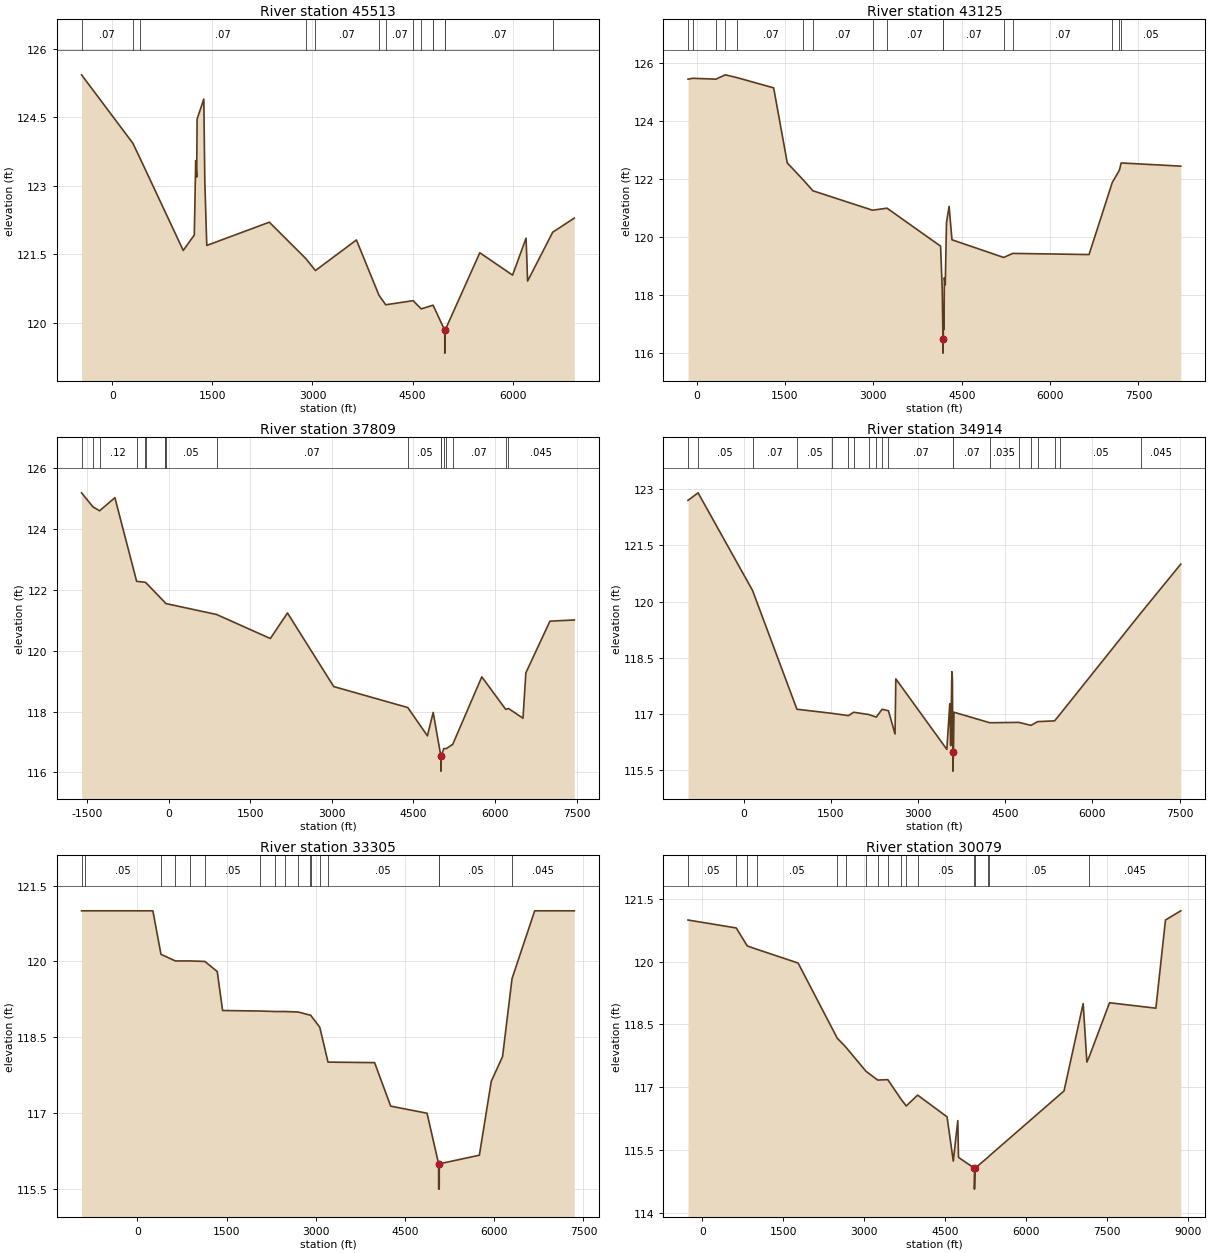
Type RM Length L Ch R = 1 ,45513   ,2388,2388,2388
BEGIN DESCRIPTION:
TRIB 3A TO COLETO CREEK 62.0
END DESCRIPTION:
XS GIS Cut Line= 3
      2543405.64     13438771.99      2546581.71     13434331.66
      2546878.24     13432430.95
#Sta/Elev= 30
  -459.3  125.43   309.7  123.93   414.2  123.61  1064.3  121.58  1230.1  121.92
    1251  123.55  1265.8  123.19  1271.9  124.46  1372.6   124.9  1387.4  123.09
  1416.9  121.69  2354.3   122.2  2902.6   121.4  3044.5  121.14  3659.1  121.81
  3996.9   120.6  4097.9  120.39  4508.6  120.48  4630.1   120.3  4805.9  120.38
  4807.5  120.38  4982.7  119.83    4983  119.33  4986.9  119.83  5507.8  121.53
  5998.6  121.04    6201  121.85  6223.9  120.91  6600.1  121.98  6923.7  122.29
#Mann= 14 ,-1 , 0
  -459.3     .07       0   309.7     .12       0   414.2     .07       0
  2902.6     .05       0  3044.5     .07       0  3996.9      .1       0
  4097.9     .07       0  4508.6    .035       0  4630.1     .07       0
  4805.9    .035       0  4807.5     .07       0  4982.7     .05       0
  4986.9     .07       0  6600.1     .05       0
Bank Sta=4982.7,4986.9
XS Rating Curve= 0 ,0
Exp/Cntr=0.3,0.1

Type RM Length L Ch R = 1 ,43125   ,5316,5316,5316
BEGIN DESCRIPTION:
Mapping XS b0b22f73
END DESCRIPTION:
XS GIS Cut Line= 4
      2544580.94     13440017.18      2547428.19     13435763.67
      2548475.61     13433519.19      2548353.01      13432761.2
#Sta/Elev= 30
  -145.3  125.43     -62  125.46   328.1  125.43   487.4  125.58   691.9  125.48
  1308.3  125.13  1539.4  122.54  1812.5  121.95  1974.5  121.58  2986.1  120.91
  3232.2  120.98  4141.3  119.67  4169.4  118.17  4181.7  116.48  4182.1  115.98
  4187.1  116.48  4190.5  117.34  4199.4   116.8  4205.5  118.58  4220.5  118.33
  4241.5  120.48  4285.7  121.04  4334.6  119.89  5212.3  119.28  5366.8  119.42
    6661  119.38    7056  121.87  7176.2  122.29  7206.4  122.54  8217.9  122.43
#Mann= 16 ,-1 , 0
  -145.3     .07       0     -62     .05       0   328.1     .07       0
   487.4     .05       0   691.9     .07       0  1812.5     .05       0
  1974.5     .07       0  2986.1     .05       0  3232.2     .07       0
  4181.7     .05       0  4187.1     .07       0  5212.3     .05       0
  5366.8     .07       0    7056     .05       0  7176.2     .07       0
  7206.4     .05       0
Bank Sta=4181.7,4187.1
XS Rating Curve= 0 ,0
Exp/Cntr=0.3,0.1

Type RM Length L Ch R = 1 ,37809   ,2895,2895,2895
BEGIN DESCRIPTION:
Mapping XS 89eafbc9
END DESCRIPTION:
XS GIS Cut Line= 3
      2545709.45     13440746.29      2549702.49     13435416.44
      2550722.92     13433249.38
#Sta/Elev= 30
 -1599.6  125.19 -1390.6  124.73 -1268.3   124.6  -986.8  125.03  -587.2  122.28
  -432.9  122.25  -419.9  122.24   -74.8   121.6   -71.7  121.59   -52.2  121.55
   881.4  121.19  1869.9   120.4  2184.5  121.24  3034.7  118.82  4395.7  118.13
  4755.8   117.2    4862  117.97  5002.6  116.54  5003.1  116.04    5009  116.54
  5056.4  116.78  5103.1  116.78  5221.1  116.92  5755.5  119.14  6195.2  118.07
  6244.7   118.1  6512.4  117.78  6564.9  119.27  7007.6  120.97  7455.4  121.01
#Mann= 18 ,-1 , 0
 -1599.6     .05       0 -1390.6     .07       0 -1268.3     .12       0
  -587.2     .07       0  -432.9     .12       0  -419.9     .07       0
   -74.8     .05       0   -71.7     .07       0   -52.2     .05       0
   881.4     .07       0  4395.7     .05       0  5002.6     .05       0
    5009     .05       0  5056.4     .07       0  5103.1     .05       0
  5221.1     .07       0  6195.2      .1       0  6244.7    .045       0
Bank Sta=5002.6,5009
XS Rating Curve= 0 ,0
Exp/Cntr=0.3,0.1

Type RM Length L Ch R = 1 ,34914   ,1609,1609,1609
BEGIN DESCRIPTION:
Mapping XS d85e7bdf
END DESCRIPTION:
XS GIS Cut Line= 4
      2548764.99     13440537.98      2551714.63     13436131.22
      2551638.24     13435106.91      2552044.49     13432992.35
#Sta/Elev= 30
  -961.3   122.7    -788   122.9   148.8   120.3   913.5  117.13  1520.8  117.02
  1801.3  116.96  1889.6  117.05  2147.7  116.99  2279.5  116.92  2380.7  117.13
  2488.9  117.09  2602.7  116.47  2616.2  117.94  3494.6  116.06  3545.5  117.28
  3560.5  116.16  3581.5  118.13  3590.5  117.93  3597.6  115.98  3598.1  115.48
  3608.3  115.98  3617.5  117.05  4234.8  116.77  4732.8  116.78  4942.1   116.7
  5057.5   116.8  5349.7  116.82  5449.4  117.01  6831.7  119.69  7521.9     121
#Mann= 20 ,-1 , 0
  -961.3     .07       0    -788     .05       0   148.8     .07       0
   913.5     .05       0  1520.8     .07       0  1801.3     .07       0
  1889.6     .05       0  2147.7     .07       0  2279.5     .05       0
  2380.7     .05       0  2488.9     .07       0  3597.6     .05       0
  3608.3     .07       0  4234.8    .035       0  4732.8      .1       0
  4942.1     .07       0  5057.5     .05       0  5349.7     .07       0
  5449.4     .05       0  6831.7    .045       0
Bank Sta=3597.6,3608.3
XS Rating Curve= 0 ,0
Exp/Cntr=0.3,0.1

Type RM Length L Ch R = 1 ,33305   ,3226,3226,3226
BEGIN DESCRIPTION:
Mapping XS 065fb335
END DESCRIPTION:
XS GIS Cut Line= 3
      2552295.23     13441501.49      2552694.54     13435754.99
      2552663.35     13433228.54
#Sta/Elev= 30
    -940     121    -875     121   259.4     121   395.7  120.14     637  120.01
     883  120.01  1133.6     120    1342   119.8  1432.1  119.03  2060.3  119.02
  2311.8  119.01  2480.8  119.01  2705.8     119  2896.6  118.94  2910.9  118.94
  3066.4   118.7  3204.7  118.01  3988.3     118    4259  117.14  4870.4     117
  5064.9     116  5065.4   115.5  5075.4   115.5  5075.9     116  5750.4  116.17
  5950.4  117.63  6140.4  118.12  6299.5  119.66  6680.5     121    7347     121
#Mann= 17 ,-1 , 0
    -940    .035       0    -875     .05       0   395.7     .07       0
     637     .05       0     883     .07       0  1133.6     .05       0
  2060.3     .12       0  2311.8     .05       0  2480.8     .12       0
  2705.8     .05       0  2896.6     .07       0  2910.9     .05       0
  3066.4     .07       0  3204.7     .05       0  5064.9     .05       0
  5075.9     .05       0  6299.5    .045       0
Bank Sta=5064.9,5075.9
XS Rating Curve= 0 ,0
Exp/Cntr=0.3,0.1

Type RM Length L Ch R = 1 ,30079   ,2649,2649,2649
BEGIN DESCRIPTION:
Mapping XS 3758fe31
END DESCRIPTION:
XS GIS Cut Line= 5
      2553215.37     13441258.44      2554703.69     13436463.24
      2554885.99     13435864.28       2554643.5      13433912.5
      2553489.86     13432930.08
#Sta/Elev= 30
    -265     121   628.2  120.81   832.9  120.38  1010.3   120.3  1774.9  119.97
  2500.9  118.17  2657.9  117.96  3032.5  117.38  3248.9  117.17  3435.8  117.18
  3688.6   116.7  3778.5  116.55  3988.5  116.81  4534.1  116.29  4649.3  115.23
  4733.1   116.2  4746.1  115.32    5041  115.06  5041.5  114.56  5052.5  115.06
  5298.4  115.33  5303.8  115.34  6701.3  116.91  7055.8     119  7124.5   117.6
  7168.5  117.73    7544  119.02  8402.8  118.89  8580.7     121    8864  121.22
#Mann= 17 ,-1 , 0
    -265     .05       0   628.2     .07       0   832.9    .035       0
  1010.3     .05       0  2500.9     .07       0  2657.9     .05       0
  3032.5     .07       0  3248.9     .05       0  3435.8     .07       0
  3688.6     .05       0  3778.5     .07       0  3988.5     .05       0
    5041     .05       0  5052.5     .05       0  5298.4     .07       0
  5303.8     .05       0  7168.5    .045       0
Bank Sta=5041,5052.5
XS Rating Curve= 0 ,0
Exp/Cntr=0.3,0.1

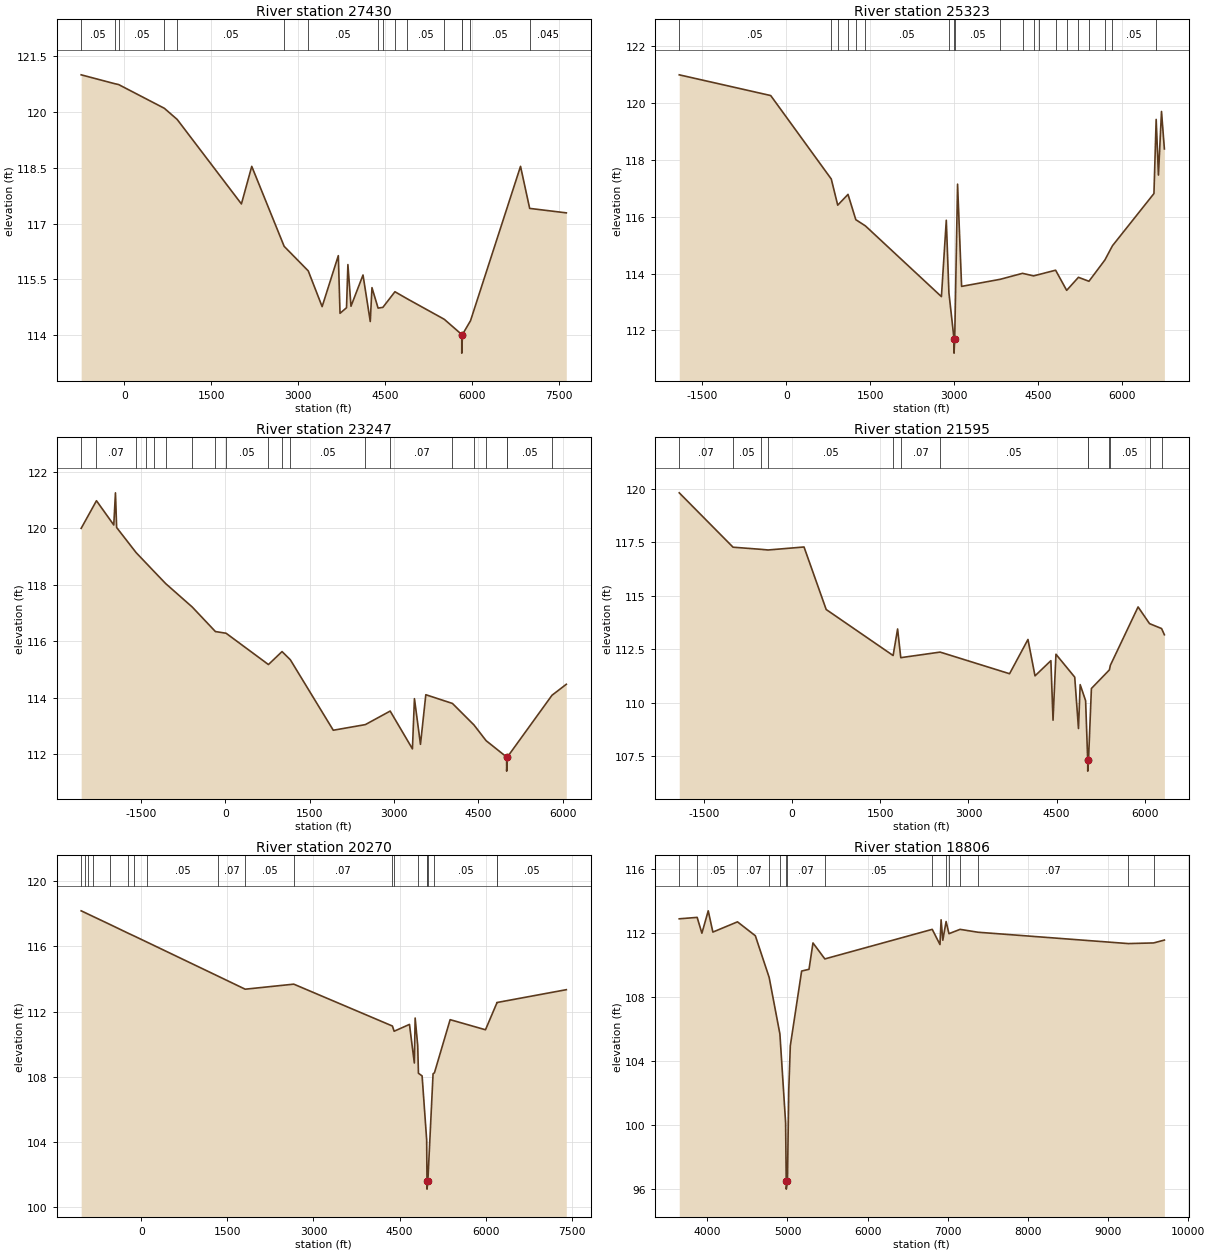
Type RM Length L Ch R = 1 ,27430   ,2107,2107,2107
BEGIN DESCRIPTION:
Mapping XS 64906c3f
END DESCRIPTION:
XS GIS Cut Line= 4
      2553779.21     13441254.91       2555706.3      13436567.4
      2555719.32     13434744.49      2555484.95     13433273.17
#Sta/Elev= 30
  -746.7     121  -162.9  120.76  -101.7  120.74   690.8   120.1   912.4   119.8
  2021.7  117.53  2200.2  118.54  2760.1  116.39  3176.4  115.73    3416  114.77
  3695.8  116.14  3725.2  114.59  3837.5  114.74  3861.2   115.9  3914.5  114.78
  4122.4  115.62  4247.6  114.37    4277  115.28  4382.7  114.73  4465.4  114.75
  4673.8  115.17  4886.2  114.98  5525.6  114.43    5828  114.02  5828.5  113.52
  5839.8  114.02  5979.1  114.39  6843.5  118.54  7001.3  117.41  7634.3  117.29
#Mann= 16 ,-1 , 0
  -746.7     .05       0  -162.9     .07       0  -101.7     .05       0
   690.8    .035       0   912.4     .05       0  2760.1    .035       0
  3176.4     .05       0  4382.7     .07       0  4465.4     .05       0
  4673.8     .07       0  4886.2     .05       0  5525.6     .07       0
    5828     .05       0  5839.8     .07       0  5979.1     .05       0
  7001.3    .045       0
Bank Sta=5828,5839.8
XS Rating Curve= 0 ,0
Exp/Cntr=0.3,0.1

Type RM Length L Ch R = 1 ,25323   ,2076,2076,2076
BEGIN DESCRIPTION:
Mapping XS 71c9da65
END DESCRIPTION:
XS GIS Cut Line= 3
      2554073.53     13441329.96      2557310.99     13436461.95
      2557422.04     13433638.68
#Sta/Elev= 30
 -1912.1     121    -277  120.27   805.5  117.33   920.5  116.41  1104.2  116.79
  1243.8   115.9  1415.7  115.68  2774.1  113.19  2861.3  115.88  2907.9  113.33
  2999.4   111.7  2999.9   111.2  3011.7   111.7  3062.7  117.15  3134.8  113.55
    3826   113.8  4223.5  114.01  4420.7  113.92    4521  113.97  4815.1  114.12
  5013.1  113.41  5223.4  113.87    5411  113.73  5696.1  114.48  5830.9  114.98
  6573.1  116.82  6612.8  119.43  6653.2  117.47    6708  119.71  6759.6  118.39
#Mann= 20 ,-1 , 0
 -1912.1     .05       0   805.5     .05       0   920.5    .035       0
  1104.2     .05       0  1243.8    .035       0  1415.7     .05       0
  2907.9     .07       0  2999.4     .05       0  3011.7     .05       0
    3826     .07       0  4223.5     .05       0  4420.7     .07       0
    4521     .05       0  4815.1     .07       0  5013.1     .05       0
  5223.4     .07       0    5411     .05       0  5696.1     .07       0
  5830.9     .05       0  6612.8    .045       0
Bank Sta=2999.4,3011.7
XS Rating Curve= 0 ,0
Exp/Cntr=0.3,0.1

Type RM Length L Ch R = 1 ,23247   ,1652,1652,1652
BEGIN DESCRIPTION:
Mapping XS cc6ae3f2
END DESCRIPTION:
XS GIS Cut Line= 3
      2554509.31     13442136.37      2558871.27     13435860.36
      2559384.61      13435023.3
#Sta/Elev= 30
 -2563.3     120 -2291.3  120.98 -1983.5  120.12 -1953.8  121.26 -1932.9  120.03
 -1586.6  119.14 -1419.4  118.79 -1276.5  118.49 -1060.4  118.04  -588.6  117.21
  -176.6  116.34    13.1  116.28   766.1  115.17  1007.8  115.63  1155.1  115.34
  1918.7  112.84  2488.9  113.04  2930.4  113.52  3325.9  112.18  3361.7  113.96
    3469  112.34  3563.9   114.1  4037.3  113.79    4419  113.03  4635.8  112.47
  5000.9  111.89  5001.4  111.39  5013.5  111.89  5806.9  114.08  6061.6  114.47
#Mann= 20 ,-1 , 0
 -2563.3     .05       0 -2291.3     .07       0 -1586.6     .05       0
 -1419.4    .035       0 -1276.5     .05       0 -1060.4     .07       0
  -588.6     .07       0  -176.6     .07       0    13.1     .05       0
   766.1     .05       0  1007.8    .035       0  1155.1     .05       0
  2488.9     .05       0  2930.4     .07       0  4037.3     .07       0
    4419     .07       0  4635.8     .05       0  5000.9     .05       0
  5013.5     .05       0  5806.9     .05       0
Bank Sta=5000.9,5013.5
XS Rating Curve= 0 ,0
Exp/Cntr=0.3,0.1

Type RM Length L Ch R = 1 ,21595   ,1325,1325,1325
BEGIN DESCRIPTION:
Mapping XS 544a5035
END DESCRIPTION:
XS GIS Cut Line= 3
      2555186.51     13442672.82      2559561.66      13437311.7
      2560443.53     13436311.56
#Sta/Elev= 30
 -1919.8   119.8 -1004.6  117.26  -526.5  117.16  -407.9  117.13   202.9  117.27
   579.8  114.35  1718.5   112.2  1794.7  113.44  1848.7   112.1  2517.9  112.36
  3699.5  111.35  4012.5  112.95  4132.4  111.25  4402.4  111.96    4439  109.18
  4488.6  112.26  4808.1  111.19    4872  108.79  4900.7  110.84  4993.3  110.09
    5029   107.3  5029.5   106.8  5042.2   107.3  5091.9  110.66    5398  111.53
  5413.8  111.74  5885.9  114.47  6080.8  113.69  6285.7  113.46  6333.4  113.17
#Mann= 13 ,-1 , 0
 -1919.8     .07       0 -1004.6     .05       0  -526.5    .035       0
  -407.9     .05       0  1718.5    .035       0  1848.7     .07       0
  2517.9     .05       0    5029     .05       0  5042.2     .05       0
    5398    .035       0  5413.8     .05       0  6080.8    .035       0
  6285.7     .05       0
Bank Sta=5029,5042.2
XS Rating Curve= 0 ,0
Exp/Cntr=0.3,0.1

Type RM Length L Ch R = 1 ,20270   ,1464,1464,1464
BEGIN DESCRIPTION:
Mapping XS e7e4772e
END DESCRIPTION:
XS GIS Cut Line= 3
      2555880.99     13443193.61      2559725.37     13438525.18
      2561350.01     13436749.99
#Sta/Elev= 30
 -1047.6  118.18  -974.5  118.06  -927.8  117.98  -849.6  117.85  -549.9  117.35
  -225.2   116.8  -127.6  116.64      99  116.26  1343.7  114.16  1810.7  113.37
  2657.1  113.68  4376.3  111.11  4406.2  110.79  4673.4  111.21  4758.1  108.84
  4772.4   111.6  4817.2  109.91  4829.8  108.21  4893.6  108.05  4973.1  104.12
  4978.6   101.6  4979.1   101.1  4993.8   101.6  5084.6  108.18  5108.6  108.24
  5381.9   111.5  5997.9  110.88  6194.6  112.51  6194.8  112.55  7406.4  113.34
#Mann= 20 ,-1 , 0
 -1047.6     .07       0  -974.5     .12       0  -927.8     .07       0
  -849.6     .05       0  -549.9     .07       0  -225.2    .035       0
  -127.6     .07       0      99     .05       0  1343.7     .07       0
  1810.7     .05       0  2657.1     .07       0  4376.3     .05       0
  4406.2     .07       0  4817.2     .05       0  4973.1     .07       0
  4978.6     .05       0  4993.8     .07       0  5108.6     .05       0
  6194.6    .035       0  6194.8     .05       0
Bank Sta=4978.6,4993.8
XS Rating Curve= 0 ,0
Exp/Cntr=0.3,0.1

Type RM Length L Ch R = 1 ,18806   ,553,553,553
BEGIN DESCRIPTION:
Mapping XS 9ae5457f
END DESCRIPTION:
XS GIS Cut Line= 3
      2559110.73     13440469.67      2560270.41     13439747.46
      2563660.03     13436511.55
#Sta/Elev= 30
  3650.2  112.91  3873.6     113  3932.7  112.01  4011.8  113.41  4069.6  112.08
  4376.6  112.72  4599.5  111.85    4772  109.24  4905.9   105.7  4977.2  100.14
  4984.8   96.49  4985.3   95.99  5000.2   96.49  5016.1  102.13  5035.7  104.96
  5176.9  109.64    5269  109.75  5318.4   111.4  5466.6   110.4  6806.3  112.25
  6902.9   111.3  6916.8  112.85  6938.2  111.57  6979.2  112.74  7015.1  111.98
  7153.9  112.25  7377.3  112.07  9251.6  111.36  9568.5   111.4  9702.6  111.58
#Mann= 15 ,-1 , 0
  3650.2     .07       0  3873.6     .05       0  4376.6     .07       0
    4772     .05       0  4905.9     .07       0  4984.8     .05       0
  5000.2     .07       0  5466.6     .05       0  6806.3    .035       0
  6979.2     .07       0  7015.1    .035       0  7153.9     .05       0
  7377.3     .07       0  9251.6    .035       0  9568.5     .07       0
Bank Sta=4984.8,5000.2
XS Rating Curve= 0 ,0
Exp/Cntr=0.3,0.1

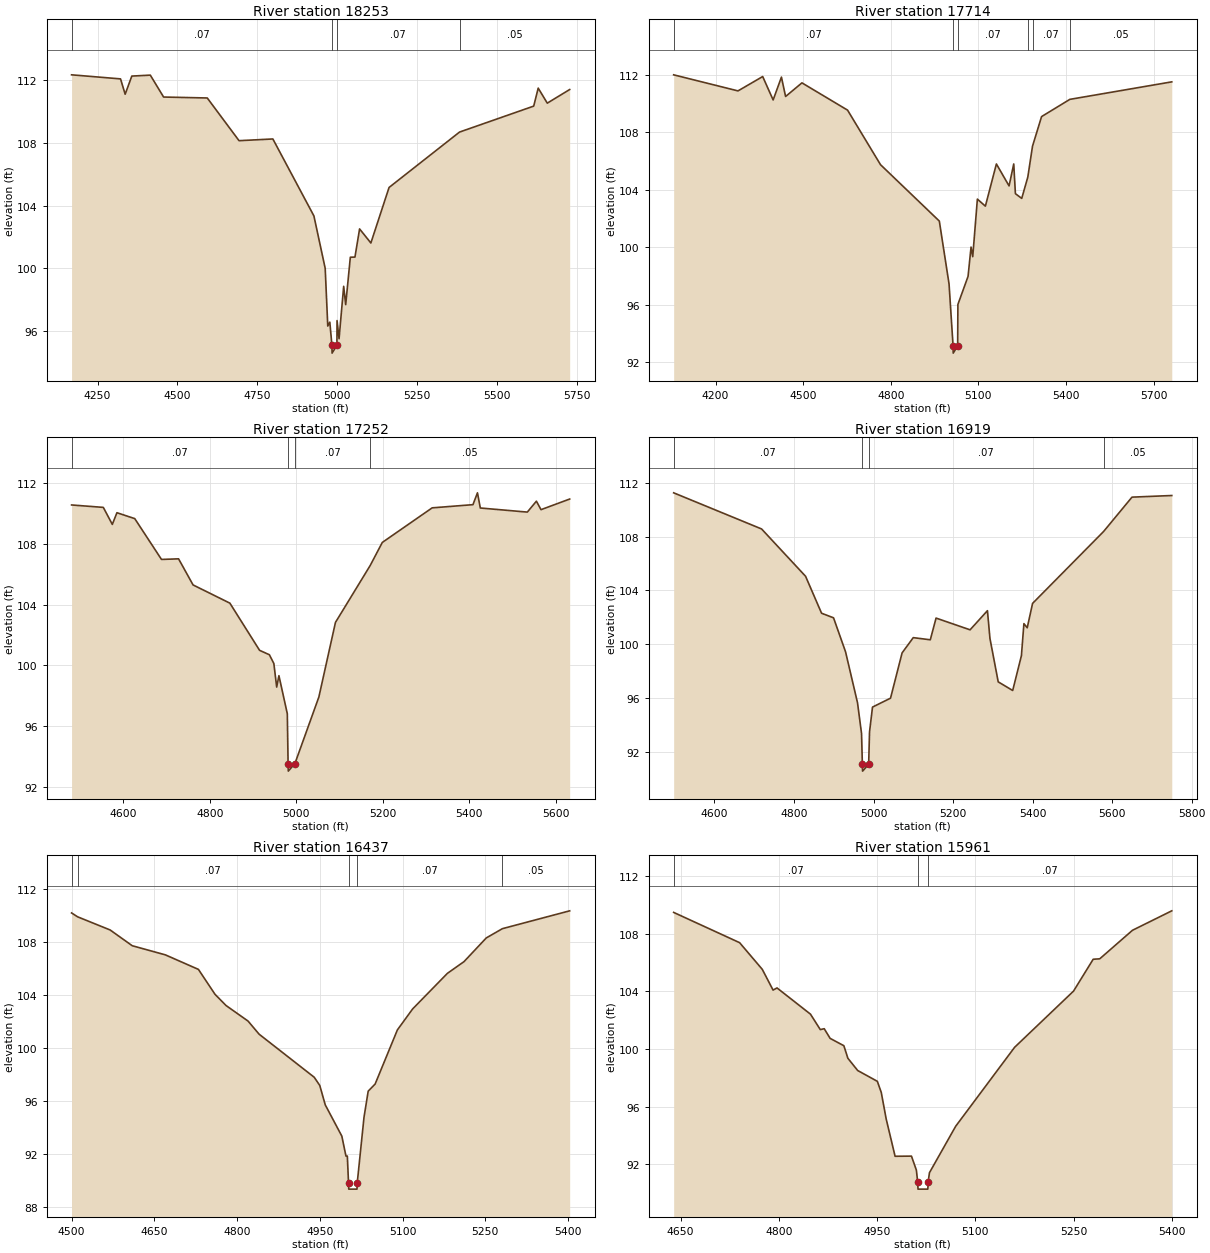
Type RM Length L Ch R = 1 ,18253   ,539,539,539
BEGIN DESCRIPTION:
Mapping XS 317e5e4a
END DESCRIPTION:
XS GIS Cut Line= 3
      2560156.15     13440631.38       2560739.5     13439881.35
      2561156.17      13439436.9
#Sta/Elev= 30
  4168.5  112.36  4321.8   112.1  4336.3  111.12  4357.1  112.28    4415  112.34
  4456.6  110.94  4593.3  110.88  4692.8  108.15  4798.7  108.26  4927.2  103.34
  4962.5   99.99  4970.6    96.3    4977   96.55  4983.6   95.07  4984.1   94.57
  4999.2   95.07  4999.6   96.65  5005.9   95.49  5020.4   98.84  5026.7   97.67
  5041.2   100.7  5055.7  100.71  5070.2  102.51  5105.5  101.61  5162.5  105.16
    5383   108.7  5615.3  110.36  5629.4  111.51  5657.8  110.55  5727.9  111.42
#Mann= 4 ,-1 , 0
  4168.5     .07       0  4983.6     .05       0  4999.2     .07       0
    5383     .05       0
Bank Sta=4983.6,4999.2
XS Rating Curve= 0 ,0
Exp/Cntr=0.3,0.1

Type RM Length L Ch R = 1 ,17714   ,462,462,462
BEGIN DESCRIPTION:
Mapping XS dade6720
END DESCRIPTION:
XS GIS Cut Line= 3
      2560440.86     13440721.66       2561114.5     13440110.52
       2561503.4     13439416.05
#Sta/Elev= 30
  4056.6  112.01  4276.9  110.89  4361.4  111.89  4397.2  110.26  4425.6  111.85
  4439.8   110.5  4495.8  111.45    4652  109.55  4764.8  105.75  4966.2  101.82
  4999.5   97.44  5013.3   93.12  5013.8   92.62    5029   93.12  5029.8   96.01
  5064.6   97.97  5074.8  100.01  5080.6   99.34  5096.5  103.35  5123.9  102.86
  5161.6   105.8    5205  104.27    5221   105.8  5226.7  103.73  5248.4   103.4
  5269.2  104.89  5285.3  107.04  5316.3   109.1  5413.1   110.3  5762.1  111.52
#Mann= 6 ,-1 , 0
  4056.6     .07       0  5013.3     .05       0    5029     .07       0
  5269.2     .05       0  5285.3     .07       0  5413.1     .05       0
Bank Sta=5013.3,5029
XS Rating Curve= 0 ,0
Exp/Cntr=0.3,0.1

Type RM Length L Ch R = 1 ,17252   ,333,333,333
BEGIN DESCRIPTION:
Mapping XS 4b6126cb
END DESCRIPTION:
XS GIS Cut Line= 3
       2560774.2     13440596.63        2561302.      13440450.8
      2561878.41     13440631.36
#Sta/Elev= 30
  4480.5  110.56  4553.9   110.4  4574.7  109.28  4585.4  110.05  4626.6  109.66
  4688.4  106.97  4727.9  107.01  4761.4  105.29  4846.5  104.09  4915.2  100.98
  4937.8  100.69  4948.2  100.11  4954.7   98.56  4959.9   99.31  4979.3    96.8
  4981.1   93.52  4981.6   93.02  4996.9   93.52  5052.2    97.9  5090.6  102.82
  5170.9  106.57  5198.9  108.09  5314.2  110.37  5408.5  110.58  5418.9  111.36
  5425.5  110.36  5534.2  110.09  5555.2  110.81  5565.8  110.25  5632.1  110.95
#Mann= 4 ,-1 , 0
  4480.5     .07       0  4981.1     .05       0  4996.9     .07       0
  5170.9     .05       0
Bank Sta=4981.1,4996.9
XS Rating Curve= 0 ,0
Exp/Cntr=0.3,0.1

Type RM Length L Ch R = 1 ,16919   ,482,482,482
BEGIN DESCRIPTION:
TRIB 3A TO COLETO CREEK 36.0
END DESCRIPTION:
XS GIS Cut Line= 3
      2560724.95       13440725.        2561225.       13440775.
      2561824.97     13441224.97
#Sta/Elev= 30
  4497.5  111.24  4718.6  108.56  4829.2  105.05  4869.4  102.31  4899.5  101.97
  4929.7   99.45  4959.8   95.67  4969.9   93.39    4972    91.1  4972.5    90.6
  4987.8    91.1    4990   93.51  4997.5   95.35  5042.8   96.01  5071.9   99.37
    5100   100.5  5142.8  100.34  5157.3  101.95  5242.8  101.08  5286.5   102.5
  5292.8  100.44  5313.6   97.22    5350   96.58  5371.9   99.16  5378.2  101.54
  5386.5  101.23    5400  103.04  5578.5  108.37    5650  110.92    5750  111.04
#Mann= 4 ,-1 , 0
  4497.5     .07       0    4972     .05       0  4987.8     .07       0
  5578.5     .05       0
Bank Sta=4972,4987.8
XS Rating Curve= 0 ,0
Exp/Cntr=0.3,0.1

Type RM Length L Ch R = 1 ,16437   ,476,476,476
BEGIN DESCRIPTION:
TRIB 3A TO COLETO CREEK 35.0
END DESCRIPTION:
XS GIS Cut Line= 3
      2560825.02       13441225.        2561325.       13441225.
      2561725.01       13441275.
#Sta/Elev= 30
    4500  110.22  4510.8  109.93    4570  108.93    4610  107.74    4670  107.05
    4730  105.95    4760  104.07    4780  103.22    4820  102.04    4840  101.05
    4940   97.79    4950   97.17    4960    95.7    4990   93.34  4997.5   91.83
    5000   91.83  5002.1   89.83  5002.6   89.33  5017.5   89.33    5018   89.83
  5030.2   94.76  5037.8   96.74  5050.4   97.28  5090.7  101.37  5118.4  102.96
  5181.4  105.65  5211.6  106.54  5251.9  108.33  5281.1  109.03  5403.1  110.38
#Mann= 5 ,-1 , 0
    4500     .05       0  4510.8     .07       0  5002.1     .05       0
    5018     .07       0  5281.1     .05       0
Bank Sta=5002.1,5018
XS Rating Curve= 0 ,0
Exp/Cntr=0.3,0.1

Type RM Length L Ch R = 1 ,15961   ,464,464,464
BEGIN DESCRIPTION:
TRIB 3A TO COLETO CREEK 34.0
END DESCRIPTION:
XS GIS Cut Line= 3
      2560824.96     13441424.97        2561125.       13441625.
        2561525.       13441625.
#Sta/Elev= 30
  4639.4  109.48  4740.1  107.38  4774.7  105.53  4791.2  104.09  4797.2  104.24
  4848.3  102.42  4863.3  101.35  4869.3  101.41  4878.3  100.74  4899.3  100.23
  4905.4   99.36  4920.4   98.51  4950.4   97.76  4956.4   96.99  4963.9   95.15
  4977.5   92.56  5002.5   92.57    5010    91.6    5012   90.78  5012.5   90.28
  5027.5   90.28    5028   90.78    5030   91.42    5070   94.64    5160  100.12
    5250  104.02    5280  106.23    5290  106.26    5340  108.24    5400  109.59
#Mann= 3 ,-1 , 0
  4639.4     .07       0    5012     .05       0    5028     .07       0
Bank Sta=5012,5028
XS Rating Curve= 0 ,0
Exp/Cntr=0.3,0.1

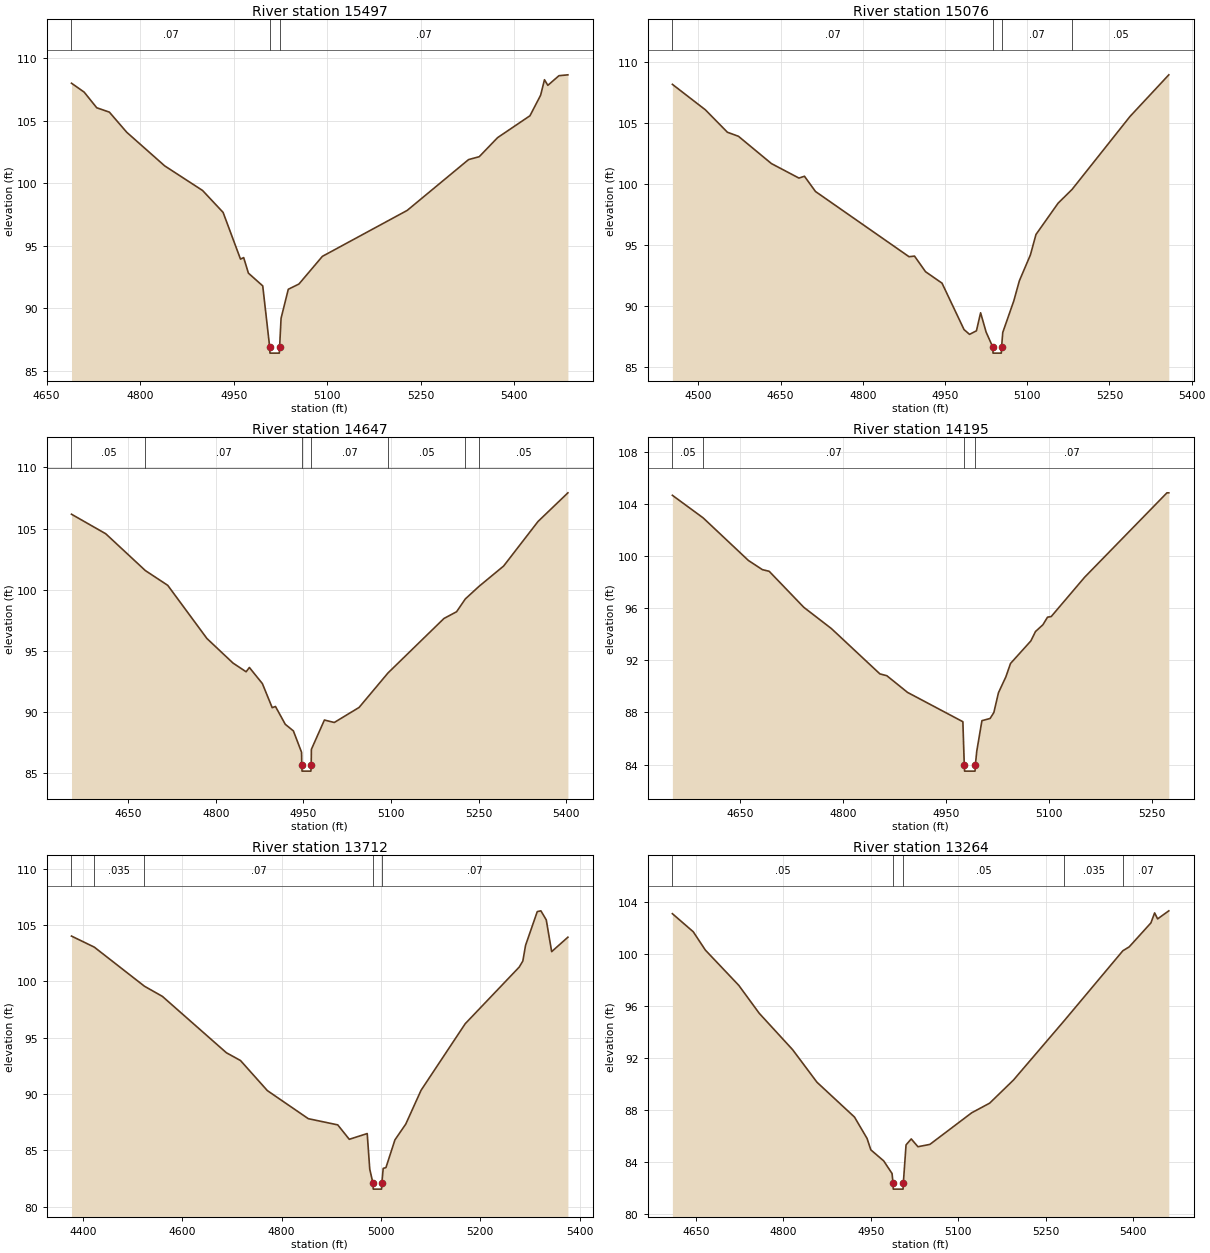
Type RM Length L Ch R = 1 ,15497   ,421,421,421
BEGIN DESCRIPTION:
TRIB 3A TO COLETO CREEK 33.0
END DESCRIPTION:
XS GIS Cut Line= 3
      2560725.01       13442075.        2561025.       13442025.
      2561475.02     13441824.99
#Sta/Elev= 30
  4689.8  107.99  4710.1  107.28  4730.3  106.03  4750.6  105.68  4778.5  104.07
  4839.3  101.39  4900.2   99.42  4933.1   97.67    4961   93.94  4966.1   94.06
  4973.7   92.82  4996.7    91.8  5007.8   86.93  5008.3   86.43  5023.3   86.43
  5023.8   86.93  5026.1   89.21  5037.7   91.53  5054.8   91.95  5092.4   94.16
  5228.5   97.83    5327  101.89  5344.1  102.12  5373.5  103.64  5425.5  105.39
  5442.6  107.03  5448.8  108.27  5454.2  107.82    5472  108.59  5486.4  108.66
#Mann= 3 ,-1 , 0
  4689.8     .07       0  5007.8     .05       0  5023.8     .07       0
Bank Sta=5007.8,5023.8
XS Rating Curve= 0 ,0
Exp/Cntr=0.3,0.1

Type RM Length L Ch R = 1 ,15076   ,429,429,429
BEGIN DESCRIPTION:
TRIB 3A TO COLETO CREEK 32.0
END DESCRIPTION:
XS GIS Cut Line= 3
      2560725.01       13442275.        2561275.       13442325.
      2561624.98       13442375.
#Sta/Elev= 30
  4452.5   108.2  4512.7  106.11  4552.9  104.27    4573  103.94  4633.2   101.7
  4683.4  100.51  4693.5  100.66  4713.6   99.41  4884.3   94.06  4894.3   94.11
  4914.4   92.83  4944.5   91.89  4984.7   88.08  4994.7   87.69  5007.3   87.98
  5014.9   89.46    5025   87.87  5037.1   86.65  5037.6   86.15  5052.7   86.15
  5053.2   86.65  5055.3   87.84  5075.5   90.44  5085.6   92.08  5105.8   94.21
  5115.9   95.88  5156.3   98.45  5181.8   99.58  5287.6  105.57  5358.3  108.98
#Mann= 4 ,-1 , 0
  4452.5     .07       0  5037.1     .05       0  5053.2     .07       0
  5181.8     .05       0
Bank Sta=5037.1,5053.2
XS Rating Curve= 0 ,0
Exp/Cntr=0.3,0.1

Type RM Length L Ch R = 1 ,14647   ,452,452,452
BEGIN DESCRIPTION:
TRIB 3A TO COLETO CREEK 31.0
END DESCRIPTION:
XS GIS Cut Line= 3
        2560875.       13442925.        2561275.       13442725.
      2561624.97     13442525.01
#Sta/Elev= 30
  4552.7  106.17  4611.4  104.57  4679.2  101.56  4717.6  100.35  4784.7      96
  4829.4   93.99  4851.8   93.28  4857.4   93.63  4879.7   92.31  4896.5   90.34
  4902.1   90.44  4918.9   88.98  4932.8   88.44  4946.8   86.69  4947.1   85.65
  4947.6   85.15  4962.8   85.15  4963.3   85.65  4963.6   86.93  4985.9   89.33
  5002.8   89.13  5045.3   90.36  5094.8   93.18  5190.7   97.64  5212.3   98.19
  5227.3   99.24  5250.8  100.27  5292.9  101.93  5351.9  105.58    5403  107.92
#Mann= 7 ,-1 , 0
  4552.7     .05       0  4679.2     .07       0  4947.1     .05       0
  4963.3     .07       0  5094.8     .05       0  5227.3     .07       0
  5250.8     .05       0
Bank Sta=4947.1,4963.3
XS Rating Curve= 0 ,0
Exp/Cntr=0.3,0.1

Type RM Length L Ch R = 1 ,14195   ,483,483,483
BEGIN DESCRIPTION:
TRIB 3A TO COLETO CREEK 30.0
END DESCRIPTION:
XS GIS Cut Line= 3
      2560975.04       13443075.        2561425.       13443125.
      2561675.02     13443024.99
#Sta/Elev= 30
  4552.1  104.66  4596.8  102.93  4662.7   99.66  4682.9   98.96  4692.9   98.83
  4743.2   96.07  4783.5   94.43  4853.9   90.96    4864   90.82  4894.1   89.54
  4974.6   87.29  4976.6      84  4977.1    83.5  4992.3    83.5  4992.8      84
  4994.8   85.03  5002.3   87.37  5014.2   87.54  5019.6   87.99  5026.4   89.52
  5037.1   90.73  5043.9   91.76  5073.5   93.49  5080.2   94.21    5091   94.73
  5097.7   95.31  5103.1   95.36  5151.6   98.37  5271.4  104.85  5274.1  104.85
#Mann= 4 ,-1 , 0
  4552.1     .05       0  4596.8     .07       0  4976.6     .05       0
  4992.8     .07       0
Bank Sta=4976.6,4992.8
XS Rating Curve= 0 ,0
Exp/Cntr=0.3,0.1

Type RM Length L Ch R = 1 ,13712   ,448,448,448
BEGIN DESCRIPTION:
TRIB 3A TO COLETO CREEK 29.0
END DESCRIPTION:
XS GIS Cut Line= 3
        2561425.     13444125.01        2561575.       13443525.
      2561925.04     13443374.98
#Sta/Elev= 30
  4377.2  104.02  4423.1  103.04  4524.1   99.57  4560.2   98.67    4689   93.67
  4717.4   92.98  4771.5   90.31  4853.9   87.82  4913.2   87.27  4936.4   85.99
  4972.5    86.5  4977.6   83.34  4984.2   82.07  4984.7   81.57  5001.4   81.57
  5001.9   82.07  5004.7   83.41  5010.2   83.48  5028.3   85.94  5050.1   87.34
  5080.9   90.34  5169.7   96.24  5278.5  101.27  5285.8  101.81  5291.2  103.19
  5314.8  106.19  5322.1  106.26  5332.9  105.46  5343.8  102.64  5376.5  103.92
#Mann= 5 ,-1 , 0
  4377.2     .05       0  4423.1    .035       0  4524.1     .07       0
  4984.2     .05       0  5001.9     .07       0
Bank Sta=4984.2,5001.9
XS Rating Curve= 0 ,0
Exp/Cntr=0.3,0.1

Type RM Length L Ch R = 1 ,13264   ,246,246,246
BEGIN DESCRIPTION:
TRIB 3A TO COLETO CREEK 28.0
END DESCRIPTION:
XS GIS Cut Line= 3
        2561575.       13444175.        2561825.       13443875.
        2561925.     13443424.99
#Sta/Elev= 30
  4609.5  103.07  4645.3  101.68  4666.1  100.27  4723.4   97.56  4758.5   95.41
  4815.8   92.61  4857.5   90.11  4921.9   87.43  4943.4   85.79  4949.9   84.91
    4972   84.06  4986.3   83.09  4987.9   82.39  4988.4   81.89  5005.2   81.89
  5005.7   82.39  5010.3   85.29  5019.2   85.75  5030.7   85.15  5051.2   85.33
  5122.9   87.76  5153.7    88.5  5194.6   90.28  5281.8   94.85  5382.2  100.22
  5393.1  100.52  5430.3  102.36  5436.7  103.13  5441.8  102.67    5461  103.29
#Mann= 5 ,-1 , 0
  4609.5     .05       0  4987.9     .05       0  5005.7     .05       0
  5281.8    .035       0  5382.2     .07       0
Bank Sta=4987.9,5005.7
XS Rating Curve= 0 ,0
Exp/Cntr=0.3,0.1

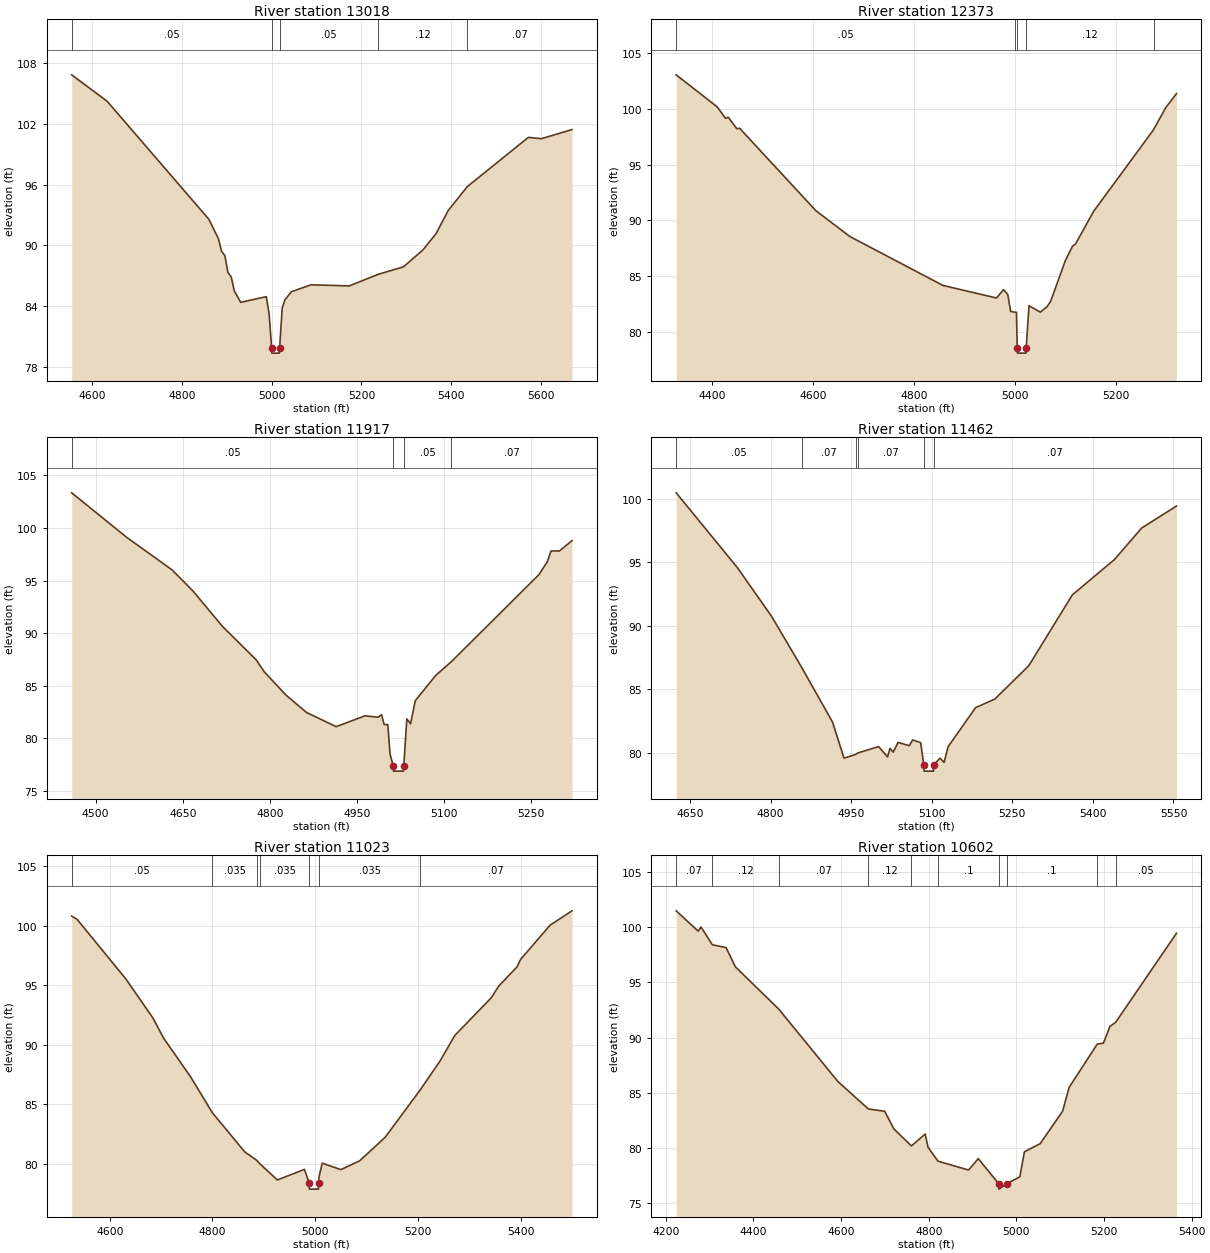
Type RM Length L Ch R = 1 ,13018   ,645,645,645
BEGIN DESCRIPTION:
Mapping XS 4b91098f
END DESCRIPTION:
XS GIS Cut Line= 3
      2561670.03     13444402.22      2561954.78     13444082.74
      2562370.74     13443535.06
#Sta/Elev= 30
  4553.7  106.82  4632.9  104.21  4859.5   92.58  4881.2   90.63  4887.9   89.43
  4895.4   88.98  4902.1   87.34  4909.7   86.86  4916.4   85.51  4930.6   84.38
  4987.7   84.94    4994   83.23  4999.6   79.87  5000.1   79.37  5016.9   79.37
  5017.4   79.87  5023.1   83.79  5029.3   84.64  5043.9   85.43  5087.5   86.11
  5172.8      86  5237.9   87.15  5293.5   87.88  5337.1   89.55  5366.2   91.15
  5393.3   93.43  5435.9   95.79  5572.1  100.65  5601.2  100.52  5669.4  101.42
#Mann= 5 ,-1 , 0
  4553.7     .05       0  4999.6     .05       0  5017.4     .05       0
  5237.9     .12       0  5435.9     .07       0
Bank Sta=4999.6,5017.4
XS Rating Curve= 0 ,0
Exp/Cntr=0.3,0.1

Type RM Length L Ch R = 1 ,12373   ,456,456,456
BEGIN DESCRIPTION:
TRIB 3A TO COLETO CREEK 26.0
END DESCRIPTION:
XS GIS Cut Line= 3
      2561875.04     13444574.98        2562475.       13444275.
      2562724.98     13444075.02
#Sta/Elev= 30
  4329.2  103.08  4410.2  100.21    4427   99.18  4432.6   99.26  4449.3   98.24
  4454.9   98.28  4605.9   90.88  4672.9   88.57  4857.4   84.17  4963.6   83.04
  4977.6   83.79    4986   83.35  4991.6   81.84  5000.6   81.76  5003.2   81.76
  5004.6   78.59  5005.1   78.09    5022   78.09  5022.5   78.59    5028   82.35
  5050.4   81.77    5064   82.27  5071.2   82.78    5100    86.4  5114.4   87.71
    5120   87.88    5156   90.82  5274.7   98.15  5298.5  100.11  5320.1   101.4
#Mann= 5 ,-1 , 0
  4329.2     .05       0  5000.6     .12       0  5004.6     .05       0
  5022.5     .12       0  5274.7     .07       0
Bank Sta=5004.6,5022.5
XS Rating Curve= 0 ,0
Exp/Cntr=0.3,0.1

Type RM Length L Ch R = 1 ,11917   ,455,455,455
BEGIN DESCRIPTION:
TRIB 3A TO COLETO CREEK 25.0
END DESCRIPTION:
XS GIS Cut Line= 3
        2562225.       13444925.        2562675.       13444625.
      2562925.01     13444424.99
#Sta/Elev= 30
  4458.9  103.34  4553.5   99.11  4631.7   96.01  4667.7      94  4718.8   90.61
  4775.9   87.49  4790.9   86.28    4827   84.14    4863   82.45  4914.1    81.1
  4963.7   82.13  4986.2      82  4992.2   82.24  4996.7    81.3  5002.9    81.3
  5006.9   78.47  5012.3   77.37  5012.8   76.87  5029.9   76.87  5030.4   77.37
  5035.7   81.83  5042.1   81.38  5050.2   83.57  5085.4   85.97  5112.1   87.27
  5263.1   95.56  5277.5   96.79  5283.9   97.81  5298.3   97.81  5319.9   98.79
#Mann= 4 ,-1 , 0
  4458.9     .05       0  5012.3     .05       0  5030.4     .05       0
  5112.1     .07       0
Bank Sta=5012.3,5030.4
XS Rating Curve= 0 ,0
Exp/Cntr=0.3,0.1

Type RM Length L Ch R = 1 ,11462   ,439,439,439
BEGIN DESCRIPTION:
TRIB 3A TO COLETO CREEK 24.0
END DESCRIPTION:
XS GIS Cut Line= 3
      2562625.01     13445224.99        2562925.       13444975.
      2563374.97     13444675.02
#Sta/Elev= 30
  4624.3  100.46  4738.2   94.58    4802   90.74  4857.7   86.75  4915.2   82.45
  4936.7    79.6  4958.2   79.89  4962.1      80  5001.1   80.51  5017.8    79.7
  5022.3   80.37  5028.3   80.07  5037.3   80.84  5058.4   80.58  5064.4   81.03
  5079.4   80.82  5085.2   79.08  5085.7   78.58  5103.2   78.58  5103.7   79.08
  5115.5    79.6    5123   79.26  5130.5    80.5  5181.6   83.57  5217.6   84.25
  5280.7   86.87  5361.8   92.44    5440   95.21    5491    97.7  5555.6   99.42
#Mann= 6 ,-1 , 0
  4624.3     .05       0  4857.7     .07       0  4958.2     .05       0
  4962.1     .07       0  5085.2     .05       0  5103.7     .07       0
Bank Sta=5085.2,5103.7
XS Rating Curve= 0 ,0
Exp/Cntr=0.3,0.1

Type RM Length L Ch R = 1 ,11023   ,421,421,421
BEGIN DESCRIPTION:
TRIB 3A TO COLETO CREEK 23.0
END DESCRIPTION:
XS GIS Cut Line= 3
        2562725.       13445325.        2563175.       13445175.
      2563574.96     13444875.03
#Sta/Elev= 30
  4525.9  100.79  4536.4  100.53  4631.3   95.52    4684   92.24  4705.1   90.53
  4757.8   87.27  4799.9   84.27  4863.2   80.97  4886.1   80.28  4892.2   79.99
  4926.5   78.62  4979.2   79.51  4988.4   78.35  4988.9   77.85  5006.4   77.85
  5006.9   78.35  5007.5   78.85  5013.8   80.03  5050.2   79.49  5086.7   80.23
  5136.7   82.22  5204.8    86.2    5243    88.6  5272.1   90.77    5343   93.93
  5357.5   94.91    5393   96.52  5400.2   97.16  5457.5  100.03  5500.2  101.24
#Mann= 7 ,-1 , 0
  4525.9     .05       0  4799.9    .035       0  4886.1     .05       0
  4892.2    .035       0  4988.4    .035       0  5006.9    .035       0
  5204.8     .07       0
Bank Sta=4988.4,5006.9
XS Rating Curve= 0 ,0
Exp/Cntr=0.3,0.1

Type RM Length L Ch R = 1 ,10602   ,615,615,615
BEGIN DESCRIPTION:
TRIB 3A TO COLETO CREEK 22.0
END DESCRIPTION:
XS GIS Cut Line= 3
      2562974.98     13446025.03        2563475.       13445425.
      2563774.99     13445225.01
#Sta/Elev= 30
  4223.8  101.48    4274   99.64  4280.5  100.02  4306.2   98.41  4337.7   98.15
  4358.6   96.42  4457.4    92.6  4592.9   86.02  4662.3   83.54  4699.6   83.33
  4720.4   81.74  4760.6   80.19    4792   81.27  4798.5   80.07  4821.2   78.81
    4891   78.01  4913.1   79.04  4959.7   76.78  4960.2   76.28  4978.4   76.78
  5007.9   77.39  5018.4   79.66  5054.4    80.4  5105.5   83.33  5120.5    85.5
  5184.6   89.41  5198.7    89.5  5213.7   91.02  5226.7   91.39  5365.4   99.45
#Mann= 10 ,-1 , 0
  4223.8     .07       0  4306.2     .12       0  4457.4     .07       0
  4662.3     .12       0  4760.6     .07       0  4821.2      .1       0
  4959.7     .05       0  4978.4      .1       0  5184.6     .12       0
  5226.7     .05       0
Bank Sta=4959.7,4978.4
XS Rating Curve= 0 ,0
Exp/Cntr=0.3,0.1