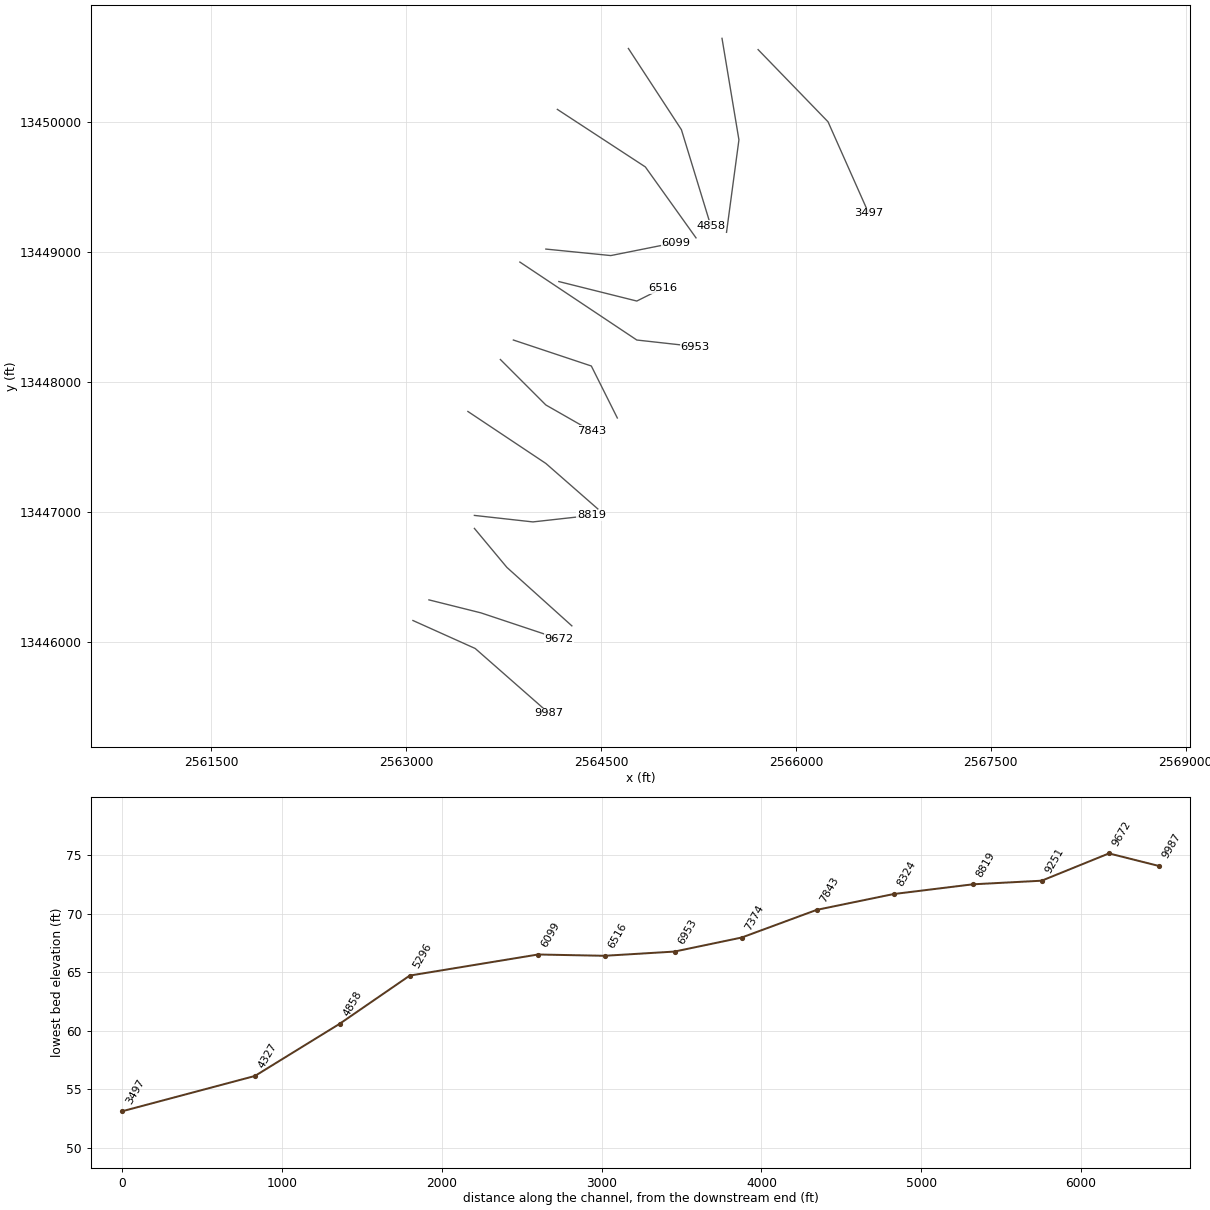
HEC-RAS study TRIB 3A TO COLETO CREEK.prj: TRIB 3A TO COLETO CREEK Base Level Engineering

--- TRIB 3A TO COLETO CREEK.g01 (geometry) --- (continued)

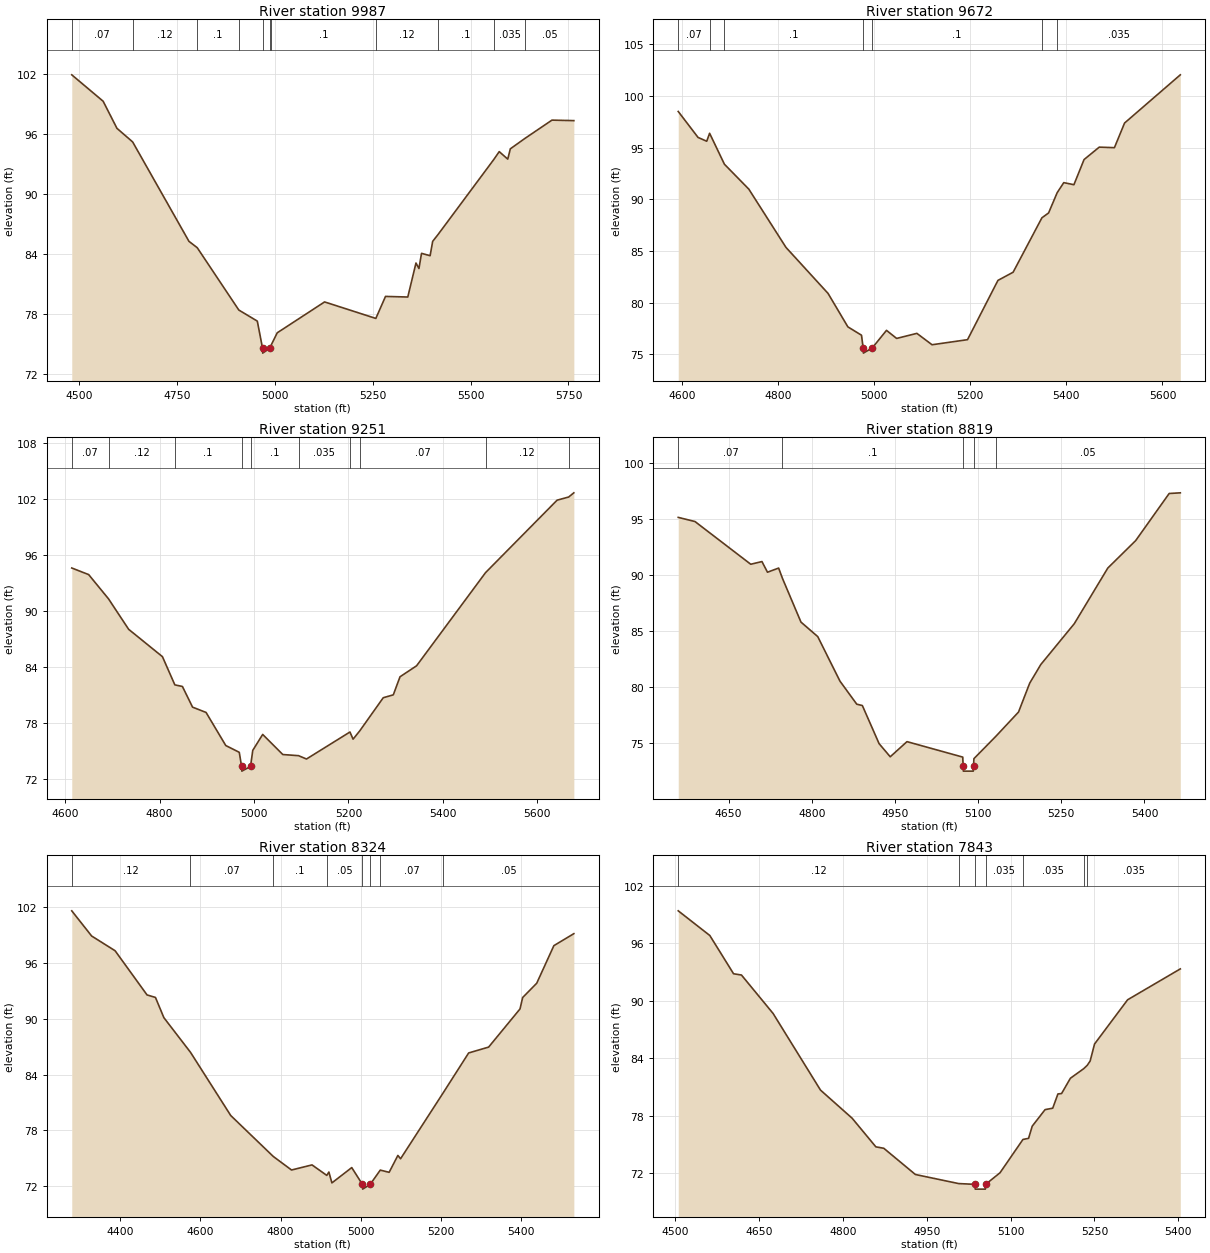
Type RM Length L Ch R = 1 ,9987    ,315,315,315
BEGIN DESCRIPTION:
Mapping XS 3e264ac8
END DESCRIPTION:
XS GIS Cut Line= 3
      2563051.98     13446166.08      2563531.17      13445950.8
      2564099.98     13445451.35
#Sta/Elev= 30
  4481.4  101.88  4561.5   99.24  4596.8   96.53  4636.9   95.17  4780.7   85.23
  4801.9   84.59    4908   78.36  4955.3   77.25  4968.6   74.55  4969.1   74.05
  4987.5   74.55  4990.5   74.84  5006.1   76.08  5127.1   79.17    5258   77.52
  5282.7   79.72  5339.6   79.66  5360.5   83.06  5368.1   82.51  5374.7   84.03
  5396.6   83.79  5403.2   85.23  5416.5   85.89  5559.4   93.42  5573.1    94.2
  5594.9   93.45  5601.5   94.48  5639.5   95.54  5707.8   97.35  5763.7    97.3
#Mann= 11 ,-1 , 0
  4481.4     .07       0  4636.9     .12       0  4801.9      .1       0
    4908     .07       0  4968.6     .05       0  4987.5     .07       0
  4990.5      .1       0    5258     .12       0  5416.5      .1       0
  5559.4    .035       0  5639.5     .05       0
Bank Sta=4968.6,4987.5
XS Rating Curve= 0 ,0
Exp/Cntr=0.3,0.1

Type RM Length L Ch R = 1 ,9672    ,421,421,421
BEGIN DESCRIPTION:
TRIB 3A TO COLETO CREEK 20.0
END DESCRIPTION:
XS GIS Cut Line= 3
      2563175.01       13446325.        2563575.       13446225.
      2564175.04     13446024.99
#Sta/Elev= 30
  4592.3   98.49  4633.5   95.98  4651.6   95.61  4657.6   96.38  4688.4   93.39
  4739.2   90.98  4816.5   85.35  4904.1    80.9  4945.3   77.67  4973.7   76.86
  4977.1   75.63  4977.6   75.13    4996   75.63  5025.7   77.33  5046.8   76.55
  5088.9   77.04  5120.5   75.94  5194.3   76.43  5257.6   82.16  5289.2   82.95
  5349.1   88.21    5363   88.68  5380.9   90.64  5394.6   91.61  5415.7   91.41
  5436.8   93.84  5468.4   95.04    5500   94.99  5521.1   97.37  5637.1  102.03
#Mann= 7 ,-1 , 0
  4592.3     .07       0  4657.6     .05       0  4688.4      .1       0
  4977.1     .05       0    4996      .1       0  5349.1     .12       0
  5380.9    .035       0
Bank Sta=4977.1,4996
XS Rating Curve= 0 ,0
Exp/Cntr=0.3,0.1

Type RM Length L Ch R = 1 ,9251    ,432,432,432
BEGIN DESCRIPTION:
TRIB 3A TO COLETO CREEK 19.0
END DESCRIPTION:
XS GIS Cut Line= 3
      2563525.01     13446874.99        2563775.       13446575.
      2564275.01     13446124.99
#Sta/Elev= 30
  4614.1   94.61  4649.9    93.9  4691.9    91.3  4734.5   88.03  4806.1   85.09
  4832.4   82.06  4848.4   81.89  4869.9   79.67  4898.5    79.1  4940.2   75.55
  4968.8   74.82  4973.7    73.3  4974.2    72.8  4992.6    73.3  4997.4   75.03
  5018.4   76.74    5061   74.58  5094.3   74.46  5111.1    74.1  5203.2      77
  5209.8   76.23  5224.2   77.14  5273.7   80.68    5295   80.99  5309.2   82.93
  5344.3   84.11  5490.3   94.11  5641.8  101.89  5666.3  102.23  5677.3  102.68
#Mann= 10 ,-1 , 0
  4614.1     .07       0  4691.9     .12       0  4832.4      .1       0
  4973.7     .05       0  4992.6      .1       0  5094.3    .035       0
  5203.2      .1       0  5224.2     .07       0  5490.3     .12       0
  5666.3    .035       0
Bank Sta=4973.7,4992.6
XS Rating Curve= 0 ,0
Exp/Cntr=0.3,0.1

Type RM Length L Ch R = 1 ,8819    ,495,495,495
BEGIN DESCRIPTION:
TRIB 3A TO COLETO CREEK 18.0
END DESCRIPTION:
XS GIS Cut Line= 3
      2563524.97       13446975.        2563975.       13446925.
      2564425.03       13446975.
#Sta/Elev= 30
  4559.1   95.12  4589.3   94.75  4689.9   90.94  4710.1   91.18  4720.1   90.23
  4740.2    90.6  4747.1   89.68  4780.5   85.78  4810.7   84.49  4850.9   80.51
  4881.1   78.46  4891.2   78.34  4921.4   74.94  4941.5   73.77  4971.7   75.12
  5072.3   73.74  5072.9   72.99  5073.4   72.49  5091.3   72.49  5091.8   72.99
  5092.4    73.6  5132.3   75.61  5172.9   77.76    5193   80.33  5213.1      82
  5273.5   85.64  5333.9    90.6  5384.2   93.05  5444.6   97.25  5464.7   97.31
#Mann= 5 ,-1 , 0
  4559.1     .07       0  4747.1      .1       0  5072.9     .05       0
  5091.8      .1       0  5132.3     .05       0
Bank Sta=5072.9,5091.8
XS Rating Curve= 0 ,0
Exp/Cntr=0.3,0.1

Type RM Length L Ch R = 1 ,8324    ,481,481,481
BEGIN DESCRIPTION:
TRIB 3A TO COLETO CREEK 17.0
END DESCRIPTION:
XS GIS Cut Line= 3
      2563475.03     13447774.98        2564075.       13447375.
      2564475.01     13447024.99
#Sta/Elev= 30
  4278.9  101.64  4328.4   98.93    4387   97.34  4466.7   92.58  4487.7   92.31
  4508.7   90.13  4575.1    86.4  4675.5   79.59  4781.6   75.18  4827.2   73.72
  4878.3   74.27  4915.1   73.14  4920.4    73.5  4927.9   72.33  4977.4   73.98
  5004.2   72.16  5004.7   71.66  5023.2   72.16  5048.6   73.71  5070.7   73.47
  5092.5   75.29  5099.2   74.93  5204.9   81.99  5269.1   86.33  5318.9   86.96
  5397.2   91.07  5403.8    92.3  5438.9   93.84  5481.7   97.89  5531.5   99.18
#Mann= 8 ,-1 , 0
  4278.9     .12       0  4575.1     .07       0  4781.6      .1       0
  4915.1     .05       0  5004.2     .05       0  5023.2     .05       0
  5048.6     .07       0  5204.9     .05       0
Bank Sta=5004.2,5023.2
XS Rating Curve= 0 ,0
Exp/Cntr=0.3,0.1

Type RM Length L Ch R = 1 ,7843    ,469,469,469
BEGIN DESCRIPTION:
TRIB 3A TO COLETO CREEK 16.0
END DESCRIPTION:
XS GIS Cut Line= 3
      2563725.01     13448174.99        2564075.       13447825.
      2564425.03     13447624.98
#Sta/Elev= 30
  4505.4    99.4  4561.9   96.82  4604.4   92.82  4618.5   92.69  4675.1   88.67
  4759.9   80.66  4816.5   77.72  4858.9   74.73  4873.1   74.58  4929.6   71.84
    5007   70.89  5036.2   70.81  5036.7   70.31  5054.8   70.31  5055.3   70.81
    5081   72.02    5122    75.5  5132.1   75.62  5138.6   76.89  5161.6   78.62
  5175.3   78.77  5184.6   80.26  5191.1    80.3  5206.9    81.9  5230.7    82.9
    5237   83.25  5242.2    83.7  5250.1   85.48  5309.2    90.1  5403.5   93.33
#Mann= 7 ,-1 , 0
  4505.4     .12       0    5007    .035       0  5036.2     .05       0
  5055.3    .035       0    5122    .035       0  5230.7     .05       0
    5237    .035       0
Bank Sta=5036.2,5055.3
XS Rating Curve= 0 ,0
Exp/Cntr=0.3,0.1

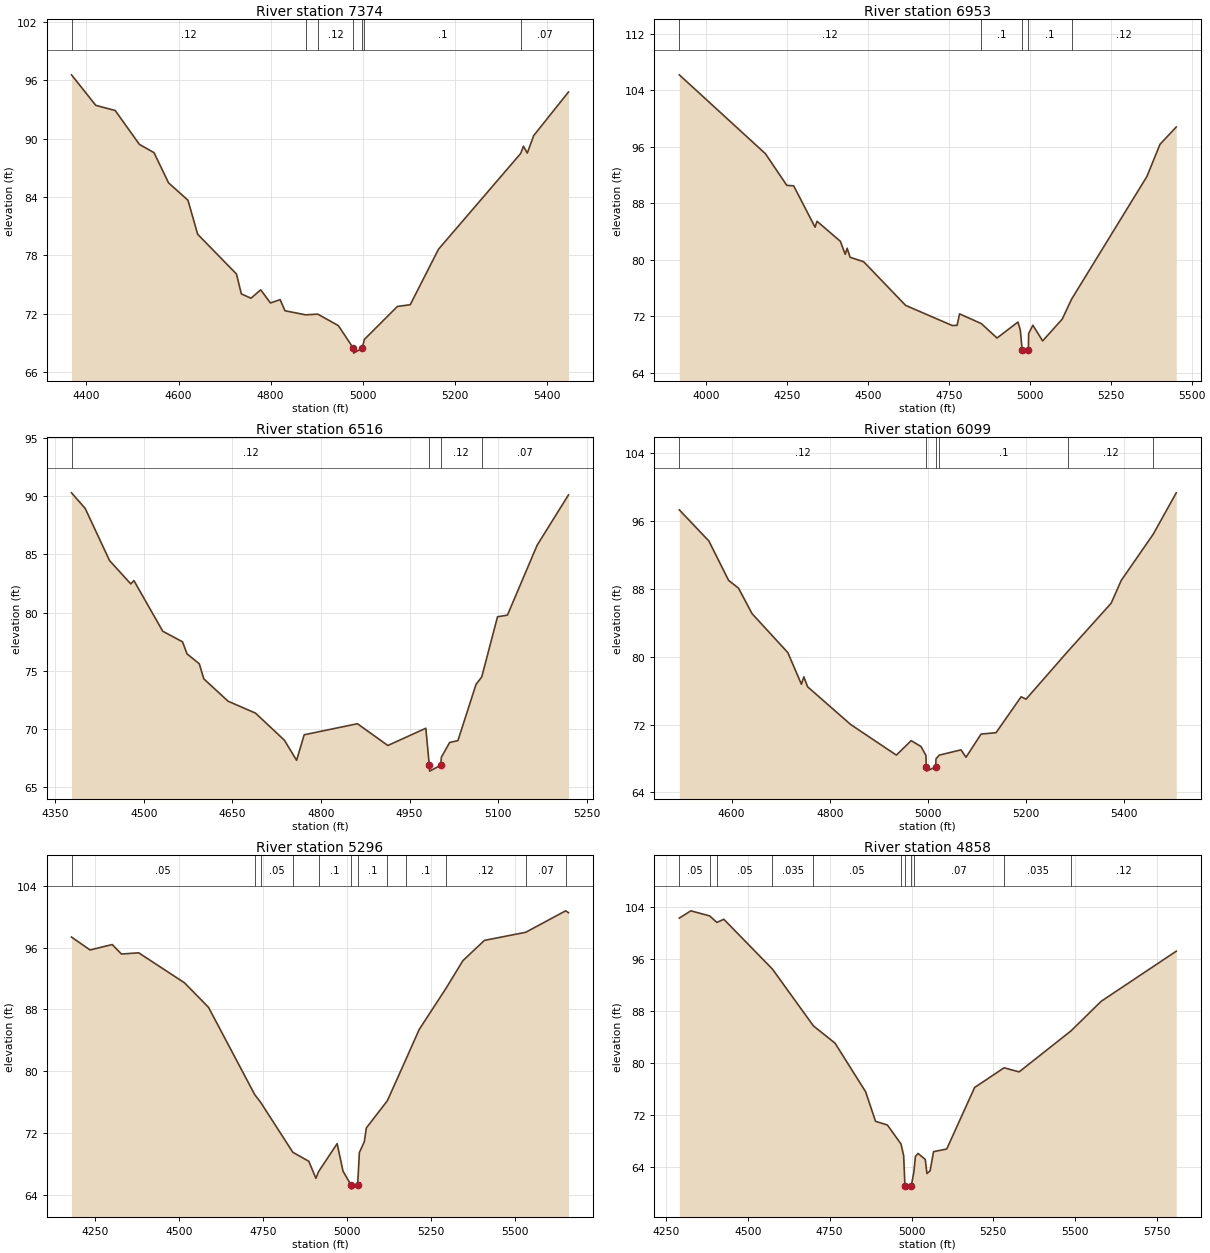
Type RM Length L Ch R = 1 ,7374    ,421,421,421
BEGIN DESCRIPTION:
TRIB 3A TO COLETO CREEK 15.0
END DESCRIPTION:
XS GIS Cut Line= 3
      2563824.97     13448325.01        2564425.       13448125.
        2564625.       13447725.
#Sta/Elev= 30
  4367.5   96.58  4420.2   93.44  4462.4   92.91  4515.1   89.42  4546.7   88.58
  4578.3   85.47  4620.5   83.68  4641.6   80.18  4725.9   76.09  4736.5   74.04
  4757.5    73.6  4778.6   74.46  4799.7   73.11  4820.8   73.45  4831.3   72.31
    4876   71.89  4902.6   71.96  4947.3   70.78  4979.9   68.45  4980.4   67.95
    4999   68.45  5003.8   69.36  5075.5   72.75  5103.4   72.93  5164.9   78.64
  5343.4   88.49  5349.4   89.24  5357.8   88.53  5371.7   90.33  5447.2   94.81
#Mann= 7 ,-1 , 0
  4367.5     .12       0    4876     .07       0  4902.6     .12       0
  4979.9     .05       0    4999     .12       0  5003.8      .1       0
  5343.4     .07       0
Bank Sta=4979.9,4999
XS Rating Curve= 0 ,0
Exp/Cntr=0.3,0.1

Type RM Length L Ch R = 1 ,6953    ,437,437,437
BEGIN DESCRIPTION:
TRIB 3A TO COLETO CREEK 14.0
END DESCRIPTION:
XS GIS Cut Line= 3
      2563874.98     13448925.01        2564775.       13448325.
      2565225.04       13448275.
#Sta/Elev= 30
    3918  106.17  4183.9      95    4250   90.51  4271.1   90.45  4337.2   84.59
  4343.2   85.43  4415.3   82.59  4430.3   80.75  4436.3   81.61  4445.3   80.33
  4487.4   79.69  4616.6   73.52  4760.8   70.66  4775.8   70.69  4783.4   72.31
  4850.7   70.93    4899   68.89  4963.6   71.15  4971.1      70  4976.6   67.25
  4977.1   66.75  4995.8   67.25  4996.7   69.52  5009.8    70.7  5039.9   68.48
  5100.3   71.56  5129.4    74.4  5361.9   91.77  5402.2   96.32  5452.5   98.78
#Mann= 5 ,-1 , 0
    3918     .12       0  4850.7      .1       0  4976.6     .05       0
  4995.8      .1       0  5129.4     .12       0
Bank Sta=4976.6,4995.8
XS Rating Curve= 0 ,0
Exp/Cntr=0.3,0.1

Type RM Length L Ch R = 1 ,6516    ,417,417,417
BEGIN DESCRIPTION:
TRIB 3A TO COLETO CREEK 13.0
END DESCRIPTION:
XS GIS Cut Line= 3
        2564175.       13448775.        2564775.       13448625.
      2564975.03     13448725.01
#Sta/Elev= 30
  4377.2   90.28  4400.4   88.94  4441.6   84.47  4477.7   82.46  4482.9   82.75
  4531.8    78.4  4565.3   77.49    4573   76.45  4593.7   75.61  4601.4   74.31
  4642.6   72.39    4689   71.37    4738   69.04  4758.6   67.32  4771.5   69.51
  4861.7   70.46  4913.2   68.59  4977.6   70.07  4983.5   66.89    4984   66.39
  5002.7   66.89    5004   67.59    5018   68.85    5032   69.01  5062.7   73.84
  5072.4   74.48  5099.1   79.64  5115.9   79.78  5166.2   85.78  5219.3    90.1
#Mann= 4 ,-1 , 0
  4377.2     .12       0  4983.5     .05       0  5002.7     .12       0
  5072.4     .07       0
Bank Sta=4983.5,5002.7
XS Rating Curve= 0 ,0
Exp/Cntr=0.3,0.1

Type RM Length L Ch R = 1 ,6099    ,803,803,803
BEGIN DESCRIPTION:
TRIB 3A TO COLETO CREEK 12.0
END DESCRIPTION:
XS GIS Cut Line= 3
      2564074.99       13449025.        2564575.       13448975.
        2565075.       13449075.
#Sta/Elev= 30
  4493.3   97.34  4553.6   93.66  4593.8   89.01  4613.9    88.1  4641.5   85.09
  4714.4   80.49    4742   76.76  4747.1   77.63  4754.6   76.46  4842.5      72
  4935.5   68.39  4965.7    70.1  4985.8    69.4  4995.8   68.35  4996.4      67
  4996.9    66.5  5015.7      67  5016.2   67.95  5022.9   68.39  5067.2   69.01
  5077.4   68.14    5108   70.87  5138.6   71.04  5189.6   75.27  5199.8      75
  5284.6   80.62  5373.1   86.32  5393.5      89  5458.7   94.46  5505.7   99.35
#Mann= 6 ,-1 , 0
  4493.3     .12       0  4996.4     .05       0  5015.7     .12       0
  5022.9      .1       0  5284.6     .12       0  5458.7     .07       0
Bank Sta=4996.4,5015.7
XS Rating Curve= 0 ,0
Exp/Cntr=0.3,0.1

Type RM Length L Ch R = 1 ,5296    ,438,438,438
BEGIN DESCRIPTION:
Mapping XS f26f1134
END DESCRIPTION:
XS GIS Cut Line= 3
       2564163.5      13450100.1      2564840.55     13449657.42
       2565230.6     13449111.34
#Sta/Elev= 30
  4178.9   97.36  4234.2   95.69  4300.2   96.39  4327.7   95.16    4379   95.32
  4515.2   91.44    4587   88.25  4724.5   76.95  4741.8   75.97  4838.1   69.47
  4885.6   68.31  4906.8    66.1  4914.6   66.96    4970   70.59  4987.5   67.03
  5011.7    65.2  5012.2    64.7  5031.1    65.2  5036.2   69.44  5050.9   70.83
    5057   72.63  5119.5   76.15  5175.2   81.55  5214.3   85.38  5294.7   90.75
  5344.6   94.31  5408.6   96.93  5531.7   97.98  5650.5  100.76  5658.9  100.52
#Mann= 12 ,-1 , 0
  4178.9     .05       0  4724.5    .035       0  4741.8     .05       0
  4838.1     .12       0  4914.6      .1       0  5011.7     .05       0
  5031.1      .1       0  5119.5     .07       0  5175.2      .1       0
  5294.7     .12       0  5531.7     .07       0  5650.5     .12       0
Bank Sta=5011.7,5031.1
XS Rating Curve= 0 ,0
Exp/Cntr=0.3,0.1

Type RM Length L Ch R = 1 ,4858    ,531,531,531
BEGIN DESCRIPTION:
Mapping XS 4b6ea2ac
END DESCRIPTION:
XS GIS Cut Line= 3
      2564710.32      13450568.9      2565118.33     13449943.87
      2565344.02     13449206.02
#Sta/Elev= 30
  4290.7  102.27    4326  103.39  4383.4  102.61  4405.4  101.61  4426.7  102.09
    4575   94.44  4700.4   85.69  4766.4   83.04  4859.9   75.56  4890.1   71.02
  4926.4   70.45  4967.9   67.53    4976   65.75  4979.9   61.09  4980.4   60.59
  4999.3   61.09  5007.2   63.23  5011.9   65.61  5019.9   66.08    5042   65.16
  5047.2   62.99  5056.8   63.41  5067.3   66.35  5107.6   66.76  5192.8   76.22
  5282.8   79.25  5328.7   78.62  5487.3   84.93  5579.7   89.49  5808.7   97.18
#Mann= 11 ,-1 , 0
  4290.7     .05       0  4383.4     .07       0  4405.4     .05       0
    4575    .035       0  4700.4     .05       0  4967.9     .12       0
  4979.9     .05       0  4999.3     .12       0  5007.2     .07       0
  5282.8    .035       0  5487.3     .12       0
Bank Sta=4979.9,4999.3
XS Rating Curve= 0 ,0
Exp/Cntr=0.3,0.1

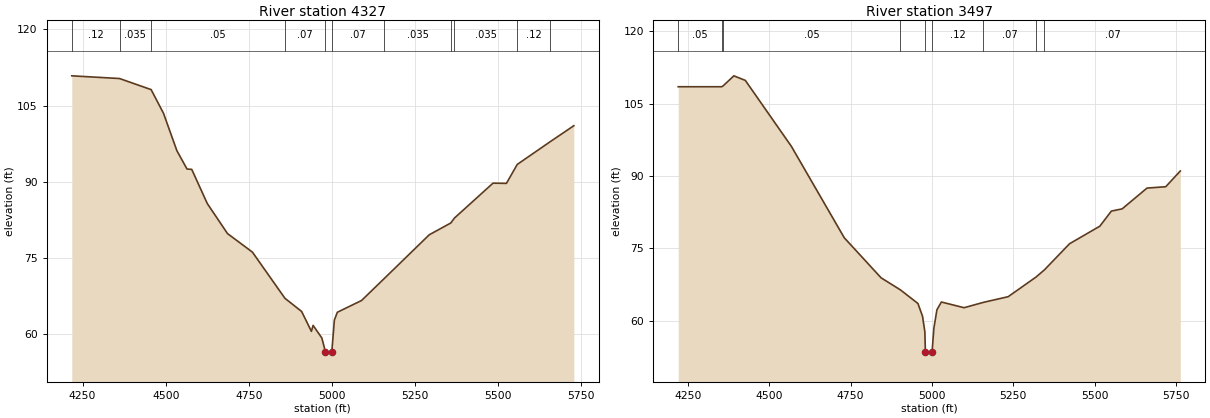
Type RM Length L Ch R = 1 ,4327    ,830,830,830
BEGIN DESCRIPTION:
Mapping XS 37034615
END DESCRIPTION:
XS GIS Cut Line= 3
      2565430.82     13450647.01      2565561.03     13449865.75
      2565465.55     13449153.96
#Sta/Elev= 30
  4217.5  110.86  4361.1  110.33  4456.2  108.15  4493.3  103.51  4533.8   96.12
  4564.2   92.53  4578.4   92.46  4625.1   85.75  4685.9   79.84  4760.9   76.19
  4858.7   67.11  4908.9   64.52  4938.3   60.61  4943.4   61.78  4969.7   59.31
  4980.3   56.63  4980.8   56.13  4999.7   56.63  5007.4   62.83  5016.3   64.36
  5089.2   66.68  5157.8   71.02  5292.8    79.6  5357.6   81.92  5368.6   82.89
  5484.5   89.75  5524.9   89.71  5557.4   93.43  5657.3   97.94  5727.7  101.05
#Mann= 11 ,-1 , 0
  4217.5     .12       0  4361.1    .035       0  4456.2     .05       0
  4858.7     .07       0  4980.3     .05       0  4999.7     .07       0
  5157.8    .035       0  5357.6     .12       0  5368.6    .035       0
  5557.4     .12       0  5657.3    .035       0
Bank Sta=4980.3,4999.7
XS Rating Curve= 0 ,0
Exp/Cntr=0.3,0.1

Type RM Length L Ch R = 1 ,3497    ,312,312,312
BEGIN DESCRIPTION:
Mapping XS 6ec29b47
END DESCRIPTION:
XS GIS Cut Line= 3
      2565708.57     13450560.23       2566246.8     13450004.64
       2566559.3      13449301.5
#Sta/Elev= 30
  4220.5  108.48  4354.3  108.48  4358.6  108.67  4391.5  110.74  4426.7  109.79
  4568.2   96.14  4730.8   77.21  4843.9   68.92  4903.4   66.42  4957.1   63.61
  4971.3   60.96  4978.5   57.73    4980   53.62  4980.5   53.12  5000.7   53.62
    5006   58.41  5015.5    62.3  5029.2   63.91    5099   62.73  5158.6   63.84
  5234.4   65.01  5320.1   69.08  5345.8   70.56  5423.2   75.98  5516.2   79.61
  5551.7   82.74  5584.6   83.19  5661.2    87.5  5718.7   87.78  5763.5   91.04
#Mann= 9 ,-1 , 0
  4220.5     .05       0  4354.3    .035       0  4358.6     .05       0
  4903.4     .12       0    4980     .05       0  5000.7     .12       0
  5158.6     .07       0  5320.1     .12       0  5345.8     .07       0
Bank Sta=4980,5000.7
XS Rating Curve= 0 ,0
Exp/Cntr=0.3,0.1