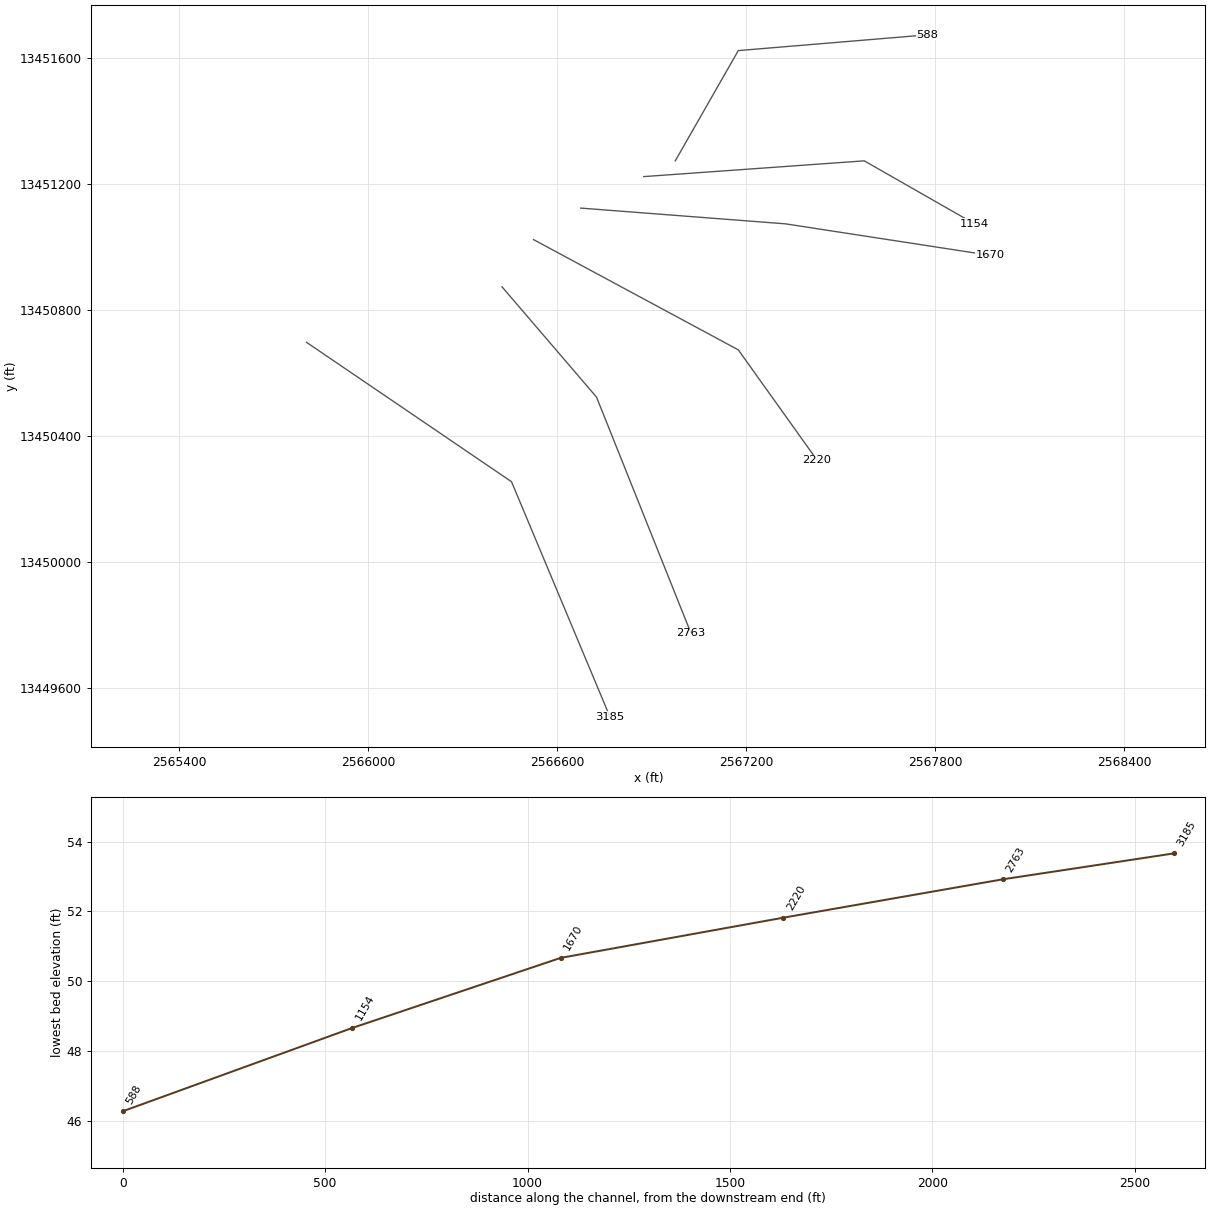
HEC-RAS study TRIB 3A TO COLETO CREEK.prj: TRIB 3A TO COLETO CREEK Base Level Engineering

--- TRIB 3A TO COLETO CREEK.g01 (geometry) --- (continued)

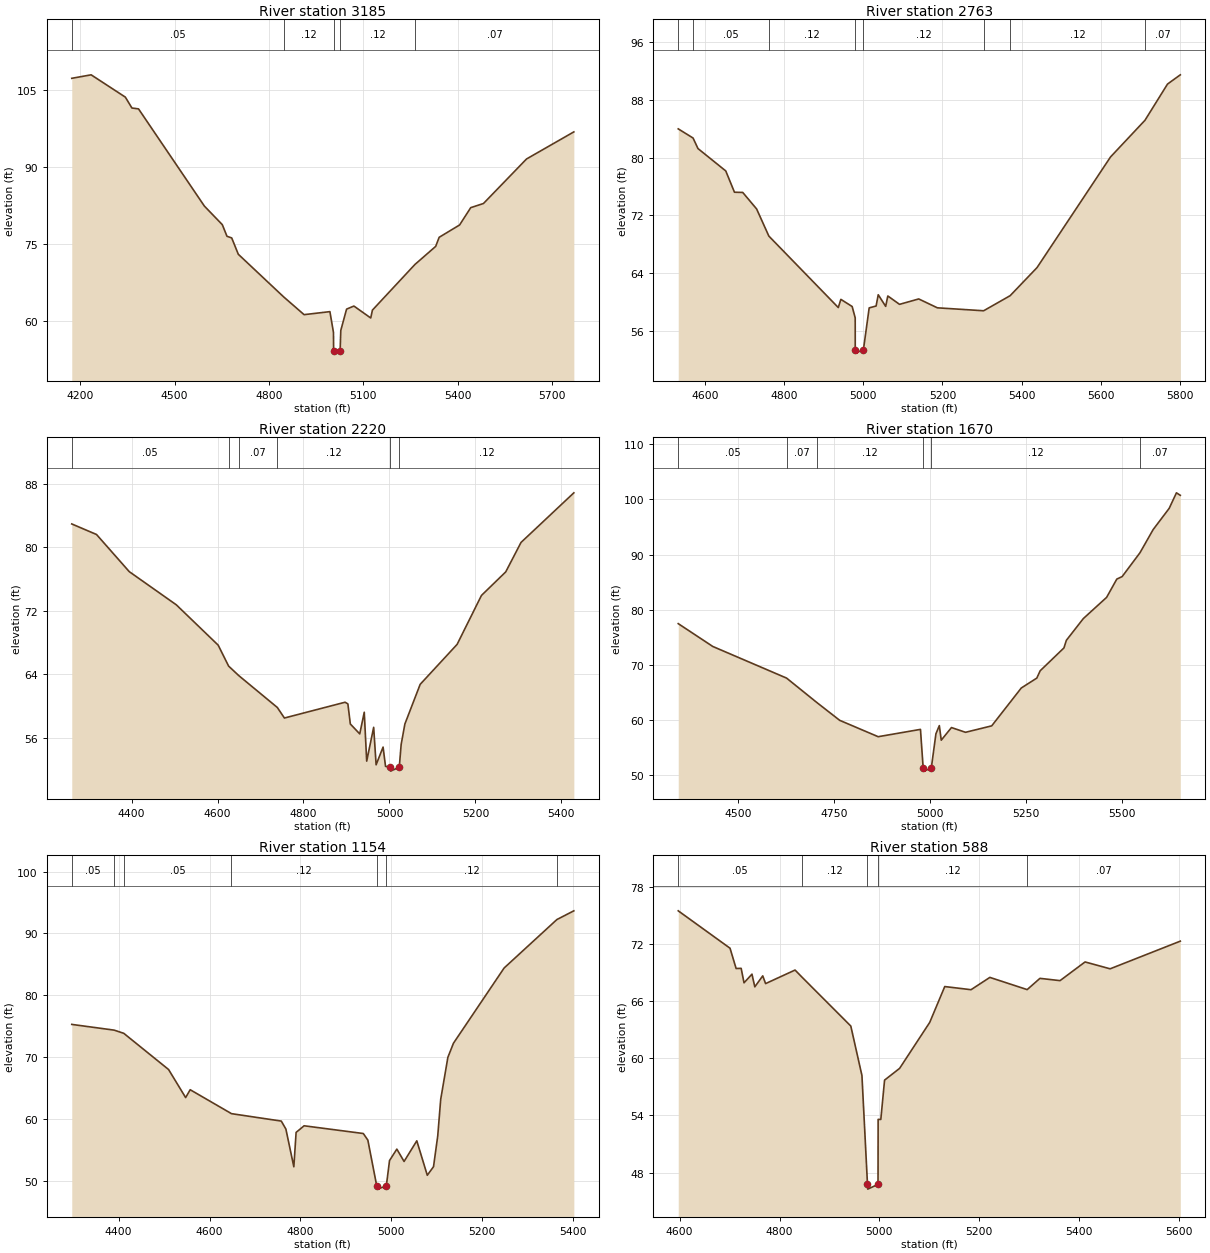
Type RM Length L Ch R = 1 ,3185    ,422,422,422
BEGIN DESCRIPTION:
Mapping XS c0765bd2
END DESCRIPTION:
XS GIS Cut Line= 3
      2565804.05     13450699.11      2566455.13     13450256.37
      2566767.61     13449509.89
#Sta/Elev= 30
  4173.3  107.31  4234.9  107.99  4343.6  103.64  4364.6  101.51  4385.6  101.34
  4595.1   82.36    4652   78.74  4666.9   76.47  4681.9   76.15  4702.9   72.96
  4846.9   64.65  4912.1   61.17  4994.2   61.76  5005.5    57.7    5006   54.16
  5006.5   53.66  5026.7   54.16  5028.8   58.09  5047.2   62.25  5070.5   62.85
    5124   60.52  5129.4   62.06  5264.6   70.97  5330.6    74.5  5341.6   76.27
  5406.6   78.68    5442   82.06  5482.5   82.87  5619.4   91.56  5769.9   96.85
#Mann= 5 ,-1 , 0
  4173.3     .05       0  4846.9     .12       0    5006     .05       0
  5026.7     .12       0  5264.6     .07       0
Bank Sta=5006,5026.7
XS Rating Curve= 0 ,0
Exp/Cntr=0.3,0.1

Type RM Length L Ch R = 1 ,2763    ,543,543,543
BEGIN DESCRIPTION:
TRIB 3A TO COLETO CREEK 5.0
END DESCRIPTION:
XS GIS Cut Line= 3
      2566425.02     13450874.97        2566725.       13450525.
      2567024.99     13449775.02
#Sta/Elev= 30
  4532.3      84  4569.8   82.73  4582.2   81.27  4652.4   78.17  4674.4   75.22
  4695.3   75.19  4730.4    72.9  4761.3   69.14  4936.7   59.24  4943.3   60.37
  4971.8   59.38  4979.5    57.8  4979.6   53.42  4980.1   52.92  5000.3   53.42
  5014.8   59.19  5032.3   59.45  5037.7   61.01  5056.5    59.4  5061.9   60.84
  5091.5   59.68    5140   60.43  5187.1    59.2    5304   58.79    5371   60.88
  5438.9   64.77  5624.7   80.11  5711.7   85.19  5768.7   90.21    5801   91.49
#Mann= 8 ,-1 , 0
  4532.3    .035       0  4569.8     .05       0  4761.3     .12       0
  4979.6     .05       0  5000.3     .12       0    5304     .07       0
    5371     .12       0  5711.7     .07       0
Bank Sta=4979.6,5000.3
XS Rating Curve= 0 ,0
Exp/Cntr=0.3,0.1

Type RM Length L Ch R = 1 ,2220    ,550,550,550
BEGIN DESCRIPTION:
TRIB 3A TO COLETO CREEK 4.0
END DESCRIPTION:
XS GIS Cut Line= 3
      2566525.03     13451024.98        2567175.       13450675.
      2567424.99     13450325.01
#Sta/Elev= 30
  4260.8   82.96  4318.4   81.63  4394.6   76.95  4504.1   72.77  4601.5   67.69
  4625.8   65.05  4649.3   63.86  4739.1   59.84  4755.6   58.51  4896.8    60.5
  4903.3   60.29    4909   57.76  4930.9   56.51  4941.4   59.24  4947.1   53.08
  4963.3   57.34    4969   52.62  4985.2   54.85  4990.9   52.42  5002.1   52.32
  5002.6   51.82  5022.9   52.32  5027.3   55.19  5035.9   57.75  5071.5   62.75
  5157.5   67.79  5214.1   73.95  5270.6   76.92  5306.2   80.63  5429.1   86.88
#Mann= 6 ,-1 , 0
  4260.8     .05       0  4625.8     .12       0  4649.3     .07       0
  4739.1     .12       0  5002.1     .05       0  5022.9     .12       0
Bank Sta=5002.1,5022.9
XS Rating Curve= 0 ,0
Exp/Cntr=0.3,0.1

Type RM Length L Ch R = 1 ,1670    ,516,516,516
BEGIN DESCRIPTION:
TRIB 3A TO COLETO CREEK 3.0
END DESCRIPTION:
XS GIS Cut Line= 3
      2566675.03       13451125.        2567325.       13451075.
      2567974.96     13450975.01
#Sta/Elev= 30
  4343.2   77.45  4433.4    73.3  4625.8   67.56  4705.4   63.09  4764.4   59.89
  4864.7   56.92    4975   58.25  4982.1   51.17  4982.6   50.67  5003.1   51.17
  5015.3   57.45  5024.2   58.93  5029.2   56.29  5055.8   58.58  5092.5   57.72
  5160.8   58.89  5237.9   65.76  5278.4   67.56  5287.2   68.89  5349.2   73.04
  5355.5   74.42  5399.8   78.37  5460.5   82.22  5487.1   85.54    5501   85.99
  5547.5   90.32  5581.9   94.53  5623.7   98.38  5642.6   101.2  5652.7  100.75
#Mann= 6 ,-1 , 0
  4343.2     .05       0  4625.8     .07       0  4705.4     .12       0
  4982.1     .05       0  5003.1     .12       0  5547.5     .07       0
Bank Sta=4982.1,5003.1
XS Rating Curve= 0 ,0
Exp/Cntr=0.3,0.1

Type RM Length L Ch R = 1 ,1154    ,566,566,566
BEGIN DESCRIPTION:
TRIB 3A TO COLETO CREEK 2.0
END DESCRIPTION:
XS GIS Cut Line= 3
      2566875.02       13451225.        2567575.       13451275.
      2567925.02     13451074.99
#Sta/Elev= 30
  4296.8   75.29  4390.3   74.36  4411.2   73.85  4509.8      68  4547.4   63.46
  4557.4   64.73  4648.3   60.86  4757.9   59.66    4768   58.37  4785.5   52.27
  4790.5   57.83  4808.1    58.9  4938.4   57.65  4948.4   56.58    4968   49.16
  4968.5   48.66    4989   49.16  4996.1   53.28  5012.2   55.13  5028.1   53.13
  5056.1   56.47  5079.2    50.9  5092.9   52.29  5102.2   57.27  5108.7   63.17
  5124.5   69.97  5136.8   72.25  5248.3   84.41  5364.4   92.24  5401.7   93.65
#Mann= 7 ,-1 , 0
  4296.8     .05       0  4390.3     .07       0  4411.2     .05       0
  4648.3     .12       0    4968     .05       0    4989     .12       0
  5364.4     .07       0
Bank Sta=4968,4989
XS Rating Curve= 0 ,0
Exp/Cntr=0.3,0.1

Type RM Length L Ch R = 1 ,588     ,0,0,0
BEGIN DESCRIPTION:
TRIB 3A TO COLETO CREEK 1.0
END DESCRIPTION:
XS GIS Cut Line= 3
        2566975.       13451275.        2567175.       13451625.
      2567775.01       13451675.
#Sta/Elev= 30
  4597.2   75.46  4700.9   71.54  4713.1   69.41  4723.2   69.43  4728.9   67.91
  4744.8   68.82  4750.5   67.49  4766.4   68.64  4772.1   67.83  4831.1   69.25
  4844.9   68.51  4942.7   63.38    4965   58.19  4976.1   46.78  4976.6   46.28
  4997.2   46.78  4997.4   53.59  5002.8   53.59  5010.3   57.71  5040.4   58.94
  5100.7   63.76  5130.8   67.52  5183.4   67.19  5221.1   68.48  5295.8    67.2
  5321.4   68.38  5361.6   68.14  5411.7    70.1  5461.9   69.38  5602.4   72.28
#Mann= 5 ,-1 , 0
  4597.2     .05       0  4844.9     .12       0  4976.1     .05       0
  4997.2     .12       0  5295.8     .07       0
Bank Sta=4976.1,4997.2
XS Rating Curve= 0 ,0
Exp/Cntr=0.3,0.1

Chan Stop Cuts=-1
Use User Specified Reach Order=0
Composite Channel Slope=5