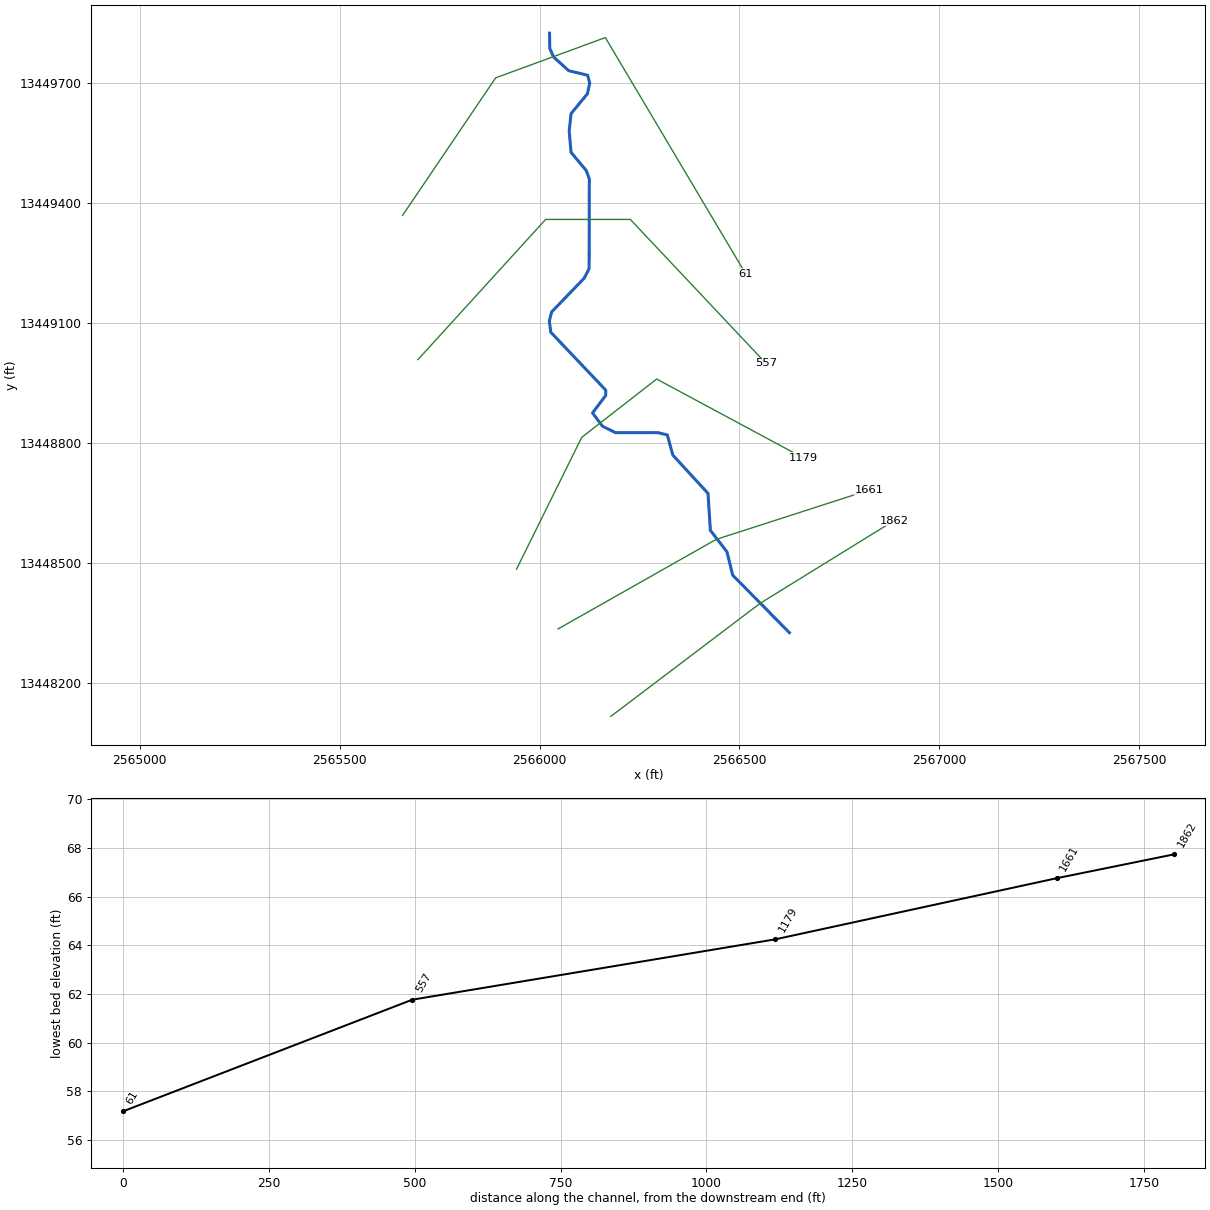
--- TRIB 3A_1 TO COLETO CREEK.prj (project) ---

Proj Title=TRIB 3A_1 TO COLETO CREEK Base Level Engineering
Current Plan=p01
Default Exp/Contr=0.3,0.1
English Units
Geom File=g01
Flow File=f01
Plan File=p01
Y Axis Title=Elevation
X Axis Title(PF)=Main Channel Distance
X Axis Title(XS)=Station
BEGIN DESCRIPTION:
TRIB 3A_1 TO COLETO CREEK
END DESCRIPTION:
DSS Export Rating Curves= 0
DSS Export Rating Curve Sorted= 0
DSS Export Volume Flow Curves= 0
DXF OffsetX= 0
DXF OffsetY= 0
DXF ScaleX= 1
DXF ScaleY= 10

--- TRIB 3A_1 TO COLETO CREEK.p01 (plan) ---

Plan Title=Multiple Run
Short Identifier=Multiple
Geom File=g01
Flow File=f01
Subcritical Flow
K Sum by GR= 0
Std Step Tol= 0.01
Critical Tol= 0.01
Num of Std Step Trials= 20
Max Error Tol= 0.3
Flow Tol Ratio= 0.001
Split Flow NTrial= 30
Split Flow Tol= 0.02
Split Flow Ratio= 0.02
Log Output Level= 0
Friction Slope Method= 1
Unsteady Friction Slope Method= 2
Unsteady Bridges Friction Slope Method= 1
Parabolic Critical Depth
Global Vel Dist=  1 , 1 , 1
Global Log Level= 0
CheckData=True
Encroach Param= -1, 0, 0, 0
BEGIN DESCRIPTION:
Multiple Run
END DESCRIPTION:

--- TRIB 3A_1 TO COLETO CREEK.f01 (steady flow) ---

Flow Title=Multiple
Number of Profiles=7
Profile Names=10-year,25-year,50-year,1pct_min,100-year,1pct_plu,500-year
River Rch & RM= TRIB 3A_1 TO COL,Reach-1,1862
     616     961    1262     802    1600    3192    2538
River Rch & RM= TRIB 3A_1 TO COL,Reach-1,1661
     671    1055    1392     888    1773    3537    2841
Boundary for River Rch & Prof#=TRIB 3A_1 TO COL,Reach-1,1
Up Type=0
Dn Type=3
Dn Slope=0.005
Boundary for River Rch & Prof#=TRIB 3A_1 TO COL,Reach-1,2
Up Type=0
Dn Type=3
Dn Slope=0.005
Boundary for River Rch & Prof#=TRIB 3A_1 TO COL,Reach-1,3
Up Type=0
Dn Type=3
Dn Slope=0.005
Boundary for River Rch & Prof#=TRIB 3A_1 TO COL,Reach-1,4
Up Type=0
Dn Type=3
Dn Slope=0.005
Boundary for River Rch & Prof#=TRIB 3A_1 TO COL,Reach-1,5
Up Type=0
Dn Type=3
Dn Slope=0.005
Boundary for River Rch & Prof#=TRIB 3A_1 TO COL,Reach-1,6
Up Type=0
Dn Type=3
Dn Slope=0.005
Boundary for River Rch & Prof#=TRIB 3A_1 TO COL,Reach-1,7
Up Type=0
Dn Type=3
Dn Slope=0.005

--- TRIB 3A_1 TO COLETO CREEK.g01 (geometry) ---

Geom Title=Existing Conditions
Program Version=4.10

River Reach=TRIB 3A_1 TO COL,Reach-1
Reach XY= 30
        2566625.       13448325.      2566483.13     13448468.94
      2566468.86     13448527.17      2566427.33     13448580.97
      2566421.38      13448673.5      2566333.32     13448769.31
      2566319.56     13448819.81      2566295.42     13448825.51
      2566189.91      13448825.4      2566157.38     13448841.43
      2566132.46     13448874.76      2566165.38     13448918.31
      2566165.69     13448931.66       2566028.1     13449076.65
      2566024.53     13449104.84      2566030.08     13449127.28
       2566111.6     13449211.69      2566123.94     13449235.44
      2566124.48     13449459.78      2566116.85     13449481.06
      2566078.71      13449526.6       2566074.2     13449580.03
      2566078.75     13449623.44      2566119.78     13449673.16
      2566125.53     13449700.13      2566120.24     13449719.41
        2566073.     13449730.86      2566035.41     13449764.78
      2566025.53     13449786.63        2566025.       13449825.

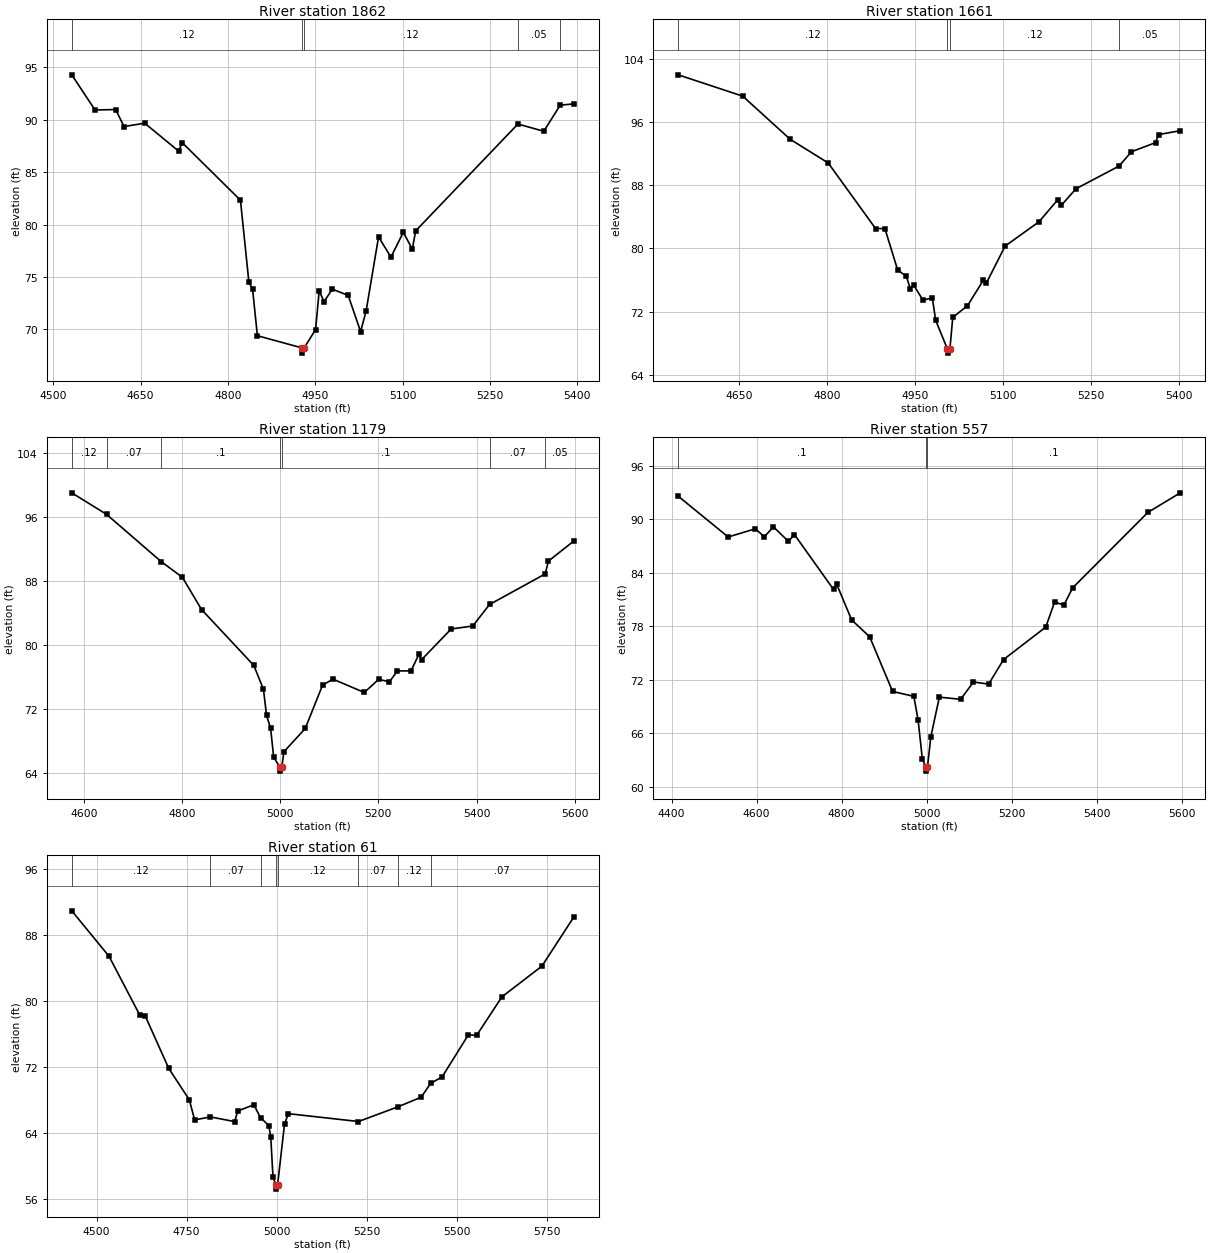
Type RM Length L Ch R = 1 ,1862    ,201,201,201
BEGIN DESCRIPTION:
TRIB 3A-1 TO COLETO CREEK 1.0
END DESCRIPTION:
XS GIS Cut Line= 3
      2566178.41     13448115.75      2566551.61     13448398.31
      2566886.72     13448605.33
#Sta/Elev= 30
  4531.9   94.27  4571.8   90.92  4607.2   90.96  4621.7   89.34  4657.1   89.66
  4715.3      87  4721.6    87.8  4821.5   82.32    4836    74.5  4842.3   73.84
  4850.6    69.4    4927   68.24  4927.2   67.74    4931   68.24  4950.5   69.99
  4956.7   73.69    4965   72.64  4979.2   73.84  5006.5   73.24  5027.8   69.79
  5037.3   71.77  5058.6   78.82  5079.9   76.89  5101.1   79.26  5116.5   77.65
  5122.4    79.4  5297.9   89.58  5342.3   88.89  5370.5   91.38  5393.9    91.5
#Mann= 5 ,-1 , 0
  4531.9     .12       0    4927     .05       0    4931     .12       0
  5297.9     .05       0  5370.5     .12       0
Bank Sta=4927,4931
XS Rating Curve= 0 ,0
Exp/Cntr=0.3,0.1

Type RM Length L Ch R = 1 ,1661    ,482,482,482
BEGIN DESCRIPTION:
TRIB 3A-1 TO COLETO CREEK 4.0
END DESCRIPTION:
XS GIS Cut Line= 3
      2566046.52     13448334.53      2566441.83      13448558.4
      2566824.24     13448681.73
#Sta/Elev= 30
  4545.7  101.97  4655.7   99.27  4736.5   93.82  4801.4   90.82  4882.2   82.52
  4898.1   82.52  4919.8   77.29  4934.7   76.46  4941.4    74.9  4947.1   75.38
    4963   73.46  4978.9   73.76  4984.7    70.9  5004.8   67.26  5005.1   66.76
  5008.9   67.26  5013.8   71.28  5038.9   72.76  5065.7   75.95    5071    75.6
    5103    80.3  5160.9   83.38  5192.5   86.14  5199.2   85.49    5224   87.56
  5297.4   90.43  5318.5   92.24  5359.5   93.39  5364.7   94.41  5401.8    94.9
#Mann= 4 ,-1 , 0
  4545.7     .12       0  5004.8     .05       0  5008.9     .12       0
  5297.4     .05       0
Bank Sta=5004.8,5008.9
XS Rating Curve= 0 ,0
Exp/Cntr=0.3,0.1

Type RM Length L Ch R = 1 ,1179    ,622,622,622
BEGIN DESCRIPTION:
TRIB 3A-1 TO COLETO CREEK 3.0
END DESCRIPTION:
XS GIS Cut Line= 4
      2565942.32     13448483.82      2566105.51     13448813.68
      2566293.01     13448959.51      2566660.49     13448761.91
#Sta/Elev= 30
  4575.5   99.04  4646.3   96.35  4757.9   90.43  4800.7   88.49  4839.9   84.45
  4946.4   77.46    4966   74.47  4972.3   71.22  4980.5   69.62  4986.8   66.01
  4999.2   64.75  4999.5   64.25  5003.4   64.75  5007.6   66.67  5051.1   69.58
  5086.3   74.99  5107.6   75.75  5171.4   74.08  5200.7   75.72  5222.7   75.42
  5238.9   76.78  5266.5   76.78  5282.7   78.85  5288.4    78.2  5348.4   82.02
  5392.3   82.39  5426.6   85.08  5539.9    88.9  5546.6   90.51  5598.3   93.02
#Mann= 7 ,-1 , 0
  4575.5     .12       0  4646.3     .07       0  4757.9      .1       0
  4999.2     .04       0  5003.4      .1       0  5426.6     .07       0
  5539.9     .05       0
Bank Sta=4999.2,5003.4
XS Rating Curve= 0 ,0
Exp/Cntr=0.3,0.1

Type RM Length L Ch R = 1 ,557     ,496,496,496
BEGIN DESCRIPTION:
TRIB 3A-1 TO COLETO CREEK 2.0
END DESCRIPTION:
XS GIS Cut Line= 4
       2565695.8     13449008.14      2566015.23     13449358.82
      2566227.04     13449358.82      2566566.26     13448998.83
#Sta/Elev= 30
  4415.8   92.58  4533.3   88.01  4597.2   88.93  4618.2   88.04  4639.8   89.14
  4674.9   87.52  4689.1   88.28    4781   82.13  4788.4   82.73  4823.6   78.72
  4866.1   76.82  4919.9    70.7  4969.9   70.15  4979.9    67.5  4989.9   63.14
  4997.8   62.27  4998.1   61.77    5002   62.27  5009.9   65.63  5029.9   70.06
  5079.9   69.82  5110.2   71.76  5145.8   71.52    5181   74.28  5280.1   77.91
  5301.1   80.74  5322.6   80.37  5343.6   82.32  5520.4   90.77  5596.6   92.96
#Mann= 3 ,-1 , 0
  4415.8      .1       0  4997.8     .04       0    5002      .1       0
Bank Sta=4997.8,5002
XS Rating Curve= 0 ,0
Exp/Cntr=0.3,0.1

Type RM Length L Ch R = 1 ,61      ,0,0,0
BEGIN DESCRIPTION:
TRIB 3A-1 TO COLETO CREEK 0.0
END DESCRIPTION:
XS GIS Cut Line= 4
      2565657.58     13449369.22      2565890.23     13449712.99
      2566164.54     13449813.68      2566515.23      13449223.4
#Sta/Elev= 30
  4431.2   90.97  4534.8   85.44  4619.6   78.34  4634.6   78.26  4700.5   71.83
  4757.4   68.04  4772.4   65.58  4815.8   65.95  4883.3   65.38  4892.2   66.67
  4936.6   67.42  4955.3   65.85  4978.3   64.89  4983.6   63.53  4989.9    58.6
  4998.4   57.68  4998.7   57.18  5002.6   57.68  5021.8   65.06  5032.5   66.34
  5227.2   65.39    5336   67.16  5401.2   68.34  5427.4   70.01  5459.6   70.82
  5532.4   75.93  5555.1   75.84  5625.5   80.53  5736.3   84.25  5825.1   90.22
#Mann= 8 ,-1 , 0
  4431.2     .12       0  4815.8     .07       0  4955.3     .12       0
  4998.4     .05       0  5002.6     .12       0  5227.2     .07       0
    5336     .12       0  5427.4     .07       0
Bank Sta=4998.4,5002.6
XS Rating Curve= 0 ,0
Exp/Cntr=0.3,0.1

Chan Stop Cuts=-1
Use User Specified Reach Order=0
Composite Channel Slope=5