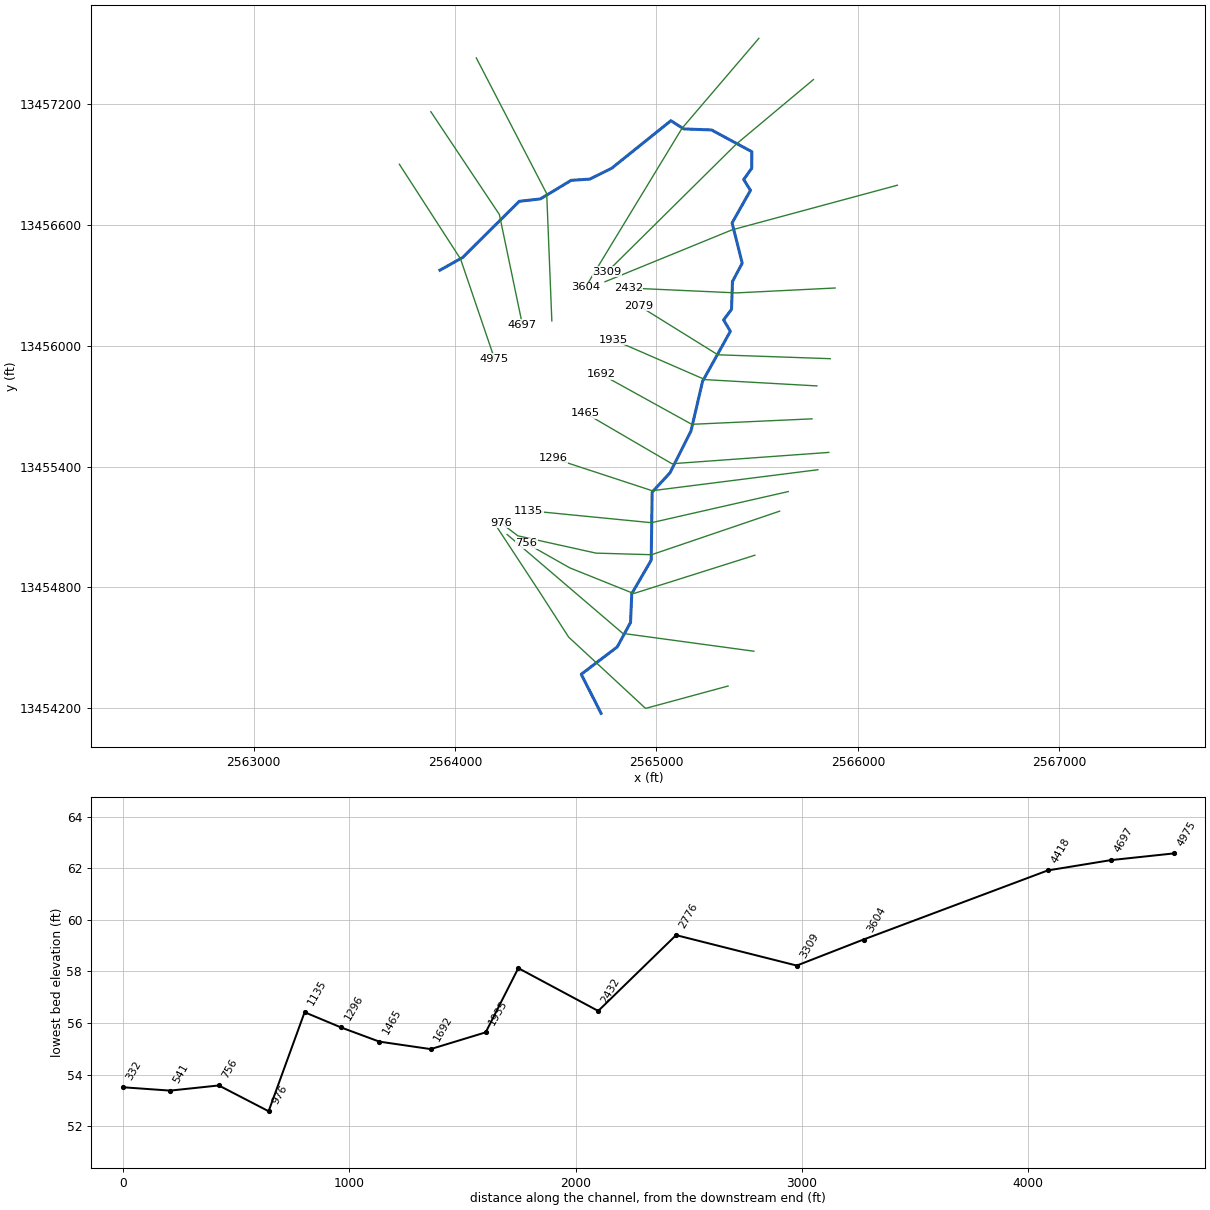
--- TRIB 3B TO COLETO CREEK.prj (project) ---

Proj Title=TRIB 3B TO COLETO CREEK Base Level Engineering
Current Plan=p01
Default Exp/Contr=0.3,0.1
English Units
Geom File=g01
Flow File=f01
Plan File=p01
Y Axis Title=Elevation
X Axis Title(PF)=Main Channel Distance
X Axis Title(XS)=Station
BEGIN DESCRIPTION:
TRIB 3B TO COLETO CREEK
END DESCRIPTION:
DSS Export Rating Curves= 0
DSS Export Rating Curve Sorted= 0
DSS Export Volume Flow Curves= 0
DXF OffsetX= 0
DXF OffsetY= 0
DXF ScaleX= 1
DXF ScaleY= 10

--- TRIB 3B TO COLETO CREEK.p01 (plan) ---

Plan Title=Multiple Run
Short Identifier=Multiple
Geom File=g01
Flow File=f01
Subcritical Flow
K Sum by GR= 0
Std Step Tol= 0.01
Critical Tol= 0.01
Num of Std Step Trials= 20
Max Error Tol= 0.3
Flow Tol Ratio= 0.001
Split Flow NTrial= 30
Split Flow Tol= 0.02
Split Flow Ratio= 0.02
Log Output Level= 0
Friction Slope Method= 1
Unsteady Friction Slope Method= 2
Unsteady Bridges Friction Slope Method= 1
Parabolic Critical Depth
Global Vel Dist=  1 , 1 , 1
Global Log Level= 0
CheckData=True
Encroach Param= -1, 0, 0, 0
BEGIN DESCRIPTION:
Multiple Run
END DESCRIPTION:

--- TRIB 3B TO COLETO CREEK.f01 (steady flow) ---

Flow Title=Multiple
Number of Profiles=7
Profile Names=10-year,25-year,50-year,1pct_min,100-year,1pct_plu,500-year
River Rch & RM= TRIB 3B TO COLET,Reach-1,4975
     759    1206    1604    1031    2057    4105    3345
River Rch & RM= TRIB 3B TO COLET,Reach-1,4697
     940    1511    2024    1310    2613    5213    4306
Boundary for River Rch & Prof#=TRIB 3B TO COLET,Reach-1,1
Up Type=0
Dn Type=3
Dn Slope=0.005
Boundary for River Rch & Prof#=TRIB 3B TO COLET,Reach-1,2
Up Type=0
Dn Type=3
Dn Slope=0.005
Boundary for River Rch & Prof#=TRIB 3B TO COLET,Reach-1,3
Up Type=0
Dn Type=3
Dn Slope=0.005
Boundary for River Rch & Prof#=TRIB 3B TO COLET,Reach-1,4
Up Type=0
Dn Type=3
Dn Slope=0.005
Boundary for River Rch & Prof#=TRIB 3B TO COLET,Reach-1,5
Up Type=0
Dn Type=3
Dn Slope=0.005
Boundary for River Rch & Prof#=TRIB 3B TO COLET,Reach-1,6
Up Type=0
Dn Type=3
Dn Slope=0.005
Boundary for River Rch & Prof#=TRIB 3B TO COLET,Reach-1,7
Up Type=0
Dn Type=3
Dn Slope=0.005

--- TRIB 3B TO COLETO CREEK.g01 (geometry) ---

Geom Title=Existing Conditions
Program Version=4.10

River Reach=TRIB 3B TO COLET,Reach-1
Reach XY= 30
        2563925.       13456375.      2564038.23     13456438.57
      2564318.83     13456717.14      2564423.41     13456728.83
      2564576.58     13456821.17      2564669.03     13456827.33
       2564777.3     13456880.83      2565071.59     13457117.19
      2565135.44      13457076.4      2565273.44     13457071.24
      2565473.49     13456963.14      2565472.68     13456880.98
       2565432.8     13456824.91      2565466.76     13456771.77
      2565375.37     13456609.73      2565425.71     13456409.94
      2565377.27     13456319.06      2565372.54     13456180.86
      2565333.28     13456128.22      2565366.76     13456071.77
      2565228.83     13455823.42      2565171.17     13455576.58
      2565066.84     13455368.95      2564978.55     13455273.53
       2564973.8      13454935.5      2564877.25     13454769.07
      2564871.24     13454626.56      2564805.23     13454504.87
       2564626.5     13454369.13        2564725.       13454175.

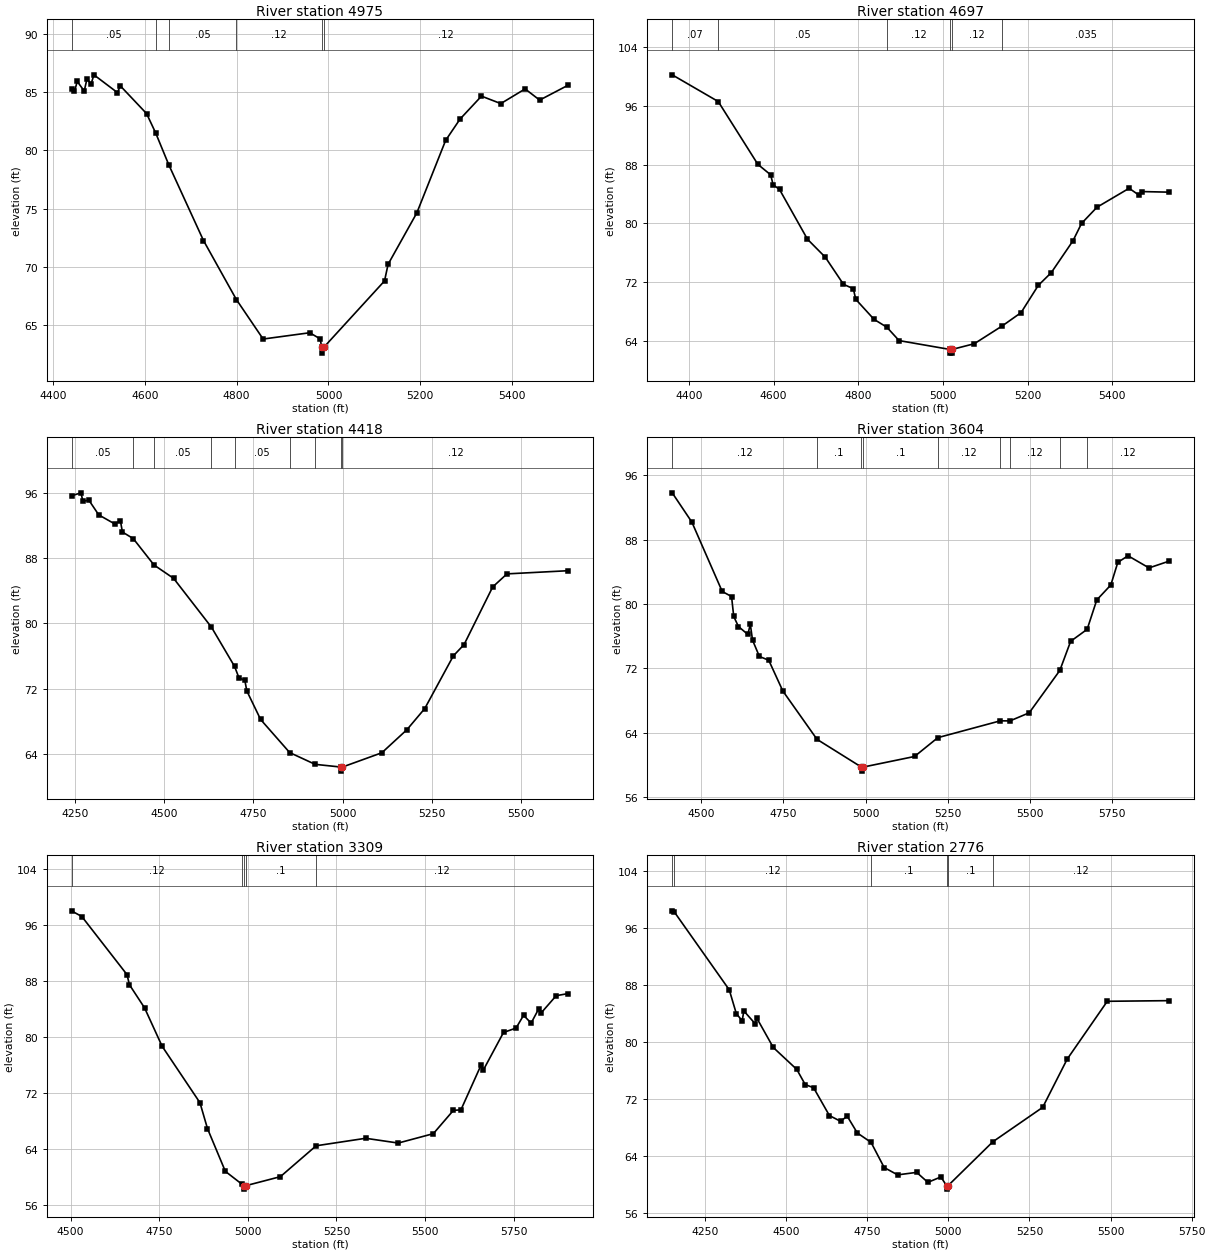
Type RM Length L Ch R = 1 ,4975    ,278,278,278
BEGIN DESCRIPTION:
TRIB 3B TO COLETO CREEK 8.0
END DESCRIPTION:
XS GIS Cut Line= 3
      2563723.57     13456901.05      2564027.34     13456430.72
      2564195.78      13455935.8
#Sta/Elev= 30
  4440.1   85.28  4446.6   85.05  4452.6   85.91  4467.8   85.09  4473.7   86.11
  4482.9   85.71  4488.9   86.48  4540.3   84.95  4546.3   85.54  4603.7   83.15
  4623.6   81.48    4652   78.76  4727.7   72.25  4799.4   67.18  4857.7   63.79
  4959.2   64.33  4981.8   63.81  4985.5   63.08  4985.8   62.58  4989.9   63.08
  5122.2   68.78    5130   70.21  5192.7   74.63  5255.4   80.85  5286.8   82.68
  5333.5   84.65  5375.6   84.01  5428.6   85.27  5460.3   84.31  5522.8    85.6
#Mann= 6 ,-1 , 0
  4440.1     .05       0  4623.6     .12       0    4652     .05       0
  4799.4     .12       0  4985.5     .05       0  4989.9     .12       0
Bank Sta=4985.5,4989.9
XS Rating Curve= 0 ,0
Exp/Cntr=0.3,0.1

Type RM Length L Ch R = 1 ,4697    ,279,279,279
BEGIN DESCRIPTION:
Mapping XS 0ceb3893
END DESCRIPTION:
XS GIS Cut Line= 3
      2563879.88      13457161.7      2564220.16     13456651.28
      2564334.75     13456102.67
#Sta/Elev= 30
  4360.3  100.27    4469   96.63  4562.7   88.06  4592.8   86.64  4598.8   85.28
  4613.8   84.64  4679.9   77.85    4722    75.4    4765    71.7  4788.1   71.11
  4794.1   69.65  4837.1   66.93  4867.5   65.85  4896.3   64.03  5016.7   62.82
    5017   62.32  5020.8   62.32  5021.1   62.82    5074    63.6  5140.3   66.04
  5184.5   67.84  5225.3   71.56    5256    73.3  5307.1   77.63  5327.5   80.01
  5363.8   82.21  5439.9    84.8  5463.7   83.84  5470.5   84.35  5534.2   84.27
#Mann= 6 ,-1 , 0
  4360.3     .07       0    4469     .05       0  4867.5     .12       0
  5016.7     .05       0  5021.1     .12       0  5140.3    .035       0
Bank Sta=5016.7,5021.1
XS Rating Curve= 0 ,0
Exp/Cntr=0.3,0.1

Type RM Length L Ch R = 1 ,4418    ,814,814,814
BEGIN DESCRIPTION:
TRIB 3B TO COLETO CREEK 7.0
END DESCRIPTION:
XS GIS Cut Line= 3
      2564105.49     13457428.87      2564455.11     13456754.74
      2564480.51     13456123.25
#Sta/Elev= 30
  4240.6   95.61    4267   95.98  4272.6   94.94  4289.1   95.09  4316.9   93.28
  4361.1   92.19  4377.6   92.54  4383.2   91.18  4413.5   90.38  4471.6   87.15
  4526.6   85.51  4632.6   79.53  4697.3   74.73  4709.5   73.34    4726   73.03
  4731.6   71.73  4770.2   68.24  4851.6   64.19  4922.9   62.75  4994.8   62.42
  4995.1   61.92  4999.3   62.42  5109.8   64.17  5179.9   66.99  5229.9   69.58
    5310   76.03    5340   77.41  5420.1   84.46  5460.1   86.06    5632   86.45
#Mann= 9 ,-1 , 0
  4240.6     .05       0  4413.5     .07       0  4471.6     .05       0
  4632.6     .07       0  4697.3     .05       0  4851.6     .07       0
  4922.9     .12       0  4994.8     .05       0  4999.3     .12       0
Bank Sta=4994.8,4999.3
XS Rating Curve= 0 ,0
Exp/Cntr=0.3,0.1

Type RM Length L Ch R = 1 ,3604    ,295,295,295
BEGIN DESCRIPTION:
TRIB 3B TO COLETO CREEK 6.0
END DESCRIPTION:
XS GIS Cut Line= 3
      2565508.29     13457526.07      2565126.47     13457079.03
       2564647.2     13456289.99
#Sta/Elev= 30
  4412.1   93.82  4471.9   90.18  4564.1   81.57  4592.6   80.93  4599.2   78.46
  4613.5   77.21    4642   76.23  4649.7   77.48  4656.3   75.53  4677.2   73.49
  4705.7   73.02  4748.5    69.2  4852.5   63.19  4987.6   59.74    4988   59.24
  4992.5   59.74  5149.1   61.06    5220    63.4    5410   65.49  5439.3   65.48
    5498   66.49    5591   71.75  5623.9   75.37  5674.1   76.86  5703.4   80.51
  5746.1   82.37  5767.4   85.18  5798.4      86  5862.3   84.49  5923.2   85.33
#Mann= 9 ,-1 , 0
  4412.1     .12       0  4852.5      .1       0  4987.6     .05       0
  4992.5      .1       0    5220     .12       0    5410     .07       0
  5439.3     .12       0    5591     .07       0  5674.1     .12       0
Bank Sta=4987.6,4992.5
XS Rating Curve= 0 ,0
Exp/Cntr=0.3,0.1

Type RM Length L Ch R = 1 ,3309    ,533,533,533
BEGIN DESCRIPTION:
Mapping XS 8da845a5
END DESCRIPTION:
XS GIS Cut Line= 3
      2565779.16     13457321.39      2565397.25     13457001.97
       2564754.9     13456366.56
#Sta/Elev= 30
  4502.7   97.97  4531.9   97.15  4659.4   88.85  4665.9   87.43  4708.8   84.11
  4758.3   78.63    4865   70.57  4886.2   66.88  4936.6   60.77  4982.2   58.98
  4990.1   58.73  4990.4   58.23    4995   58.73  5091.9   60.01  5192.7   64.42
  5332.4   65.49  5424.3   64.81  5523.3   66.15  5579.9   69.48  5601.1   69.55
  5657.6   75.91  5664.7   75.27  5721.2    80.6  5756.6   81.23  5777.8   83.05
  5799.1   81.94  5820.2   83.94  5827.4   83.39  5869.8   85.85  5904.1   86.16
#Mann= 5 ,-1 , 0
  4502.7     .12       0  4982.2      .1       0  4990.1     .05       0
    4995      .1       0  5192.7     .12       0
Bank Sta=4990.1,4995
XS Rating Curve= 0 ,0
Exp/Cntr=0.3,0.1

Type RM Length L Ch R = 1 ,2776    ,344,344,344
BEGIN DESCRIPTION:
TRIB 3B TO COLETO CREEK 5.0
END DESCRIPTION:
XS GIS Cut Line= 3
      2566195.75     13456796.89      2565374.18       13456575.
       2564744.4     13456317.73
#Sta/Elev= 30
    4149   98.45  4155.5   98.29  4324.8   87.37  4346.6   84.03  4364.6   83.03
  4369.8   84.41  4404.5   82.62  4409.7    83.4  4460.5   79.28    4533    76.2
  4558.9   74.08  4584.8   73.63  4633.5   69.73  4667.7   68.93  4688.4   69.64
  4719.5   67.29  4761.8   65.97  4802.3   62.44  4843.8   61.41  4902.4   61.76
    4937   60.36    4977   61.12  4994.4   59.91  4994.8   59.41  4999.5   59.91
  5137.1   66.05  5290.8   70.88  5366.4   77.65  5489.9   85.76  5680.3   85.85
#Mann= 6 ,-1 , 0
    4149    .035       0  4155.5     .12       0  4761.8      .1       0
  4994.4     .05       0  4999.5      .1       0  5137.1     .12       0
Bank Sta=4994.4,4999.5
XS Rating Curve= 0 ,0
Exp/Cntr=0.3,0.1

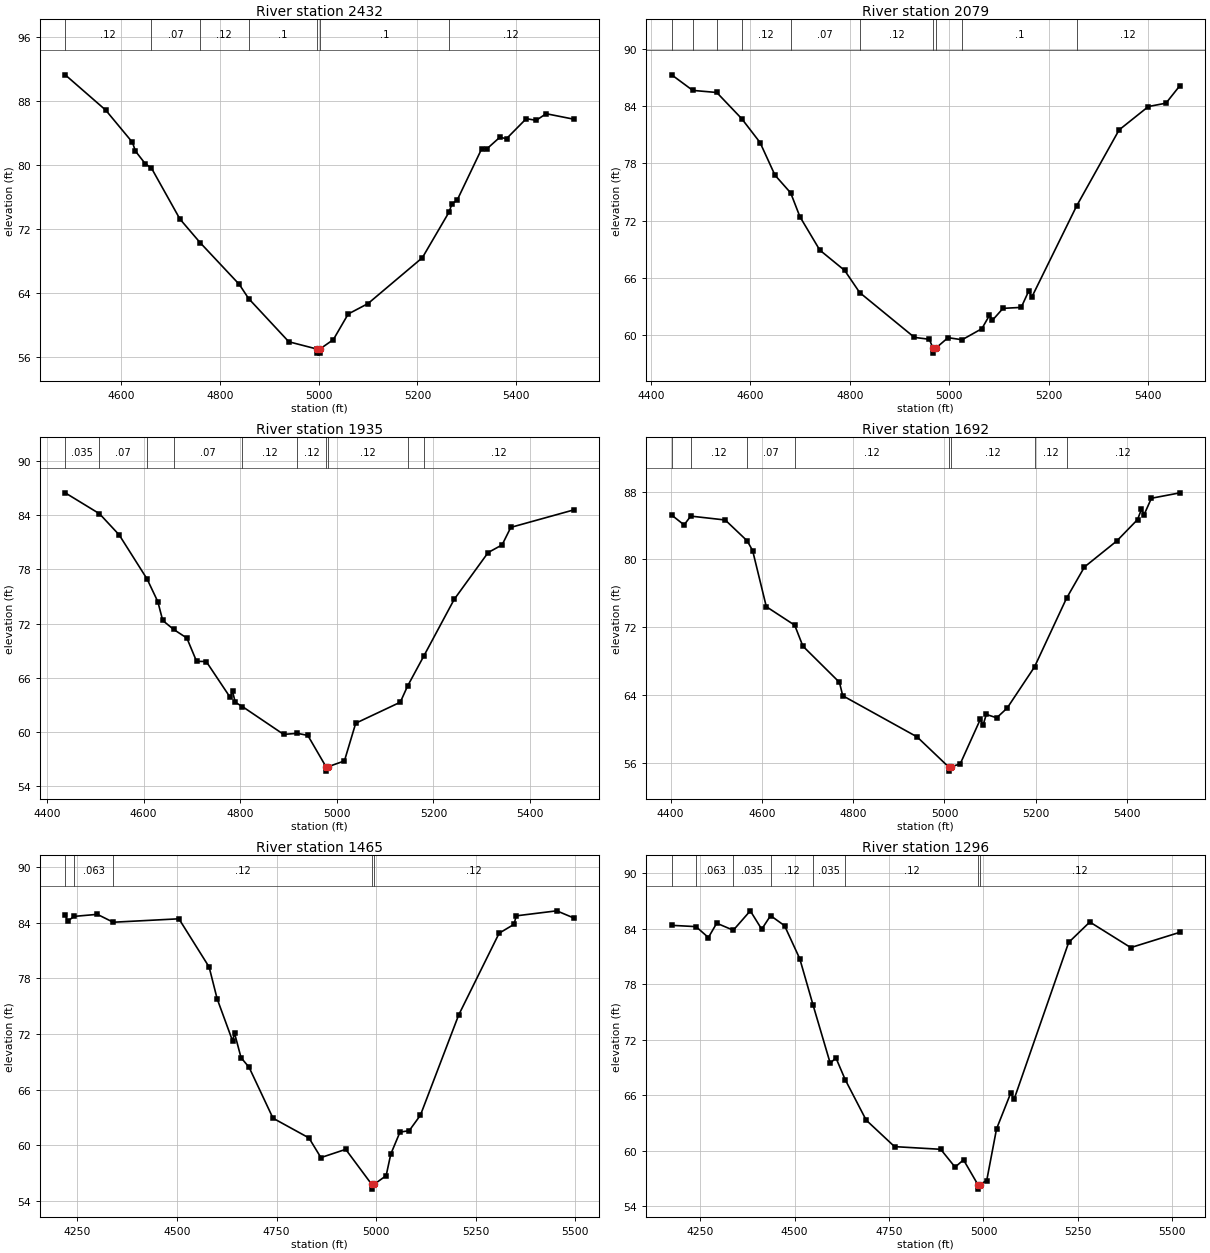
Type RM Length L Ch R = 1 ,2432    ,353,353,353
BEGIN DESCRIPTION:
Mapping XS 95779d31
END DESCRIPTION:
XS GIS Cut Line= 3
      2565886.79     13456286.69      2565397.25     13456262.39
      2564859.55     13456286.67
#Sta/Elev= 30
  4487.4   91.26  4569.3   86.85  4623.4   82.82  4629.4   81.73  4649.4   80.14
  4661.9    79.6  4719.5   73.23  4760.2   70.29  4839.6   65.06  4858.5   63.29
  4939.8   57.89  4997.3   56.97  4997.7   56.47    5002   56.47  5002.4   56.97
  5029.9   58.16  5059.9   61.36  5099.9   62.66    5210    68.4  5263.9    74.1
  5270.1   75.17  5280.1   75.56  5330.2   82.04  5340.2   81.99  5366.6   83.45
  5380.2   83.28  5420.2   85.78  5440.3   85.57  5460.3    86.4  5515.8   85.72
#Mann= 7 ,-1 , 0
  4487.4     .12       0  4661.9     .07       0  4760.2     .12       0
  4858.5      .1       0  4997.3     .05       0  5002.4      .1       0
  5263.9     .12       0
Bank Sta=4997.3,5002.4
XS Rating Curve= 0 ,0
Exp/Cntr=0.3,0.1

Type RM Length L Ch R = 1 ,2079    ,144,144,144
BEGIN DESCRIPTION:
TRIB 3B TO COLETO CREEK 4.0
END DESCRIPTION:
XS GIS Cut Line= 3
       2565862.5     13455935.78      2565304.84     13455955.07
      2564911.03      13456199.7
#Sta/Elev= 30
    4442   87.28  4484.3   85.65  4532.6   85.43  4582.7   82.69  4619.6   80.19
  4649.6   76.77  4681.2   74.91  4699.7   72.42  4739.7   68.92  4789.7   66.79
  4819.9   64.47  4929.8   59.78  4959.8   59.58  4967.3   58.63  4967.7   58.13
  4972.4   58.63  4997.4   59.75  5025.7   59.53  5065.4   60.69  5080.7   62.09
  5086.6   61.57  5107.9   62.82  5144.5   62.92  5159.8   64.66  5165.7   63.99
  5255.6   73.52  5341.2   81.51  5400.1   83.96  5435.4   84.31  5463.6   86.16
#Mann= 10 ,-1 , 0
    4442    .035       0  4484.3     .05       0  4532.6    .035       0
  4582.7     .12       0  4681.2     .07       0  4819.9     .12       0
  4967.3     .05       0  4972.4     .12       0  5025.7      .1       0
  5255.6     .12       0
Bank Sta=4967.3,4972.4
XS Rating Curve= 0 ,0
Exp/Cntr=0.3,0.1

Type RM Length L Ch R = 1 ,1935    ,243,243,243
BEGIN DESCRIPTION:
Mapping XS 91ca8050
END DESCRIPTION:
XS GIS Cut Line= 3
      2565796.54     13455800.58        2565241.     13455831.83
      2564786.11     13456029.76
#Sta/Elev= 30
  4437.6   86.49  4508.6   84.17  4549.3   81.83  4607.2   76.93  4629.4   74.42
  4639.5   72.34  4662.3   71.34  4689.5   70.39  4709.6   67.81  4729.6   67.79
    4779   63.83    4784   64.49  4789.7   63.27  4804.4    62.8  4889.9   59.71
  4918.1   59.83  4939.9    59.6  4977.4   56.14  4977.8   55.64  4982.5   56.14
  5015.7   56.77  5039.1   60.95  5131.4   63.28  5146.4   65.06  5180.4   68.43
    5243   74.68  5313.3   79.87  5342.2   80.72  5360.2   82.66  5490.1   84.59
#Mann= 10 ,-1 , 0
  4437.6    .035       0  4508.6     .07       0  4607.2     .12       0
  4662.3     .07       0  4804.4     .12       0  4918.1     .12       0
  4977.4     .05       0  4982.5     .12       0  5146.4      .1       0
  5180.4     .12       0
Bank Sta=4977.4,4982.5
XS Rating Curve= 0 ,0
Exp/Cntr=0.3,0.1

Type RM Length L Ch R = 1 ,1692    ,227,227,227
BEGIN DESCRIPTION:
TRIB 3B TO COLETO CREEK 2.0
END DESCRIPTION:
XS GIS Cut Line= 3
      2565772.13     13455637.17      2565175.16     13455609.94
      2564723.58     13455859.39
#Sta/Elev= 30
  4402.4   85.24  4429.6   84.08  4444.2   85.12  4519.7   84.66  4567.7    82.2
  4579.7   81.05  4609.7   74.42  4671.9   72.23  4689.8   69.76  4769.9   65.48
  4777.1    63.9  4940.1   59.03    5009   55.49  5009.4   54.99  5014.2   55.49
  5034.5   55.85  5078.6   61.12  5084.4   60.41  5091.6   61.69  5114.4   61.29
  5137.3   62.44  5197.2    67.3  5267.3   75.41  5306.6   79.11  5377.6   82.19
  5422.9   84.71  5431.5   85.93  5437.2   85.29  5453.3   87.23  5515.9   87.87
#Mann= 8 ,-1 , 0
  4402.4    .035       0  4444.2     .12       0  4567.7     .07       0
  4671.9     .12       0    5009     .05       0  5014.2     .12       0
  5197.2     .12       0  5267.3     .12       0
Bank Sta=5009,5014.2
XS Rating Curve= 0 ,0
Exp/Cntr=0.3,0.1

Type RM Length L Ch R = 1 ,1465    ,169,169,169
BEGIN DESCRIPTION:
TRIB 3B TO COLETO CREEK 3.0
END DESCRIPTION:
XS GIS Cut Line= 3
      2565855.47     13455470.51       2565076.7      13455414.3
      2564648.57     13455664.14
#Sta/Elev= 30
  4219.2   84.82  4225.5   84.17  4241.4   84.69  4299.9   84.91  4339.8   84.06
  4504.7   84.43  4580.6   79.23  4600.7   75.81  4639.4   71.27  4644.4    72.1
  4660.8   69.45  4680.9   68.42    4741   62.93  4831.3    60.8  4861.3   58.68
  4923.6   59.57  4989.1   55.78  4989.5   55.28  4994.3   55.78  5025.1   56.73
  5036.8   59.06  5059.9   61.43    5083   61.58  5111.2   63.25  5207.2   74.05
  5308.9   82.88  5346.1   83.83  5351.9   84.75  5453.6   85.29  5495.7   84.53
#Mann= 5 ,-1 , 0
  4219.2    .035       0  4241.4    .063       0  4339.8     .12       0
  4989.1     .05       0  4994.3     .12       0
Bank Sta=4989.1,4994.3
XS Rating Curve= 0 ,0
Exp/Cntr=0.3,0.1

Type RM Length L Ch R = 1 ,1296    ,161,161,161
BEGIN DESCRIPTION:
Mapping XS 506d8e82
END DESCRIPTION:
XS GIS Cut Line= 3
      2565801.43     13455384.56      2564978.56      13455280.4
       2564488.2     13455441.26
#Sta/Elev= 30
  4174.7   84.38  4239.1   84.24  4271.9   83.06  4293.9   84.61  4337.8   83.85
  4382.8   85.95    4413   83.96  4436.5   85.43  4473.5   84.34  4513.8   80.76
  4548.6    75.8  4594.4   69.45  4609.4   70.04  4633.9   67.69  4689.5    63.3
  4764.6   60.43  4886.8   60.14  4924.9   58.21  4947.2      59    4985   56.33
  4985.4   55.83  4990.2   56.33  5008.6   56.76  5034.6   62.35  5071.7   66.18
  5081.5   65.61  5225.5   82.53  5281.5   84.74  5389.9   81.97  5520.2   83.63
#Mann= 8 ,-1 , 0
  4174.7     .12       0  4239.1    .063       0  4337.8    .035       0
  4436.5     .12       0  4548.6    .035       0  4633.9     .12       0
    4985     .05       0  4990.2     .12       0
Bank Sta=4985,4990.2
XS Rating Curve= 0 ,0
Exp/Cntr=0.3,0.1

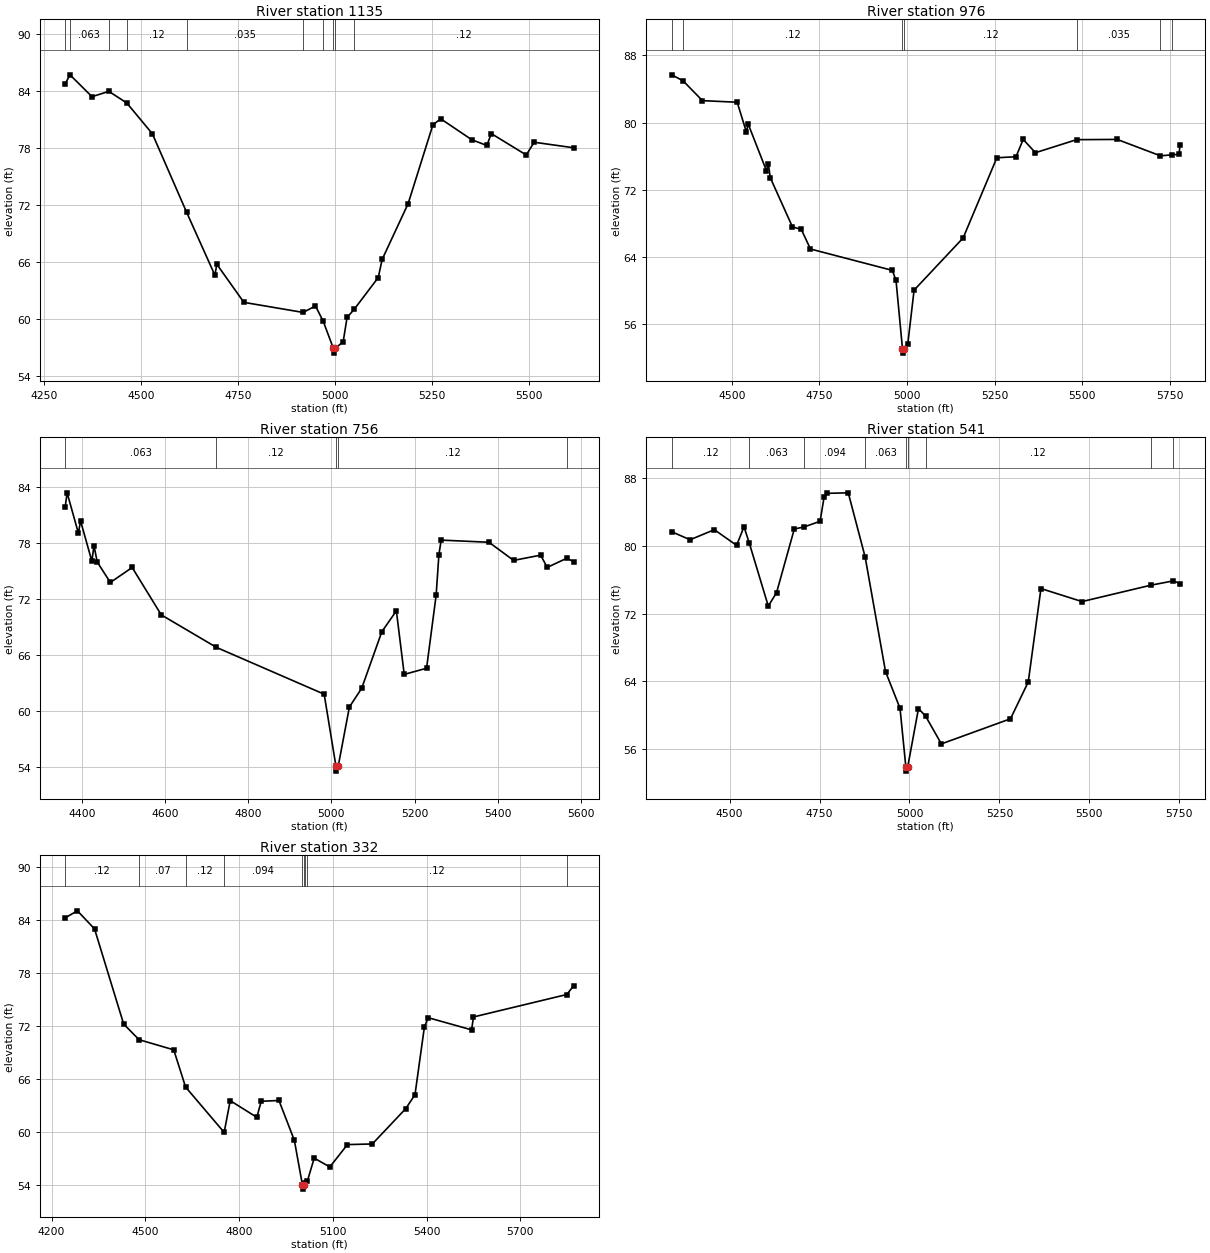
Type RM Length L Ch R = 1 ,1135    ,159,159,159
BEGIN DESCRIPTION:
TRIB 3B TO COLETO CREEK 1.0
END DESCRIPTION:
XS GIS Cut Line= 3
      2565654.13     13455276.07      2564974.99     13455121.54
      2564364.02     13455181.44
#Sta/Elev= 30
  4303.5   84.75  4315.8   85.69  4372.6   83.39  4415.9   83.95    4462   82.74
  4528.2   79.49  4616.2   71.26  4689.3   64.62  4694.4   65.76  4764.1   61.76
  4916.7    60.7  4948.7   61.38  4968.7   59.76  4994.8   56.92  4995.2   56.42
    5000   56.92  5020.1   57.63  5030.1   60.17  5048.5   61.03  5110.5   64.37
  5120.6   66.28  5187.5   72.14  5251.2   80.41  5271.3   81.07  5351.7   78.86
  5390.5   78.26  5401.9   79.51    5492   77.26  5512.4    78.6  5613.9   78.02
#Mann= 10 ,-1 , 0
  4303.5     .12       0  4315.8    .063       0  4415.9    .035       0
    4462     .12       0  4616.2    .035       0  4916.7     .12       0
  4968.7    .035       0  4994.8    .035       0    5000    .035       0
  5048.5     .12       0
Bank Sta=4994.8,5000
XS Rating Curve= 0 ,0
Exp/Cntr=0.3,0.1

Type RM Length L Ch R = 1 ,976     ,220,220,220
BEGIN DESCRIPTION:
Mapping XS 67f96cd9
END DESCRIPTION:
XS GIS Cut Line= 5
      2565611.38     13455178.84      2564975.95     13454962.69
      2564699.91      13454970.5      2564311.89     13455056.44
      2564226.97     13455120.78
#Sta/Elev= 30
  4328.3   85.67  4360.8   84.96  4416.1    82.6  4515.4   82.41  4541.5   78.88
  4546.8   79.81    4599   74.26  4604.3   75.12  4609.7   73.45    4673    67.6
  4698.4   67.29  4724.5   64.96  4958.2   62.42  4968.8   61.23  4987.3   53.08
  4987.7   52.58  4992.5   53.08  5002.5    53.7  5020.4   60.07  5160.5   66.28
  5256.7   75.81  5311.4   75.93  5331.9   77.99  5366.8   76.41  5484.2   77.96
  5600.2   77.99  5723.8   76.04  5757.1   76.16  5777.1   76.22  5779.6   77.37
#Mann= 7 ,-1 , 0
  4328.3    .063       0  4360.8     .12       0  4987.3     .05       0
  4992.5     .12       0  5484.2    .035       0  5723.8     .12       0
  5757.1    .035       0
Bank Sta=4987.3,4992.5
XS Rating Curve= 0 ,0
Exp/Cntr=0.3,0.1

Type RM Length L Ch R = 1 ,756     ,215,215,215
BEGIN DESCRIPTION:
Mapping XS 18d365cb
END DESCRIPTION:
XS GIS Cut Line= 4
      2565488.43      13454960.1      2564886.83     13454769.98
      2564569.12     13454897.59      2564352.98     13455019.98
#Sta/Elev= 30
  4360.3   81.87  4364.9   83.36    4392   79.04  4397.2   80.36  4424.3   76.05
  4429.5    77.7  4437.3   75.95  4468.8   73.77  4521.2   75.37  4591.2    70.3
  4723.8   66.82  4982.7   61.81  5011.1   54.08  5011.5   53.58  5016.3   54.08
  5043.3   60.44  5072.9   62.45  5121.3    68.5  5156.2   70.73  5175.1   63.93
  5228.8   64.59  5251.8   72.41  5258.4   76.73  5263.8    78.3  5378.8   78.07
    5438   76.13  5502.9   76.69  5518.8   75.38  5565.8   76.36    5582      76
#Mann= 5 ,-1 , 0
  4360.3    .063       0  4723.8     .12       0  5011.1     .05       0
  5016.3     .12       0  5565.8    .035       0
Bank Sta=5011.1,5016.3
XS Rating Curve= 0 ,0
Exp/Cntr=0.3,0.1

Type RM Length L Ch R = 1 ,541     ,209,209,209
BEGIN DESCRIPTION:
Mapping XS 4cd456aa
END DESCRIPTION:
XS GIS Cut Line= 3
      2565483.74     13454483.53      2564832.72     13454572.07
      2564258.57     13455063.09
#Sta/Elev= 30
  4339.2   81.69  4390.3   80.74  4457.7   81.93  4519.6   80.08  4540.2   82.28
  4554.7   80.37  4607.6    72.9  4630.6   74.48    4680   82.02  4706.9   82.25
  4751.7   82.93  4762.6   85.76  4771.9   86.23  4829.9   86.29  4876.8    78.7
  4933.4   65.16  4973.7   60.81  4989.9   53.88  4990.3   53.38  4995.1   53.88
    5025   60.78  5044.7   59.89  5088.6    56.6  5280.7   59.57  5330.1   63.93
  5365.3   74.97  5479.4   73.43  5671.1   75.37  5733.5   75.88  5751.7   75.55
#Mann= 9 ,-1 , 0
  4339.2     .12       0  4554.7    .063       0  4706.9    .094       0
  4876.8    .063       0  4989.9     .05       0  4995.1    .063       0
  5044.7     .12       0  5671.1    .035       0  5733.5     .12       0
Bank Sta=4989.9,4995.1
XS Rating Curve= 0 ,0
Exp/Cntr=0.3,0.1

Type RM Length L Ch R = 1 ,332     ,0,0,0
BEGIN DESCRIPTION:
TRIB 3B TO COLETO CREEK 0.0
END DESCRIPTION:
XS GIS Cut Line= 5
      2565355.51     13454310.79      2564945.79     13454199.68
      2564563.84     13454553.84      2564421.26     13454775.19
      2564192.08     13455124.17
#Sta/Elev= 30
  4243.7   84.21  4282.7      85  4337.5   82.96  4430.7   72.19  4479.9   70.42
  4590.9   69.27  4628.8   65.06  4752.2   59.93  4771.6   63.52  4856.6   61.64
  4870.8   63.45  4927.5   63.54  4976.8   59.03  5002.5   54.01    5003   53.51
  5007.8   54.01  5010.6   54.17  5018.8   54.47  5040.3   57.02  5090.2   56.02
  5146.6   58.55  5226.2   58.62  5333.2   62.62  5362.7    64.2  5392.7   71.84
  5404.9   72.91  5543.8   71.53  5549.8   72.99  5848.2   75.53  5869.9    76.5
#Mann= 9 ,-1 , 0
  4243.7     .12       0  4479.9     .07       0  4628.8     .12       0
  4752.2    .094       0  5002.5     .05       0  5007.8    .094       0
  5010.6    .063       0  5018.8     .12       0  5848.2    .035       0
Bank Sta=5002.5,5007.8
XS Rating Curve= 0 ,0
Exp/Cntr=0.3,0.1

Chan Stop Cuts=-1
Use User Specified Reach Order=0
Composite Channel Slope=5