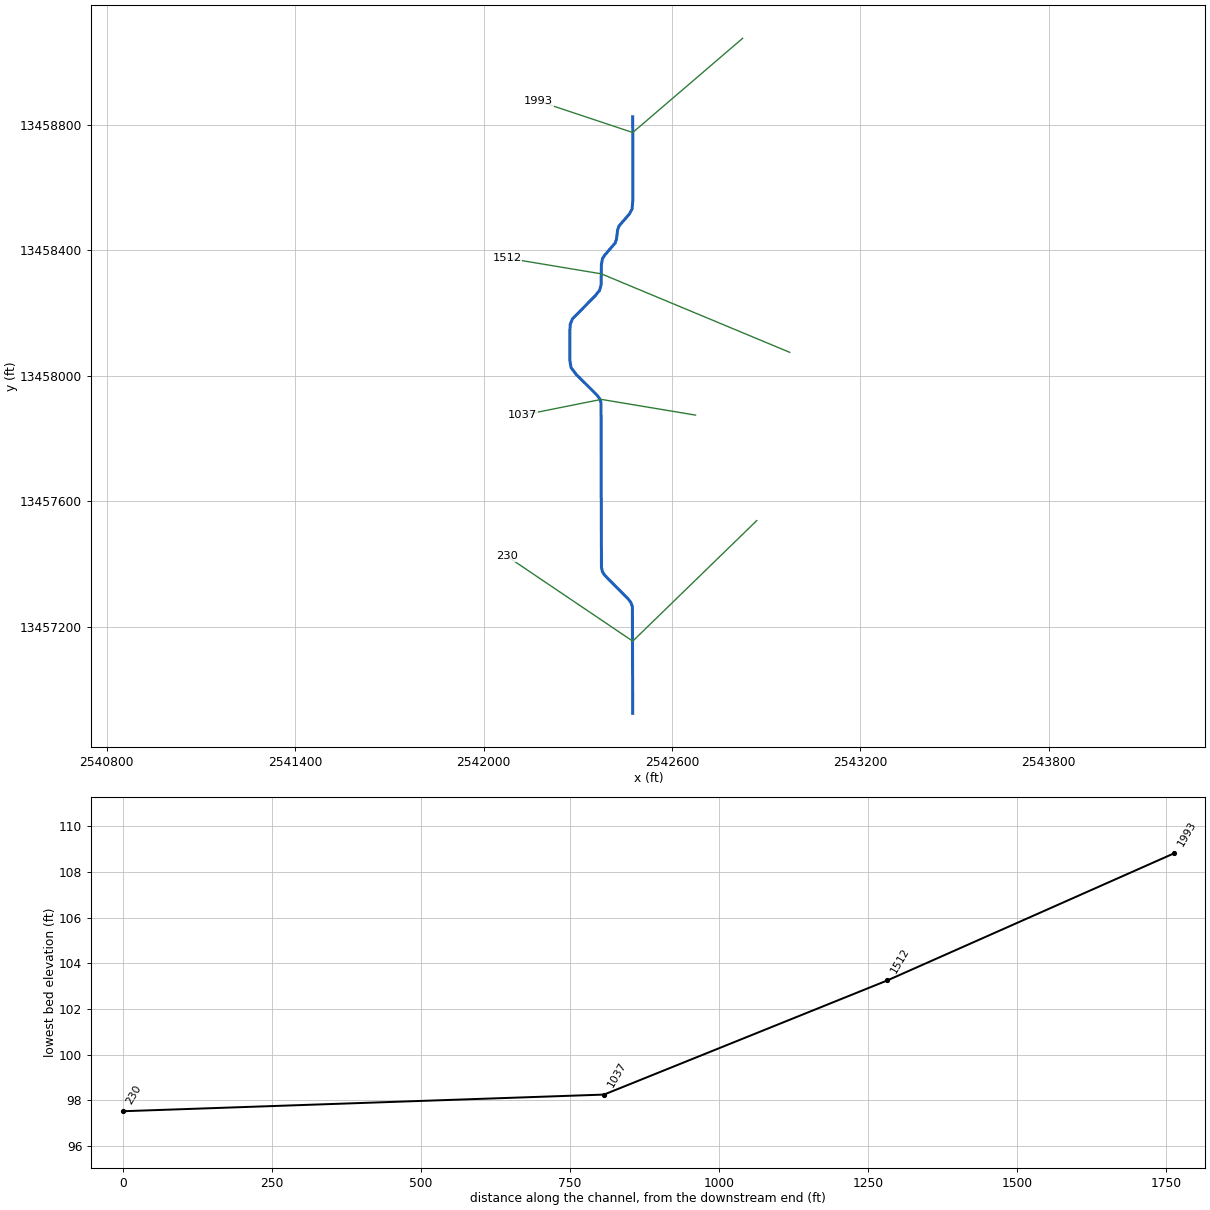
--- TRIB 4 TO COLETO CREEK RESERVOIR.prj (project) ---

Proj Title=TRIB 4 TO COLETO CREEK RESERVOIR Base Level Engineering
Current Plan=p01
Default Exp/Contr=0.3,0.1
English Units
Geom File=g01
Flow File=f01
Plan File=p01
Y Axis Title=Elevation
X Axis Title(PF)=Main Channel Distance
X Axis Title(XS)=Station
BEGIN DESCRIPTION:
TRIB 4 TO COLETO CREEK RESERVOIR
END DESCRIPTION:
DSS Export Rating Curves= 0
DSS Export Rating Curve Sorted= 0
DSS Export Volume Flow Curves= 0
DXF OffsetX= 0
DXF OffsetY= 0
DXF ScaleX= 1
DXF ScaleY= 10

--- TRIB 4 TO COLETO CREEK RESERVOIR.p01 (plan) ---

Plan Title=Multiple Run
Short Identifier=Multiple
Geom File=g01
Flow File=f01
Subcritical Flow
K Sum by GR= 0
Std Step Tol= 0.01
Critical Tol= 0.01
Num of Std Step Trials= 20
Max Error Tol= 0.3
Flow Tol Ratio= 0.001
Split Flow NTrial= 30
Split Flow Tol= 0.02
Split Flow Ratio= 0.02
Log Output Level= 0
Friction Slope Method= 1
Unsteady Friction Slope Method= 2
Unsteady Bridges Friction Slope Method= 1
Parabolic Critical Depth
Global Vel Dist=  1 , 1 , 1
Global Log Level= 0
CheckData=True
Encroach Param= -1, 0, 0, 0
BEGIN DESCRIPTION:
Multiple Run
END DESCRIPTION:

--- TRIB 4 TO COLETO CREEK RESERVOIR.f01 (steady flow) ---

Flow Title=Multiple
Number of Profiles=7
Profile Names=10-year,25-year,50-year,1pct_min,100-year,1pct_plu,500-year
River Rch & RM= TRIB 4 TO COLETO,Reach-1,1993
     409     629     819     517    1032    2059    1615
Boundary for River Rch & Prof#=TRIB 4 TO COLETO,Reach-1,1
Up Type=0
Dn Type=3
Dn Slope=0.005
Boundary for River Rch & Prof#=TRIB 4 TO COLETO,Reach-1,2
Up Type=0
Dn Type=3
Dn Slope=0.005
Boundary for River Rch & Prof#=TRIB 4 TO COLETO,Reach-1,3
Up Type=0
Dn Type=3
Dn Slope=0.005
Boundary for River Rch & Prof#=TRIB 4 TO COLETO,Reach-1,4
Up Type=0
Dn Type=3
Dn Slope=0.005
Boundary for River Rch & Prof#=TRIB 4 TO COLETO,Reach-1,5
Up Type=0
Dn Type=3
Dn Slope=0.005
Boundary for River Rch & Prof#=TRIB 4 TO COLETO,Reach-1,6
Up Type=0
Dn Type=3
Dn Slope=0.005
Boundary for River Rch & Prof#=TRIB 4 TO COLETO,Reach-1,7
Up Type=0
Dn Type=3
Dn Slope=0.005

--- TRIB 4 TO COLETO CREEK RESERVOIR.g01 (geometry) ---

Geom Title=Existing Conditions
Program Version=4.10

River Reach=TRIB 4 TO COLETO,Reach-1
Reach XY= 30
        2542475.       13458825.      2542475.44     13458559.82
      2542472.76     13458530.93       2542464.2     13458515.33
      2542431.12     13458477.18      2542426.67     13458464.31
      2542423.33     13458435.69      2542418.89     13458422.82
      2542385.84     13458384.65      2542378.83     13458373.41
      2542375.24      13458354.9      2542374.47     13458290.22
      2542369.46     13458272.58      2542355.33     13458254.86
      2542282.82     13458181.18      2542276.04     13458164.56
      2542274.45     13458135.19      2542274.68     13458049.89
      2542278.54     13458026.47      2542294.65     13458004.86
       2542361.6     13457938.31      2542369.52     13457927.45
      2542373.94     13457914.56      2542375.39     13457390.16
      2542378.55     13457376.47       2542385.5     13457365.21
       2542461.6     13457288.31      2542469.52     13457277.45
      2542473.94     13457264.56        2542475.       13456925.

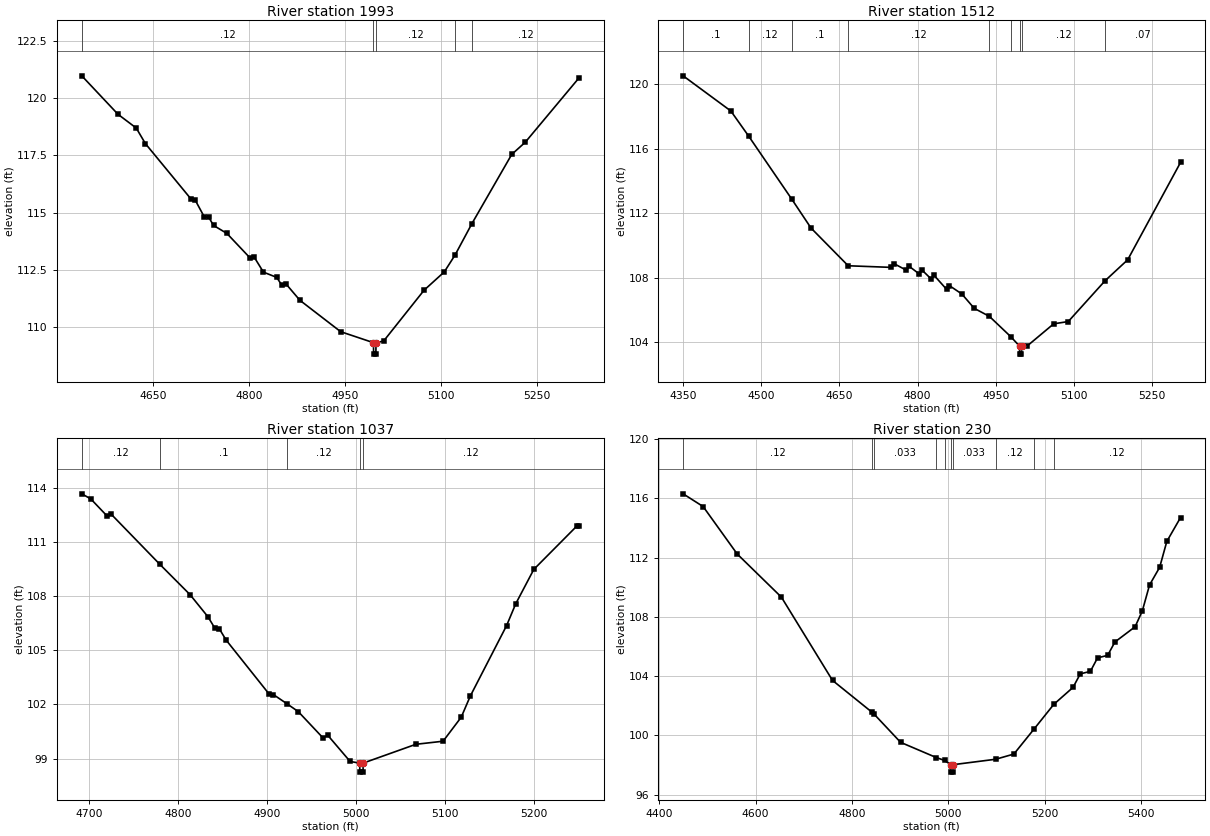
Type RM Length L Ch R = 1 ,1993    ,481,481,481
BEGIN DESCRIPTION:
TRIB 4 TO COLETO CREEK RESERVOIR 4.0
END DESCRIPTION:
XS GIS Cut Line= 3
      2542825.03     13459075.02        2542475.       13458775.
      2542175.04     13458874.99
#Sta/Elev= 30
    4539  120.97  4595.6  119.29  4624.1  118.69  4638.4  118.01  4709.7  115.59
  4716.3  115.54  4730.6   114.8  4737.1  114.81  4744.8  114.44  4765.7  114.09
  4801.9  113.02  4808.5  113.05  4822.8   112.4  4843.6  112.17  4851.3  111.84
  4857.9  111.89  4879.8  111.17  4943.5   109.8  4994.7  109.32    4995  108.82
  4998.5  108.82  4998.7  109.32  5010.6  109.39  5073.8  111.61  5105.4  112.41
  5122.3  113.15  5148.6  114.52  5210.8  117.54  5231.9  118.07  5316.2  120.89
#Mann= 5 ,-1 , 0
    4539     .12       0  4994.7     .05       0  4998.7     .12       0
  5122.3     .07       0  5148.6     .12       0
Bank Sta=4994.7,4998.7
XS Rating Curve= 0 ,0
Exp/Cntr=0.3,0.1

Type RM Length L Ch R = 1 ,1512    ,475,475,475
BEGIN DESCRIPTION:
TRIB 4 TO COLETO CREEK RESERVOIR 3.0
END DESCRIPTION:
XS GIS Cut Line= 3
      2542974.96     13458075.02        2542375.       13458325.
      2542074.99       13458375.
#Sta/Elev= 30
  4350.1  120.51  4441.6  118.33  4475.6  116.78  4558.3  112.87  4595.4  111.07
  4666.7  108.73  4749.3  108.63  4754.7  108.86  4778.5  108.45  4783.9  108.69
  4802.3  108.24  4807.8  108.48  4826.2   107.9  4831.6  108.13  4855.4  107.27
  4860.8   107.5  4884.7  106.98  4908.5  106.09  4937.6  105.59  4978.3  104.34
  4995.3  103.75  4995.6  103.25  4999.1  103.25  4999.3  103.75  5010.2  103.76
  5060.9  105.13  5088.8  105.27  5159.7  107.81  5202.8   109.1  5304.2  115.14
#Mann= 9 ,-1 , 0
  4350.1      .1       0  4475.6     .12       0  4558.3      .1       0
  4666.7     .12       0  4937.6      .1       0  4978.3     .12       0
  4995.3     .05       0  4999.3     .12       0  5159.7     .07       0
Bank Sta=4995.3,4999.3
XS Rating Curve= 0 ,0
Exp/Cntr=0.3,0.1

Type RM Length L Ch R = 1 ,1037    ,807,807,807
BEGIN DESCRIPTION:
TRIB 4 TO COLETO CREEK RESERVOIR 2.0
END DESCRIPTION:
XS GIS Cut Line= 3
        2542675.       13457875.        2542375.       13457925.
      2542124.99       13457875.
#Sta/Elev= 30
  4691.9  113.65    4702  113.37  4719.8  112.45  4724.8  112.53  4779.6  109.75
  4813.6  108.07  4833.8  106.84  4841.4  106.22  4846.5  106.18  4854.1  105.56
  4902.3  102.58  4907.3  102.54  4922.9  102.02  4935.2   101.6  4963.1  100.14
  4968.2   100.3  4993.5   98.84  5004.2   98.75  5004.5   98.25    5008   98.25
  5008.2   98.75  5067.4   99.79    5098   99.96  5118.4  101.29  5128.6  102.46
  5169.4  106.36  5179.6  107.56    5200  109.47  5248.4  111.87    5251  111.87
#Mann= 5 ,-1 , 0
  4691.9     .12       0  4779.6      .1       0  4922.9     .12       0
  5004.2     .05       0  5008.2     .12       0
Bank Sta=5004.2,5008.2
XS Rating Curve= 0 ,0
Exp/Cntr=0.3,0.1

Type RM Length L Ch R = 1 ,230     ,0,0,0
BEGIN DESCRIPTION:
TRIB 4 TO COLETO CREEK RESERVOIR 1.0
END DESCRIPTION:
XS GIS Cut Line= 3
      2542869.88      13457538.9      2542475.03     13457155.01
      2542075.01     13457424.99
#Sta/Elev= 30
  4449.3   116.3  4490.9  115.44  4561.6  112.24  4653.4  109.33  4759.6  103.71
  4842.1  101.55  4846.7  101.41  4901.1   99.53  4975.5    98.5  4992.3   98.31
  5005.5   98.02  5005.7   97.52  5009.2   97.52  5009.5   98.02  5098.7   98.39
  5136.4   98.74  5178.1  100.42  5219.5   102.1  5259.3  103.24  5274.3  104.15
  5295.3  104.32  5310.2  105.23  5331.2   105.4  5346.2   106.3  5388.2  107.33
  5403.2   108.4  5418.2  110.15  5439.2  111.34  5454.1  113.09  5482.6   114.7
#Mann= 10 ,-1 , 0
  4449.3     .12       0  4842.1     .12       0  4846.7    .033       0
  4975.5     .12       0  4992.3    .033       0  5005.5    .033       0
  5009.5    .033       0  5098.7     .12       0  5178.1     .12       0
  5219.5     .12       0
Bank Sta=5005.5,5009.5
XS Rating Curve= 0 ,0
Exp/Cntr=0.3,0.1

Chan Stop Cuts=-1
Use User Specified Reach Order=0
Composite Channel Slope=5