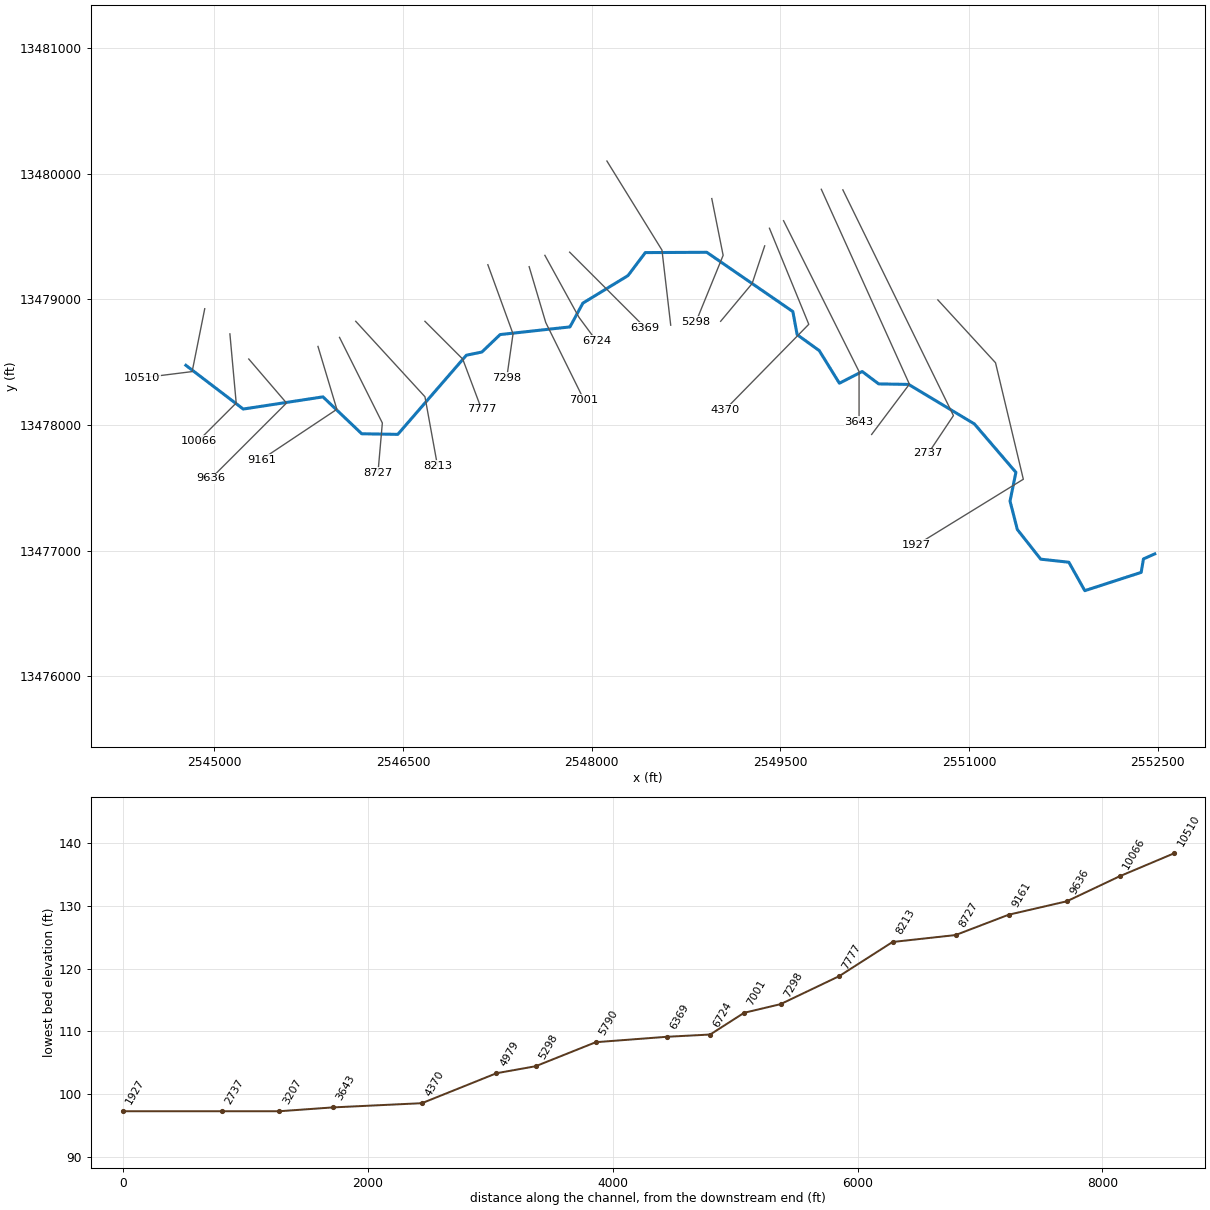
--- TRIB 4 TO COLETO CREEK.prj (project) ---

Proj Title=TRIB 4 TO COLETO CREEK Base Level Engineering
Current Plan=p01
Default Exp/Contr=0.3,0.1
English Units
Geom File=g01
Flow File=f01
Plan File=p01
Y Axis Title=Elevation
X Axis Title(PF)=Main Channel Distance
X Axis Title(XS)=Station
BEGIN DESCRIPTION:
TRIB 4 TO COLETO CREEK
END DESCRIPTION:
DSS Export Rating Curves= 0
DSS Export Rating Curve Sorted= 0
DSS Export Volume Flow Curves= 0
DXF OffsetX= 0
DXF OffsetY= 0
DXF ScaleX= 1
DXF ScaleY= 10

--- TRIB 4 TO COLETO CREEK.p01 (plan) ---

Plan Title=Multiple Run
Short Identifier=Multiple
Geom File=g01
Flow File=f01
Subcritical Flow
K Sum by GR= 0
Std Step Tol= 0.01
Critical Tol= 0.01
Num of Std Step Trials= 20
Max Error Tol= 0.3
Flow Tol Ratio= 0.001
Split Flow NTrial= 30
Split Flow Tol= 0.02
Split Flow Ratio= 0.02
Log Output Level= 0
Friction Slope Method= 1
Unsteady Friction Slope Method= 2
Unsteady Bridges Friction Slope Method= 1
Parabolic Critical Depth
Global Vel Dist=  1 , 1 , 1
Global Log Level= 0
CheckData=True
Encroach Param= -1, 0, 0, 0
BEGIN DESCRIPTION:
Multiple Run
END DESCRIPTION:

--- TRIB 4 TO COLETO CREEK.f01 (steady flow) ---

Flow Title=Multiple
Program Version=4.10
Number of Profiles= 7
Profile Names=10-year,25-year,50-year,1pct_min,100-year,1pct_plu,500-year
River Rch & RM=TRIB 4 TO COLETO,Reach-1         ,10510
     519     819    1084     696    1389    2771    2250
River Rch & RM=TRIB 4 TO COLETO,Reach-1         ,7001
     783    1264    1700    1106    2207    4404    3679
River Rch & RM=TRIB 4 TO COLETO,Reach-1         ,3643
     912    1478    1991    1296    2586    5161    4318
Boundary for River Rch & Prof#=TRIB 4 TO COLETO,Reach-1         , 1
Up Type= 0
Dn Type= 3
Dn Slope=0.0005
Boundary for River Rch & Prof#=TRIB 4 TO COLETO,Reach-1         , 2
Up Type= 0
Dn Type= 3
Dn Slope=0.0005
Boundary for River Rch & Prof#=TRIB 4 TO COLETO,Reach-1         , 3
Up Type= 0
Dn Type= 3
Dn Slope=0.0005
Boundary for River Rch & Prof#=TRIB 4 TO COLETO,Reach-1         , 4
Up Type= 0
Dn Type= 3
Dn Slope=0.0005
Boundary for River Rch & Prof#=TRIB 4 TO COLETO,Reach-1         , 5
Up Type= 0
Dn Type= 3
Dn Slope=0.0005
Boundary for River Rch & Prof#=TRIB 4 TO COLETO,Reach-1         , 6
Up Type= 0
Dn Type= 3
Dn Slope=0.0005
Boundary for River Rch & Prof#=TRIB 4 TO COLETO,Reach-1         , 7
Up Type= 0
Dn Type= 3
Dn Slope=0.0005
DSS Import GetInterval= 0
DSS Import GetPeak= 0
DSS Import FillOption= 0

--- TRIB 4 TO COLETO CREEK.g01 (geometry) ---

Geom Title=Existing Conditions
Program Version=4.10

River Reach=TRIB 4 TO COLETO,Reach-1
Reach XY= 30
        2544775.       13478475.      2545230.86     13478127.06
      2545864.57     13478223.95      2546172.55     13477930.46
      2546459.17     13477925.66       2547004.5     13478555.44
      2547127.42     13478580.53      2547272.57     13478719.48
      2547827.47     13478780.45      2547930.26     13478969.53
      2548288.56     13479188.49      2548426.45     13479371.47
      2548914.56     13479373.94      2549598.97     13478902.19
      2549632.81     13478718.79       2549808.5     13478592.05
      2549968.67     13478332.34        2550150.     13478425.58
      2550280.86     13478327.07      2550519.14     13478322.93
      2551041.75     13478008.54      2551371.46     13477623.53
      2551324.72     13477395.18      2551382.83     13477168.82
      2551568.79      13476932.8      2551792.22     13476908.76
      2551918.93     13476682.47      2552367.03     13476827.94
      2552385.28     13476935.05        2552475.       13476975.

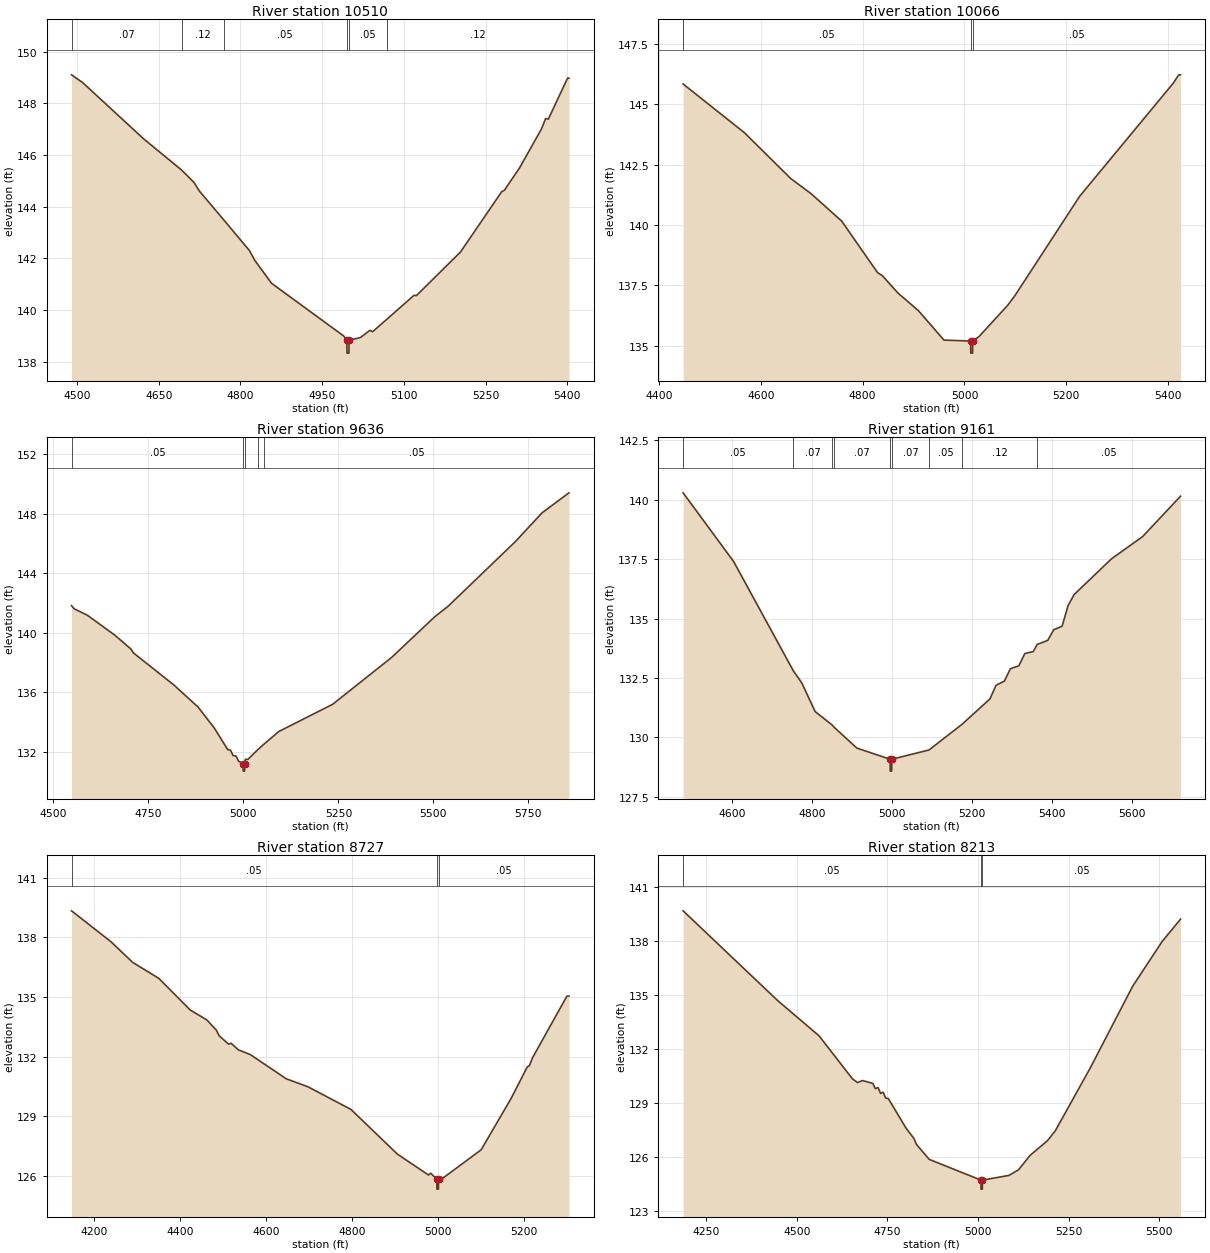
Type RM Length L Ch R = 1 ,10510   ,444,444,444
BEGIN DESCRIPTION:
TRIB 4 TO COLETO CREEK 17.0
END DESCRIPTION:
XS GIS Cut Line= 3
      2544925.01     13478925.05        2544825.       13478425.
      2544424.96       13478375.
#Sta/Elev= 30
    4490   149.1  4510.4   148.8  4622.6  146.62    4692  145.42  4714.4  144.95
  4724.6  144.61  4769.1   143.5  4816.4  142.31  4826.6  141.92  4857.2  141.04
  4989.8     139  4995.4  138.84  4995.7  138.34  4999.2  138.34  4999.4  138.84
  5020.1  138.94  5037.7  139.22  5042.8  139.17  5069.9  139.67  5118.4  140.57
  5123.4  140.57    5204  142.25  5279.6  144.58  5284.6  144.64  5312.4   145.5
  5352.7  147.01  5360.2  147.41  5365.3  147.39  5400.5  148.97  5403.1  148.97
#Mann= 6 ,-1 , 0
    4490     .07       0    4692     .12       0  4769.1     .05       0
  4995.4     .05       0  4999.4     .05       0  5069.9     .12       0
Bank Sta=4995.4,4999.4
XS Rating Curve= 0 ,0
Exp/Cntr=0.3,0.1

Type RM Length L Ch R = 1 ,10066   ,430,430,430
BEGIN DESCRIPTION:
TRIB 4 TO COLETO CREEK 16.0
END DESCRIPTION:
XS GIS Cut Line= 3
        2545125.       13478725.        2545175.       13478175.
      2544875.02     13477875.02
#Sta/Elev= 21
  4447.7  145.84  4568.2  143.82  4658.6  141.93  4698.7   141.3    4759  140.16
  4829.3  138.03  4839.3  137.89  4869.4  137.18  4909.6  136.45  4959.8  135.23
  5012.1  135.19  5012.4  134.69  5015.9  134.69  5016.1  135.19  5028.3  135.37
  5084.8  136.67    5099  137.07  5226.2  141.19  5410.1  145.88  5420.7  146.22
  5424.2  146.22
#Mann= 3 ,-1 , 0
  4447.7     .05       0  5012.1     .05       0  5016.1     .05       0
Bank Sta=5012.1,5016.1
XS Rating Curve= 0 ,0
Exp/Cntr=0.3,0.1

Type RM Length L Ch R = 1 ,9636    ,475,475,475
BEGIN DESCRIPTION:
TRIB 4 TO COLETO CREEK 15.0
END DESCRIPTION:
XS GIS Cut Line= 3
      2545275.01     13478524.99        2545575.       13478175.
        2544975.       13477575.
#Sta/Elev= 30
  4547.5  141.82  4554.6  141.61  4589.7  141.17  4661.1  139.85  4703.9  138.91
  4710.5  138.65  4816.9   136.5  4880.6  135.02  4923.4  133.61  4958.5  132.17
  4966.2  132.12  4972.8  131.77  4980.5  131.73  4987.1  131.39  4999.3  131.22
  4999.6  130.72  5003.1  130.72  5003.3  131.22  5005.2  131.51    5012  131.51
  5038.1  132.17  5054.6  132.54  5093.3  133.38  5234.7   135.2  5390.3  138.35
  5503.4  141.07  5538.8  141.78  5715.6  146.11  5786.3  148.05    5857  149.39
#Mann= 5 ,-1 , 0
  4547.5     .05       0  4999.3     .05       0  5003.3     .05       0
  5038.1      .1       0  5054.6     .05       0
Bank Sta=4999.3,5003.3
XS Rating Curve= 0 ,0
Exp/Cntr=0.3,0.1

Type RM Length L Ch R = 1 ,9161    ,434,434,434
BEGIN DESCRIPTION:
TRIB 4 TO COLETO CREEK 14.0
END DESCRIPTION:
XS GIS Cut Line= 3
      2545824.99     13478625.04        2545975.       13478125.
      2545374.97     13477724.98
#Sta/Elev= 30
    4478  140.29  4604.2   137.4  4753.5   132.8  4774.7  132.29  4807.8  131.09
  4850.5  130.52  4855.8  130.42  4912.2  129.55  4995.4  129.08  4995.7  128.58
  4999.2  128.58  4999.4  129.08  5092.5  129.47  5175.1  130.55  5244.9  131.62
    5260  132.19    5281  132.37    5296  132.89    5317  133.01  5332.1  133.53
  5353.1  133.61  5362.8  133.91  5389.2  134.08  5404.2  134.53  5425.2  134.68
  5440.2  135.55  5455.3  136.01  5548.4  137.51  5626.5  138.45  5721.2  140.15
#Mann= 9 ,-1 , 0
    4478     .05       0  4753.5     .07       0  4850.5     .05       0
  4855.8     .07       0  4995.4     .05       0  4999.4     .07       0
  5092.5     .05       0  5175.1     .12       0  5362.8     .05       0
Bank Sta=4995.4,4999.4
XS Rating Curve= 0 ,0
Exp/Cntr=0.3,0.1

Type RM Length L Ch R = 1 ,8727    ,514,514,514
BEGIN DESCRIPTION:
Mapping XS 708379f5
END DESCRIPTION:
XS GIS Cut Line= 3
      2545996.22     13478696.89      2546336.49     13478016.35
      2546301.77     13477620.53
#Sta/Elev= 30
  4147.4  139.34    4239  137.79  4289.6  136.75  4350.8  135.94  4423.8  134.35
  4462.6  133.85  4484.9  133.33  4490.9  133.06  4513.2  132.63  4518.8  132.68
  4535.6  132.35  4563.6  132.11  4647.4  130.89  4697.7  130.49    4798  129.35
  4906.2   127.1  4978.7  126.05  4983.7  126.14    4998  125.84  4998.2  125.34
  5001.7  125.34    5002  125.84    5010  125.86  5101.2  127.32  5170.6  129.89
  5208.6  131.49  5213.6  131.55  5220.8  131.95  5300.9  135.05  5305.6  135.05
#Mann= 3 ,-1 , 0
  4147.4     .05       0    4998     .05       0    5002     .05       0
Bank Sta=4998,5002
XS Rating Curve= 0 ,0
Exp/Cntr=0.3,0.1

Type RM Length L Ch R = 1 ,8213    ,436,436,436
BEGIN DESCRIPTION:
TRIB 4 TO COLETO CREEK 12.0
END DESCRIPTION:
XS GIS Cut Line= 3
      2546125.01     13478824.99        2546675.       13478225.
      2546774.99     13477675.04
#Sta/Elev= 30
  4186.1  139.67  4447.8  134.68  4561.3  132.74  4653.2  130.36  4667.4  130.15
  4681.5  130.26  4709.9   130.1  4716.7  129.81  4724.1  129.87  4730.9  129.55
  4738.3  129.61  4745.1  129.29  4752.5  129.26  4801.8  127.61  4823.4  127.04
  4830.1  126.72  4865.3  125.89  5008.2  124.74  5008.4  124.24  5011.9  124.24
  5012.2  124.74  5085.1     125  5111.8  125.31  5143.6  126.11  5191.9  126.93
  5213.5  127.48  5308.8  130.92  5426.9  135.49  5508.2  137.97    5559  139.21
#Mann= 3 ,-1 , 0
  4186.1     .05       0  5008.2     .05       0  5012.2     .05       0
Bank Sta=5008.2,5012.2
XS Rating Curve= 0 ,0
Exp/Cntr=0.3,0.1

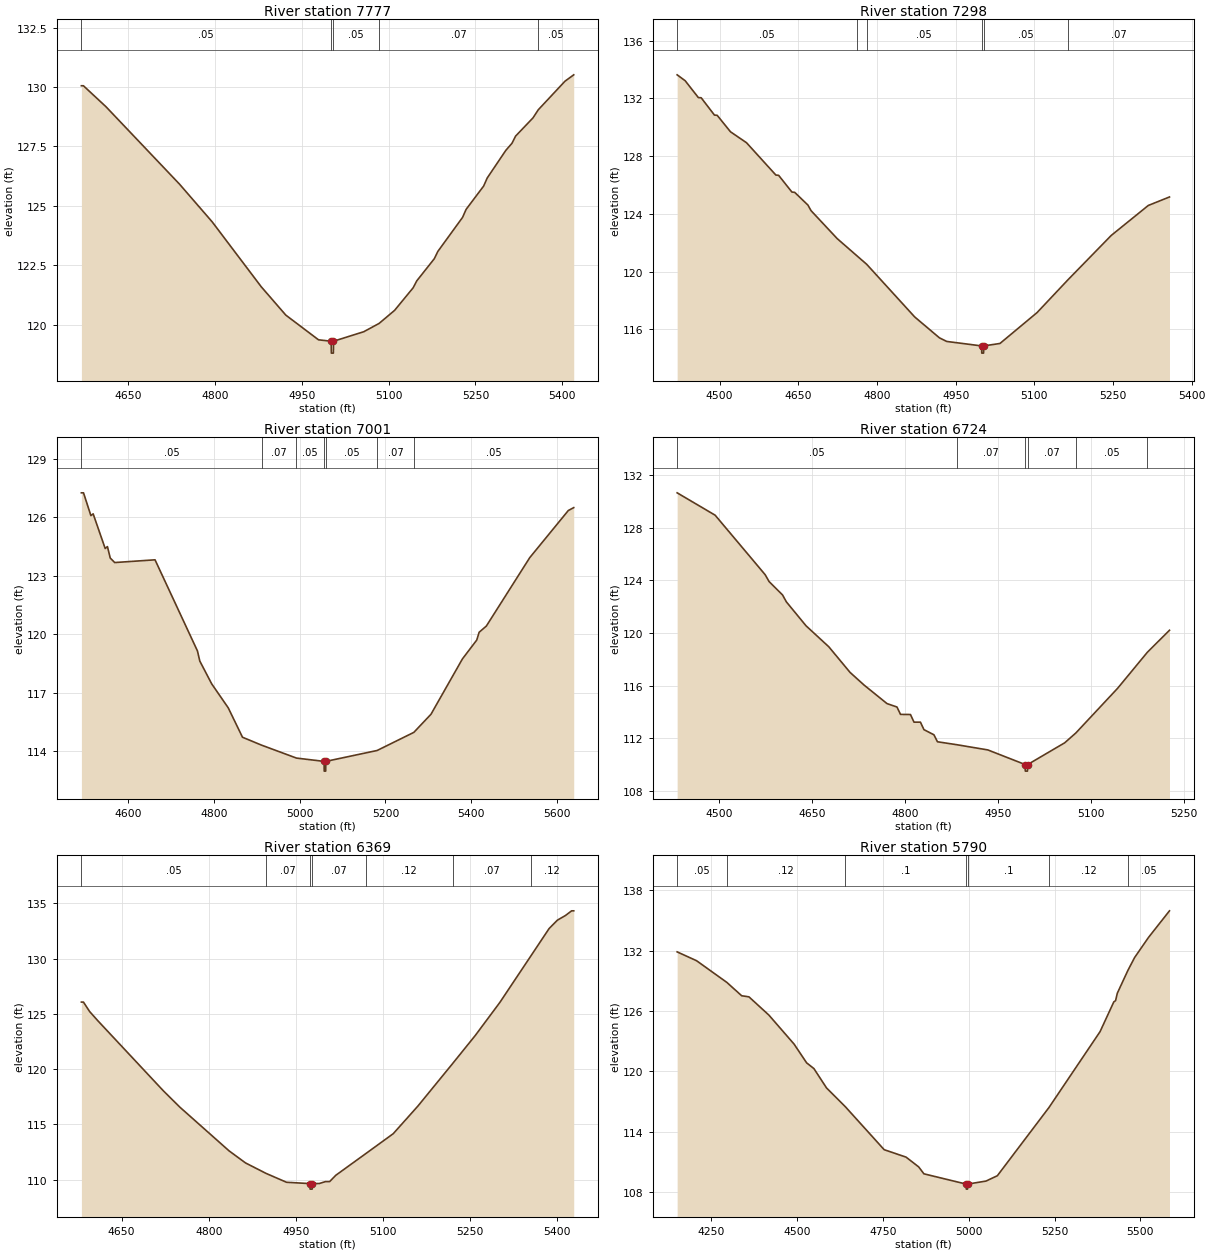
Type RM Length L Ch R = 1 ,7777    ,479,479,479
BEGIN DESCRIPTION:
TRIB 4 TO COLETO CREEK 11.0
END DESCRIPTION:
XS GIS Cut Line= 3
      2546675.01     13478824.99        2546975.       13478525.
      2547125.02     13478124.95
#Sta/Elev= 30
  4568.6  130.05  4572.1  130.05    4611  129.17  4738.3  125.91  4794.9  124.32
  4879.7  121.59  4922.1   120.4  4978.7  119.36  5000.6   119.3  5000.9   118.8
  5004.4   118.8  5004.6   119.3  5056.9   119.7  5083.5  120.05  5110.3   120.6
  5142.4  121.55  5148.6  121.84  5178.9  122.77  5185.1  123.08  5227.8  124.51
    5234  124.85  5264.3  125.83  5270.5  126.17  5302.6  127.33  5313.3  127.63
  5319.5  127.93  5349.7   128.7  5358.8  129.04  5404.9  130.24  5420.1  130.51
#Mann= 5 ,-1 , 0
  4568.6     .05       0  5000.6     .05       0  5004.6     .05       0
  5083.5     .07       0  5358.8     .05       0
Bank Sta=5000.6,5004.6
XS Rating Curve= 0 ,0
Exp/Cntr=0.3,0.1

Type RM Length L Ch R = 1 ,7298    ,297,297,297
BEGIN DESCRIPTION:
TRIB 4 TO COLETO CREEK 10.0
END DESCRIPTION:
XS GIS Cut Line= 3
      2547175.01     13479274.96        2547375.       13478725.
      2547325.01     13478375.05
#Sta/Elev= 30
    4419  133.64  4434.3  133.23  4459.5  132.06  4464.8  132.05  4490.1  130.85
  4495.4  130.83  4520.7  129.69  4551.3  128.93  4607.2  126.69  4612.5  126.67
  4637.8  125.51  4643.1  125.49  4668.3  124.61  4674.3  124.22  4724.2  122.28
  4762.7  121.06  4780.4   120.5  4871.9  116.85  4919.1   115.4    4933  115.15
  4999.5  114.84  4999.8  114.34  5003.3  114.34  5003.5  114.84  5034.5  115.01
  5105.2  117.15    5164  119.42  5246.6   122.5  5317.3  124.58  5357.7  125.17
#Mann= 6 ,-1 , 0
    4419     .05       0  4762.7     .12       0  4780.4     .05       0
  4999.5     .05       0  5003.5     .05       0    5164     .07       0
Bank Sta=4999.5,5003.5
XS Rating Curve= 0 ,0
Exp/Cntr=0.3,0.1

Type RM Length L Ch R = 1 ,7001    ,277,277,277
BEGIN DESCRIPTION:
Mapping XS d0bb3f69
END DESCRIPTION:
XS GIS Cut Line= 3
      2547503.16     13479259.41       2547635.1     13478814.96
      2547937.57      13478202.5
#Sta/Elev= 30
  4491.8  127.26  4496.7  127.26  4513.9  126.09  4519.2  126.18  4547.2   124.4
  4552.4   124.5    4559  123.91  4569.4  123.68  4663.3  123.82  4762.1  119.14
  4767.6  118.62  4795.3  117.45  4833.8  116.22    4867  114.71  4911.9   114.3
  4992.7  113.64  5057.1  113.47  5057.3  112.97  5060.8  112.97  5061.1  113.47
  5180.6  114.03  5266.1  114.96    5306  115.89  5379.2  118.73  5412.6   119.7
  5418.2   120.1    5435  120.42    5536  123.93  5625.8  126.35  5638.5   126.5
#Mann= 7 ,-1 , 0
  4491.8     .05       0  4911.9     .07       0  4992.7     .05       0
  5057.1     .05       0  5061.1     .05       0  5180.6     .07       0
  5266.1     .05       0
Bank Sta=5057.1,5061.1
XS Rating Curve= 0 ,0
Exp/Cntr=0.3,0.1

Type RM Length L Ch R = 1 ,6724    ,355,355,355
BEGIN DESCRIPTION:
Mapping XS 5817295a
END DESCRIPTION:
XS GIS Cut Line= 3
      2547628.18     13479349.64      2547898.99     13478856.63
      2548037.56     13478669.55
#Sta/Elev= 30
  4431.6  130.65    4493  128.95  4573.8  124.43  4580.1  123.91  4601.9  122.89
    4608  122.37  4639.8  120.55  4676.5  118.96  4710.9  117.01  4733.5  116.05
  4770.6  114.64  4786.7  114.38  4792.4  113.82  4808.5  113.81  4814.2  113.23
  4824.6  113.23  4830.3  112.66  4846.4  112.27  4852.1  111.74  4882.9  111.52
  4933.5  111.12  4993.8  110.01    4994  109.51  4997.5  109.51  4997.8  110.01
  5057.6  111.66  5075.7  112.41  5143.1   115.8  5191.2  118.54  5226.9  120.21
#Mann= 6 ,-1 , 0
  4431.6     .05       0  4882.9     .07       0  4993.8     .05       0
  4997.8     .07       0  5075.7     .05       0  5191.2     .07       0
Bank Sta=4993.8,4997.8
XS Rating Curve= 0 ,0
Exp/Cntr=0.3,0.1

Type RM Length L Ch R = 1 ,6369    ,579,579,579
BEGIN DESCRIPTION:
TRIB 4 TO COLETO CREEK 8.0
END DESCRIPTION:
XS GIS Cut Line= 3
      2547825.03     13479374.97        2548125.       13479075.
      2548425.01     13478774.99
#Sta/Elev= 30
  4580.6  126.06  4584.1  126.06  4594.7  125.21  4608.8  124.38    4722  118.03
  4750.3  116.56  4835.1  112.61  4863.4  111.52  4898.5  110.58  4934.1  109.77
  4974.5  109.65  4974.8  109.15  4978.3  109.15  4978.5  109.65  4990.7  109.66
  5001.3  109.83  5008.4  109.83    5019   110.4  5070.7  112.36    5118  114.16
  5160.4  116.65  5220.5  120.51  5259.4  123.04  5301.8  126.03  5354.7  130.19
  5386.7  132.71  5400.8  133.46  5414.9  133.89  5425.5  134.31  5429.1  134.31
#Mann= 7 ,-1 , 0
  4580.6     .05       0  4898.5     .07       0  4974.5     .05       0
  4978.5     .07       0  5070.7     .12       0  5220.5     .07       0
  5354.7     .12       0
Bank Sta=4974.5,4978.5
XS Rating Curve= 0 ,0
Exp/Cntr=0.3,0.1

Type RM Length L Ch R = 1 ,5790    ,492,492,492
BEGIN DESCRIPTION:
Mapping XS 422f8ce0
END DESCRIPTION:
XS GIS Cut Line= 3
      2548121.19     13480099.71      2548558.71     13479391.35
      2548628.15     13478794.16
#Sta/Elev= 30
    4151  131.87  4207.6  130.99  4295.6  128.84  4338.9  127.51  4360.1   127.4
  4418.1  125.59  4491.4  122.71  4528.1  120.84  4549.3  120.27    4586  118.35
  4640.3   116.5  4753.9  112.21  4817.7  111.47  4854.4   110.5  4869.7  109.81
  4992.9  108.79  4993.1  108.29  4996.6  108.29  4996.9  108.79  5050.4  109.09
  5083.5  109.62  5233.8   116.4  5382.6  123.94  5422.7   126.9  5427.8  127.02
  5432.9  127.76  5463.6  130.02  5483.3  131.31  5523.6   133.3  5584.8  135.95
#Mann= 7 ,-1 , 0
    4151     .05       0  4295.6     .12       0  4640.3      .1       0
  4992.9     .05       0  4996.9      .1       0  5233.8     .12       0
  5463.6     .05       0
Bank Sta=4992.9,4996.9
XS Rating Curve= 0 ,0
Exp/Cntr=0.3,0.1

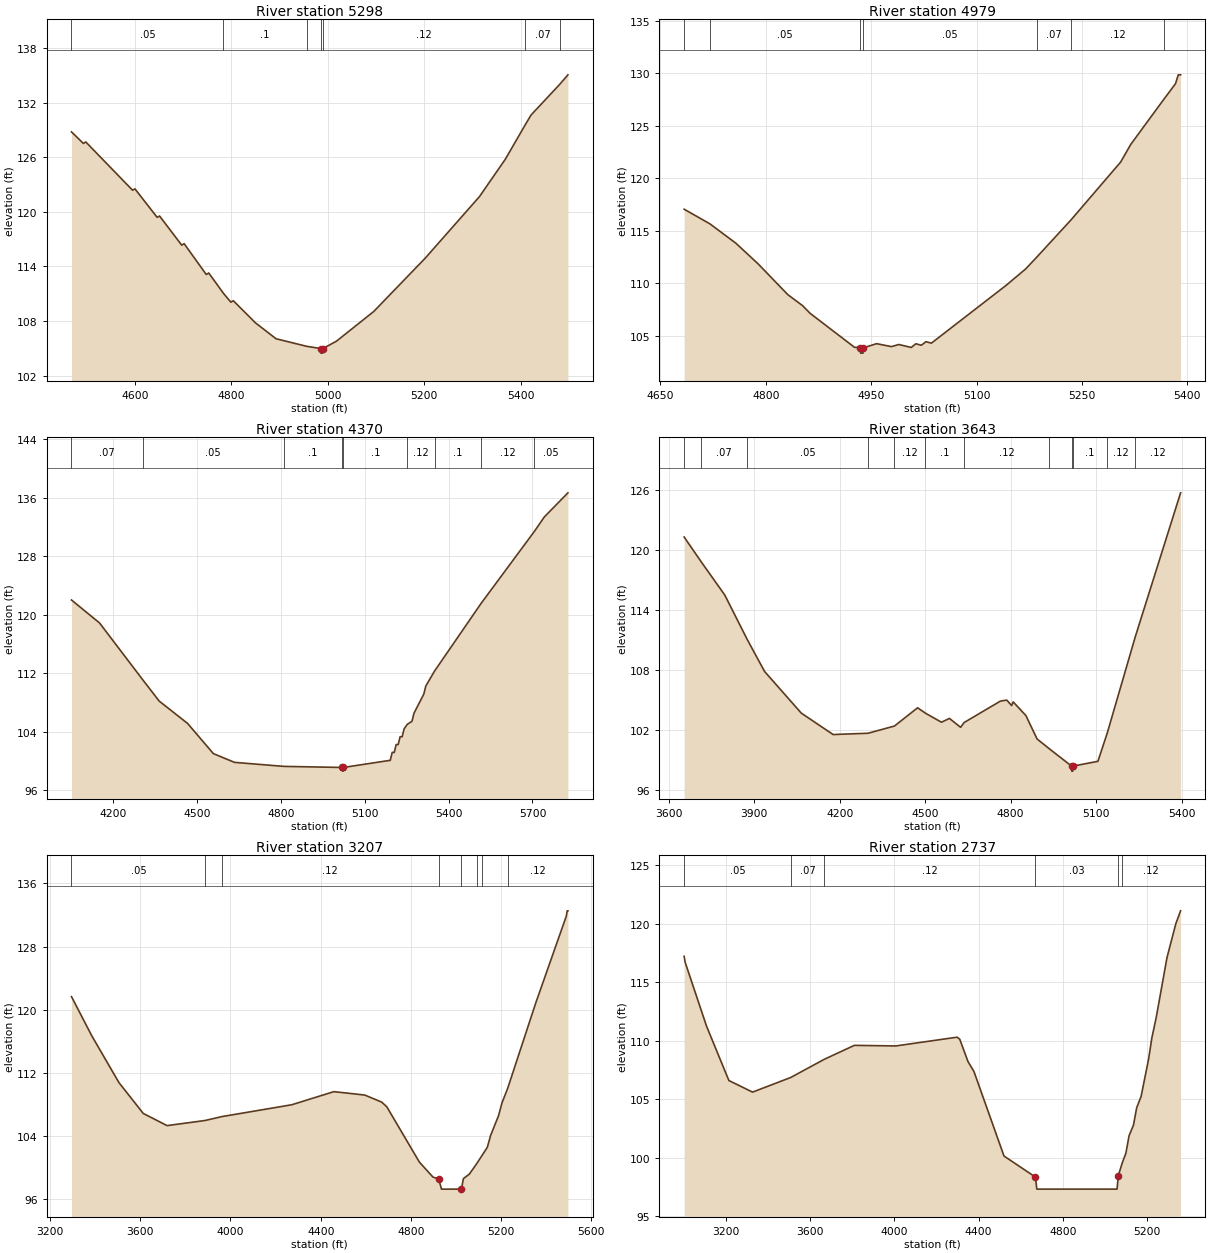
Type RM Length L Ch R = 1 ,5298    ,319,319,319
BEGIN DESCRIPTION:
Mapping XS f8e5e5bc
END DESCRIPTION:
XS GIS Cut Line= 3
      2548954.55     13479801.07      2549044.82     13479349.68
      2548829.78     13478822.48
#Sta/Elev= 30
  4468.3  128.78  4492.9  127.51    4498  127.67  4594.9  122.37    4600  122.51
  4645.9  119.39    4651  119.53  4696.9  116.33    4702  116.49  4747.9   113.1
    4753  113.27  4783.4  111.04  4798.9  110.06    4804  110.22  4849.9  107.79
  4892.6  106.04  4956.1  105.21  4985.7  104.96  4985.9  104.46  4989.4  104.46
  4989.7  104.96  5017.8  105.77  5095.3  109.04  5202.2  114.91  5314.6  121.67
  5368.1  125.77  5409.7  129.58  5421.5  130.63  5481.4  134.03    5498  135.05
#Mann= 7 ,-1 , 0
  4468.3     .05       0  4783.4      .1       0  4956.1     .12       0
  4985.7     .05       0  4989.7     .12       0  5409.7     .07       0
  5481.4     .05       0
Bank Sta=4985.7,4989.7
XS Rating Curve= 0 ,0
Exp/Cntr=0.3,0.1

Type RM Length L Ch R = 1 ,4979    ,609,609,609
BEGIN DESCRIPTION:
TRIB 4 TO COLETO CREEK 5.0
END DESCRIPTION:
XS GIS Cut Line= 3
      2549374.98     13479424.95        2549275.       13479125.
        2549025.     13478824.99
#Sta/Elev= 30
  4683.8  117.05  4720.6  115.65  4757.5  113.81  4789.2  111.84  4831.3  108.92
  4852.4  107.87  4862.9  107.15  4926.2  103.91  4934.7  103.85    4935  103.35
  4938.5  103.35  4938.7  103.85  4957.8  104.25  4978.9  103.97  4989.4  104.17
  5007.1  103.89  5013.6  104.24  5021.5   104.1    5028  104.44  5035.8   104.3
  5142.5  109.82  5169.9  111.36  5186.1  112.51  5234.9  116.06  5305.2  121.54
  5319.5  123.21  5366.3  127.48  5383.3     129  5387.2  129.84  5390.5  129.84
#Mann= 7 ,-1 , 0
  4683.8     .07       0  4720.6     .05       0  4934.7     .05       0
  4938.7     .05       0  5186.1     .07       0  5234.9     .12       0
  5366.3     .07       0
Bank Sta=4934.7,4938.7
XS Rating Curve= 0 ,0
Exp/Cntr=0.3,0.1

Type RM Length L Ch R = 1 ,4370    ,727,727,727
BEGIN DESCRIPTION:
Mapping XS e3900dc5
END DESCRIPTION:
XS GIS Cut Line= 3
      2549412.86       13479565.      2549725.38     13478801.07
      2549059.38      13478121.2
#Sta/Elev= 30
  4049.9  121.99  4150.3  118.85  4304.5   111.1  4363.9  108.16  4465.4  105.11
  4557.7  100.98  4633.3   99.78  4809.4   99.23  5019.3   99.08  5019.6   98.58
  5023.1   98.58  5023.3   99.08    5191  100.06    5198  101.15  5205.2  101.13
  5212.2  102.22  5219.3  102.21  5226.3  103.29  5233.5  103.28  5240.5  104.36
  5251.6  104.97  5268.8   105.4  5275.8  106.49  5311.2  109.13  5318.2  110.22
  5349.4  112.26  5515.9  121.51  5706.8  131.37  5742.5  133.35    5827  136.65
#Mann= 9 ,-1 , 0
  4049.9     .07       0  4304.5     .05       0  4809.4      .1       0
  5019.3     .05       0  5023.3      .1       0  5251.6     .12       0
  5349.4      .1       0  5515.9     .12       0  5706.8     .05       0
Bank Sta=5019.3,5023.3
XS Rating Curve= 0 ,0
Exp/Cntr=0.3,0.1

Type RM Length L Ch R = 1 ,3643    ,436,436,436
BEGIN DESCRIPTION:
TRIB 4 TO COLETO CREEK 4.0
END DESCRIPTION:
XS GIS Cut Line= 3
      2549524.99     13479625.02        2550125.       13478425.
        2550125.     13478024.96
#Sta/Elev= 30
  3654.4  121.27  3714.2   118.8    3797  115.48  3875.1  111.08  3936.7  107.85
  4065.3   103.7  4177.1  101.56  4299.7  101.69  4392.3  102.41  4473.4  104.23
  4501.1  103.69  4557.2  102.79  4585.2  103.17  4624.3  102.28  4636.7  102.76
  4764.1   104.9  4786.4     105  4803.2  104.45  4808.8  104.82  4853.5  103.45
  4892.6  101.12    4936  100.13  5013.8   98.41  5014.1   97.91    5018   97.91
  5018.3   98.41  5106.1   98.89  5138.8  101.71  5237.4  111.34  5396.1  125.68
#Mann= 12 ,-1 , 0
  3654.4     .05       0  3714.2     .07       0  3875.1     .05       0
  4299.7     .07       0  4392.3     .12       0  4501.1      .1       0
  4636.7     .12       0    4936      .1       0  5013.8     .05       0
  5018.3      .1       0  5138.8     .12       0  5237.4     .12       0
Bank Sta=5013.8,5018.3
XS Rating Curve= 0 ,0
Exp/Cntr=0.3,0.1

Type RM Length L Ch R = 1 ,3207    ,470,470,470
BEGIN DESCRIPTION:
TRIB 4 TO COLETO CREEK 3.0
END DESCRIPTION:
XS GIS Cut Line= 3
      2549824.99     13479875.03        2550525.       13478325.
      2550224.98     13477924.97
#Sta/Elev= 30
  3295.2  121.67  3384.4  116.75  3505.5  110.79  3613.4  106.88    3719  105.34
  3887.8  105.99  3961.6  106.48  4271.8  107.98  4458.3  109.64  4595.3  109.21
  4670.1  108.32  4693.2  107.72  4837.5  100.72  4897.2   98.84  4923.3   98.55
  4935.4    97.3  5024.1    97.3  5032.4   98.62  5059.5   99.22  5091.9  100.54
  5112.9  101.46  5138.7   102.6  5153.3   104.1  5188.7  106.62  5203.3  108.19
  5228.8  110.05  5353.3  120.86  5488.7  131.85  5492.8  132.53    5496  132.53
#Mann= 8 ,-1 , 0
  3295.2     .05       0  3887.8     .07       0  3961.6     .12       0
  4923.3     .03       0  5024.1     .03       0  5091.9     .12       0
  5112.9     .12       0  5228.8     .12       0
Bank Sta=4923.3,5024.1
XS Rating Curve= 0 ,0
Exp/Cntr=0.3,0.1

Type RM Length L Ch R = 1 ,2737    ,810,810,810
BEGIN DESCRIPTION:
TRIB 4 TO COLETO CREEK 2.0
END DESCRIPTION:
XS GIS Cut Line= 3
      2549996.21     13479870.51        2550875.       13478075.
      2550674.99     13477774.99
#Sta/Elev= 30
  3000.7  117.22  3005.3  116.72    3107  111.25  3213.4  106.59    3326   105.6
  3507.1  106.85    3666   108.4  3809.7   109.6  4006.7  109.55  4298.3   110.3
  4310.5  110.13  4349.9  108.21    4378  107.37    4521  100.13  4670.6   98.33
  4676.9    97.3  5058.3    97.3  5064.3   98.46  5082.4   99.51  5100.4  100.38
  5115.4  101.87  5136.4  102.78  5151.5  104.26  5172.5  105.22  5208.6  108.46
  5223.6  110.23  5244.6     112  5295.7  117.11  5337.8  120.02  5360.3  121.11
#Mann= 6 ,-1 , 0
  3000.7     .05       0  3507.1     .07       0    3666     .12       0
  4670.6     .03       0  5064.3     .03       0  5082.4     .12       0
Bank Sta=4670.6,5064.3
XS Rating Curve= 0 ,0
Exp/Cntr=0.3,0.1

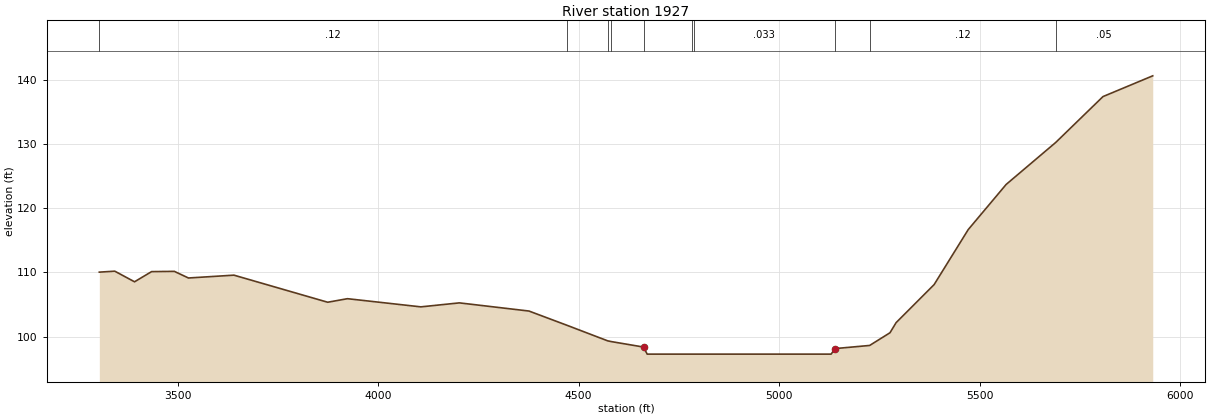
Type RM Length L Ch R = 1 ,1927    ,0,0,0
BEGIN DESCRIPTION:
TRIB 4 TO COLETO CREEK 1.0
END DESCRIPTION:
XS GIS Cut Line= 4
      2550751.14      13478995.2      2551209.45     13478495.23
      2551430.41     13477568.73      2550582.31     13477046.16
#Sta/Elev= 30
  3304.7  110.05  3343.2   110.2  3392.5  108.55    3435  110.13  3491.8  110.17
  3526.9  109.14  3640.4  109.58  3874.1  105.37  3923.4  105.92  4106.5  104.65
  4202.5  105.27  4376.1     104  4471.5  101.77  4572.2   99.37  4581.3   99.25
  4661.7    98.4  4670.9    97.3  4782.8    97.3  4787.4    97.3  5129.7    97.3
  5139.1   98.16  5225.7   98.65  5276.3  100.62  5291.7   102.2  5386.4  108.11
  5471.5  116.67  5566.1  123.69  5689.7  130.22  5807.5  137.35  5931.6  140.58
#Mann= 10 ,-1 , 0
  3304.7     .12       0  4471.5     .12       0  4572.2    .033       0
  4581.3     .12       0  4661.7     .03       0  4782.8    .033       0
  4787.4    .033       0  5139.1    .033       0  5225.7     .12       0
  5689.7     .05       0
Bank Sta=4661.7,5139.1
XS Rating Curve= 0 ,0
Exp/Cntr=0.3,0.1

Chan Stop Cuts=-1
Use User Specified Reach Order=0
Composite Channel Slope=5