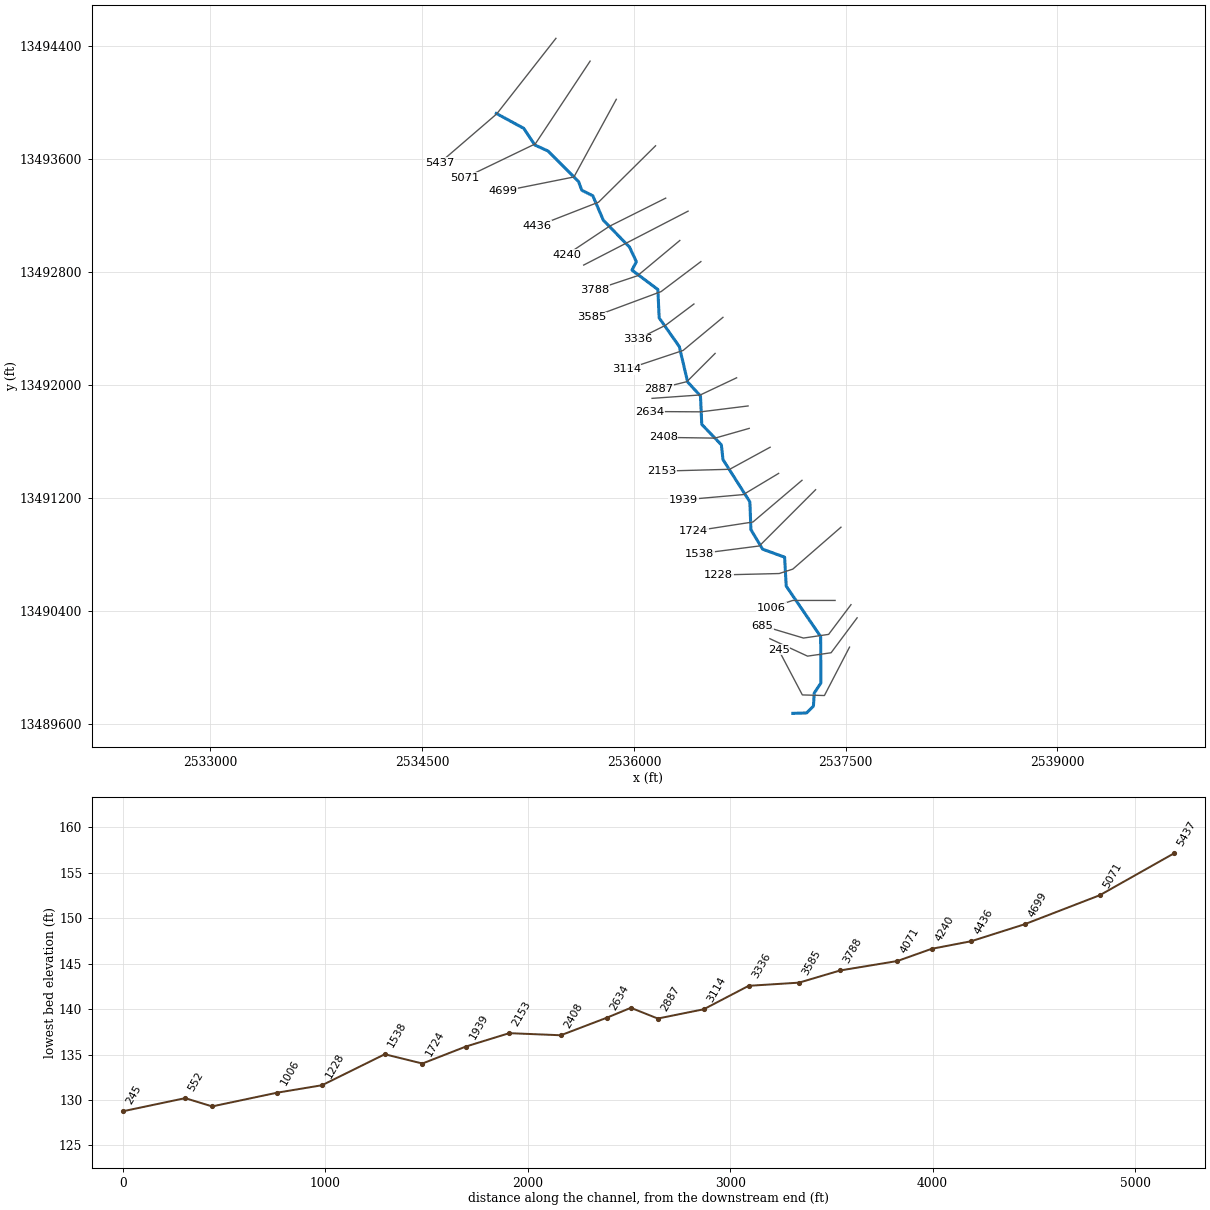
--- TRIB 4 TO HOG THIEF CREEK.prj (project) ---

Proj Title=TRIB 4 TO HOG THIEF CREEK Base Level Engineering
Current Plan=p01
Default Exp/Contr=0.3,0.1
English Units
Geom File=g01
Flow File=f01
Plan File=p01
Y Axis Title=Elevation
X Axis Title(PF)=Main Channel Distance
X Axis Title(XS)=Station
BEGIN DESCRIPTION:
TRIB 4 TO HOG THIEF CREEK
END DESCRIPTION:
DSS Export Rating Curves= 0
DSS Export Rating Curve Sorted= 0
DSS Export Volume Flow Curves= 0
DXF OffsetX= 0
DXF OffsetY= 0
DXF ScaleX= 1
DXF ScaleY= 10

--- TRIB 4 TO HOG THIEF CREEK.p01 (plan) ---

Plan Title=Multiple Run
Short Identifier=Multiple
Geom File=g01
Flow File=f01
Subcritical Flow
K Sum by GR= 0
Std Step Tol= 0.01
Critical Tol= 0.01
Num of Std Step Trials= 20
Max Error Tol= 0.3
Flow Tol Ratio= 0.001
Split Flow NTrial= 30
Split Flow Tol= 0.02
Split Flow Ratio= 0.02
Log Output Level= 0
Friction Slope Method= 1
Unsteady Friction Slope Method= 2
Unsteady Bridges Friction Slope Method= 1
Parabolic Critical Depth
Global Vel Dist=  1 , 1 , 1
Global Log Level= 0
CheckData=True
Encroach Param= -1, 0, 0, 0
BEGIN DESCRIPTION:
Multiple Run
END DESCRIPTION:

--- TRIB 4 TO HOG THIEF CREEK.f01 (steady flow) ---

Flow Title=Multiple
Number of Profiles=7
Profile Names=10-year,25-year,50-year,1pct_min,100-year,1pct_plu,500-year
River Rch & RM= TRIB 4 TO HOG TH,Reach-1,5437
     293     442     568     355     708    1412    1082
River Rch & RM= TRIB 4 TO HOG TH,Reach-1,3336
     452     701     918     583    1163    2320    1841
Boundary for River Rch & Prof#=TRIB 4 TO HOG TH,Reach-1,1
Up Type=0
Dn Type=3
Dn Slope=0.005
Boundary for River Rch & Prof#=TRIB 4 TO HOG TH,Reach-1,2
Up Type=0
Dn Type=3
Dn Slope=0.005
Boundary for River Rch & Prof#=TRIB 4 TO HOG TH,Reach-1,3
Up Type=0
Dn Type=3
Dn Slope=0.005
Boundary for River Rch & Prof#=TRIB 4 TO HOG TH,Reach-1,4
Up Type=0
Dn Type=3
Dn Slope=0.005
Boundary for River Rch & Prof#=TRIB 4 TO HOG TH,Reach-1,5
Up Type=0
Dn Type=3
Dn Slope=0.005
Boundary for River Rch & Prof#=TRIB 4 TO HOG TH,Reach-1,6
Up Type=0
Dn Type=3
Dn Slope=0.005
Boundary for River Rch & Prof#=TRIB 4 TO HOG TH,Reach-1,7
Up Type=0
Dn Type=3
Dn Slope=0.005

--- TRIB 4 TO HOG THIEF CREEK.g01 (geometry) ---

Geom Title=Existing Conditions
Program Version=4.10

River Reach=TRIB 4 TO HOG TH,Reach-1
Reach XY= 30
        2535025.       13493925.      2535219.39     13493819.41
      2535298.12     13493701.28      2535391.67     13493658.35
      2535608.27     13493441.48      2535630.65     13493380.63
      2535708.43     13493342.02      2535783.14     13493168.94
      2535969.19     13492977.29      2536017.22     13492874.91
      2535986.23     13492814.98      2536169.64      13492677.7
      2536178.75     13492476.55      2536321.38      13492273.5
      2536380.54     13492022.58      2536471.45     13491923.53
      2536480.46     13491722.55      2536619.48     13491577.43
      2536630.77     13491472.68      2536821.25     13491173.45
      2536828.75     13490976.55      2536911.34     13490838.26
      2537067.32     13490781.52      2537078.75     13490576.55
      2537322.76     13490219.07      2537324.48     13489890.22
      2537277.36     13489819.02       2537271.5     13489726.26
      2537223.88     13489678.26        2537125.       13489675.

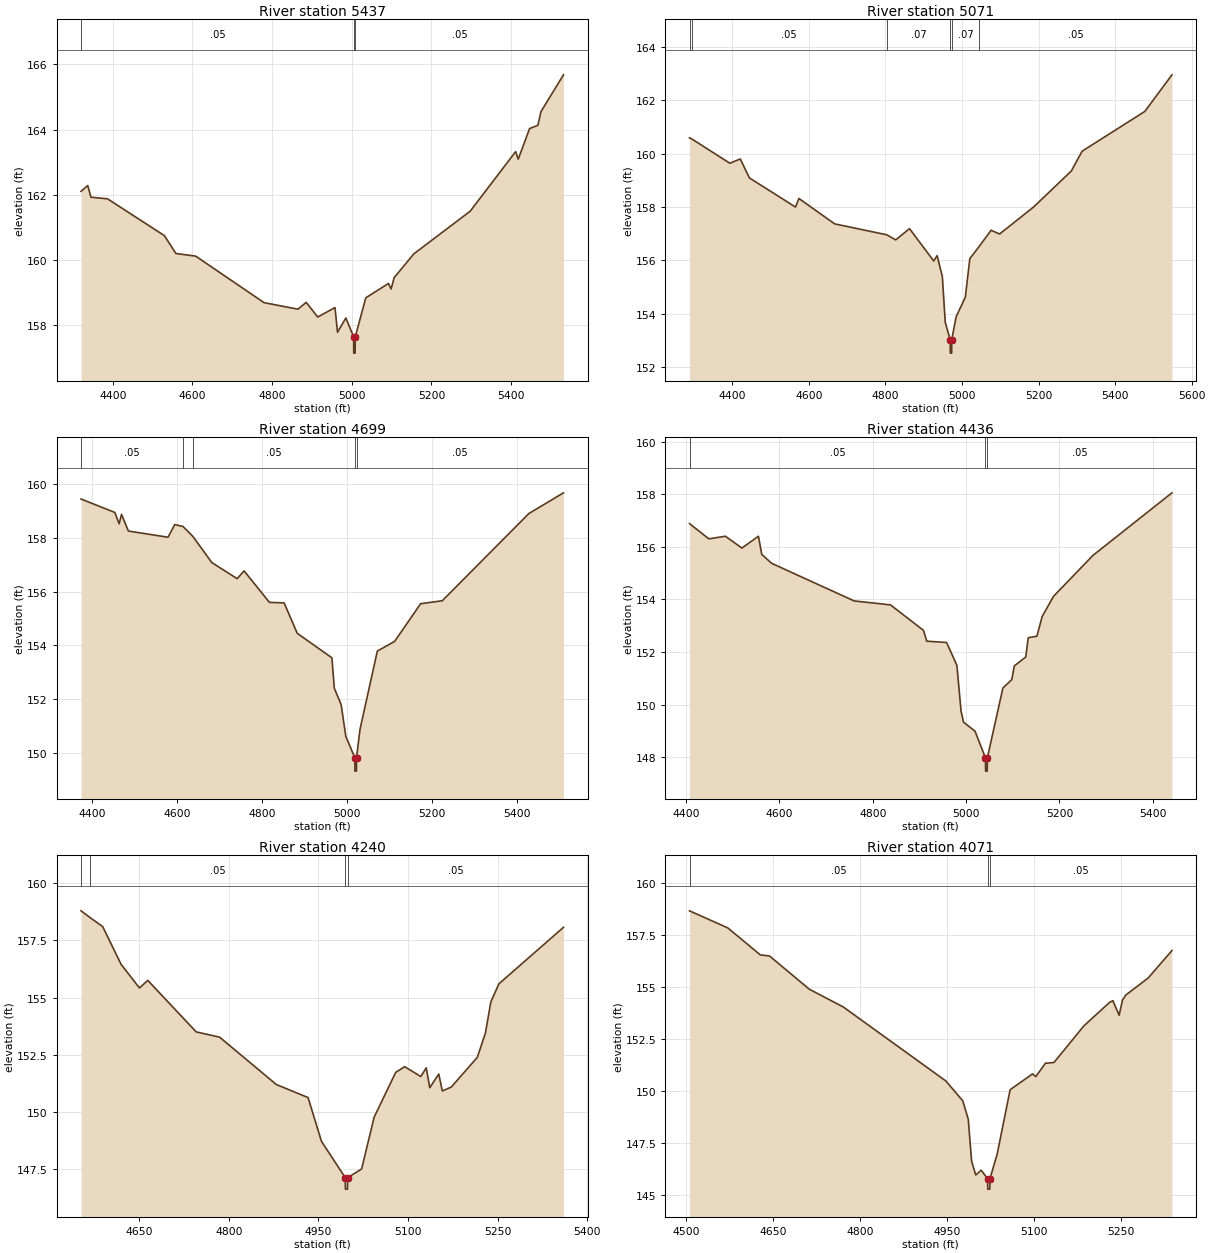
Type RM Length L Ch R = 1 ,5437    ,366,366,366
BEGIN DESCRIPTION:
TRIB 4 TO HOG THIEF CREEK 11.0
END DESCRIPTION:
XS GIS Cut Line= 3
       2535447.4     13494457.06      2535028.04      13493921.9
      2534624.98     13493574.98
#Sta/Elev= 30
  4320.1   162.1  4336.9  162.28    4345  161.92  4386.7  161.87  4529.5  160.74
  4558.4  160.19  4608.1  160.11  4779.9  158.68  4864.9  158.48  4885.7  158.69
  4914.6  158.24  4957.9  158.53  4964.3  157.77  4985.2  158.21  5004.8  157.63
    5005  157.13  5008.5  157.13  5008.8  157.63  5035.3  158.83  5092.3  159.27
  5098.9   159.1  5106.6  159.45    5156  160.18  5297.5  161.49  5411.6  163.32
  5418.2  163.09  5446.7  164.03  5467.6  164.13  5475.3  164.55  5531.8  165.68
#Mann= 3 ,-1 , 0
  4320.1     .05       0  5004.8     .05       0  5008.8     .05       0
Bank Sta=5004.8,5008.8
XS Rating Curve= 0 ,0
Exp/Cntr=0.3,0.1

Type RM Length L Ch R = 1 ,5071    ,372,372,372
BEGIN DESCRIPTION:
Mapping XS 39a4cefd
END DESCRIPTION:
XS GIS Cut Line= 3
      2535689.63     13494295.66      2535301.59     13493709.69
      2534799.45     13493467.73
#Sta/Elev= 30
  4288.3  160.59  4294.2  160.55  4393.7  159.64    4421   159.8  4444.8  159.09
  4565.1     158  4574.2  158.32  4667.4  157.37  4803.8  156.96  4826.9  156.77
    4863  157.19  4926.2  155.98  4935.2  156.18  4948.8  155.39  4956.3  153.69
  4969.3  153.03  4969.6  152.53  4973.1  152.53  4973.3  153.03  4984.7  153.89
  5008.7  154.62  5020.6  156.07  5044.8  156.52  5076.1  157.13  5098.3  156.99
  5187.1     158  5285.7  159.35  5313.8  160.09  5477.7  161.58  5548.5  162.95
#Mann= 6 ,-1 , 0
  4288.3     .07       0  4294.2     .05       0  4803.8     .07       0
  4969.3     .05       0  4973.3     .07       0  5044.8     .05       0
Bank Sta=4969.3,4973.3
XS Rating Curve= 0 ,0
Exp/Cntr=0.3,0.1

Type RM Length L Ch R = 1 ,4699    ,263,263,263
BEGIN DESCRIPTION:
TRIB 4 TO HOG THIEF CREEK 10.0
END DESCRIPTION:
XS GIS Cut Line= 3
        2535875.     13494025.01        2535575.       13493475.
      2535075.01       13493375.
#Sta/Elev= 30
  4373.7  159.44  4453.4  158.94  4463.4  158.52  4469.1  158.87  4485.2  158.25
  4578.7  158.02  4594.4  158.49  4613.8  158.42  4637.2  158.05  4681.7  157.08
  4741.5  156.48  4757.7  156.77  4817.5   155.6  4852.1  155.58    4883  154.45
  4964.6  153.54  4970.3  152.41  4986.4   151.8  4997.4  150.62  5018.6  149.83
  5018.9  149.33  5022.4  149.33  5022.6  149.83  5030.8  150.88  5071.6  153.79
  5112.4  154.15  5173.6  155.55  5224.6  155.66  5428.5   158.9  5510.1  159.67
#Mann= 5 ,-1 , 0
  4373.7     .05       0  4613.8     .07       0  4637.2     .05       0
  5018.6     .05       0  5022.6     .05       0
Bank Sta=5018.6,5022.6
XS Rating Curve= 0 ,0
Exp/Cntr=0.3,0.1

Type RM Length L Ch R = 1 ,4436    ,196,196,196
BEGIN DESCRIPTION:
Mapping XS e284edaf
END DESCRIPTION:
XS GIS Cut Line= 3
      2536153.13     13493695.78       2535749.5     13493296.49
       2535315.5     13493127.23
#Sta/Elev= 30
  4407.5  156.88  4449.1   156.3  4484.5   156.4  4519.8  155.95  4555.2   156.4
  4562.3  155.71  4583.5  155.37  4760.3  153.94  4838.1  153.79  4908.8  152.82
  4915.8  152.41  4958.3  152.36  4980.4  151.49  4989.3  149.75  4994.7  149.33
  5019.2  148.99  5041.6  147.97  5041.9  147.47  5045.4  147.47  5045.6  147.97
  5078.9  150.63    5098  150.95  5103.4  151.47  5127.9  151.81  5133.2  152.54
  5151.8   152.6  5163.1  153.35  5187.6  154.12  5271.8  155.67  5441.1  158.05
#Mann= 3 ,-1 , 0
  4407.5     .05       0  5041.6     .05       0  5045.6     .05       0
Bank Sta=5041.6,5045.6
XS Rating Curve= 0 ,0
Exp/Cntr=0.3,0.1

Type RM Length L Ch R = 1 ,4240    ,169,169,169
BEGIN DESCRIPTION:
TRIB 4 TO HOG THIEF CREEK 9.0
END DESCRIPTION:
XS GIS Cut Line= 3
      2536224.97     13493324.99        2535825.       13493125.
      2535525.03     13492925.02
#Sta/Elev= 30
  4552.6  158.79  4566.9  158.51  4588.9   158.1  4619.7  156.45  4650.4  155.42
  4664.4  155.75  4745.4   153.5  4784.6  153.27  4879.6   151.2  4932.7  150.63
  4955.1  148.72    4995  147.13  4995.2  146.63  4998.7  146.63    4999  147.13
  5022.3  147.51  5043.4  149.78  5079.4  151.73  5094.4  151.98  5121.5  151.55
  5130.5  151.93  5136.5  151.06  5151.5  151.66  5157.5  150.92  5172.5  151.09
  5216.1  152.39  5229.6  153.45  5238.7  154.81  5252.2   155.6  5360.3  158.07
#Mann= 4 ,-1 , 0
  4552.6     .07       0  4566.9     .05       0    4995     .05       0
    4999     .05       0
Bank Sta=4995,4999
XS Rating Curve= 0 ,0
Exp/Cntr=0.3,0.1

Type RM Length L Ch R = 1 ,4071    ,283,283,283
BEGIN DESCRIPTION:
Mapping XS 88e393a3
END DESCRIPTION:
XS GIS Cut Line= 3
      2536383.65     13493232.89      2535987.78     13493028.01
      2535644.05     13492850.93
#Sta/Elev= 30
  4505.8  158.67  4571.8  157.85  4628.1  156.55  4643.8   156.5  4712.6   154.9
    4771  154.05  4948.1  150.49  4977.2  149.54  4986.8  148.65  4992.5  146.64
  4999.7  145.97    5009   146.2  5020.2  145.79  5020.4  145.29  5023.9  145.29
  5024.2  145.79  5036.8  146.99    5059  150.07  5097.7  150.83  5103.3   150.7
  5119.8  151.34  5134.7  151.38  5186.3  153.14  5230.7  154.27  5236.3  154.35
  5247.1  153.65  5252.8  154.37  5258.5  154.62  5297.2  155.44  5338.2  156.76
#Mann= 3 ,-1 , 0
  4505.8     .05       0  5020.2     .05       0  5024.2     .05       0
Bank Sta=5020.2,5024.2
XS Rating Curve= 0 ,0
Exp/Cntr=0.3,0.1

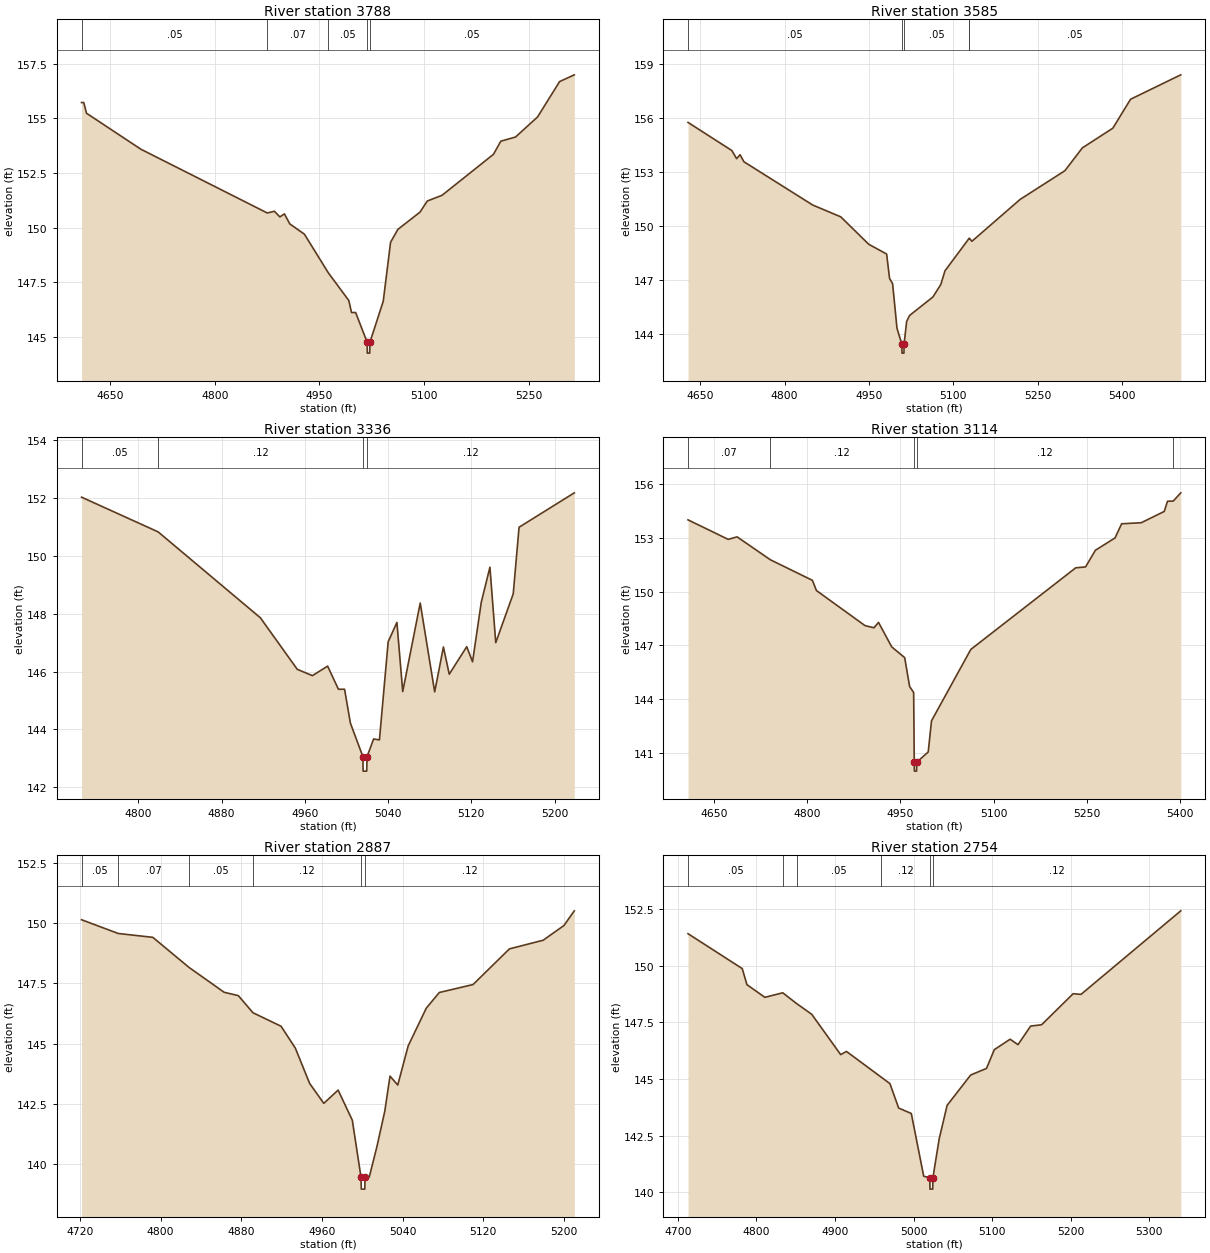
Type RM Length L Ch R = 1 ,3788    ,203,203,203
BEGIN DESCRIPTION:
TRIB 4 TO HOG THIEF CREEK 8.0
END DESCRIPTION:
XS GIS Cut Line= 3
      2536324.99     13493024.99        2536025.       13492775.
      2535725.02     13492675.01
#Sta/Elev= 30
  4608.9  155.73  4612.1  155.73    4616  155.24  4694.1  153.59  4875.3  150.67
  4885.5  150.75  4893.3  150.49  4899.8  150.63  4907.6  150.17  4928.5   149.7
  4962.6  147.94  4992.2  146.66  4996.1  146.11    5002  146.11  5018.5  144.75
  5018.7  144.25  5022.2  144.25  5022.5  144.75  5041.6  146.63  5052.1  149.33
  5062.6  149.92  5094.3  150.71  5104.8  151.22  5125.9  151.48  5199.7  153.36
  5210.2  153.96  5231.3  154.15  5262.9  155.07  5294.5  156.69  5315.6     157
#Mann= 5 ,-1 , 0
  4608.9     .05       0  4875.3     .07       0  4962.6     .05       0
  5018.5     .05       0  5022.5     .05       0
Bank Sta=5018.5,5022.5
XS Rating Curve= 0 ,0
Exp/Cntr=0.3,0.1

Type RM Length L Ch R = 1 ,3585    ,249,249,249
BEGIN DESCRIPTION:
Mapping XS 102fe0c4
END DESCRIPTION:
XS GIS Cut Line= 3
      2536474.34     13492875.49      2536192.21     13492662.81
       2535701.8     13492480.53
#Sta/Elev= 30
  4628.3  155.76  4706.4  154.19  4714.7  153.74  4720.9  153.96  4727.7  153.57
    4850  151.16    4900   150.5  4949.9  148.97  4981.6  148.43  4986.8  147.07
  4992.2  146.78    5000   144.3  5008.6  143.41  5008.9  142.91  5012.4  142.91
  5012.6  143.41  5017.2  144.68  5022.5  145.01    5064  146.04  5077.9  146.73
  5085.3  147.49  5128.5  149.31  5128.9   149.3  5133.3  149.14    5219  151.47
  5298.7  153.07  5329.7  154.34    5384  155.44  5415.5  157.05  5504.8  158.41
#Mann= 5 ,-1 , 0
  4628.3     .05       0  5008.6     .05       0  5012.6     .05       0
  5128.5     .12       0  5128.9     .05       0
Bank Sta=5008.6,5012.6
XS Rating Curve= 0 ,0
Exp/Cntr=0.3,0.1

Type RM Length L Ch R = 1 ,3336    ,222,222,222
BEGIN DESCRIPTION:
TRIB 4 TO HOG THIEF CREEK 7.0
END DESCRIPTION:
XS GIS Cut Line= 3
        2536425.       13492575.        2536225.       13492425.
      2536025.01       13492325.
#Sta/Elev= 30
  4745.4  152.03    4819  150.83  4917.3  147.86  4952.7  146.08  4967.3  145.86
  4981.9  146.19  4992.3  145.39  4998.2  145.39  5003.8  144.22  5015.8  143.06
    5016  142.56  5019.5  142.56  5019.8  143.06  5026.1  143.67  5031.7  143.64
  5040.1  147.03  5048.5   147.7  5054.1  145.31  5070.9  148.37  5084.8   145.3
  5093.2  146.85  5098.8  145.91  5115.6  146.86  5121.2  146.34  5129.6   148.4
  5137.9  149.61  5143.5     147  5160.3  148.69  5165.9  150.99    5219  152.18
#Mann= 4 ,-1 , 0
  4745.4     .05       0    4819     .12       0  5015.8     .05       0
  5019.8     .12       0
Bank Sta=5015.8,5019.8
XS Rating Curve= 0 ,0
Exp/Cntr=0.3,0.1

Type RM Length L Ch R = 1 ,3114    ,227,227,227
BEGIN DESCRIPTION:
Mapping XS 2d9cb6b6
END DESCRIPTION:
XS GIS Cut Line= 3
      2536630.58     13492480.52      2536348.46     13492246.14
      2535944.77     13492111.58
#Sta/Elev= 30
  4608.7  154.02  4673.3  152.93  4687.6  153.07  4741.1  151.79  4808.7  150.64
  4815.2  150.07  4893.3  148.11  4907.7  147.99    4915  148.29  4936.3  146.92
  4957.1  146.32    4965  144.71  4971.5  144.37  4972.5  140.48  4972.7  139.98
  4976.2  139.98  4976.5  140.48  4994.9  141.05  5000.2  142.79  5063.4  146.78
  5232.1  151.34  5247.9  151.39  5263.7  152.32  5295.3  153.01  5305.9   153.8
  5337.5  153.86  5374.4  154.49  5379.7  155.06  5388.9  155.07    5401  155.53
#Mann= 5 ,-1 , 0
  4608.7     .07       0  4741.1     .12       0  4972.5     .05       0
  4976.5     .12       0  5388.9     .05       0
Bank Sta=4972.5,4976.5
XS Rating Curve= 0 ,0
Exp/Cntr=0.3,0.1

Type RM Length L Ch R = 1 ,2887    ,133,133,133
BEGIN DESCRIPTION:
TRIB 4 TO HOG THIEF CREEK 6.0
END DESCRIPTION:
XS GIS Cut Line= 3
      2536575.02     13492225.02        2536375.       13492025.
      2536175.03     13491975.01
#Sta/Elev= 30
  4721.5  150.14  4757.9  149.57  4792.2  149.41  4828.2  148.16    4863  147.13
  4877.1  146.99  4891.6  146.28  4919.5  145.72  4933.7  144.81  4947.8  143.35
  4961.9  142.52  4976.1  143.07  4990.2  141.82  4998.8  139.46  4999.1  138.96
  5002.6  138.96  5002.8  139.46    5007  139.46  5014.7  140.74  5022.4  142.19
  5027.6  143.65  5035.3  143.28  5045.6   144.9  5063.6  146.47  5076.5  147.12
    5110  147.45  5146.1  148.93  5179.6  149.29  5200.2   149.9  5210.5  150.51
#Mann= 6 ,-1 , 0
  4721.5     .05       0  4757.9     .07       0  4828.2     .05       0
  4891.6     .12       0  4998.8     .05       0  5002.8     .12       0
Bank Sta=4998.8,5002.8
XS Rating Curve= 0 ,0
Exp/Cntr=0.3,0.1

Type RM Length L Ch R = 1 ,2754    ,120,120,120
BEGIN DESCRIPTION:
Mapping XS c6ac1c0c
END DESCRIPTION:
XS GIS Cut Line= 3
      2536727.35     13492052.31      2536470.42     13491930.79
       2536128.3      13491906.6
#Sta/Elev= 30
  4712.9  151.42  4781.9  149.88  4787.9  149.17  4810.7  148.61  4833.5  148.81
  4851.3  148.33  4870.4  147.86  4907.2  146.08  4914.6  146.22  4958.6  145.09
  4969.9   144.8    4981  143.72  4997.1  143.48  5012.9  140.71  5020.6  140.64
  5020.9  140.14  5024.4  140.14  5024.6  140.64  5032.6  142.36  5042.7  143.84
  5072.7  145.18  5092.8  145.47  5102.8   146.3  5122.9  146.76  5132.9  146.52
    5149  147.34    5163   147.4  5203.1  148.77  5213.1  148.74  5340.1  152.43
#Mann= 6 ,-1 , 0
  4712.9     .05       0  4833.5     .12       0  4851.3     .05       0
  4958.6     .12       0  5020.6     .05       0  5024.6     .12       0
Bank Sta=5020.6,5024.6
XS Rating Curve= 0 ,0
Exp/Cntr=0.3,0.1

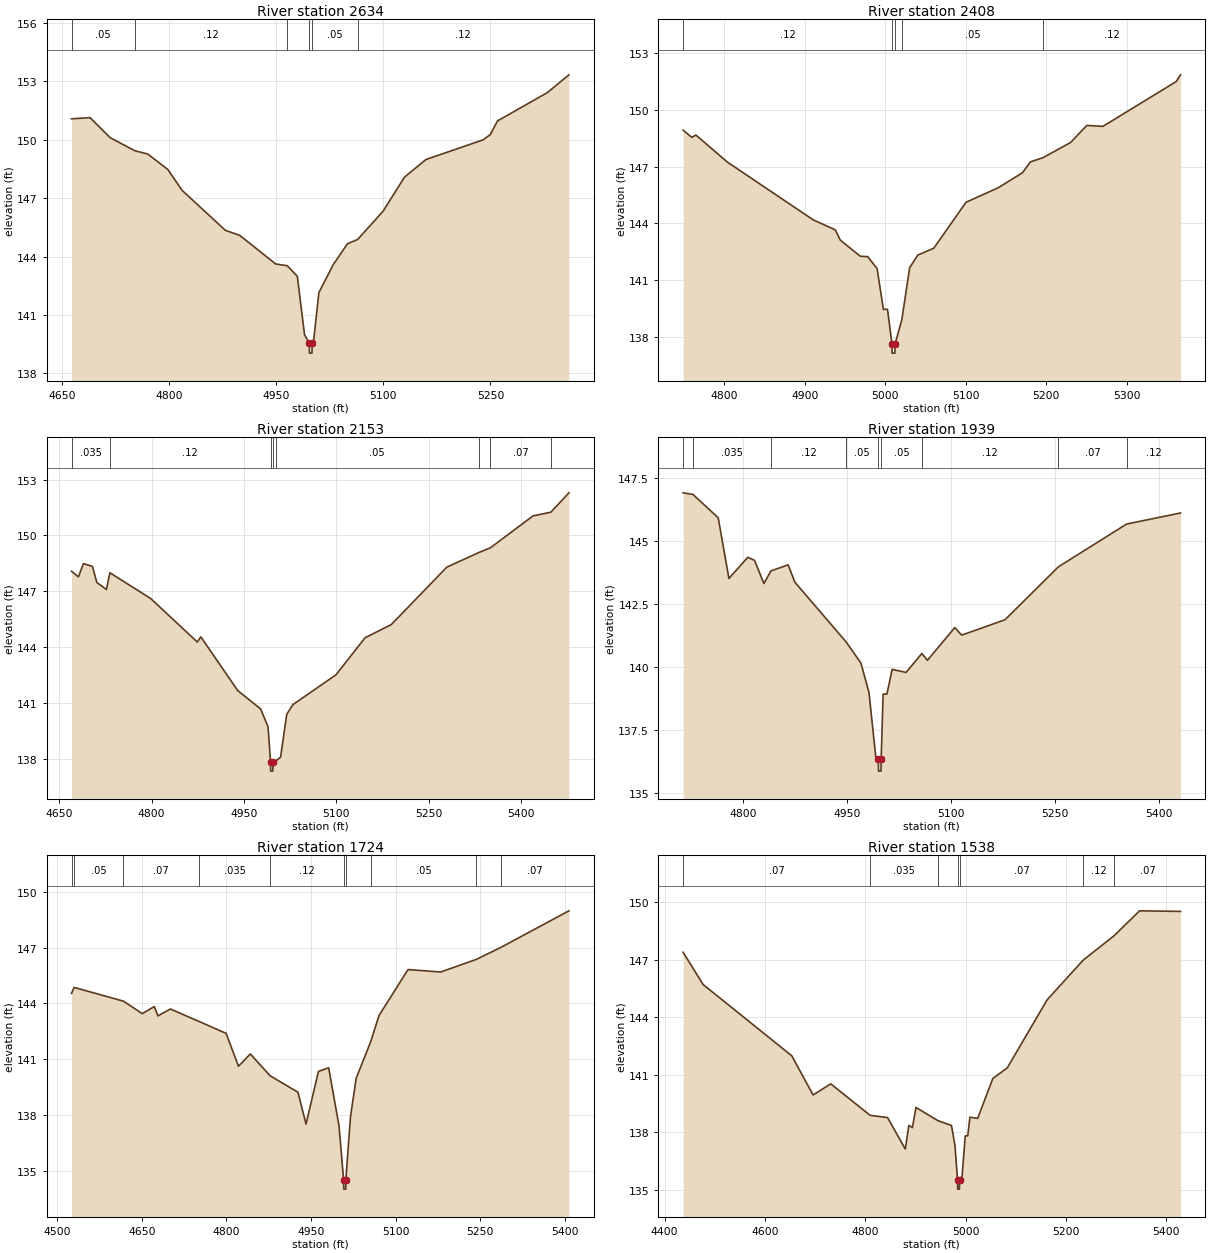
Type RM Length L Ch R = 1 ,2634    ,226,226,226
BEGIN DESCRIPTION:
Mapping XS adfbff9a
END DESCRIPTION:
XS GIS Cut Line= 3
      2536808.73     13491852.81      2536472.83     13491811.14
      2536114.91      13491813.3
#Sta/Elev= 30
  4663.6  151.08  4689.5  151.14  4717.7  150.11  4752.2  149.44  4770.4  149.27
  4798.3  148.48  4818.5   147.4    4879  145.35  4899.1  145.09  4949.5  143.62
  4965.7  143.53  4979.7  142.99  4989.8  139.99  4996.5  139.54  4996.7  139.04
  5000.2  139.04  5000.5  139.54  5002.1  139.54  5009.9  142.15  5029.9  143.58
  5049.9  144.66  5064.2  144.88  5099.9  146.34  5129.9  148.09  5159.9  148.99
  5239.9     150  5249.9  150.27  5259.9  150.97  5329.9  152.43    5360  153.34
#Mann= 6 ,-1 , 0
  4663.6     .05       0  4752.2     .12       0  4965.7     .05       0
  4996.5     .05       0  5000.5     .05       0  5064.2     .12       0
Bank Sta=4996.5,5000.5
XS Rating Curve= 0 ,0
Exp/Cntr=0.3,0.1

Type RM Length L Ch R = 1 ,2408    ,255,255,255
BEGIN DESCRIPTION:
TRIB 4 TO HOG THIEF CREEK 5.0
END DESCRIPTION:
XS GIS Cut Line= 3
      2536816.62     13491693.97        2536575.       13491625.
      2536208.61     13491630.14
#Sta/Elev= 30
    4749  148.93  4759.7  148.55  4764.9  148.67  4803.9  147.24  4910.5  144.18
  4937.9  143.65  4944.3   143.1  4969.1  142.25  4978.2  142.23  4989.9   141.6
  4997.7  139.44  5002.8  139.44  5008.3  137.62  5008.5  137.12    5012  137.12
  5012.3  137.62  5020.6  138.89  5030.3  141.64  5040.3  142.31  5060.3  142.68
  5100.3  145.11  5140.3  145.88  5170.3  146.67  5180.3  147.25  5195.9  147.47
  5230.3  148.28  5250.3  149.18  5270.3  149.13  5361.2   151.5  5366.7  151.86
#Mann= 5 ,-1 , 0
    4749     .12       0  5008.3     .05       0  5012.3     .12       0
  5020.6     .05       0  5195.9     .12       0
Bank Sta=5008.3,5012.3
XS Rating Curve= 0 ,0
Exp/Cntr=0.3,0.1

Type RM Length L Ch R = 1 ,2153    ,214,214,214
BEGIN DESCRIPTION:
Mapping XS 1abed0ad
END DESCRIPTION:
XS GIS Cut Line= 3
      2536964.81      13491560.4      2536678.32     13491404.13
      2536196.54     13491391.11
#Sta/Elev= 30
  4669.9  148.08  4681.1  147.78  4689.2  148.49  4703.9  148.34    4711  147.48
  4726.6   147.1  4732.2     148  4798.4  146.62  4874.3  144.28    4880  144.56
  4939.8  141.68  4977.2  140.69  4989.2  139.73  4993.3  137.85  4993.5  137.35
    4997  137.35  4997.3  137.85  5001.7  137.89  5009.6   138.1  5019.6   140.4
  5029.6  140.92  5099.6  142.52  5146.9  144.51  5189.6  145.22  5279.7   148.3
  5331.4  149.08  5350.6  149.34  5419.7  151.05  5448.8  151.25  5478.2  152.29
#Mann= 8 ,-1 , 0
  4669.9    .035       0  4732.2     .12       0  4993.3     .05       0
  4997.3     .12       0  5001.7     .05       0  5331.4     .12       0
  5350.6     .07       0  5448.8     .12       0
Bank Sta=4993.3,4997.3
XS Rating Curve= 0 ,0
Exp/Cntr=0.3,0.1

Type RM Length L Ch R = 1 ,1939    ,215,215,215
BEGIN DESCRIPTION:
TRIB 4 TO HOG THIEF CREEK 4.0
END DESCRIPTION:
XS GIS Cut Line= 3
      2537025.01     13491375.01        2536775.       13491225.
      2536350.42     13491187.45
#Sta/Elev= 30
  4713.1  146.93  4727.1  146.87  4763.7  145.94  4779.2  143.53  4806.4  144.37
  4816.1  144.25  4829.7  143.33  4839.8  143.83  4864.7  144.07  4874.4  143.38
  4948.3  141.01  4969.7  140.17  4981.3     139  4991.1  136.44  4994.9  136.38
  4995.1  135.88  4998.6  135.88  4998.9  136.38  5001.7  138.94  5007.2  138.94
  5014.7  139.92  5034.8   139.8  5057.6  140.55  5065.7  140.28  5105.1  141.58
  5115.1  141.28  5177.6  141.89  5254.5  143.99    5353  145.69  5430.9  146.13
#Mann= 9 ,-1 , 0
  4713.1     .07       0  4727.1    .035       0  4839.8     .12       0
  4948.3     .05       0  4994.9     .05       0  4998.9     .05       0
  5057.6     .12       0  5254.5     .07       0    5353     .12       0
Bank Sta=4994.9,4998.9
XS Rating Curve= 0 ,0
Exp/Cntr=0.3,0.1

Type RM Length L Ch R = 1 ,1724    ,186,186,186
BEGIN DESCRIPTION:
Mapping XS 3b368698
END DESCRIPTION:
XS GIS Cut Line= 3
      2537190.51     13491326.04      2536843.25     13491030.87
      2536422.21     13490965.76
#Sta/Elev= 30
  4525.4  144.54    4530  144.86  4617.5  144.12  4650.8  143.45  4672.1  143.83
  4678.6  143.33  4700.6   143.7  4751.4  143.03  4799.4  142.39  4821.4  140.62
  4842.3  141.28  4877.4  140.11  4926.8  139.22  4941.1  137.51  4963.1  140.34
  4981.2  140.54  4999.6  137.41  5007.7  134.51    5008  134.01  5011.5  134.01
  5011.7  134.51  5019.9   137.9    5030  139.97  5055.5  141.92  5070.5  143.35
  5121.9  145.82  5179.9  145.69  5243.2  146.37  5286.3  147.01  5407.2  148.98
#Mann= 10 ,-1 , 0
  4525.4     .07       0    4530     .05       0  4617.5     .07       0
  4751.4    .035       0  4877.4     .12       0  5007.7     .05       0
  5011.7     .12       0  5055.5     .05       0  5243.2     .12       0
  5286.3     .07       0
Bank Sta=5007.7,5011.7
XS Rating Curve= 0 ,0
Exp/Cntr=0.3,0.1

Type RM Length L Ch R = 1 ,1538    ,310,310,310
BEGIN DESCRIPTION:
Mapping XS c7899aa7
END DESCRIPTION:
XS GIS Cut Line= 3
      2537286.87      13491259.4      2536888.46     13490860.99
        2536464.     13490806.31
#Sta/Elev= 30
  4436.8  147.38  4476.6   145.7  4653.4  141.98  4695.8  139.94  4731.1  140.52
  4809.4  138.88  4844.3  138.76  4879.6  137.12  4886.7  138.35  4893.8  138.24
  4900.9  139.29  4944.6   138.6  4971.6  138.35  4978.6  137.31  4983.7  135.53
    4984  135.03  4987.5  135.03  4987.7  135.53  4992.8  135.71  4999.1  137.81
  5004.1  137.81  5008.4  138.78  5023.9  138.72  5054.1   140.8  5082.8  141.35
  5162.3   144.9  5234.2  146.97  5296.1  148.25  5346.5  149.54  5428.2  149.51
#Mann= 7 ,-1 , 0
  4436.8     .07       0  4809.4    .035       0  4944.6     .07       0
  4983.7     .05       0  4987.7     .07       0  5234.2     .12       0
  5296.1     .07       0
Bank Sta=4983.7,4987.7
XS Rating Curve= 0 ,0
Exp/Cntr=0.3,0.1

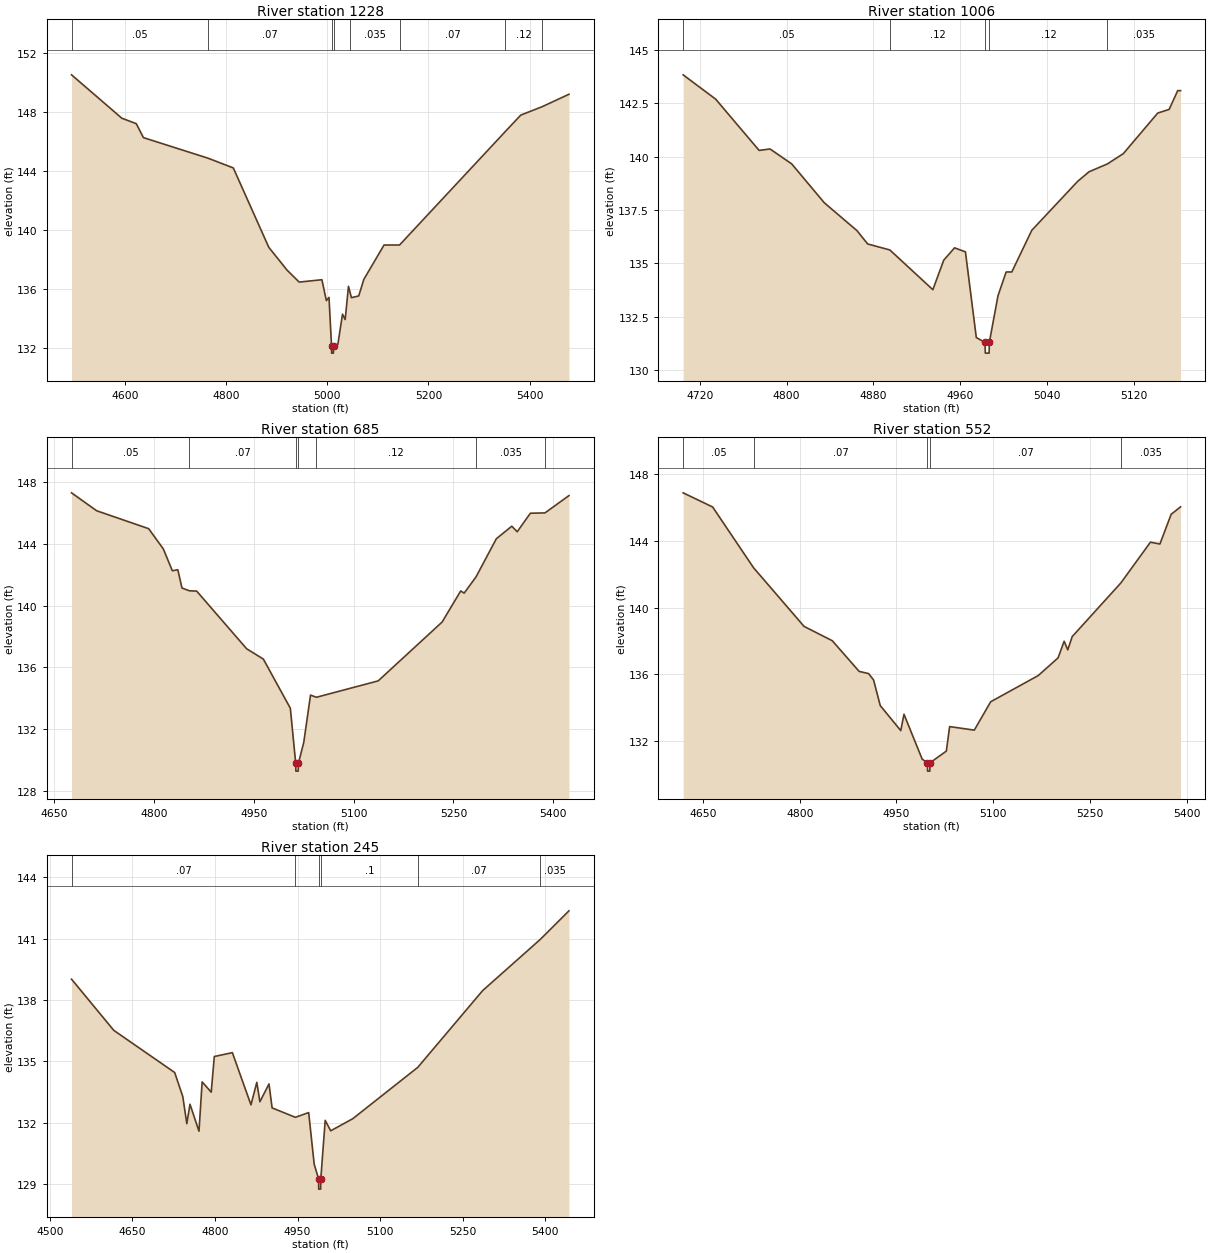
Type RM Length L Ch R = 1 ,1228    ,222,222,222
BEGIN DESCRIPTION:
Mapping XS 660421dd
END DESCRIPTION:
XS GIS Cut Line= 4
      2537466.59     13490993.81      2537125.44     13490696.93
      2537029.08     13490665.68      2536599.74     13490655.27
#Sta/Elev= 30
  4494.8  150.54  4594.2  147.59  4622.7  147.22  4636.9  146.27  4763.9  144.88
  4814.5  144.21  4884.7  138.81  4920.8  137.26  4944.7  136.45  4989.6  136.61
  4998.4  135.19  5003.6  135.41  5008.6  132.12  5008.8  131.62  5012.3  131.62
  5012.6  132.12  5021.1  132.21  5030.3  134.27  5035.6   133.9  5042.1  136.16
  5044.6  135.83  5047.9  135.39  5062.4  135.51  5072.4  136.63  5112.4  138.97
    5143  138.97  5351.9  146.68  5382.5   147.8  5425.3  148.38  5477.8  149.22
#Mann= 8 ,-1 , 0
  4494.8     .05       0  4763.9     .07       0  5008.6     .05       0
  5012.6     .07       0  5044.6    .035       0    5143     .07       0
  5351.9     .12       0  5425.3     .07       0
Bank Sta=5008.6,5012.6
XS Rating Curve= 0 ,0
Exp/Cntr=0.3,0.1

Type RM Length L Ch R = 1 ,1006    ,321,321,321
BEGIN DESCRIPTION:
TRIB 4 TO HOG THIEF CREEK 2.0
END DESCRIPTION:
XS GIS Cut Line= 3
      2537425.03       13490475.        2537125.       13490475.
      2536975.04     13490425.01
#Sta/Elev= 30
  4704.7  143.83  4734.7  142.69  4774.7  140.29  4784.7  140.36  4804.7  139.66
  4834.7  137.84  4864.7  136.54  4874.7  135.91  4895.1  135.63  4934.7  133.77
  4944.7  135.15  4954.7  135.73  4964.7  135.54  4974.7  131.53  4982.7   131.3
    4983   130.8  4986.5   130.8  4986.7   131.3  4994.7  133.49  5002.2   134.6
  5007.4   134.6  5025.8  136.55    5068  138.84  5078.5  139.29  5095.5  139.66
  5110.1  140.14  5141.8  142.04  5152.3  142.21  5160.2  143.09  5162.8  143.09
#Mann= 5 ,-1 , 0
  4704.7     .05       0  4895.1     .12       0  4982.7     .05       0
  4986.7     .12       0  5095.5    .035       0
Bank Sta=4982.7,4986.7
XS Rating Curve= 0 ,0
Exp/Cntr=0.3,0.1

Type RM Length L Ch R = 1 ,685     ,133,133,133
BEGIN DESCRIPTION:
Mapping XS 6c2a6b45
END DESCRIPTION:
XS GIS Cut Line= 4
      2537537.72     13490445.14      2537379.28     13490234.61
      2537201.33     13490208.56      2536910.55     13490295.36
#Sta/Elev= 30
  4676.6   147.3  4714.3  146.14  4792.4  144.98  4814.4  143.67  4827.9  142.26
  4836.2  142.32  4842.4  141.14  4853.6  140.96  4864.5  140.94  4939.5  137.21
  4964.6  136.54  5005.1  133.36  5013.2  129.79  5013.4  129.29  5016.9  129.29
  5017.2  129.79  5025.3  131.16  5035.4  134.21  5044.3  134.07    5137  135.13
    5233  138.94  5260.9  140.95  5266.1  140.81  5283.9  141.86  5314.4  144.33
  5337.6  145.14  5345.7  144.78  5365.5  145.98  5387.4     146  5423.4  147.12
#Mann= 7 ,-1 , 0
  4676.6     .05       0  4853.6     .07       0  5013.2     .05       0
  5017.2     .07       0  5044.3     .12       0  5283.9    .035       0
  5387.4     .07       0
Bank Sta=5013.2,5017.2
XS Rating Curve= 0 ,0
Exp/Cntr=0.3,0.1

Type RM Length L Ch R = 1 ,552     ,307,307,307
BEGIN DESCRIPTION:
Mapping XS 5c1483ba
END DESCRIPTION:
XS GIS Cut Line= 4
      2537581.09     13490351.79      2537396.64      13490104.4
      2537229.54     13490080.53      2536962.59     13490204.23
#Sta/Elev= 30
  4619.1  146.89  4664.9  146.04  4728.3   142.4  4806.7  138.88  4850.5  138.02
  4892.2  136.18  4906.8  136.05  4914.5  135.67  4924.9  134.13  4956.7  132.63
  4961.7  133.61  4989.9  130.92    4998   130.7  4998.3   130.2  5001.8   130.2
    5002   130.7  5027.4   131.4  5032.5  132.87  5070.8  132.66  5096.2  134.36
  5169.9  135.93  5200.7  136.99  5210.2  137.99  5215.7  137.47  5222.7  138.27
    5298  141.48    5344  143.93  5358.7  143.82  5376.1   145.6  5390.7  146.05
#Mann= 5 ,-1 , 0
  4619.1     .05       0  4728.3     .07       0    4998     .05       0
    5002     .07       0    5298    .035       0
Bank Sta=4998,5002
XS Rating Curve= 0 ,0
Exp/Cntr=0.3,0.1

Type RM Length L Ch R = 1 ,245     ,0,0,0
BEGIN DESCRIPTION:
TRIB 4 TO HOG THIEF CREEK 1.0
END DESCRIPTION:
XS GIS Cut Line= 4
       2537527.3     13490144.27      2537349.36      13489801.4
      2537193.11     13489805.74      2537025.01     13490124.98
#Sta/Elev= 30
  4539.5  139.02  4616.2  136.52  4726.8  134.46  4741.5  133.29  4748.9  131.96
  4754.6  132.91    4771  131.59  4776.7     134  4793.2   133.5  4798.8  135.24
  4831.6  135.43  4865.4  132.88    4876  133.98  4881.6  133.03  4898.1   133.9
  4903.8  132.73    4946  132.27  4970.2   132.5  4980.2  129.98  4988.2  129.26
  4988.4  128.76  4991.9  128.76  4992.2  129.26  5000.2  132.12  5010.2  131.61
  5050.2   132.2  5168.3  134.71  5286.1  138.46  5391.1  140.97  5442.9  142.36
#Mann= 6 ,-1 , 0
  4539.5     .07       0    4946      .1       0  4988.2     .05       0
  4992.2      .1       0  5168.3     .07       0  5391.1    .035       0
Bank Sta=4988.2,4992.2
XS Rating Curve= 0 ,0
Exp/Cntr=0.3,0.1

Chan Stop Cuts=-1
Use User Specified Reach Order=0
Composite Channel Slope=5