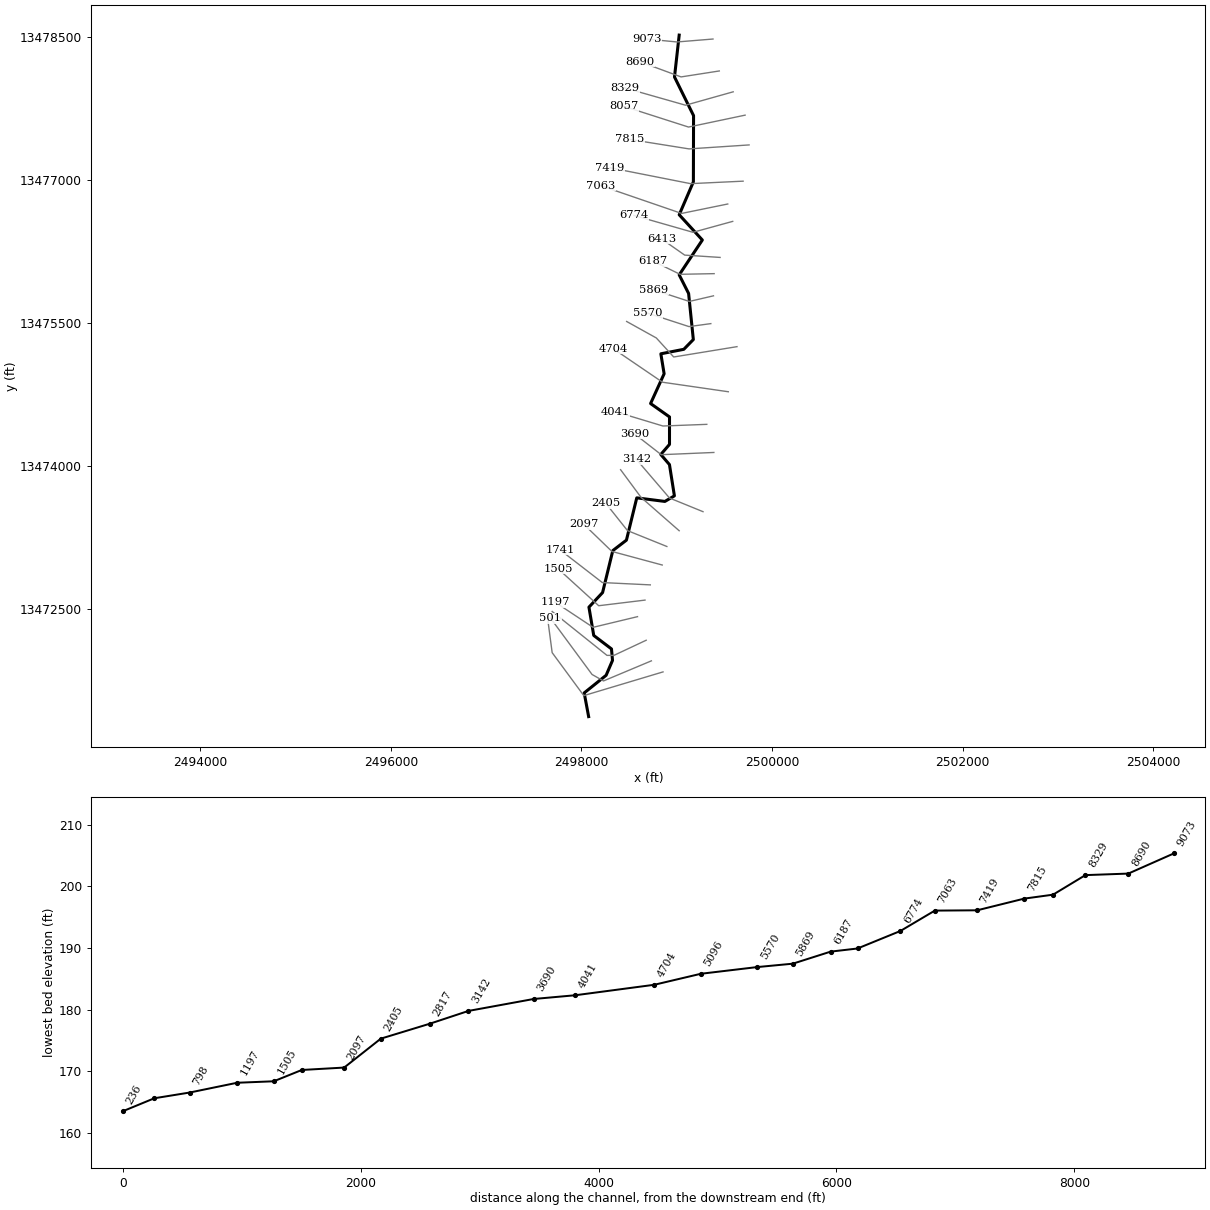
--- TRIB 4 TO PERDIDO CREEK.prj (project) ---

Proj Title=TRIB 4 TO PERDIDO CREEK Base Level Engineering
Current Plan=p01
Default Exp/Contr=0.3,0.1
English Units
Geom File=g01
Flow File=f01
Plan File=p01
Y Axis Title=Elevation
X Axis Title(PF)=Main Channel Distance
X Axis Title(XS)=Station
BEGIN DESCRIPTION:
TRIB 4 TO PERDIDO CREEK
END DESCRIPTION:
DSS Export Rating Curves= 0
DSS Export Rating Curve Sorted= 0
DSS Export Volume Flow Curves= 0
DXF OffsetX= 0
DXF OffsetY= 0
DXF ScaleX= 1
DXF ScaleY= 10

--- TRIB 4 TO PERDIDO CREEK.p01 (plan) ---

Plan Title=Multiple Run
Short Identifier=Multiple
Geom File=g01
Flow File=f01
Subcritical Flow
K Sum by GR= 0
Std Step Tol= 0.01
Critical Tol= 0.01
Num of Std Step Trials= 20
Max Error Tol= 0.3
Flow Tol Ratio= 0.001
Split Flow NTrial= 30
Split Flow Tol= 0.02
Split Flow Ratio= 0.02
Log Output Level= 0
Friction Slope Method= 1
Unsteady Friction Slope Method= 2
Unsteady Bridges Friction Slope Method= 1
Parabolic Critical Depth
Global Vel Dist=  1 , 1 , 1
Global Log Level= 0
CheckData=True
Encroach Param= -1, 0, 0, 0
BEGIN DESCRIPTION:
Multiple Run
END DESCRIPTION:

--- TRIB 4 TO PERDIDO CREEK.f01 (steady flow) ---

Flow Title=Multiple
Number of Profiles=7
Profile Names=10-year,25-year,50-year,1pct_min,100-year,1pct_plu,500-year
River Rch & RM= TRIB 4 TO PERDID,Reach-1,9073
     556     885    1177     759    1514    3021    2476
River Rch & RM= TRIB 4 TO PERDID,Reach-1,4041
     788    1279    1723    1123    2241    4472    3752
Boundary for River Rch & Prof#=TRIB 4 TO PERDID,Reach-1,1
Up Type=0
Dn Type=3
Dn Slope=0.005
Boundary for River Rch & Prof#=TRIB 4 TO PERDID,Reach-1,2
Up Type=0
Dn Type=3
Dn Slope=0.005
Boundary for River Rch & Prof#=TRIB 4 TO PERDID,Reach-1,3
Up Type=0
Dn Type=3
Dn Slope=0.005
Boundary for River Rch & Prof#=TRIB 4 TO PERDID,Reach-1,4
Up Type=0
Dn Type=3
Dn Slope=0.005
Boundary for River Rch & Prof#=TRIB 4 TO PERDID,Reach-1,5
Up Type=0
Dn Type=3
Dn Slope=0.005
Boundary for River Rch & Prof#=TRIB 4 TO PERDID,Reach-1,6
Up Type=0
Dn Type=3
Dn Slope=0.005
Boundary for River Rch & Prof#=TRIB 4 TO PERDID,Reach-1,7
Up Type=0
Dn Type=3
Dn Slope=0.005

--- TRIB 4 TO PERDIDO CREEK.g01 (geometry) ---

Geom Title=Existing Conditions
Program Version=4.10

River Reach=TRIB 4 TO PERDID,Reach-1
Reach XY= 30
        2499025.       13478525.      2498975.75     13478085.68
      2499175.82     13477680.04      2499173.95     13476985.44
      2499025.19     13476640.09      2499267.99      13476375.2
      2499025.09      13476009.6       2499123.8      13475814.5
      2499173.38     13475331.03      2499073.55     13475228.53
      2498832.67     13475181.52      2498866.92      13474971.7
      2498724.87     13474659.57      2498923.47     13474519.17
      2498923.36     13474231.03       2498832.1       13474125.
      2498922.92     13474019.15      2498974.77     13473690.98
      2498875.05     13473632.52      2498580.01       13473670.
      2498471.46     13473226.46      2498328.51     13473116.52
      2498221.39      13472676.5      2498078.13     13472523.37
      2498128.53     13472226.45      2498314.66     13472085.12
      2498325.51     13471964.83      2498258.37     13471808.29
      2498028.45     13471623.52        2498075.       13471375.

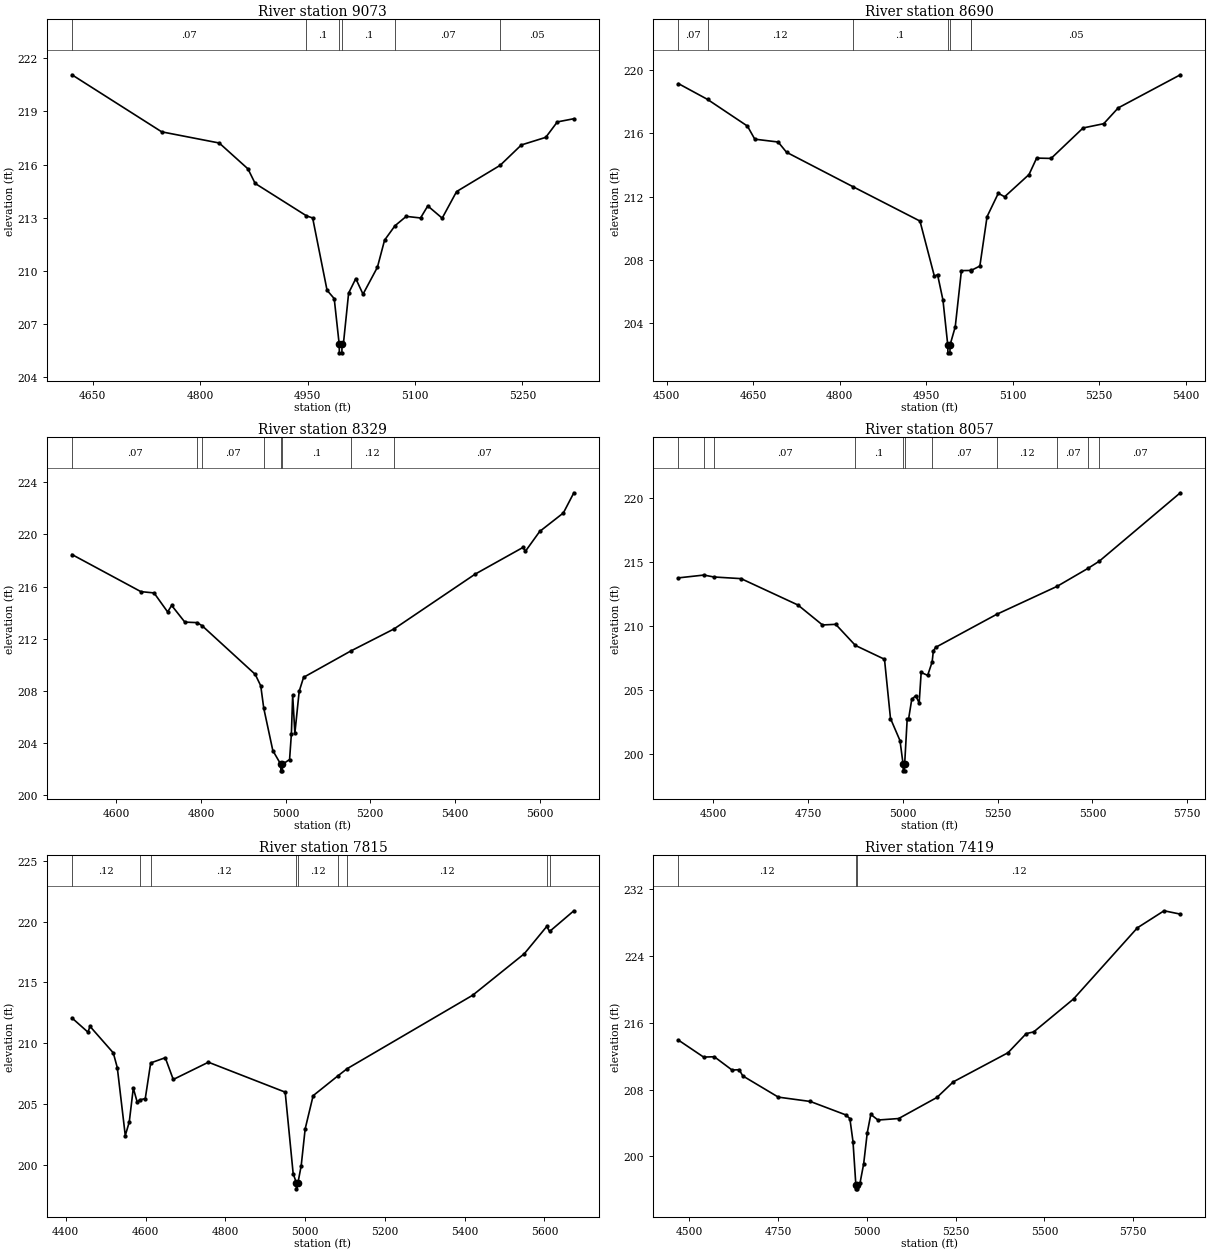
Type RM Length L Ch R = 1 ,9073    ,383,383,383
BEGIN DESCRIPTION:
TRIB 4 TO PERDIDO CREEK 19.0
END DESCRIPTION:
XS GIS Cut Line= 3
      2499379.88     13478483.88      2499002.25     13478452.96
      2498682.04     13478483.87
#Sta/Elev= 30
  4621.1  221.07  4746.4  217.85  4826.7  217.22  4866.8  215.76  4876.8  214.94
  4948.5  213.11  4957.1  212.99  4977.2  208.91  4987.2  208.44  4994.1  205.88
  4994.4  205.38  4997.9  205.38  4998.1  205.88    5000  205.88  5007.3  208.75
  5017.3  209.57  5027.4  208.69  5047.5  210.21  5057.5  211.74    5072  212.55
  5087.7  213.08  5107.7  212.99  5117.8  213.67  5137.9  212.98    5158  214.48
  5218.8  215.96  5248.4  217.11  5282.5  217.54  5298.6  218.41  5321.7  218.59
#Mann= 6 ,-1 , 0
  4621.1     .07       0  4948.5      .1       0  4994.1     .05       0
  4998.1      .1       0    5072     .07       0  5218.8     .05       0
Bank Sta=4994.1,4998.1
XS Rating Curve= 0 ,0
Exp/Cntr=0.3,0.1

Type RM Length L Ch R = 1 ,8690    ,361,361,361
BEGIN DESCRIPTION:
Mapping XS 84037c28
END DESCRIPTION:
XS GIS Cut Line= 3
       2499445.9     13478148.81      2499044.84     13478086.31
       2498608.7     13478247.27
#Sta/Elev= 30
  4520.1  219.16  4570.6  218.16  4639.8  216.47  4652.6  215.64  4693.1  215.46
  4707.7  214.81  4822.3  212.64  4939.2  210.45  4964.3  206.94  4969.7  207.06
  4979.1  205.44  4987.4   202.6  4987.7   202.1  4991.2   202.1  4991.4   202.6
  5000.4  203.75  5011.1  207.31  5026.9  207.32  5027.4  207.31  5043.1   207.6
  5055.6  210.73  5075.1  212.21  5086.1  211.99  5128.4   213.4  5141.6  214.44
  5166.7  214.42  5222.2  216.35    5258  216.62  5283.1  217.62  5390.9  219.72
#Mann= 7 ,-1 , 0
  4520.1     .07       0  4570.6     .12       0  4822.3      .1       0
  4987.4     .05       0  4991.4      .1       0  5026.9     .07       0
  5027.4     .05       0
Bank Sta=4987.4,4991.4
XS Rating Curve= 0 ,0
Exp/Cntr=0.3,0.1

Type RM Length L Ch R = 1 ,8329    ,272,272,272
BEGIN DESCRIPTION:
Mapping XS cf0f9994
END DESCRIPTION:
XS GIS Cut Line= 3
      2499591.68     13477930.05      2499091.72     13477789.43
      2498451.11     13477971.72
#Sta/Elev= 30
  4495.5  218.46  4658.3  215.61  4689.4  215.51  4721.5  214.05    4731  214.55
  4762.1  213.27  4791.1  213.23    4803  212.99  4928.3  209.26  4941.4  208.38
  4948.5  206.66  4969.9  203.41  4988.7  202.35  4988.9  201.85  4992.4  201.85
  4992.7  202.35  5009.5  202.72  5013.8   204.7  5016.8  207.67    5022  204.74
  5032.2  207.96  5042.6  209.03  5153.4  211.04  5256.4  212.75  5448.1  216.96
  5561.1  219.01  5566.3   218.7  5600.2  220.23  5656.1  221.65  5680.9   223.2
#Mann= 8 ,-1 , 0
  4495.5     .07       0  4791.1      .1       0    4803     .07       0
  4948.5      .1       0  4988.7     .05       0  4992.7      .1       0
  5153.4     .12       0  5256.4     .07       0
Bank Sta=4988.7,4992.7
XS Rating Curve= 0 ,0
Exp/Cntr=0.3,0.1

Type RM Length L Ch R = 1 ,8057    ,242,242,242
BEGIN DESCRIPTION:
Mapping XS 5dc5dcfa
END DESCRIPTION:
XS GIS Cut Line= 3
      2499716.67     13477685.26      2499122.97     13477560.27
      2498440.69     13477779.01
#Sta/Elev= 30
  4408.4  213.75  4475.6  213.97  4501.7  213.82  4573.6  213.69  4723.5  211.63
  4788.2  210.07  4823.1  210.12    4875  208.47  4951.7  207.39  4967.5  202.76
  4992.6  201.03  5000.8  199.17  5001.1  198.67  5004.6  198.67  5004.8  199.17
  5011.5   202.7  5015.1   202.7  5023.5  204.25    5034  204.55  5043.1  203.97
  5048.4  206.36  5065.5  206.13  5077.3  207.18  5080.5  208.04  5086.5  208.32
  5247.4   210.9  5406.9  213.09    5488  214.49  5517.8  215.05  5731.6   220.4
#Mann= 11 ,-1 , 0
  4408.4     .07       0  4475.6    .035       0  4501.7     .07       0
    4875      .1       0  5000.8     .05       0  5004.8      .1       0
  5077.3     .07       0  5247.4     .12       0  5406.9     .07       0
    5488     .12       0  5517.8     .07       0
Bank Sta=5000.8,5004.8
XS Rating Curve= 0 ,0
Exp/Cntr=0.3,0.1

Type RM Length L Ch R = 1 ,7815    ,396,396,396
BEGIN DESCRIPTION:
Mapping XS c492a886
END DESCRIPTION:
XS GIS Cut Line= 3
      2499758.42     13477372.77      2499128.18      13477331.1
      2498509.33     13477429.91
#Sta/Elev= 30
  4415.6  212.08  4455.8  210.91  4460.8  211.39  4519.2  209.21  4529.3  207.99
  4549.3  202.41  4559.3  203.53  4569.4  206.31  4579.4  205.14    4585  205.34
  4599.4  205.45    4613  208.38  4649.5  208.81  4669.6  207.02  4757.7  208.44
  4950.2  205.98  4970.2  199.28  4978.2  198.53  4978.5  198.03  4982.2  198.53
  4990.3  199.92  5000.3  202.96  5020.3  205.69    5082  207.31  5105.6  207.91
  5420.4  213.95  5549.7  217.36  5605.9   219.6  5613.1  219.19  5673.9  220.89
#Mann= 9 ,-1 , 0
  4415.6     .12       0    4585     .07       0    4613     .12       0
  4978.2     .05       0  4982.2     .12       0    5082      .1       0
  5105.6     .12       0  5605.9     .07       0  5613.1     .12       0
Bank Sta=4978.2,4982.2
XS Rating Curve= 0 ,0
Exp/Cntr=0.3,0.1

Type RM Length L Ch R = 1 ,7419    ,356,356,356
BEGIN DESCRIPTION:
Mapping XS 39623251
END DESCRIPTION:
XS GIS Cut Line= 3
      2499695.87     13476992.56       2499143.8     13476966.52
      2498300.08     13477133.18
#Sta/Elev= 30
  4469.8  213.92  4540.7  211.89  4570.8  211.93  4620.8  210.34  4640.9  210.38
  4650.9  209.64    4751   207.1  4841.1  206.58  4941.2  204.97  4952.4  204.53
  4961.2  201.78  4969.2  196.63  4969.5  196.13    4973  196.13  4973.2  196.63
  4981.2  196.88  4991.2  199.11  5001.3  202.83  5011.3  205.03  5031.5  204.36
  5089.8  204.54  5197.4  207.06  5243.6  208.93  5397.5  212.41  5448.8   214.7
  5469.8   214.9  5581.9  218.84  5761.6  227.35  5836.7  229.39  5882.5  228.99
#Mann= 3 ,-1 , 0
  4469.8     .12       0  4969.2     .05       0  4973.2     .12       0
Bank Sta=4969.2,4973.2
XS Rating Curve= 0 ,0
Exp/Cntr=0.3,0.1

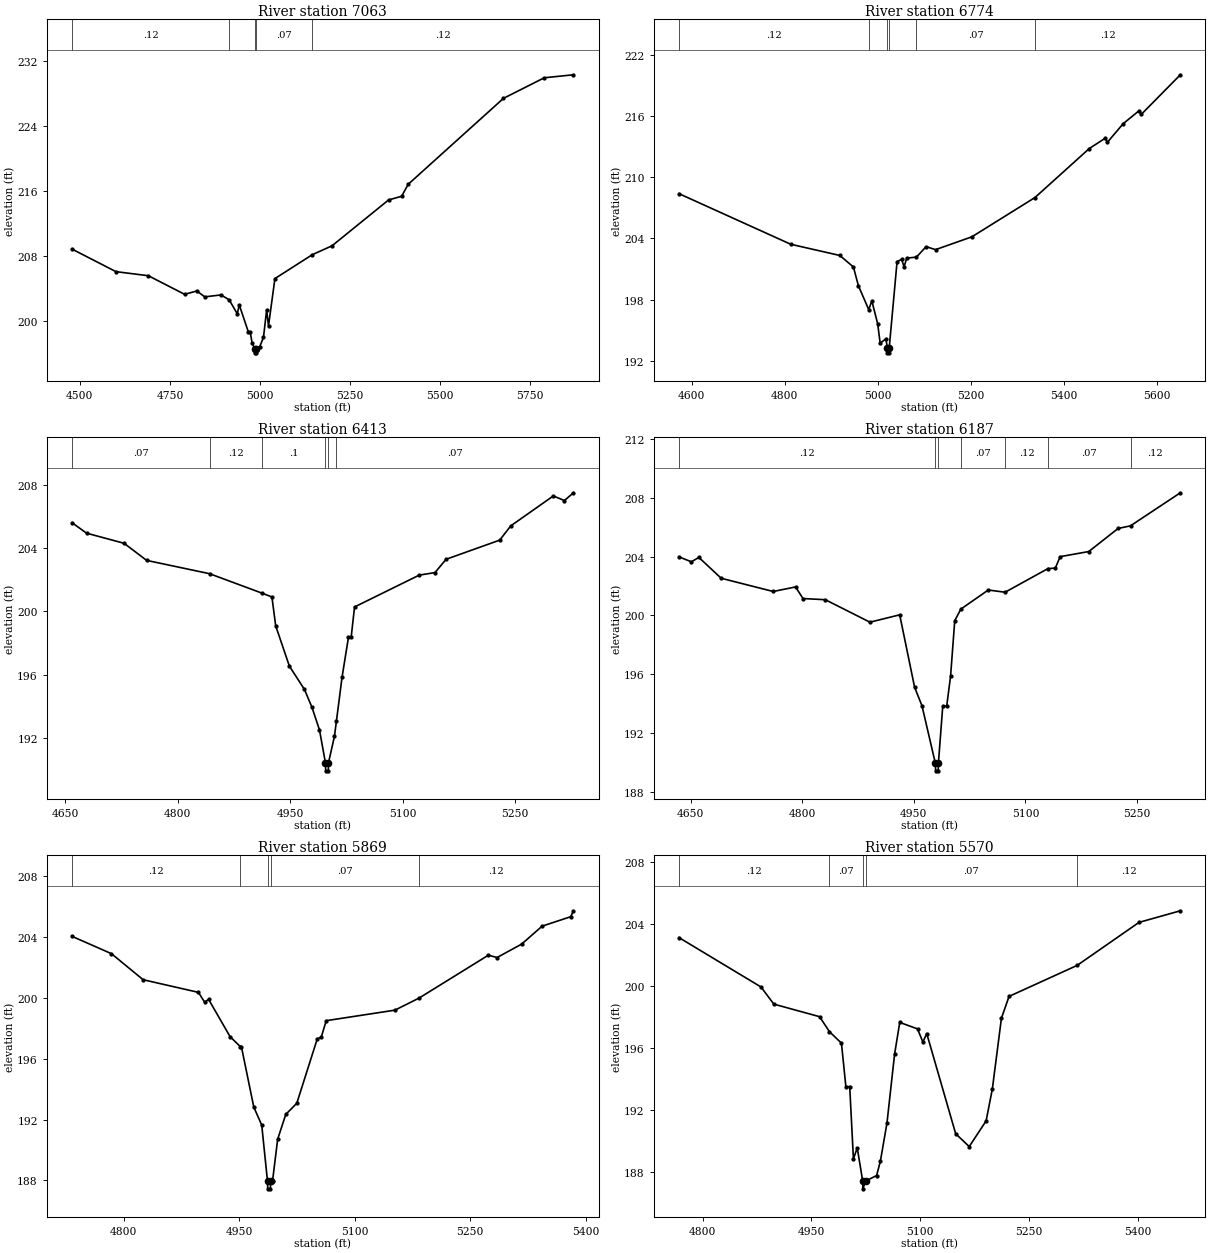
Type RM Length L Ch R = 1 ,7063    ,289,289,289
BEGIN DESCRIPTION:
Mapping XS 376027fe
END DESCRIPTION:
XS GIS Cut Line= 3
      2499534.43     13476752.98      2499050.05     13476654.02
      2498201.13     13476945.67
#Sta/Elev= 30
  4478.3  208.83  4600.2  206.06    4690  205.56    4791  203.27  4824.7  203.69
  4846.6  202.96    4892   203.2  4914.6  202.59    4937  200.88  4942.5  201.97
  4967.6  198.67  4972.7  198.67    4978  197.33  4985.2  196.58  4985.5  196.08
    4989  196.08  4989.2  196.58  4999.2  196.82  5009.7  197.98  5018.5  201.34
  5023.7   199.4  5041.5  205.21  5145.1  208.14  5200.1  209.24  5356.9  214.87
  5393.4  215.33  5411.5   216.8  5675.9  227.36  5789.1  229.89  5870.3  230.26
#Mann= 5 ,-1 , 0
  4478.3     .12       0  4914.6     .07       0  4985.2     .05       0
  4989.2     .07       0  5145.1     .12       0
Bank Sta=4985.2,4989.2
XS Rating Curve= 0 ,0
Exp/Cntr=0.3,0.1

Type RM Length L Ch R = 1 ,6774    ,361,361,361
BEGIN DESCRIPTION:
Mapping XS 3a99ee53
END DESCRIPTION:
XS GIS Cut Line= 3
      2499586.51     13476570.69      2499169.84      13476456.1
      2498550.08     13476633.18
#Sta/Elev= 30
  4572.9   208.4    4813  203.43  4918.4  202.33  4947.6   201.2  4958.2  199.37
  4980.4  197.02  4987.2  197.86  4999.7  195.62    5005  193.72  5017.3  194.14
  5020.5  193.27  5020.7  192.77  5024.2  192.77  5024.5  193.27  5041.3  201.72
  5051.1  201.95  5056.3  201.22  5062.1  202.07    5083  202.17  5103.7   203.2
  5123.9   202.9  5201.9  204.16  5337.5  208.02  5454.1  212.83  5487.9  213.83
  5493.1  213.45  5526.9  215.27  5560.7  216.53  5565.9  216.19  5649.6  220.07
#Mann= 6 ,-1 , 0
  4572.9     .12       0  4980.4      .1       0  5020.5     .05       0
  5024.5      .1       0    5083     .07       0  5337.5     .12       0
Bank Sta=5020.5,5024.5
XS Rating Curve= 0 ,0
Exp/Cntr=0.3,0.1

Type RM Length L Ch R = 1 ,6413    ,226,226,226
BEGIN DESCRIPTION:
Mapping XS 16d5230e
END DESCRIPTION:
XS GIS Cut Line= 3
      2499454.29     13476192.48      2499082.77     13476216.79
      2498839.88     13476386.81
#Sta/Elev= 30
  4659.2  205.59  4678.5  204.93  4728.6  204.29  4758.7  203.21  4842.6  202.37
  4913.2  201.13  4925.8   200.9  4930.8  199.08  4949.1  196.53  4969.2  195.06
  4979.2  193.93  4989.2  192.51  4997.2  190.42  4997.5  189.92    5001  189.92
  5001.2  190.42  5009.2   192.1  5011.9  193.09  5019.3  195.82  5027.9  198.36
  5031.5  198.36    5036  200.27  5122.3  202.28  5143.3  202.44  5158.1  203.28
  5229.6  204.49  5244.4  205.39  5301.1  207.28  5315.9  206.99    5328  207.48
#Mann= 6 ,-1 , 0
  4659.2     .07       0  4842.6     .12       0  4913.2      .1       0
  4997.2     .05       0  5001.2      .1       0  5011.9     .07       0
Bank Sta=4997.2,5001.2
XS Rating Curve= 0 ,0
Exp/Cntr=0.3,0.1

Type RM Length L Ch R = 1 ,6187    ,318,318,318
BEGIN DESCRIPTION:
Mapping XS cb91a20b
END DESCRIPTION:
XS GIS Cut Line= 3
      2499391.76     13476022.34      2499034.15      13476015.4
      2498749.76     13476154.13
#Sta/Elev= 30
  4634.2  203.98    4651  203.64    4661  203.94    4691  202.52    4761  201.62
    4791  201.93    4801  201.14    4831  201.06    4891  199.53    4931  200.03
    4951  195.11    4961  193.83    4979  189.91  4979.3  189.41  4982.8  189.41
    4983  189.91  4988.9  193.82  4994.2  193.82  4999.4  195.85    5005  199.63
  5013.2  200.42  5050.1  201.72  5072.7  201.57  5130.4  203.18  5140.2  203.21
  5146.7  203.99  5185.2  204.34  5224.6  205.91  5241.3  206.09  5308.3  208.34
#Mann= 7 ,-1 , 0
  4634.2     .12       0    4979     .05       0    4983     .12       0
  5013.2     .07       0  5072.7     .12       0  5130.4     .07       0
  5241.3     .12       0
Bank Sta=4979,4983
XS Rating Curve= 0 ,0
Exp/Cntr=0.3,0.1

Type RM Length L Ch R = 1 ,5869    ,299,299,299
BEGIN DESCRIPTION:
Mapping XS d272c945
END DESCRIPTION:
XS GIS Cut Line= 3
      2499384.85      13475789.7      2499131.38     13475730.68
       2498759.9     13475852.19
#Sta/Elev= 30
  4733.1  204.04  4784.3   202.9  4825.4  201.19  4897.2  200.36  4905.3  199.71
  4910.4   199.9  4938.3  197.45  4951.5   196.8    4953  196.79  4969.1  192.82
  4979.4  191.64  4986.9  187.95  4987.2  187.45  4990.7  187.45  4990.9  187.95
  4993.4  187.95  5000.1  190.71  5010.6  192.34  5024.9  193.07  5051.5   197.3
  5056.7  197.42  5063.2   198.5  5152.3  199.19  5183.6  199.98  5273.6   202.8
    5285  202.65  5316.9  203.53  5343.5  204.71  5380.6  205.33  5384.2  205.72
#Mann= 5 ,-1 , 0
  4733.1     .12       0  4951.5     .07       0  4986.9     .05       0
  4990.9     .07       0  5183.6     .12       0
Bank Sta=4986.9,4990.9
XS Rating Curve= 0 ,0
Exp/Cntr=0.3,0.1

Type RM Length L Ch R = 1 ,5570    ,474,474,474
BEGIN DESCRIPTION:
Mapping XS f17118e6
END DESCRIPTION:
XS GIS Cut Line= 3
      2499357.08     13475498.04       2499127.9     13475466.79
      2498690.38     13475609.16
#Sta/Elev= 30
  4767.2  203.13  4880.3  199.94  4898.1  198.83  4961.1  198.02  4974.8  197.05
  4991.3  196.31  4997.4   193.5  5002.7   193.5  5007.8  188.84  5013.1  189.54
  5020.6   187.4  5020.8   186.9  5024.6   187.4  5039.8  187.76    5045  188.69
  5054.1  191.16  5064.6  195.61  5071.7  197.65  5096.2  197.23  5103.6  196.38
  5108.9  196.93  5148.8  190.46  5167.5  189.63  5190.8  191.29  5199.4  193.36
  5211.9  197.92  5222.4  199.33  5316.2  201.33  5401.6  204.11  5458.6  204.86
#Mann= 5 ,-1 , 0
  4767.2     .12       0  4974.8     .07       0  5020.6     .05       0
  5024.6     .07       0  5316.2     .12       0
Bank Sta=5020.6,5024.6
XS Rating Curve= 0 ,0
Exp/Cntr=0.3,0.1

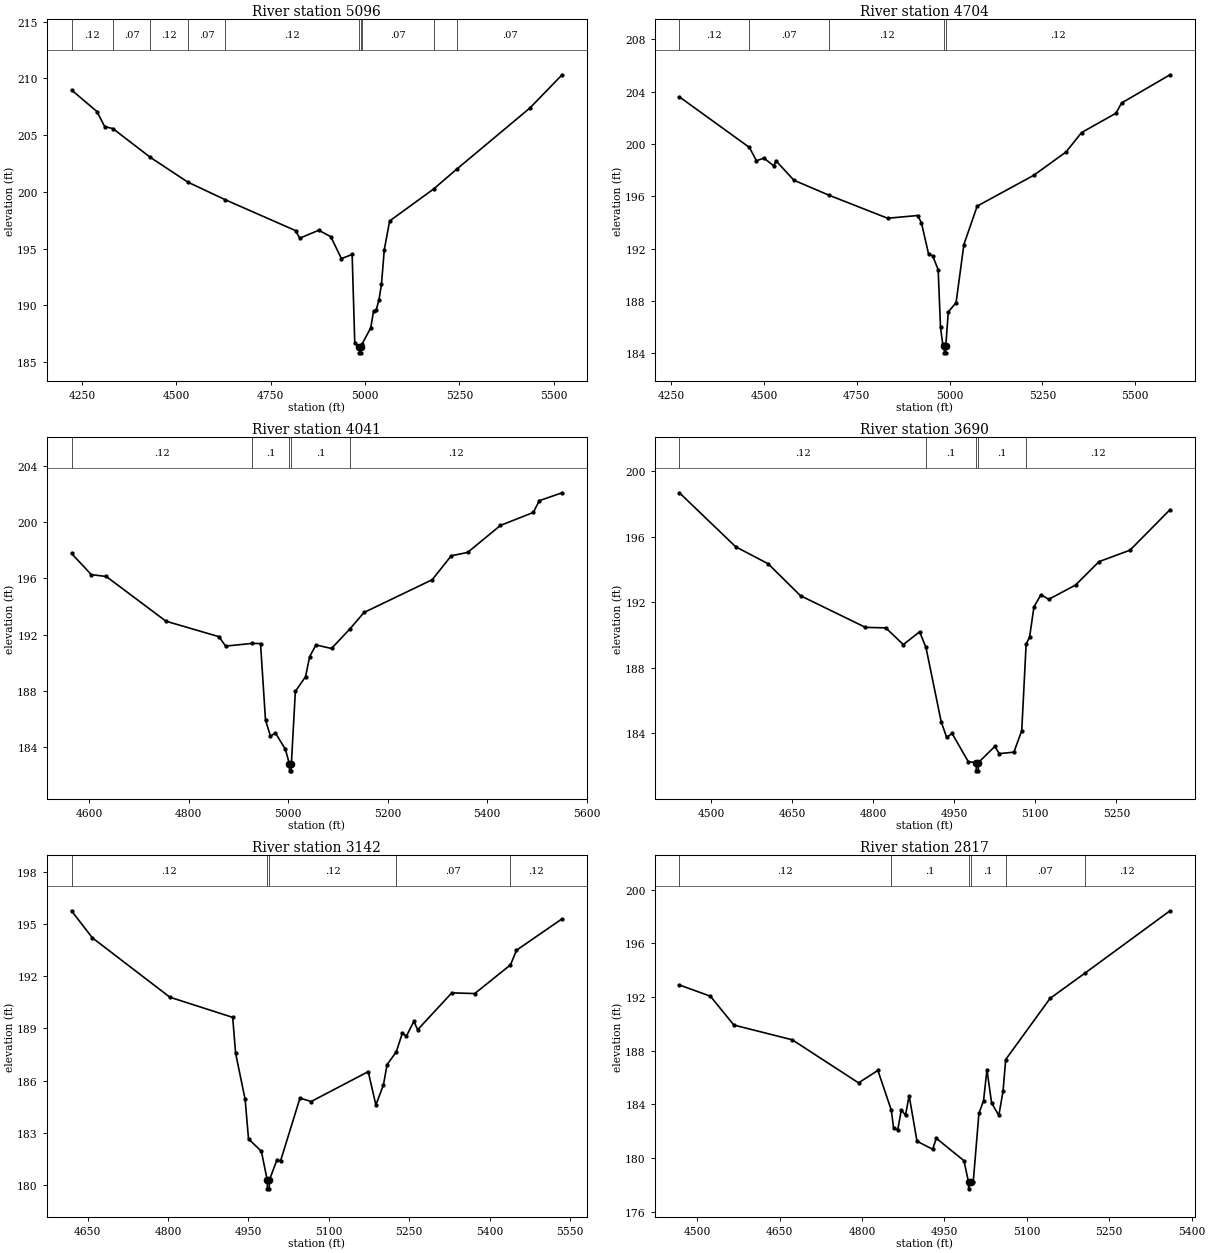
Type RM Length L Ch R = 1 ,5096    ,392,392,392
BEGIN DESCRIPTION:
Mapping XS 74934fac
END DESCRIPTION:
XS GIS Cut Line= 4
      2499631.56     13475256.37      2498967.48     13475147.86
      2498785.19     13475347.51      2498473.68     13475520.57
#Sta/Elev= 30
  4222.4  208.97  4289.8  207.07  4310.1  205.75  4332.3  205.56  4431.4  203.03
  4530.6  200.85  4629.7   199.3  4815.8  196.58  4826.9  195.91  4877.2  196.61
  4909.1  196.05  4937.4  194.11  4965.8  194.48  4972.7  186.71  4984.8  186.31
    4985  185.81  4988.5  185.81  4988.8  186.31  4992.5  186.61  5015.1  188.02
  5022.5  189.48  5029.3  189.57  5036.7  190.45  5043.5  191.85  5050.9  194.89
  5065.1  197.43  5181.4  200.24  5244.1  202.03  5436.6  207.38    5522  210.31
#Mann= 10 ,-1 , 0
  4222.4     .12       0  4332.3     .07       0  4431.4     .12       0
  4530.6     .07       0  4629.7     .12       0  4984.8     .05       0
  4988.8     .12       0  4992.5     .07       0  5181.4     .12       0
  5244.1     .07       0
Bank Sta=4984.8,4988.8
XS Rating Curve= 0 ,0
Exp/Cntr=0.3,0.1

Type RM Length L Ch R = 1 ,4704    ,663,663,663
BEGIN DESCRIPTION:
Mapping XS c4a073f5
END DESCRIPTION:
XS GIS Cut Line= 3
      2499540.43     13474783.27       2498850.3      13474883.1
      2498333.81     13475234.66
#Sta/Elev= 30
    4272  203.61  4460.6  199.74  4479.6  198.72  4499.8  198.92  4526.8  198.32
  4531.8  198.73  4580.6  197.23  4675.4  196.08  4833.2  194.32    4914  194.53
  4924.1  193.98  4943.5  191.58  4954.5  191.44  4969.3  190.38  4975.6  185.96
  4981.7  184.66  4985.8  184.52  4986.1  184.02  4989.6  184.02  4989.8  184.52
  4996.6  187.15  5017.6  187.86  5038.6  192.31  5074.5  195.25    5227  197.61
  5313.8  199.39  5355.8  200.88  5448.6  202.36  5463.5  203.14  5594.1   205.3
#Mann= 5 ,-1 , 0
    4272     .12       0  4460.6     .07       0  4675.4     .12       0
  4985.8     .05       0  4989.8     .12       0
Bank Sta=4985.8,4989.8
XS Rating Curve= 0 ,0
Exp/Cntr=0.3,0.1

Type RM Length L Ch R = 1 ,4041    ,351,351,351
BEGIN DESCRIPTION:
Mapping XS 96e013c2
END DESCRIPTION:
XS GIS Cut Line= 3
      2499314.73     13474441.22      2498854.61     13474423.85
      2498351.17     13474575.75
#Sta/Elev= 30
  4564.4  197.78  4604.2  196.27  4634.2  196.14  4754.3  192.96  4860.6  191.86
  4874.3  191.19  4927.3  191.38  4944.4  191.37  4954.4  185.92  4964.4  184.79
  4974.4  185.01  4994.4  183.85  5002.4  182.82  5002.7  182.32  5006.2  182.32
  5006.4  182.82  5014.4  187.97  5034.9  189.01  5043.1  190.43  5055.8  191.27
  5087.1  191.02  5124.8  192.44  5152.5  193.58  5289.6  195.91  5327.8  197.61
  5360.8  197.85  5426.8  199.77  5492.7  200.69  5504.9  201.53  5550.7  202.09
#Mann= 5 ,-1 , 0
  4564.4     .12       0  4927.3      .1       0  5002.4     .05       0
  5006.4      .1       0  5124.8     .12       0
Bank Sta=5002.4,5006.4
XS Rating Curve= 0 ,0
Exp/Cntr=0.3,0.1

Type RM Length L Ch R = 1 ,3690    ,548,548,548
BEGIN DESCRIPTION:
Mapping XS 3a2ededc
END DESCRIPTION:
XS GIS Cut Line= 3
      2499388.91     13474146.29      2498836.82     13474122.86
      2498556.59     13474340.81
#Sta/Elev= 30
  4441.7  198.67  4545.7  195.38  4605.8  194.34  4665.8  192.39  4785.9  190.46
  4823.4  190.43    4856  189.41    4886  190.19  4897.8  189.24    4926   184.7
  4936.1  183.75  4946.1  183.99  4976.1  182.27  4990.7  182.21  4990.9  181.71
  4994.4  181.71  4994.7  182.21  5025.2   183.2  5033.4  182.76  5060.5  182.85
    5075  184.16  5083.1  189.44  5089.5  189.87  5097.6  191.71  5110.6  192.46
  5124.8  192.17  5174.5  193.04    5218  194.47  5275.3  195.17  5349.3  197.64
#Mann= 5 ,-1 , 0
  4441.7     .12       0  4897.8      .1       0  4990.7     .05       0
  4994.7      .1       0  5083.1     .12       0
Bank Sta=4990.7,4994.7
XS Rating Curve= 0 ,0
Exp/Cntr=0.3,0.1

Type RM Length L Ch R = 1 ,3142    ,325,325,325
BEGIN DESCRIPTION:
TRIB 4 TO PERDIDO CREEK 7.0
END DESCRIPTION:
XS GIS Cut Line= 3
      2499274.96     13473525.02      2498923.18     13473668.45
      2498574.98     13474075.02
#Sta/Elev= 30
  4620.1  195.76  4658.8  194.21  4803.6  190.79  4920.8  189.63  4926.2  187.57
    4944  184.91  4950.3  182.64  4974.3  181.93  4985.2  180.27  4985.5  179.77
    4989  179.77  4989.2  180.27  5003.5  181.45    5010  181.37  5046.3  184.99
  5067.1  184.79  5173.6  186.51  5187.9  184.59  5202.1  185.76  5208.7  186.91
  5225.8  187.64  5237.3  188.72  5244.9  188.56  5258.8   189.4  5265.8  188.92
  5329.5  191.04  5372.3     191    5439  192.65  5450.2  193.49  5535.3   195.3
#Mann= 5 ,-1 , 0
  4620.1     .12       0  4985.2     .05       0  4989.2     .12       0
  5225.8     .07       0    5439     .12       0
Bank Sta=4985.2,4989.2
XS Rating Curve= 0 ,0
Exp/Cntr=0.3,0.1

Type RM Length L Ch R = 1 ,2817    ,412,412,412
BEGIN DESCRIPTION:
TRIB 4 TO PERDIDO CREEK 6.0
END DESCRIPTION:
XS GIS Cut Line= 3
      2499024.96     13473325.03        2498625.       13473675.
      2498410.27     13473965.49
#Sta/Elev= 30
  4467.8  192.89  4524.2  192.05  4566.9   189.9  4673.2   188.8  4793.8  185.59
  4828.9  186.52  4853.5  183.54  4857.4  182.24    4865  182.08  4871.6  183.57
  4879.2  183.18  4885.8  184.64  4900.1  181.24  4928.6  180.64  4935.2  181.46
  4985.5  179.79  4993.9  178.19  4994.1  177.69    4998  178.19  5002.4  178.19
  5012.8  183.32  5021.2  184.26  5027.4  186.58  5035.8   184.1    5049  183.16
  5056.7  184.98  5061.5  187.33  5142.3  191.89    5205  193.75  5360.5  198.42
#Mann= 6 ,-1 , 0
  4467.8     .12       0  4853.5      .1       0  4993.9     .05       0
    4998      .1       0  5061.5     .07       0    5205     .12       0
Bank Sta=4993.9,4998
XS Rating Curve= 0 ,0
Exp/Cntr=0.3,0.1

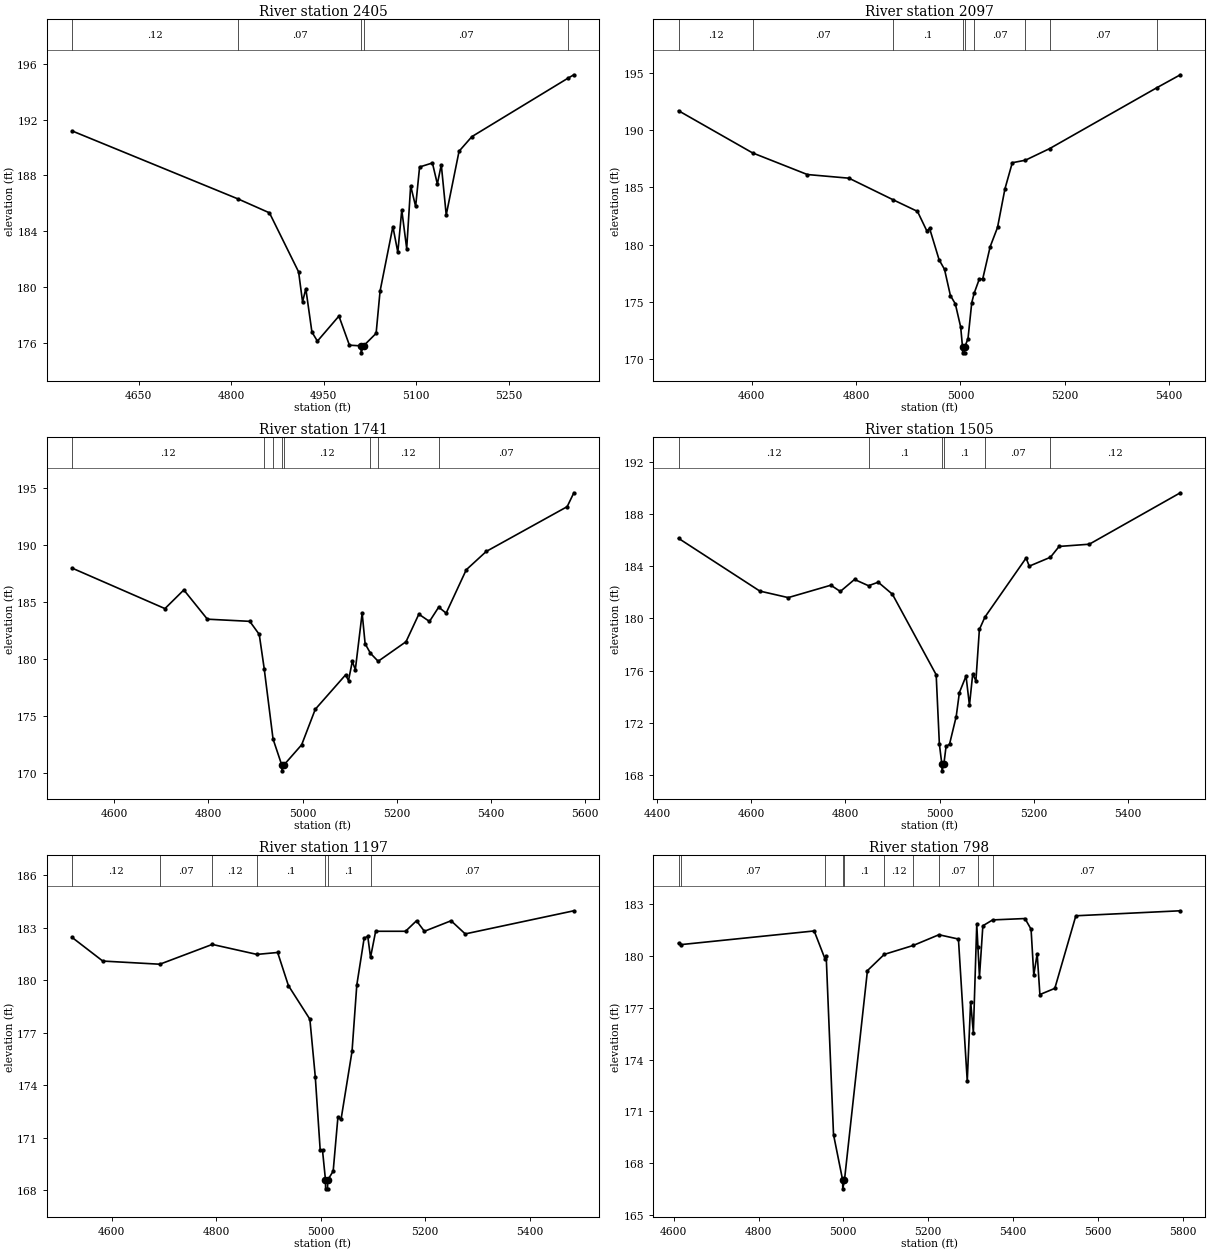
Type RM Length L Ch R = 1 ,2405    ,308,308,308
BEGIN DESCRIPTION:
Mapping XS 1ad1f8cc
END DESCRIPTION:
XS GIS Cut Line= 3
      2498895.75     13473159.83      2498482.53     13473326.51
      2498253.35     13473614.73
#Sta/Elev= 30
  4541.7  191.19  4811.3   186.3  4861.8  185.31  4909.1  181.07  4915.5  178.92
  4920.8  179.86  4930.7  176.75  4939.6   176.1  4974.5   177.9  4991.5  175.81
  5010.3  175.76  5010.5  175.26  5014.4  175.76  5034.8  176.66  5041.2  179.69
    5062  184.32    5070  182.48  5076.4  185.51  5084.4  182.74  5090.8  187.25
  5098.9  185.77  5105.3   188.6  5126.1  188.89  5134.1  187.38  5140.5  188.76
  5148.5  185.16  5169.3  189.73  5190.1  190.78  5346.5  194.99  5355.5  195.22
#Mann= 5 ,-1 , 0
  4541.7     .12       0  4811.3     .07       0  5010.3     .05       0
  5014.4     .07       0  5346.5     .12       0
Bank Sta=5010.3,5014.4
XS Rating Curve= 0 ,0
Exp/Cntr=0.3,0.1

Type RM Length L Ch R = 1 ,2097    ,356,356,356
BEGIN DESCRIPTION:
Mapping XS feada416
END DESCRIPTION:
XS GIS Cut Line= 3
      2498847.09     13472965.41      2498319.34     13473107.76
      2498020.73     13473395.95
#Sta/Elev= 30
  4459.9   191.7  4601.7  188.02  4706.7  186.13  4786.5  185.81  4870.9  183.93
  4917.8  182.91  4935.8   181.2    4941  181.43  4959.2  178.69  4969.6  177.85
  4980.9  175.56  4990.3  174.84  5000.6  172.81  5004.1  171.06  5004.4  170.56
    5008  170.56  5008.3  171.06  5014.6   171.8  5021.8  174.94  5026.3  175.75
    5036  176.97  5042.9  177.03  5057.1  179.83  5071.2  181.51  5085.4  184.88
  5099.5  187.16  5124.6  187.38  5170.9  188.39  5376.9  193.72  5421.5  194.84
#Mann= 9 ,-1 , 0
  4459.9     .12       0  4601.7     .07       0  4870.9      .1       0
  5004.1     .05       0  5008.3      .1       0  5026.3     .07       0
  5124.6      .1       0  5170.9     .07       0  5376.9     .12       0
Bank Sta=5004.1,5008.3
XS Rating Curve= 0 ,0
Exp/Cntr=0.3,0.1

Type RM Length L Ch R = 1 ,1741    ,236,236,236
BEGIN DESCRIPTION:
Mapping XS 34bcf640
END DESCRIPTION:
XS GIS Cut Line= 3
       2498722.1     13472757.07      2498218.64     13472781.37
      2497774.21     13473125.12
#Sta/Elev= 30
  4510.3  187.99  4707.6  184.43  4747.7  186.07  4797.7   183.5  4887.8  183.31
  4907.9  182.16  4918.4  179.16  4937.2  172.97  4955.8  170.67  4956.1  170.17
    4960  170.67    4998  172.46  5026.9  175.58  5091.2   178.6  5097.5  178.11
  5105.6  179.79    5112  179.06  5126.5  184.03  5132.8  181.34  5144.2   180.5
  5160.5   179.8  5219.7  181.52  5246.9  183.94  5269.5   183.3  5289.1  184.56
  5304.9  184.03  5347.6  187.84    5390  189.45    5562  193.39  5576.2  194.61
#Mann= 8 ,-1 , 0
  4510.3     .12       0  4918.4      .1       0  4937.2     .12       0
  4955.8     .05       0    4960     .12       0  5144.2     .07       0
  5160.5     .12       0  5289.1     .07       0
Bank Sta=4955.8,4960
XS Rating Curve= 0 ,0
Exp/Cntr=0.3,0.1

Type RM Length L Ch R = 1 ,1505    ,308,308,308
BEGIN DESCRIPTION:
Mapping XS 078192f7
END DESCRIPTION:
XS GIS Cut Line= 3
       2498666.6     13472597.35      2498180.45     13472538.31
      2497753.39     13472927.18
#Sta/Elev= 30
  4444.9  186.14  4617.8   182.1  4678.2   181.6  4768.9  182.55    4789  182.07
  4819.2  182.99    4849  182.51  4869.6  182.78  4899.8  181.86  4992.9  175.69
  4999.7  170.38    5005  168.83  5005.3  168.33  5009.2  168.83  5013.9   170.2
  5021.3  170.37  5035.5  172.49  5042.3  174.33  5056.4  175.59  5063.7  173.35
  5070.6  175.75  5077.4  175.23  5084.8  179.16  5096.6  180.11  5184.1  184.63
  5190.9  184.01  5235.9  184.69  5254.4  185.52  5318.6  185.69  5512.2  189.63
#Mann= 6 ,-1 , 0
  4444.9     .12       0    4849      .1       0    5005     .05       0
  5009.2      .1       0  5096.6     .07       0  5235.9     .12       0
Bank Sta=5005,5009.2
XS Rating Curve= 0 ,0
Exp/Cntr=0.3,0.1

Type RM Length L Ch R = 1 ,1197    ,399,399,399
BEGIN DESCRIPTION:
Mapping XS c0b84b95
END DESCRIPTION:
XS GIS Cut Line= 3
      2498587.62     13472423.64      2498121.45     13472311.66
      2497720.37     13472577.31
#Sta/Elev= 30
  4524.1  182.44  4582.9  181.09  4692.1  180.91  4792.5  182.04  4877.9  181.47
  4917.6  181.58  4938.2  179.69  4979.3  177.77  4989.6   174.5  4999.1  170.28
  5003.5  170.28  5009.2  168.59  5009.4  168.09  5013.1  168.09  5013.4  168.59
  5023.9   169.1    5033  172.19    5039  172.06    5060  175.94  5069.1  179.72
  5083.2   182.4  5090.1   182.5  5095.4   181.3  5105.2  182.79  5162.4  182.79
  5183.4  183.39  5198.5  182.79  5249.6  183.39  5276.7  182.64  5484.6  183.96
#Mann= 7 ,-1 , 0
  4524.1     .12       0  4692.1     .07       0  4792.5     .12       0
  4877.9      .1       0  5009.2     .05       0  5013.4      .1       0
  5095.4     .07       0
Bank Sta=5009.2,5013.4
XS Rating Curve= 0 ,0
Exp/Cntr=0.3,0.1

Type RM Length L Ch R = 1 ,798     ,297,297,297
BEGIN DESCRIPTION:
Mapping XS 98d4be59
END DESCRIPTION:
XS GIS Cut Line= 4
      2498678.76     13472176.25       2498340.2     13472017.39
      2498267.29     13472017.39      2497692.39     13472477.76
#Sta/Elev= 30
  4611.3  180.75  4618.1  180.67  4931.2  181.46  4956.9  179.83  4959.5  180.02
  4976.8  169.65  4998.4     167  4998.6   166.5  5002.6     167  5056.8  179.16
  5096.5   180.1    5165  180.62  5225.4  181.24  5271.4  180.99  5292.2  172.75
  5300.2  177.36  5306.6  175.55  5314.6  181.85  5317.4  180.52    5321   178.8
    5329  181.76  5352.1   182.1  5428.3  182.18  5442.7  181.56  5449.1   178.9
  5457.1  180.14  5463.5  177.77  5498.7  178.13  5548.3  182.34  5794.7  182.63
#Mann= 10 ,-1 , 0
  4611.3     .12       0  4618.1     .07       0  4956.9      .1       0
  4998.4     .05       0  5002.6      .1       0  5096.5     .12       0
    5165      .1       0  5225.4     .07       0  5317.4      .1       0
  5352.1     .07       0
Bank Sta=4998.4,5002.6
XS Rating Curve= 0 ,0
Exp/Cntr=0.3,0.1

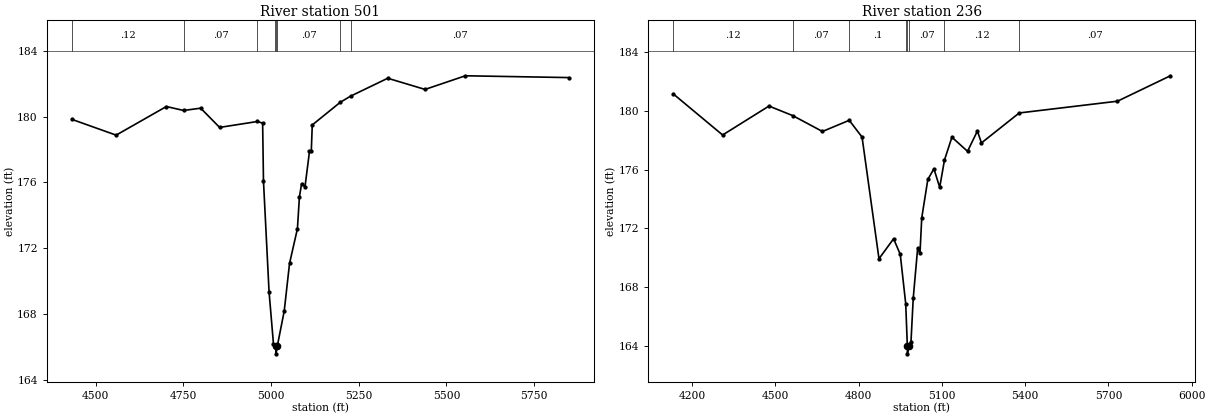
Type RM Length L Ch R = 1 ,501     ,265,265,265
BEGIN DESCRIPTION:
Mapping XS 2d725809
END DESCRIPTION:
XS GIS Cut Line= 4
      2498733.46     13471960.11      2498230.83     13471749.16
      2498111.04     13471816.87      2497675.02     13472408.31
#Sta/Elev= 30
  4432.1  179.83  4558.4  178.87  4701.6  180.61  4750.7  180.37  4799.4  180.51
  4853.4  179.34  4961.4   179.7  4976.1   179.6  4978.5  176.08  4994.4  169.35
  5006.9  166.19  5012.1   166.1  5013.9  166.07  5014.2  165.57  5018.2  166.07
  5037.7  168.18  5052.8  171.07  5075.3  173.18    5081  175.12  5087.3  175.92
  5096.9  175.73  5109.7  177.88  5114.8  177.88  5117.6  179.49  5197.6  180.87
  5226.8  181.24  5332.8  182.33  5439.2  181.65  5554.1  182.48  5849.6  182.37
#Mann= 8 ,-1 , 0
  4432.1     .12       0  4750.7     .07       0  4961.4      .1       0
  5012.1     .07       0  5013.9     .05       0  5018.2     .07       0
  5197.6     .12       0  5226.8     .07       0
Bank Sta=5013.9,5018.2
XS Rating Curve= 0 ,0
Exp/Cntr=0.3,0.1

Type RM Length L Ch R = 1 ,236     ,0,0,0
BEGIN DESCRIPTION:
TRIB 4 TO PERDIDO CREEK 1.0
END DESCRIPTION:
XS GIS Cut Line= 4
      2498855.53      13471844.1      2498024.33     13471595.08
      2497692.35     13472045.93      2497644.61      13472406.2
#Sta/Elev= 30
  4132.3  181.15  4310.3  178.35  4477.3  180.32  4562.9  179.67  4669.9  178.59
  4766.4  179.35  4812.6  178.21  4873.6  169.93  4926.2  171.29  4950.2  170.23
  4969.9  166.87  4975.8  163.96  4976.1  163.46  4980.2  163.96  4988.9  164.29
    4997  167.25  5012.9  170.65  5021.3   170.3  5027.6  172.71  5049.6  175.33
  5071.5  176.05  5092.3  174.79  5109.6  176.65  5136.3   178.2  5192.6  177.24
  5228.1  178.62  5242.7  177.81  5378.8  179.85  5732.8  180.65  5923.3  182.38
#Mann= 8 ,-1 , 0
  4132.3     .12       0  4562.9     .07       0  4766.4      .1       0
  4969.9     .07       0  4975.8     .05       0  4980.2     .07       0
  5109.6     .12       0  5378.8     .07       0
Bank Sta=4975.8,4980.2
XS Rating Curve= 0 ,0
Exp/Cntr=0.3,0.1

Chan Stop Cuts=-1
Use User Specified Reach Order=0
Composite Channel Slope=5