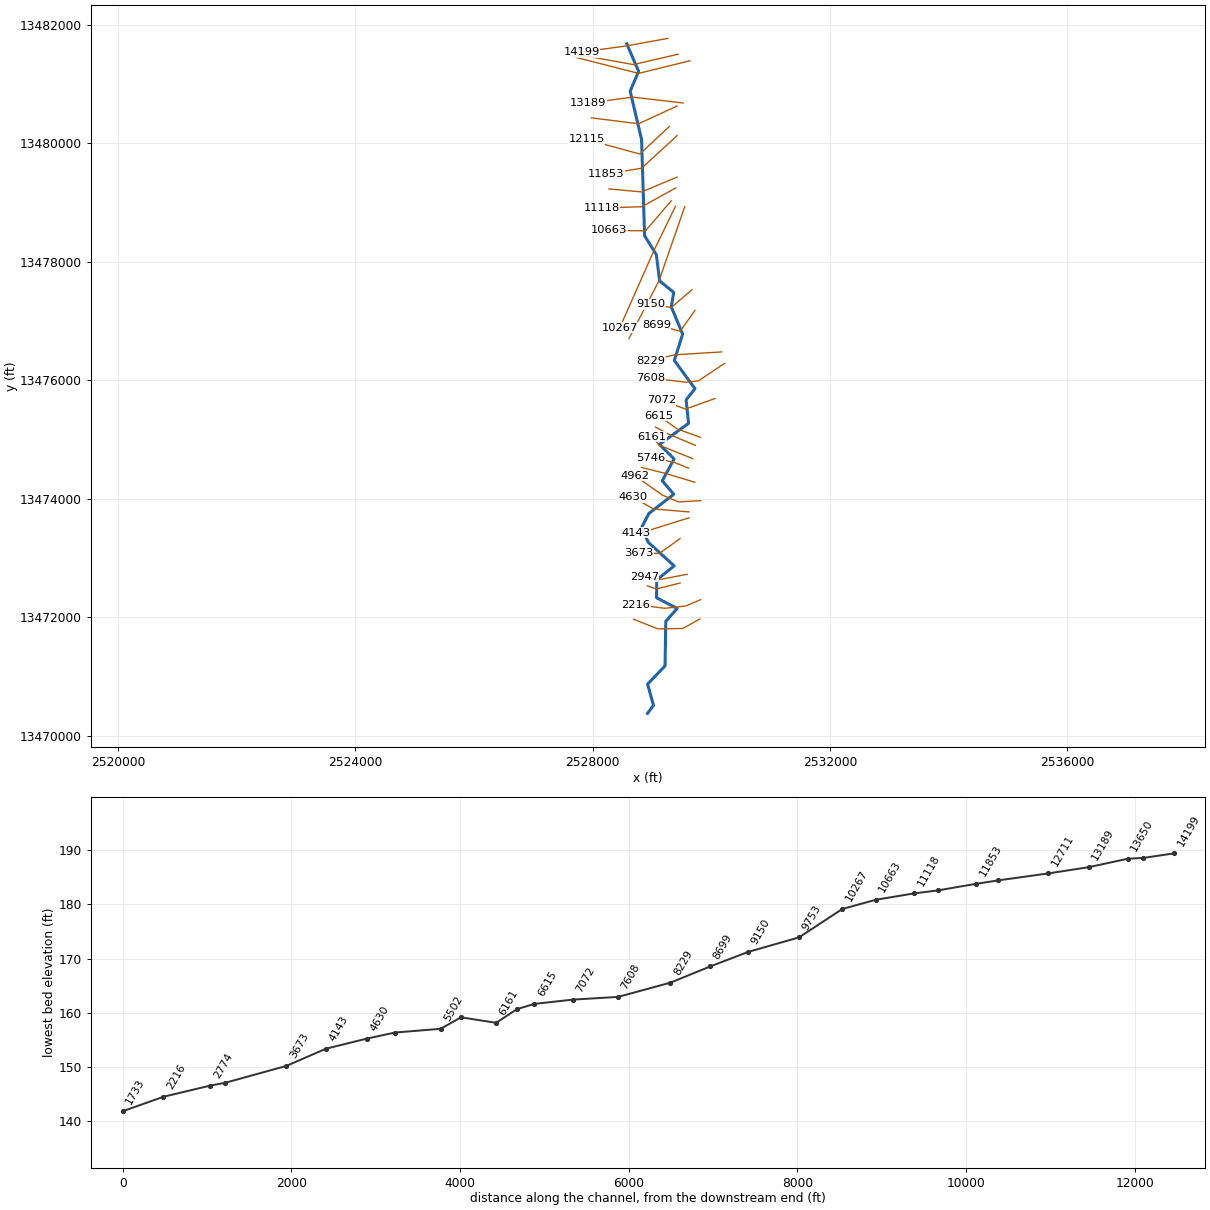
--- TRIB 4 TO TURKEY CREEK.prj (project) ---

Proj Title=TRIB 4 TO TURKEY CREEK Base Level Engineering
Current Plan=p01
Default Exp/Contr=0.3,0.1
English Units
Geom File=g01
Flow File=f01
Plan File=p01
Y Axis Title=Elevation
X Axis Title(PF)=Main Channel Distance
X Axis Title(XS)=Station
BEGIN DESCRIPTION:
TRIB 4 TO TURKEY CREEK
END DESCRIPTION:
DSS Export Rating Curves= 0
DSS Export Rating Curve Sorted= 0
DSS Export Volume Flow Curves= 0
DXF OffsetX= 0
DXF OffsetY= 0
DXF ScaleX= 1
DXF ScaleY= 10

--- TRIB 4 TO TURKEY CREEK.p01 (plan) ---

Plan Title=Multiple Run
Short Identifier=Multiple
Geom File=g01
Flow File=f01
Subcritical Flow
K Sum by GR= 0
Std Step Tol= 0.01
Critical Tol= 0.01
Num of Std Step Trials= 20
Max Error Tol= 0.3
Flow Tol Ratio= 0.001
Split Flow NTrial= 30
Split Flow Tol= 0.02
Split Flow Ratio= 0.02
Log Output Level= 0
Friction Slope Method= 1
Unsteady Friction Slope Method= 2
Unsteady Bridges Friction Slope Method= 1
Parabolic Critical Depth
Global Vel Dist=  1 , 1 , 1
Global Log Level= 0
CheckData=True
Encroach Param= -1, 0, 0, 0
BEGIN DESCRIPTION:
Multiple Run
END DESCRIPTION:

--- TRIB 4 TO TURKEY CREEK.f01 (steady flow) ---

Flow Title=Multiple
Number of Profiles=7
Profile Names=10-year,25-year,50-year,1pct_min,100-year,1pct_plu,500-year
River Rch & RM= TRIB 4 TO TURKEY,Reach-1,14199
     307     463     594     369     736    1469    1118
River Rch & RM= TRIB 4 TO TURKEY,Reach-1,10267
     629     996    1320     847    1689    3370    2733
River Rch & RM= TRIB 4 TO TURKEY,Reach-1,7072
     893    1441    1936    1256    2506    5001    4156
Boundary for River Rch & Prof#=TRIB 4 TO TURKEY,Reach-1,1
Up Type=0
Dn Type=3
Dn Slope=0.005
Boundary for River Rch & Prof#=TRIB 4 TO TURKEY,Reach-1,2
Up Type=0
Dn Type=3
Dn Slope=0.005
Boundary for River Rch & Prof#=TRIB 4 TO TURKEY,Reach-1,3
Up Type=0
Dn Type=3
Dn Slope=0.005
Boundary for River Rch & Prof#=TRIB 4 TO TURKEY,Reach-1,4
Up Type=0
Dn Type=3
Dn Slope=0.005
Boundary for River Rch & Prof#=TRIB 4 TO TURKEY,Reach-1,5
Up Type=0
Dn Type=3
Dn Slope=0.005
Boundary for River Rch & Prof#=TRIB 4 TO TURKEY,Reach-1,6
Up Type=0
Dn Type=3
Dn Slope=0.005
Boundary for River Rch & Prof#=TRIB 4 TO TURKEY,Reach-1,7
Up Type=0
Dn Type=3
Dn Slope=0.005

--- TRIB 4 TO TURKEY CREEK.g01 (geometry) ---

Geom Title=Existing Conditions
Program Version=4.10

River Reach=TRIB 4 TO TURKEY,Reach-1
Reach XY= 30
        2528575.       13481675.      2528775.04     13481209.66
       2528632.5       13480875.      2528824.99     13480059.64
      2528876.05     13478435.44      2529072.75     13478119.07
      2529130.46     13477672.55      2529367.31     13477478.67
      2529326.05     13477235.44      2529517.67      13476774.9
      2529377.06     13476330.86      2529725.36     13475854.79
      2529576.05     13475664.57      2529617.64     13475268.66
      2529125.55     13474914.36       2529373.5     13474669.13
       2529174.5     13474299.96      2529367.41     13474071.67
      2528947.86     13473748.57      2528825.24     13473509.78
      2528938.63     13473261.79      2529374.47     13472864.31
      2529080.46     13472627.45      2529078.43     13472326.22
      2529425.69     13472145.07      2529232.79     13471928.43
      2529221.25     13471176.55       2528926.8     13470868.89
      2529025.55     13470509.76        2528925.       13470375.

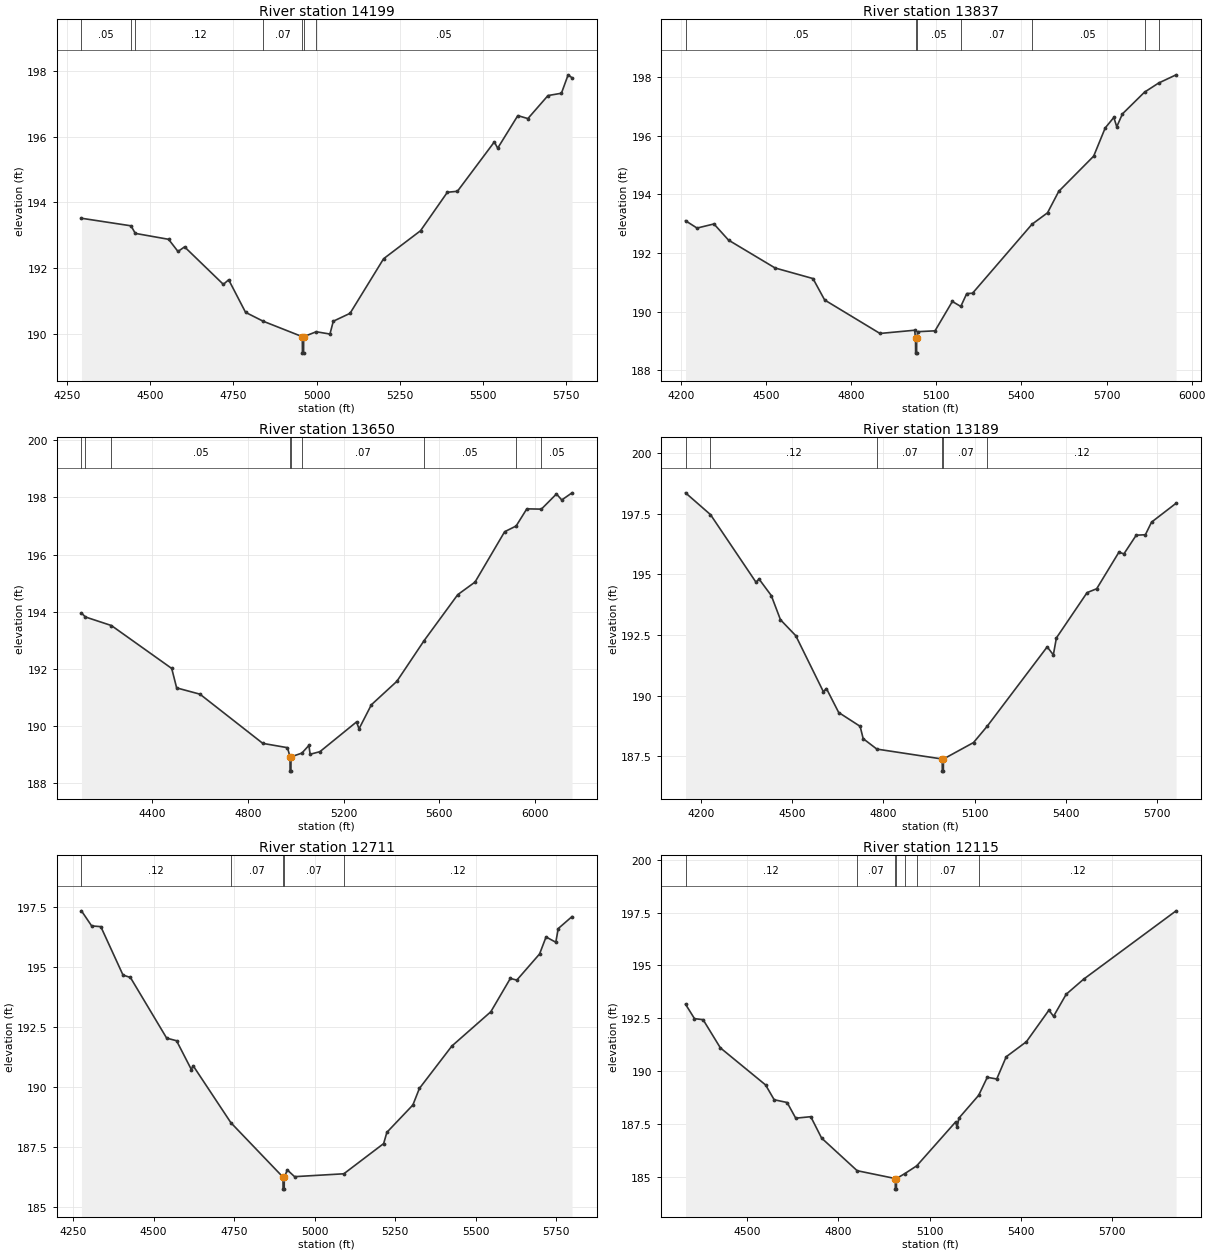
Type RM Length L Ch R = 1 ,14199   ,362,362,362
BEGIN DESCRIPTION:
TRIB 4 TO TURKEY CREEK 31.0
END DESCRIPTION:
XS GIS Cut Line= 3
      2529270.78     13481766.58      2528574.89     13481639.48
      2527813.41     13481534.41
#Sta/Elev= 30
  4292.6  193.52  4441.7  193.29  4454.6  193.06  4554.8  192.88  4583.1  192.51
  4602.9  192.65  4719.6  191.51  4735.6  191.65  4786.4  190.66  4839.4  190.39
  4957.2  189.92  4957.5  189.42    4961  189.42  4961.2  189.92  4999.1  190.07
  5040.3     190  5050.4  190.39  5100.8  190.63  5201.8  192.29  5312.8  193.14
  5393.6  194.31  5423.9  194.34  5534.9  195.84    5545  195.65  5605.6  196.64
  5635.9  196.55  5696.4  197.25  5736.8  197.32    5757  197.88  5768.7  197.79
#Mann= 7 ,-1 , 0
  4292.6     .05       0  4441.7     .07       0  4454.6     .12       0
  4839.4     .07       0  4957.2     .05       0  4961.2     .07       0
  4999.1     .05       0
Bank Sta=4957.2,4961.2
XS Rating Curve= 0 ,0
Exp/Cntr=0.3,0.1

Type RM Length L Ch R = 1 ,13837   ,187,187,187
BEGIN DESCRIPTION:
Mapping XS 014193fe
END DESCRIPTION:
XS GIS Cut Line= 3
      2529442.62     13481498.41      2528685.56     13481323.82
      2527749.19     13481492.67
#Sta/Elev= 30
  4216.8   193.1  4257.4  192.85    4317  192.99  4368.3  192.44  4532.5  191.49
  4665.9  191.13    4707   190.4  4901.9  189.26  5024.1  189.37  5027.2  189.09
  5027.5  188.59    5031  188.59  5031.2  189.09  5034.9  189.32  5095.9  189.35
  5156.9  190.35  5186.6  190.18  5207.7  190.62    5228  190.63  5437.5  192.98
  5492.2  193.37  5531.7   194.1  5654.8   195.3  5695.4  196.26  5725.9  196.62
  5736.1   196.3  5756.2  196.74    5834  197.48  5883.6  197.79  5945.2  198.07
#Mann= 7 ,-1 , 0
  4216.8     .05       0  5027.2     .05       0  5031.2     .05       0
  5186.6     .07       0  5437.5     .05       0    5834     .07       0
  5883.6     .05       0
Bank Sta=5027.2,5031.2
XS Rating Curve= 0 ,0
Exp/Cntr=0.3,0.1

Type RM Length L Ch R = 1 ,13650   ,461,461,461
BEGIN DESCRIPTION:
TRIB 4 TO TURKEY CREEK 30.0
END DESCRIPTION:
XS GIS Cut Line= 3
       2529641.5     13481388.57        2528775.       13481175.
       2527651.9      13481461.5
#Sta/Elev= 30
  4103.7  193.96  4120.1  193.82    4229  193.52  4481.2  192.02  4501.8  191.34
  4599.4  191.12  4862.2   189.4  4965.2  189.25    4976  188.93  4976.2  188.43
  4979.7  188.43    4980  188.93  5025.5  189.06  5054.9  189.33    5060  189.02
  5100.9  189.11    5254  190.15  5264.5  189.91  5316.1  190.75  5422.7  191.57
  5536.4  192.99  5677.3   194.6  5749.6  195.04  5873.4   196.8  5921.4     197
  5966.2   197.6    6027  197.59  6090.1  198.12  6112.3  197.91  6155.2  198.16
#Mann= 9 ,-1 , 0
  4103.7     .05       0  4120.1    .035       0    4229     .05       0
    4976     .05       0    4980     .05       0  5025.5     .07       0
  5536.4     .05       0  5921.4     .07       0    6027     .05       0
Bank Sta=4976,4980
XS Rating Curve= 0 ,0
Exp/Cntr=0.3,0.1

Type RM Length L Ch R = 1 ,13189   ,478,478,478
BEGIN DESCRIPTION:
TRIB 4 TO TURKEY CREEK 29.0
END DESCRIPTION:
XS GIS Cut Line= 3
      2529525.01       13480675.        2528675.       13480775.
        2527925.       13480675.
#Sta/Elev= 30
  4149.5  198.37  4231.6  197.47  4381.1  194.68  4391.2  194.81  4431.4  194.13
  4461.6  193.13    4512  192.47  4602.6  190.16  4612.7  190.29    4653   189.3
  4723.4  188.73  4733.5  188.22  4778.4  187.79  4993.3  187.38  4993.5  186.88
    4997  186.88  4997.3  187.38  5096.2  188.06  5141.5  188.74  5338.3  192.01
  5358.5  191.68  5368.6  192.38  5469.4  194.25    5501  194.41  5574.1  195.92
  5590.5  195.85  5630.9  196.62  5661.1  196.64  5681.3  197.16    5762  197.94
#Mann= 6 ,-1 , 0
  4149.5     .07       0  4231.6     .12       0  4778.4     .07       0
  4993.3     .05       0  4997.3     .07       0  5141.5     .12       0
Bank Sta=4993.3,4997.3
XS Rating Curve= 0 ,0
Exp/Cntr=0.3,0.1

Type RM Length L Ch R = 1 ,12711   ,596,596,596
BEGIN DESCRIPTION:
TRIB 4 TO TURKEY CREEK 28.0
END DESCRIPTION:
XS GIS Cut Line= 3
      2529425.03     13480625.01        2528775.       13480325.
      2527975.05     13480424.99
#Sta/Elev= 30
  4276.3  197.34    4308  196.71  4336.4  196.68  4405.3  194.66  4428.2  194.56
  4540.7  192.03  4571.4  191.92  4617.3  190.72  4622.8  190.88    4740   188.5
  4901.7  186.23  4901.9  185.73  4905.4  185.73  4905.7  186.23  4915.1  186.53
  4937.6  186.25  5090.4  186.37  5213.9  187.63    5224   188.1  5304.6  189.24
  5324.8  189.93  5425.6   191.7  5546.5  193.13    5607  194.52  5627.1  194.45
  5697.7  195.54  5717.8  196.25  5748.1  196.03  5755.6   196.6  5798.4   197.1
#Mann= 5 ,-1 , 0
  4276.3     .12       0    4740     .07       0  4901.7     .05       0
  4905.7     .07       0  5090.4     .12       0
Bank Sta=4901.7,4905.7
XS Rating Curve= 0 ,0
Exp/Cntr=0.3,0.1

Type RM Length L Ch R = 1 ,12115   ,262,262,262
BEGIN DESCRIPTION:
Mapping XS e9593cc9
END DESCRIPTION:
XS GIS Cut Line= 4
      2529292.55     13480279.18      2528797.78     13479815.66
       2528750.9     13479826.07      2527896.77     13480060.44
#Sta/Elev= 30
  4297.9  193.17  4327.4  192.49  4355.7  192.44  4412.4  191.11  4560.9  189.36
  4589.2  188.66  4631.7  188.53    4660  187.79  4709.4  187.86    4745  186.85
  4861.8  185.31    4987  184.94  4987.2  184.44  4990.7  184.44    4991  184.94
    5018  185.17  5057.5  185.54  5185.1  187.61  5190.3  187.35  5195.9  187.79
    5261  188.87  5289.3  189.72  5320.4  189.64  5351.5  190.69  5417.8   191.4
  5491.8  192.89    5507   192.6  5548.5  193.64  5605.6  194.35  5909.6  197.58
#Mann= 7 ,-1 , 0
  4297.9     .12       0  4861.8     .07       0    4987     .05       0
    4991     .07       0    5018     .12       0  5057.5     .07       0
    5261     .12       0
Bank Sta=4987,4991
XS Rating Curve= 0 ,0
Exp/Cntr=0.3,0.1

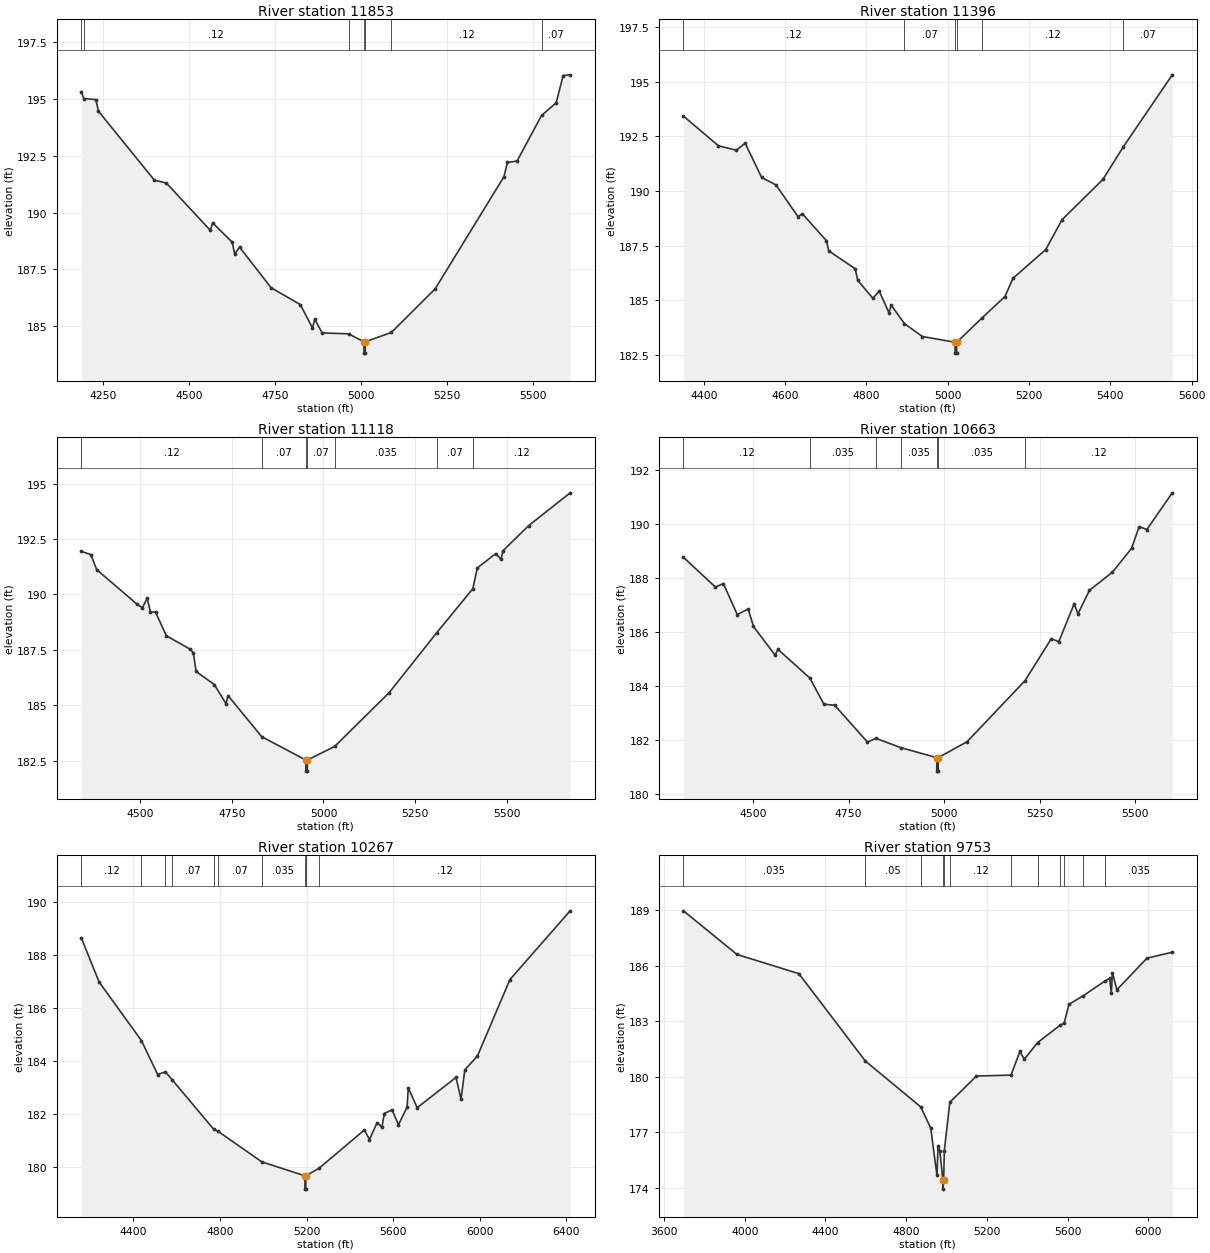
Type RM Length L Ch R = 1 ,11853   ,457,457,457
BEGIN DESCRIPTION:
TRIB 4 TO TURKEY CREEK 26.0
END DESCRIPTION:
XS GIS Cut Line= 3
      2529424.96     13480124.97        2528825.       13479575.
      2528224.97     13479474.99
#Sta/Elev= 30
  4186.6  195.32  4193.9  195.02  4228.8  194.98  4236.2  194.47    4399  191.43
  4434.1   191.3  4561.8  189.22  4568.5  189.55  4625.3   188.7  4632.7  188.18
  4646.9  188.48  4738.7  186.69  4823.8  185.95    4859  184.92  4865.8   185.3
  4887.3   184.7  4964.1  184.66  5008.6  184.31  5008.9  183.81  5012.4  183.81
  5012.6  184.31  5088.6  184.72  5215.9  186.64  5416.1  191.58  5426.3  192.21
  5454.2  192.27  5525.6  194.28  5568.2  194.84  5588.5  196.04  5608.8  196.07
#Mann= 7 ,-1 , 0
  4186.6     .07       0  4193.9     .12       0  4964.1     .07       0
  5008.6     .05       0  5012.6     .07       0  5088.6     .12       0
  5525.6     .07       0
Bank Sta=5008.6,5012.6
XS Rating Curve= 0 ,0
Exp/Cntr=0.3,0.1

Type RM Length L Ch R = 1 ,11396   ,278,278,278
BEGIN DESCRIPTION:
TRIB 4 TO TURKEY CREEK 25.0
END DESCRIPTION:
XS GIS Cut Line= 3
      2529425.01       13479425.        2528825.       13479175.
      2528274.97       13479225.
#Sta/Elev= 30
    4350  193.43  4436.1  192.07    4480  191.87  4501.7  192.19  4542.3  190.62
  4577.5  190.28  4631.7  188.83  4642.5  188.96  4701.5  187.73  4707.5  187.26
  4772.5  186.44  4778.5  185.92  4815.8  185.09  4831.5  185.42  4855.4  184.43
  4860.8  184.78  4893.6  183.93  4937.7  183.34  5018.1  183.08  5018.3  182.58
  5021.8  182.58  5022.1  183.08    5085   184.2  5140.6  185.17  5160.7  186.01
    5241  187.32  5281.2  188.69  5381.6  190.53  5432.1  192.03  5552.3  195.32
#Mann= 6 ,-1 , 0
    4350     .12       0  4893.6     .07       0  5018.1     .05       0
  5022.1     .07       0    5085     .12       0  5432.1     .07       0
Bank Sta=5018.1,5022.1
XS Rating Curve= 0 ,0
Exp/Cntr=0.3,0.1

Type RM Length L Ch R = 1 ,11118   ,455,455,455
BEGIN DESCRIPTION:
Mapping XS 4f4fdaeb
END DESCRIPTION:
XS GIS Cut Line= 3
      2529401.98     13479242.76      2528829.03     13478925.03
       2528151.9      13478904.2
#Sta/Elev= 30
    4340  191.94  4365.7   191.8  4381.8  191.12  4490.5  189.58  4506.5   189.4
  4519.5  189.84  4528.2  189.22  4542.4   189.2  4571.7  188.14    4637  187.53
  4645.3  187.37    4653  186.53  4702.5  185.94  4734.3  185.08    4740  185.44
  4831.9  183.59    4952  182.54  4952.3  182.04  4955.8  182.04    4956  182.54
  5030.5  183.15  5179.3  185.58    5309  188.28  5407.3  190.26  5419.4  191.19
  5469.4  191.84  5484.1  191.59  5489.4  191.97  5559.4   193.1  5672.6  194.58
#Mann= 7 ,-1 , 0
    4340     .12       0  4831.9     .07       0    4952     .05       0
    4956     .07       0  5030.5    .035       0    5309     .07       0
  5407.3     .12       0
Bank Sta=4952,4956
XS Rating Curve= 0 ,0
Exp/Cntr=0.3,0.1

Type RM Length L Ch R = 1 ,10663   ,396,396,396
BEGIN DESCRIPTION:
Mapping XS bc724f7e
END DESCRIPTION:
XS GIS Cut Line= 3
      2529323.85     13479024.02      2528891.53     13478518.78
      2528278.51     13478523.98
#Sta/Elev= 30
  4318.4  188.78  4401.9  187.68  4422.8  187.81    4459  186.66  4487.6  186.87
  4501.4  186.22  4557.8  185.16  4565.5  185.37  4648.7  184.31  4685.6  183.34
  4713.7   183.3  4799.3  181.94  4822.2  182.07  4886.7  181.73  4980.6  181.36
  4980.8  180.86  4984.3  180.86  4984.6  181.36  5059.9  181.95  5211.3  184.21
  5279.9  185.76  5299.9  185.66  5339.9  187.06  5349.9  186.69  5379.9  187.56
  5439.9  188.23  5489.9  189.11  5509.9  189.92  5529.9  189.81  5596.4  191.17
#Mann= 7 ,-1 , 0
  4318.4     .12       0  4648.7    .035       0  4822.2     .07       0
  4886.7    .035       0  4980.6    .035       0  4984.6    .035       0
  5211.3     .12       0
Bank Sta=4980.6,4984.6
XS Rating Curve= 0 ,0
Exp/Cntr=0.3,0.1

Type RM Length L Ch R = 1 ,10267   ,514,514,514
BEGIN DESCRIPTION:
Mapping XS c5ed691a
END DESCRIPTION:
XS GIS Cut Line= 3
      2529396.42      13478932.1      2529035.33     13478189.07
      2528455.48     13476880.08
#Sta/Elev= 30
  4159.6  188.63  4241.3  186.97  4437.1  184.76    4512  183.48  4548.2  183.58
  4578.1  183.29  4770.6  181.42  4790.7  181.34  4992.8  180.19  5192.5  179.66
  5192.7  179.16  5196.2  179.16  5196.5  179.66  5257.8  179.95    5467  181.39
  5490.3  181.03  5526.1  181.67    5548  181.49  5558.9  182.01  5594.3  182.15
  5624.5  181.59  5664.2  182.25  5669.6  182.98  5710.7  182.23  5890.1  183.37
  5913.4  182.55  5930.8  183.66  5988.7  184.17  6139.3  187.06  6417.4  189.65
#Mann= 10 ,-1 , 0
  4159.6     .12       0  4437.1     .07       0  4548.2    .035       0
  4578.1     .07       0  4770.6    .035       0  4790.7     .07       0
  4992.8    .035       0  5192.5    .035       0  5196.5    .035       0
  5257.8     .12       0
Bank Sta=5192.5,5196.5
XS Rating Curve= 0 ,0
Exp/Cntr=0.3,0.1

Type RM Length L Ch R = 1 ,9753    ,603,603,603
BEGIN DESCRIPTION:
Mapping XS b34066ee
END DESCRIPTION:
XS GIS Cut Line= 3
       2529552.7     13478925.23      2529118.66     13477675.18
      2528611.85     13476699.75
#Sta/Elev= 30
  3696.3  188.98  3961.2  186.62  4268.2  185.58  4597.9  180.85  4872.2  178.37
  4921.6  177.23  4952.7  174.66    4958  176.25  4966.8  175.99  4981.8  174.42
  4982.1  173.92  4985.8  174.42  4989.1  176.01  5016.5  178.62  5148.1  180.04
  5319.6  180.09  5363.6  181.37  5385.7  180.95  5451.4  181.85  5564.2   182.8
  5582.6  182.89  5606.8  183.92    5677  184.38  5784.8  185.18  5808.6  185.33
  5816.7  184.56  5822.3  185.63  5844.4  184.71  5993.6  186.42  6118.8  186.74
#Mann= 12 ,-1 , 0
  3696.3    .035       0  4597.9     .05       0  4872.2    .035       0
  4981.8    .035       0  4985.8    .035       0  5016.5     .12       0
  5319.6    .035       0  5451.4     .12       0  5564.2     .07       0
  5582.6    .035       0    5677     .07       0  5784.8    .035       0
Bank Sta=4981.8,4985.8
XS Rating Curve= 0 ,0
Exp/Cntr=0.3,0.1

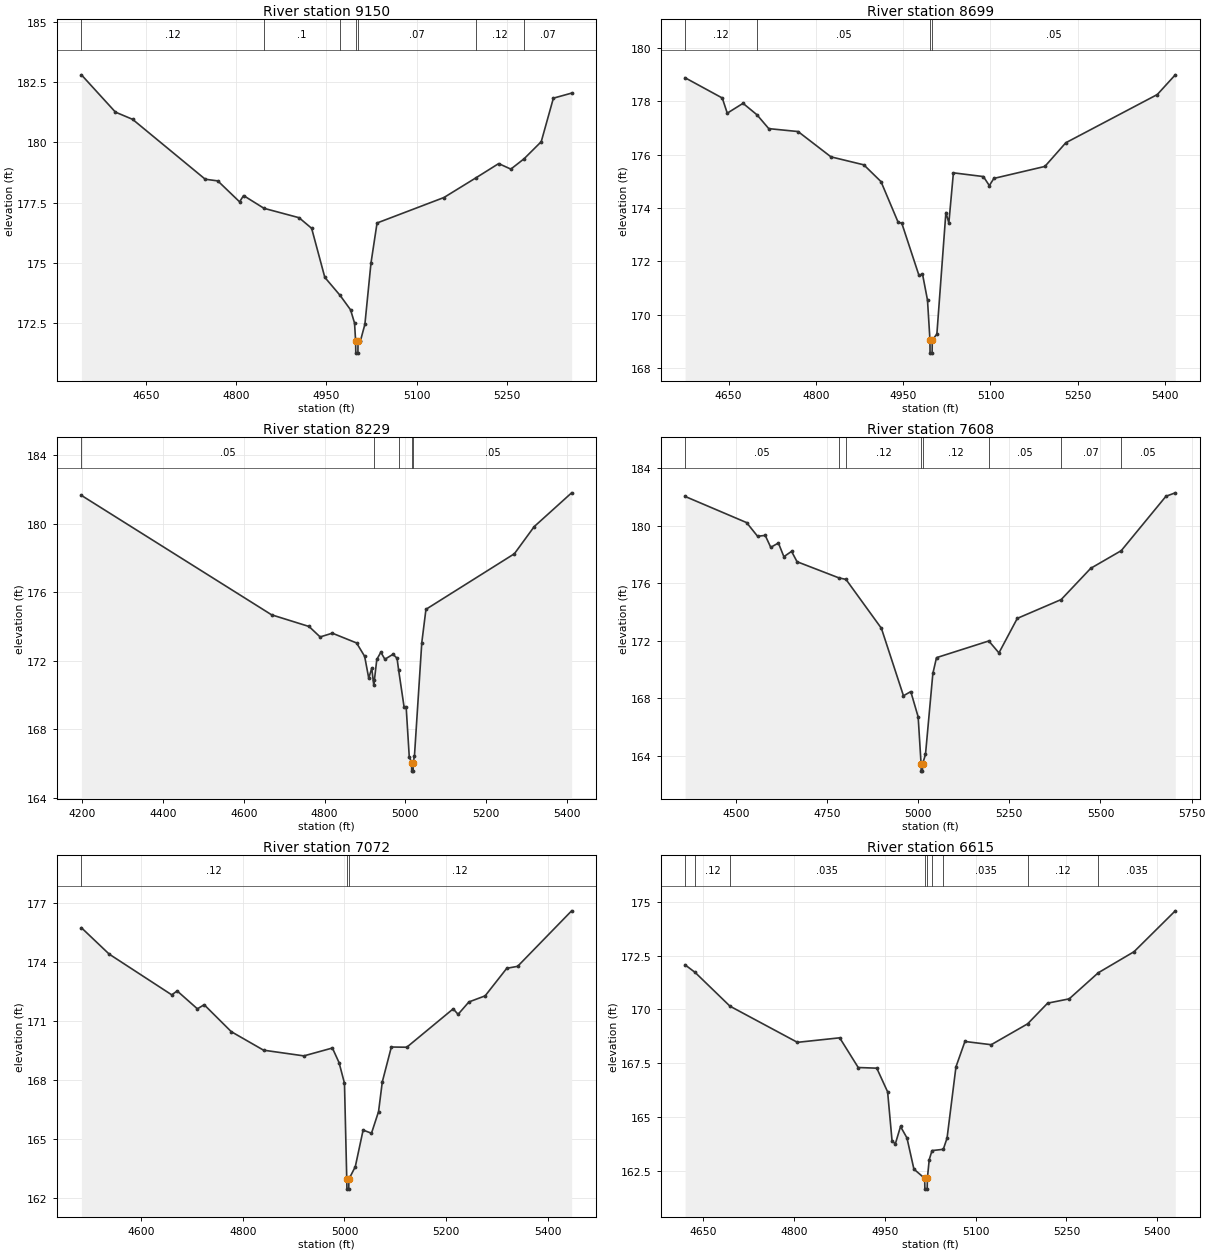
Type RM Length L Ch R = 1 ,9150    ,451,451,451
BEGIN DESCRIPTION:
TRIB 4 TO TURKEY CREEK 20.0
END DESCRIPTION:
XS GIS Cut Line= 3
      2529674.96     13477524.97        2529325.       13477225.
      2528974.98       13477275.
#Sta/Elev= 30
  4543.2  182.81  4599.7  181.26  4628.2  180.96  4748.9  178.47  4769.8   178.4
    4806  177.53  4812.6  177.79  4846.6  177.26  4904.8  176.87  4925.7  176.43
  4947.6  174.39    4973  173.64  4990.4  173.04    4997  172.49  4998.8  171.74
  4999.1  171.24  5002.6  171.24  5002.8  171.74  5006.7  171.74  5014.2  172.44
  5024.3  174.98  5034.4  176.65  5145.6  177.71  5198.2  178.52  5236.5  179.12
  5256.7  178.89  5278.7  179.32  5307.2  180.03  5327.4  181.84  5357.7  182.05
#Mann= 7 ,-1 , 0
  4543.2     .12       0  4846.6      .1       0    4973     .07       0
  4998.8     .05       0  5002.8     .07       0  5198.2     .12       0
  5278.7     .07       0
Bank Sta=4998.8,5002.8
XS Rating Curve= 0 ,0
Exp/Cntr=0.3,0.1

Type RM Length L Ch R = 1 ,8699    ,470,470,470
BEGIN DESCRIPTION:
TRIB 4 TO TURKEY CREEK 19.0
END DESCRIPTION:
XS GIS Cut Line= 3
      2529725.01     13477175.02        2529475.       13476825.
      2529075.05     13476924.99
#Sta/Elev= 30
  4575.2  178.89  4639.1  178.13  4647.7  177.56  4674.8  177.93  4698.7   177.5
    4719  176.98  4769.4  176.87  4825.9  175.92  4882.4  175.62  4911.9  174.99
  4941.4  173.46  4947.6  173.43  4977.1  171.47  4983.2  171.52  4991.8  170.54
    4996  169.05  4996.2  168.55  4999.7  168.55    5000  169.05  5007.9  169.26
  5023.4  173.83  5028.5  173.44  5036.3  175.32  5087.8  175.18  5098.1  174.84
  5105.8  175.11  5193.5  175.56  5229.5  176.45  5386.7  178.26  5417.6     179
#Mann= 4 ,-1 , 0
  4575.2     .12       0  4698.7     .05       0    4996     .05       0
    5000     .05       0
Bank Sta=4996,5000
XS Rating Curve= 0 ,0
Exp/Cntr=0.3,0.1

Type RM Length L Ch R = 1 ,8229    ,621,621,621
BEGIN DESCRIPTION:
TRIB 4 TO TURKEY CREEK 18.0
END DESCRIPTION:
XS GIS Cut Line= 3
      2530174.98       13476475.        2529375.       13476425.
      2528975.05     13476325.01
#Sta/Elev= 30
    4198  181.64  4668.9  174.68  4761.6     174  4789.1  173.39  4819.2  173.61
  4879.3  173.04  4899.3  172.26  4909.4  170.99  4916.9  171.57  4921.9  170.57
  4923.5  170.89  4929.4  172.08  4939.4   172.5  4949.4  172.09  4969.5  172.38
  4979.5  172.15  4983.5  171.45    4997   169.3  5002.1   169.3  5009.8  166.39
  5015.6  166.07  5015.8  165.57  5019.3  165.57  5019.6  166.07  5022.7  166.48
  5040.8  173.06  5051.1     175  5270.1  178.24  5319.1  179.82  5411.8  181.79
#Mann= 5 ,-1 , 0
    4198     .05       0  4923.5      .1       0  4983.5     .05       0
  5015.6     .05       0  5019.6     .05       0
Bank Sta=5015.6,5019.6
XS Rating Curve= 0 ,0
Exp/Cntr=0.3,0.1

Type RM Length L Ch R = 1 ,7608    ,536,536,536
BEGIN DESCRIPTION:
Mapping XS 5e671358
END DESCRIPTION:
XS GIS Cut Line= 4
      2530224.58     13476280.75      2529783.59     13475987.34
       2529582.2     13475963.03      2528974.59     13476032.47
#Sta/Elev= 30
    4361  182.04  4529.7  180.22  4559.8  179.27  4580.8  179.33  4595.9   178.5
  4616.9   178.8  4631.9  177.85    4653  178.22    4668   177.5  4782.4  176.38
  4802.2  176.27  4899.3  172.87  4959.8  168.18  4979.9  168.47  5000.1  166.71
  5008.1  163.44  5008.4  162.94  5011.9  162.94  5012.2  163.44  5020.2   164.1
  5040.4  169.73  5050.4  170.83  5193.8  171.99  5221.6  171.16  5271.9  173.56
  5392.3  174.87  5473.2  177.04    5557  178.27  5679.5  182.05  5705.1  182.29
#Mann= 8 ,-1 , 0
    4361     .05       0  4782.4     .07       0  4802.2     .12       0
  5008.1     .05       0  5012.2     .12       0  5193.8     .05       0
  5392.3     .07       0    5557     .05       0
Bank Sta=5008.1,5012.2
XS Rating Curve= 0 ,0
Exp/Cntr=0.3,0.1

Type RM Length L Ch R = 1 ,7072    ,457,457,457
BEGIN DESCRIPTION:
Mapping XS fd887a9d
END DESCRIPTION:
XS GIS Cut Line= 3
       2530062.4     13475688.19      2529567.56     13475510.22
      2529155.22     13475662.14
#Sta/Elev= 30
    4482  175.72  4536.7  174.38  4659.9  172.31  4670.5  172.51  4710.4   171.6
  4723.7  171.81  4777.1  170.44  4840.6   169.5  4920.1  169.21  4976.2  169.61
  4989.3  168.87    5000  167.82  5004.5  162.94  5004.8  162.44  5008.4  162.44
  5008.6  162.94  5021.3  163.58  5036.7  165.44  5053.2  165.28  5067.1  166.38
  5074.5  167.89  5092.3  169.66  5122.7  169.65  5214.1   171.6  5223.7  171.32
    5245  171.95    5277  172.26  5319.6  173.66    5341  173.76  5447.3  176.58
#Mann= 3 ,-1 , 0
    4482     .12       0  5004.5     .05       0  5008.6     .12       0
Bank Sta=5004.5,5008.6
XS Rating Curve= 0 ,0
Exp/Cntr=0.3,0.1

Type RM Length L Ch R = 1 ,6615    ,206,206,206
BEGIN DESCRIPTION:
Mapping XS f96d090c
END DESCRIPTION:
XS GIS Cut Line= 3
      2529819.31     13475032.79      2529424.33     13475176.02
      2529107.53     13475401.69
#Sta/Elev= 30
  4620.5  172.07    4637  171.72  4694.6  170.15  4805.9  168.47  4875.7  168.68
  4906.3   167.3  4936.9  167.27  4954.8  166.17  4962.2  163.87  4967.6  163.76
  4976.1  164.56  4986.7  164.03  4998.2  162.58    5016  162.15  5016.3  161.65
  5020.1  161.65  5020.4  162.15  5023.5  163.02  5028.1  163.44  5046.7   163.5
  5052.9  164.02  5067.6  167.33  5082.4  168.51  5125.8  168.36  5185.9  169.33
  5218.9  170.29  5254.5  170.49  5302.4   171.7  5361.5  172.68  5429.6  174.58
#Mann= 9 ,-1 , 0
  4620.5    .035       0    4637     .12       0  4694.6    .035       0
    5016    .035       0  5020.4    .035       0  5028.1     .12       0
  5046.7    .035       0  5185.9     .12       0  5302.4    .035       0
Bank Sta=5016,5020.4
XS Rating Curve= 0 ,0
Exp/Cntr=0.3,0.1

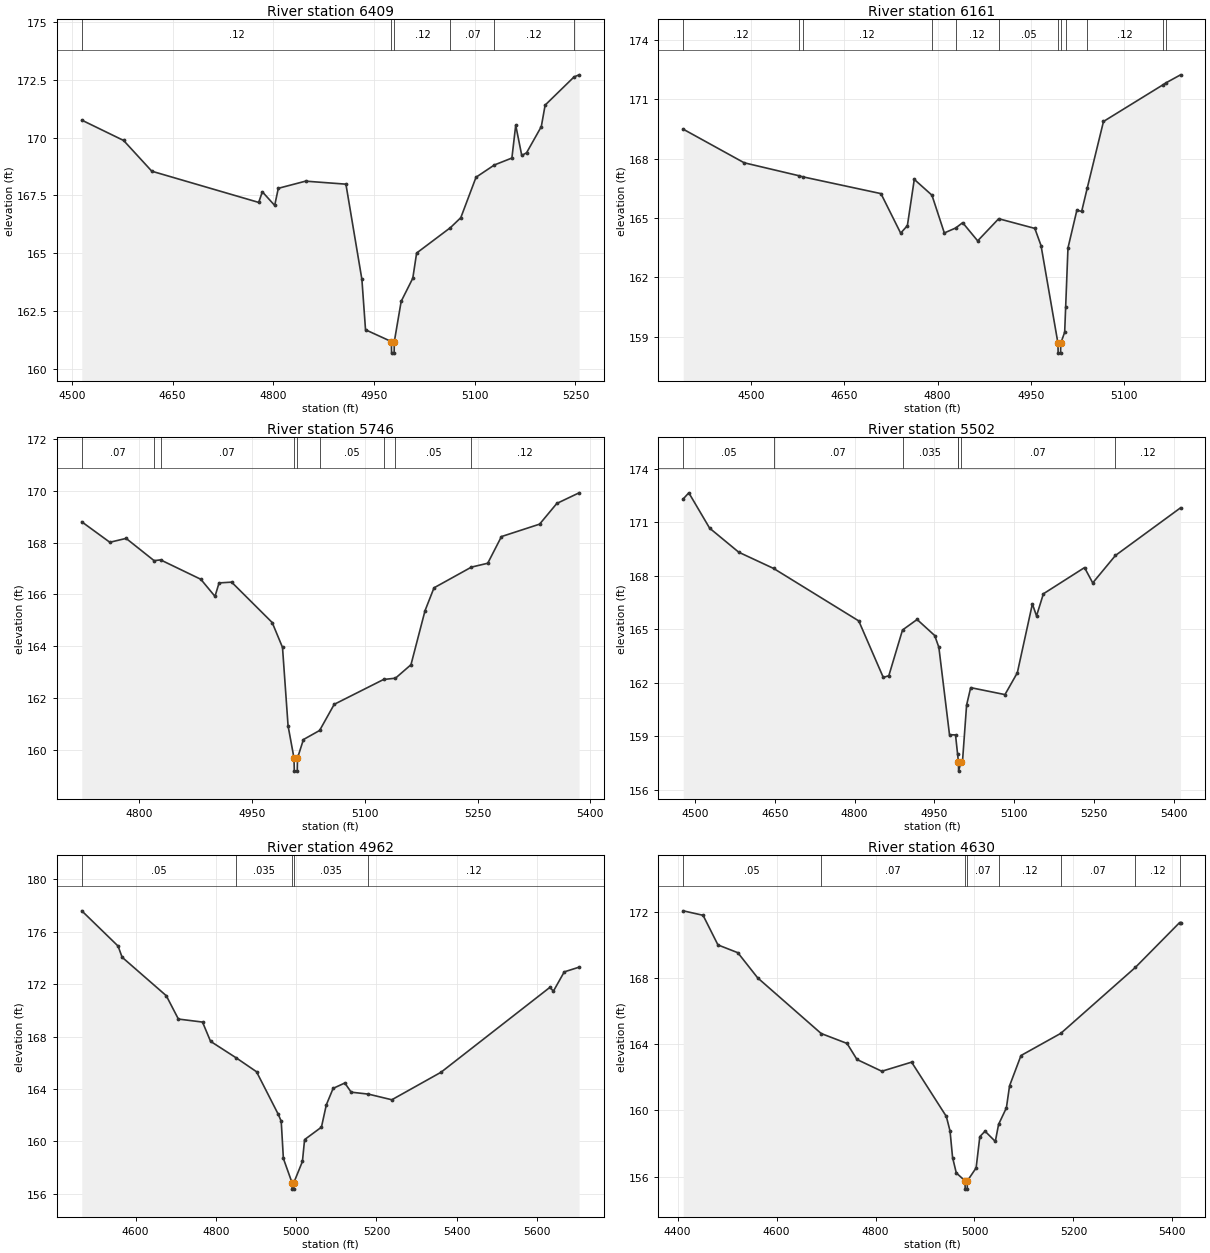
Type RM Length L Ch R = 1 ,6409    ,248,248,248
BEGIN DESCRIPTION:
Mapping XS f0b2768e
END DESCRIPTION:
XS GIS Cut Line= 3
      2529732.53     13474898.23      2529285.45     13475084.88
      2529059.85     13475206.35
#Sta/Elev= 30
  4514.7  170.76    4577  169.88    4619  168.55  4778.2   167.2  4783.6  167.66
    4802  167.07  4807.4  167.81    4848  168.12  4908.1  167.99  4931.9  163.87
  4937.3  161.69  4975.8  161.18  4976.1  160.68  4979.9  160.68  4980.2  161.18
  4990.4  162.92  5007.7  163.92  5013.4  165.01  5063.8  166.11  5079.2  166.54
  5101.9  168.29  5129.2  168.82  5155.3  169.12    5161  170.54    5170  169.23
  5177.2  169.35  5199.1  170.48  5204.8  171.41  5247.9  172.63  5255.4  172.72
#Mann= 6 ,-1 , 0
  4514.7     .12       0  4975.8     .05       0  4980.2     .12       0
  5063.8     .07       0  5129.2     .12       0  5247.9     .07       0
Bank Sta=4975.8,4980.2
XS Rating Curve= 0 ,0
Exp/Cntr=0.3,0.1

Type RM Length L Ch R = 1 ,6161    ,415,415,415
BEGIN DESCRIPTION:
Mapping XS 51ad77f2
END DESCRIPTION:
XS GIS Cut Line= 3
      2529689.07     13474672.56      2529120.51     13474902.58
        2529000.     13475044.62
#Sta/Elev= 30
  4390.9  169.49  4488.9  167.79  4576.3  167.14  4583.1  167.08  4708.8  166.23
  4740.5  164.23  4751.3  164.61  4762.4  166.95  4790.8  166.15  4810.7  164.24
  4828.9  164.49  4840.2  164.76  4864.3  163.84  4898.1  164.96  4956.2  164.47
  4966.2   163.6  4993.4  158.66  4993.7  158.16  4997.6  158.16  4997.9  158.66
  5004.2  159.22  5005.8  160.51  5009.5  163.48  5023.8  165.39  5031.5  165.33
  5040.4   166.5  5066.6  169.88    5163  171.75  5166.8  171.83  5190.5  172.24
#Mann= 12 ,-1 , 0
  4390.9     .12       0  4576.3    .035       0  4583.1     .12       0
  4790.8     .05       0  4828.9     .12       0  4898.1     .05       0
  4993.4     .05       0  4997.9     .05       0  5005.8    .035       0
  5040.4     .12       0    5163    .035       0  5166.8     .12       0
Bank Sta=4993.4,4997.9
XS Rating Curve= 0 ,0
Exp/Cntr=0.3,0.1

Type RM Length L Ch R = 1 ,5746    ,244,244,244
BEGIN DESCRIPTION:
Mapping XS 44aa76a2
END DESCRIPTION:
XS GIS Cut Line= 3
      2529619.61     13474511.97      2529372.25     13474611.78
      2528986.01      13474689.9
#Sta/Elev= 30
  4724.2   168.8  4761.5  168.01  4783.1  168.16  4820.3   167.3  4828.9  167.33
  4882.4  166.58  4901.2  165.92  4906.6  166.44  4923.3  166.47  4977.2  164.91
  4990.9  163.95  4998.3  160.92  5006.2  159.67  5006.6  159.17  5010.5  159.17
  5010.8  159.67  5018.7  160.39  5040.2  160.74  5059.6  161.75  5125.2  162.71
    5141  162.76  5161.6  163.28  5180.3  165.37  5192.2  166.25  5241.9  167.05
  5263.6   167.2  5281.8  168.23  5332.5  168.71  5355.4  169.51    5385  169.92
#Mann= 9 ,-1 , 0
  4724.2     .07       0  4820.3    .035       0  4828.9     .07       0
  5006.2     .05       0  5010.8     .07       0  5040.2     .05       0
  5125.2    .035       0    5141     .05       0  5241.9     .12       0
Bank Sta=5006.2,5010.8
XS Rating Curve= 0 ,0
Exp/Cntr=0.3,0.1

Type RM Length L Ch R = 1 ,5502    ,540,540,540
BEGIN DESCRIPTION:
TRIB 4 TO TURKEY CREEK 12.0
END DESCRIPTION:
XS GIS Cut Line= 3
      2529725.03     13474274.99        2529225.       13474425.
      2528824.95     13474525.01
#Sta/Elev= 30
  4477.9  172.31  4488.4  172.65  4527.5  170.67  4582.3  169.32  4647.8  168.41
  4807.7  165.47  4853.8   162.3  4864.2   162.4  4889.9  164.96  4917.3  165.55
  4950.4  164.65  4958.2  163.99  4978.2  159.09  4989.5  159.08  4993.4     158
    4995  157.55  4995.3  157.05  4999.6  157.55  5002.5  157.55  5010.3  160.75
    5018  161.73  5082.4  161.34  5105.6  162.56  5133.9  166.42  5141.7  165.75
  5154.6  166.99  5231.9  168.46  5247.3   167.6    5290  169.14  5412.3  171.81
#Mann= 7 ,-1 , 0
  4477.9     .05       0  4647.8     .07       0  4889.9    .035       0
  4993.4     .07       0    4995     .05       0  4999.6     .07       0
    5290     .12       0
Bank Sta=4995,4999.6
XS Rating Curve= 0 ,0
Exp/Cntr=0.3,0.1

Type RM Length L Ch R = 1 ,4962    ,332,332,332
BEGIN DESCRIPTION:
Mapping XS 31f2ba8c
END DESCRIPTION:
XS GIS Cut Line= 4
      2529825.22      13473964.3      2529446.78     13473943.47
      2529175.95     13474058.05      2528714.14     13474384.45
#Sta/Elev= 30
    4466   177.6  4556.4  174.91  4566.4  174.06  4676.5  171.12  4706.6  169.34
  4766.7  169.11  4786.7  167.64    4851  166.37  4901.2  165.32  4955.5  162.06
  4962.7  161.54  4968.1   158.7  4989.5  156.86  4989.8  156.36  4993.8  156.36
  4994.2  156.86  5015.5  158.47  5020.9  160.14  5062.9  161.09    5075  162.79
    5092  164.05  5121.1  164.46  5136.9  163.76    5180  163.61  5238.2  163.18
  5360.7  165.28  5631.9  171.76  5640.6  171.47  5667.6  172.94  5704.6   173.3
#Mann= 5 ,-1 , 0
    4466     .05       0    4851    .035       0  4989.5    .035       0
  4994.2    .035       0    5180     .12       0
Bank Sta=4989.5,4994.2
XS Rating Curve= 0 ,0
Exp/Cntr=0.3,0.1

Type RM Length L Ch R = 1 ,4630    ,487,487,487
BEGIN DESCRIPTION:
TRIB 4 TO TURKEY CREEK 10.0
END DESCRIPTION:
XS GIS Cut Line= 3
      2529624.97       13473775.        2529025.       13473825.
      2528674.97     13474025.02
#Sta/Elev= 30
  4411.3  172.06  4451.4  171.79  4481.5     170  4521.7  169.53  4561.8  168.01
  4690.1  164.65  4742.4  164.05  4762.5  163.08  4812.7  162.37  4872.9  162.92
  4943.1  159.64  4950.6  158.76  4955.7  157.16  4963.2  156.23  4980.9  155.75
  4981.2  155.25  4985.3  155.25  4985.6  155.75  5003.3  156.53  5010.8  158.42
  5021.3  158.75  5042.1  158.13  5048.7  159.16  5064.5  160.16  5070.9  161.49
    5094  163.32  5174.5  164.66  5325.1  168.64  5414.6  171.35  5416.5  171.35
#Mann= 8 ,-1 , 0
  4411.3     .05       0  4690.1     .07       0  4980.9     .05       0
  4985.6     .07       0  5048.7     .12       0  5174.5     .07       0
  5325.1     .12       0  5414.6     .07       0
Bank Sta=4980.9,4985.6
XS Rating Curve= 0 ,0
Exp/Cntr=0.3,0.1

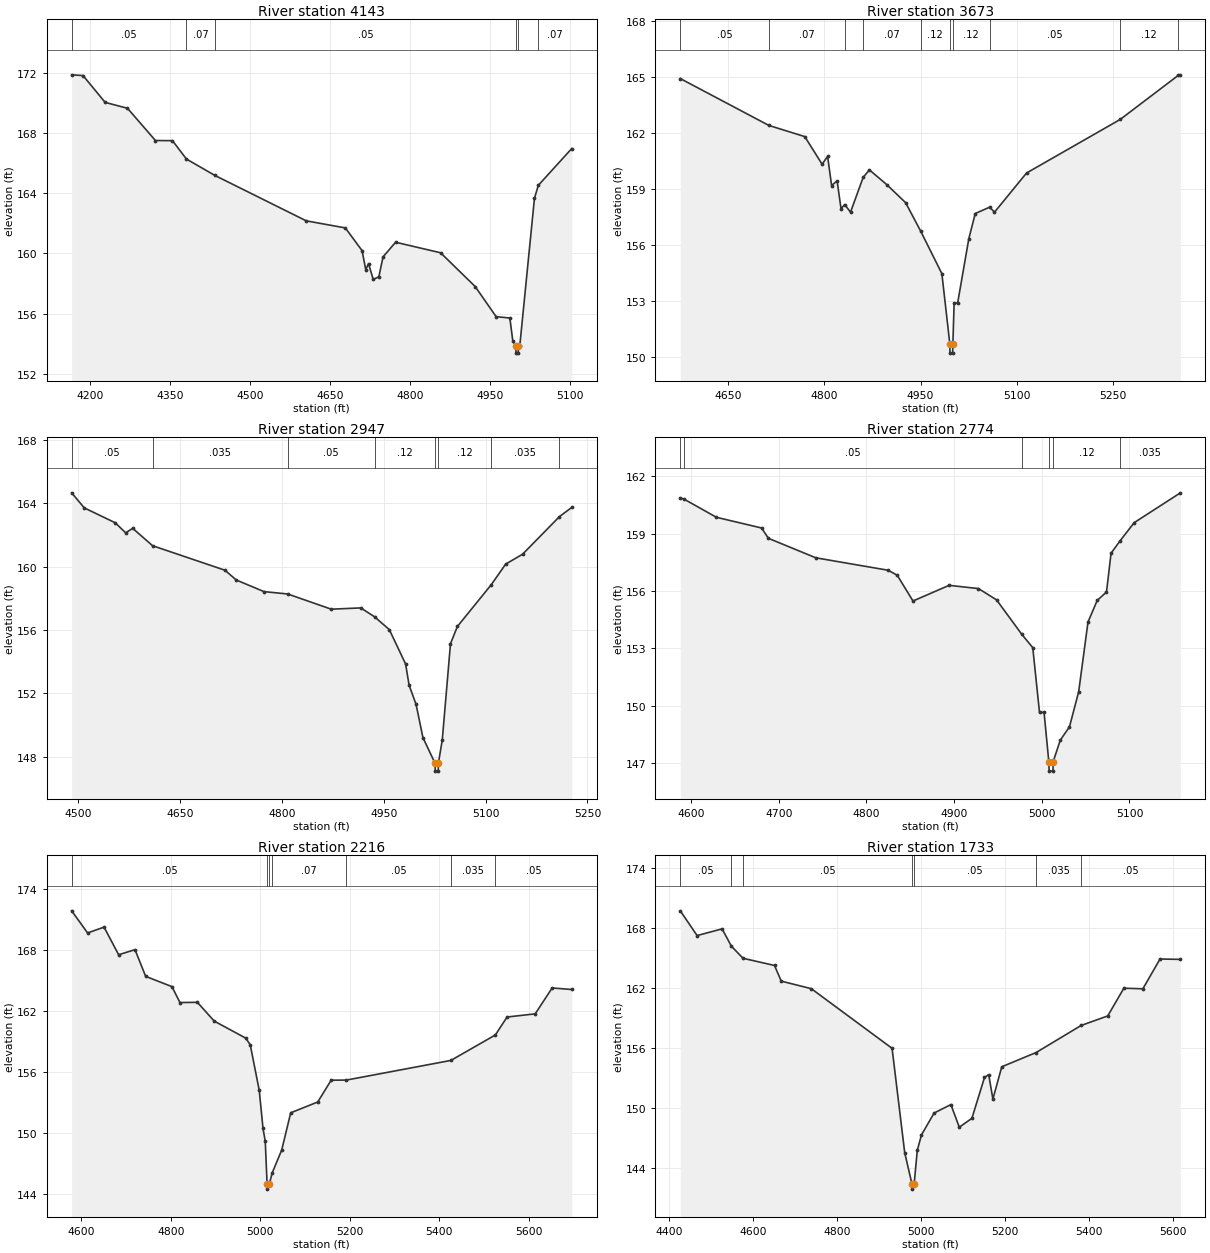
Type RM Length L Ch R = 1 ,4143    ,470,470,470
BEGIN DESCRIPTION:
TRIB 4 TO TURKEY CREEK 9.0
END DESCRIPTION:
XS GIS Cut Line= 3
      2529624.97     13473674.99        2528825.       13473425.
      2528725.02       13473425.
#Sta/Elev= 30
  4165.7  171.85  4187.1   171.8  4228.5  170.02  4270.4  169.63  4322.8  167.49
  4354.8  167.48    4381  166.26  4434.5  165.17  4605.7  162.16    4679  161.69
  4710.5  160.18  4717.3  158.92  4722.5  159.32  4731.4  158.27  4741.9  158.45
  4749.8  159.77  4773.3  160.74  4857.7  160.04  4922.6   157.8  4961.9   155.8
  4987.6  155.71  4993.3  154.16  4998.8  153.88  4999.2  153.38  5003.3  153.38
  5003.6  153.88  5006.3  153.88  5033.8  163.66  5041.1  164.52  5103.8  166.96
#Mann= 6 ,-1 , 0
  4165.7     .05       0    4381     .07       0  4434.5     .05       0
  4998.8     .05       0  5003.6     .05       0  5041.1     .07       0
Bank Sta=4998.8,5003.6
XS Rating Curve= 0 ,0
Exp/Cntr=0.3,0.1

Type RM Length L Ch R = 1 ,3673    ,726,726,726
BEGIN DESCRIPTION:
TRIB 4 TO TURKEY CREEK 8.0
END DESCRIPTION:
XS GIS Cut Line= 3
      2529475.01     13473325.01        2529125.       13473075.
      2528775.03       13473075.
#Sta/Elev= 30
  4575.2  164.91  4713.3   162.4  4769.4   161.8  4796.4  160.32    4805  160.74
  4811.2  159.18  4819.8  159.43  4825.9  157.94  4831.7  158.16  4840.7  157.75
  4860.4  159.61  4870.1  160.02  4897.2  159.23  4926.7  158.26  4950.1  156.74
  4983.2  154.46  4995.6   150.7  4995.9   150.2    5000   150.2  5000.4   150.7
  5002.3  152.88  5007.8  152.88  5025.3  156.34  5035.3  157.68  5057.8  158.02
  5065.3  157.75  5115.3  159.85  5261.4  162.72  5351.9  165.08  5355.3  165.11
#Mann= 10 ,-1 , 0
  4575.2     .05       0  4713.3     .07       0  4831.7     .05       0
  4860.4     .07       0  4950.1     .12       0  4995.6     .05       0
  5000.4     .12       0  5057.8     .05       0  5261.4     .12       0
  5351.9     .05       0
Bank Sta=4995.6,5000.4
XS Rating Curve= 0 ,0
Exp/Cntr=0.3,0.1

Type RM Length L Ch R = 1 ,2947    ,173,173,173
BEGIN DESCRIPTION:
Mapping XS 587f3735
END DESCRIPTION:
XS GIS Cut Line= 3
       2529593.2     13472721.95      2529137.51     13472635.15
      2528869.19     13472682.76
#Sta/Elev= 30
  4490.6  164.66  4509.1  163.71  4554.7  162.77  4570.2  162.13  4580.4  162.42
  4609.7  161.32  4716.3  159.77  4733.1  159.15  4773.8  158.42  4808.7  158.27
  4872.8  157.31  4916.3  157.39  4936.6  156.83  4958.3  156.02  4982.3  153.85
  4987.5   152.5  4997.7   151.3  5007.8   149.2  5025.6  147.58    5026  147.08
  5030.3  147.08  5030.6  147.58  5036.3  149.05  5048.4  155.13  5058.6  156.22
  5108.5  158.86  5129.7  160.16  5154.5  160.78  5208.9  163.16    5227  163.74
#Mann= 8 ,-1 , 0
  4490.6     .05       0  4609.7    .035       0  4808.7     .05       0
  4936.6     .12       0  5025.6     .05       0  5030.6     .12       0
  5108.5    .035       0  5208.9     .12       0
Bank Sta=5025.6,5030.6
XS Rating Curve= 0 ,0
Exp/Cntr=0.3,0.1

Type RM Length L Ch R = 1 ,2774    ,558,558,558
BEGIN DESCRIPTION:
TRIB 4 TO TURKEY CREEK 6.0
END DESCRIPTION:
XS GIS Cut Line= 3
      2529474.97     13472574.99        2529075.       13472475.
      2528924.99       13472525.
#Sta/Elev= 30
  4587.7  160.87    4592  160.81  4628.9  159.86  4680.4   159.3  4688.2  158.76
  4742.3  157.74  4824.7  157.09  4835.1  156.83  4853.1  155.48  4894.3   156.3
  4927.8  156.13  4948.4  155.54  4977.3  153.73  4989.7  153.04  4997.4  149.65
  5002.6  149.65    5008  147.08  5008.4  146.58  5012.7  146.58    5013  147.08
  5021.1   148.2  5031.6   148.9  5042.1  150.74  5052.7  154.38  5063.2  155.51
  5073.8  155.95    5079  157.98  5089.3  158.63  5105.4  159.58  5158.1  161.14
#Mann= 6 ,-1 , 0
  4587.7    .035       0    4592     .05       0  4977.3     .12       0
    5008     .05       0    5013     .12       0  5089.3    .035       0
Bank Sta=5008,5013
XS Rating Curve= 0 ,0
Exp/Cntr=0.3,0.1

Type RM Length L Ch R = 1 ,2216    ,483,483,483
BEGIN DESCRIPTION:
Mapping XS a2be44a8
END DESCRIPTION:
XS GIS Cut Line= 4
      2529821.82     13472294.18      2529564.84     13472186.53
      2529214.14     13472148.33      2528731.46     13472210.84
#Sta/Elev= 30
  4578.1  171.82  4613.7  169.65  4650.5  170.22  4683.1  167.51  4719.7  168.01
  4743.5  165.39  4802.3  164.38  4820.2  162.82  4859.2  162.84  4896.8     161
  4967.2  159.33  4977.3  158.68  4997.4  154.22  5005.9  150.46  5010.9  149.21
    5015  145.01  5015.4  144.51  5020.1  145.01  5026.2  146.08  5047.7  148.35
  5067.8     152  5128.2  153.06  5158.3   155.2  5192.2  155.21  5425.9  157.14
  5525.4  159.64  5551.5   161.4  5614.4  161.71  5652.3  164.25  5696.2   164.1
#Mann= 7 ,-1 , 0
  4578.1     .05       0    5015     .05       0  5020.1     .05       0
  5026.2     .07       0  5192.2     .05       0  5425.9    .035       0
  5525.4     .05       0
Bank Sta=5015,5020.1
XS Rating Curve= 0 ,0
Exp/Cntr=0.3,0.1

Type RM Length L Ch R = 1 ,1733    ,526,526,526
BEGIN DESCRIPTION:
Mapping XS 75eaec34
END DESCRIPTION:
XS GIS Cut Line= 4
      2529807.87     13471967.76       2529519.7     13471808.05
      2529099.56     13471801.11      2528689.92     13471964.27
#Sta/Elev= 30
  4426.2  169.75  4466.2  167.27  4525.7  167.94  4547.9   166.2  4575.6  164.99
  4650.5  164.27  4666.5   162.7  4738.2  161.94  4930.4  155.96  4960.4  145.51
  4977.8  142.34  4978.2  141.84  4982.9  142.34  4990.4  145.73  5000.4  147.28
  5030.4  149.47  5070.4  150.32  5090.4  148.05  5120.4  148.94  5150.4  153.04
  5160.4  153.32  5170.4  150.87  5191.5  154.11  5273.3  155.54  5380.3  158.25
  5443.8  159.21  5482.2  161.99  5527.4  161.93  5568.3  164.92  5616.8  164.88
#Mann= 7 ,-1 , 0
  4426.2     .05       0  4547.9     .07       0  4575.6     .05       0
  4977.8     .05       0  4982.9     .05       0  5273.3    .035       0
  5380.3     .05       0
Bank Sta=4977.8,4982.9
XS Rating Curve= 0 ,0
Exp/Cntr=0.3,0.1