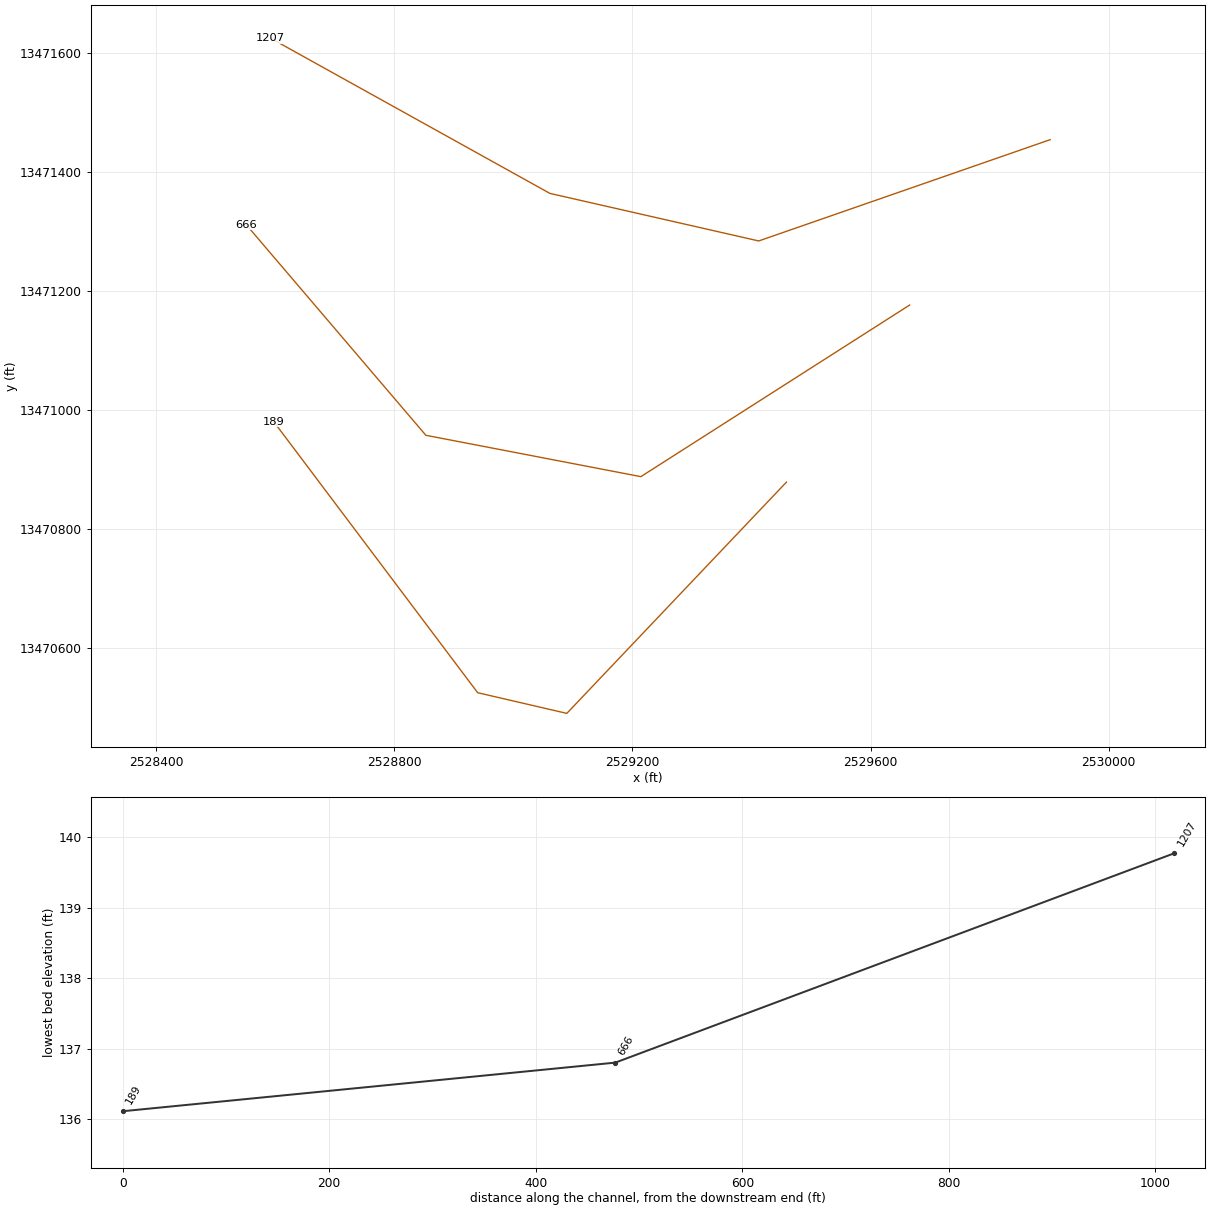
HEC-RAS study TRIB 4 TO TURKEY CREEK.prj: TRIB 4 TO TURKEY CREEK Base Level Engineering

--- TRIB 4 TO TURKEY CREEK.g01 (geometry) --- (continued)

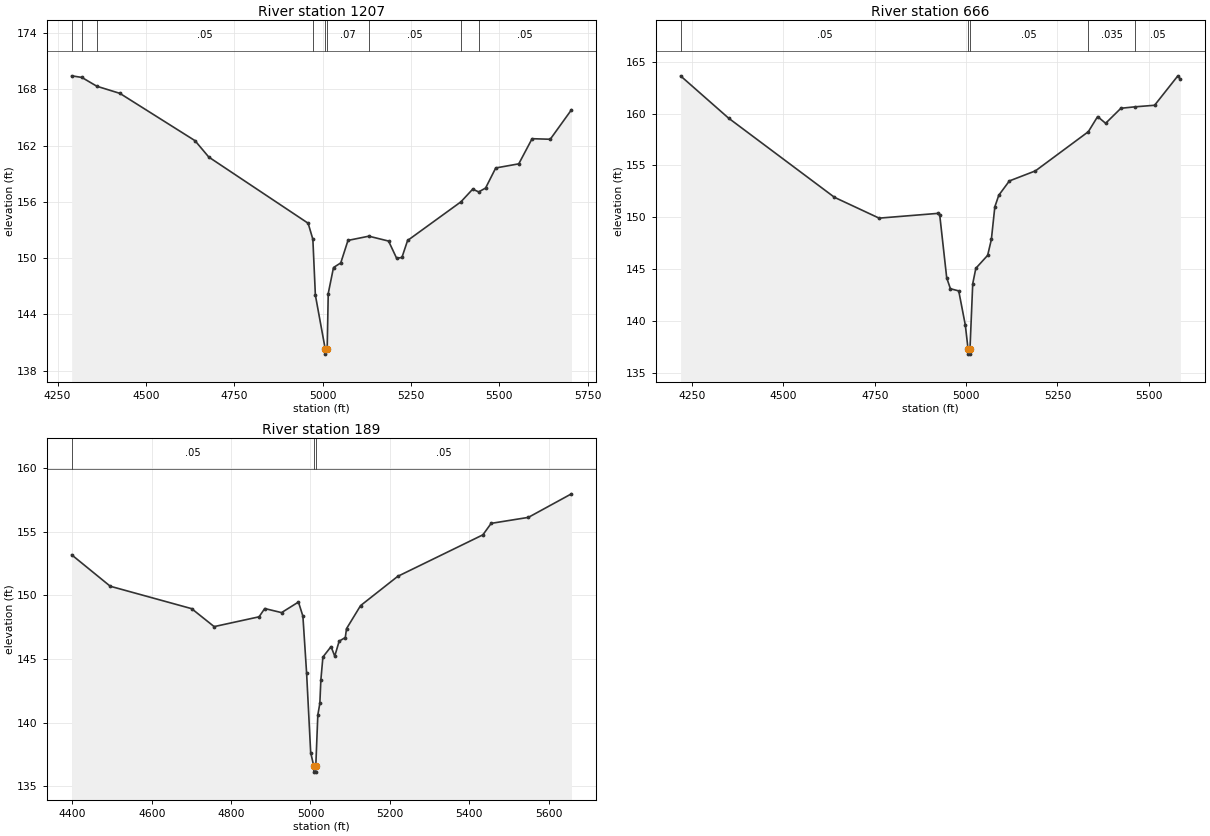
Type RM Length L Ch R = 1 ,1207    ,541,541,541
BEGIN DESCRIPTION:
Mapping XS e29275c1
END DESCRIPTION:
XS GIS Cut Line= 4
      2529901.61     13471453.87      2529412.06     13471283.75
      2529061.37     13471363.61      2528592.59     13471624.04
#Sta/Elev= 30
  4289.9  169.43  4318.7  169.26  4361.2  168.32  4426.4  167.56  4638.9  162.52
    4678  160.77    4959  153.72  4972.4  152.01  4979.5  146.06  5007.6  140.27
    5008  139.77  5012.9  140.27  5015.9  146.23  5030.8     149  5051.3  149.49
  5071.8  151.89  5130.8  152.34  5186.6  151.82  5209.4  149.99  5224.4  150.07
  5240.4  151.88  5391.3     156  5424.6  157.35  5441.7  157.06  5461.1  157.47
  5489.8  159.61    5555  160.05  5592.7  162.73  5644.1  162.67  5704.1  165.81
#Mann= 9 ,-1 , 0
  4289.9     .05       0  4318.7     .12       0  4361.2     .05       0
  4972.4     .07       0  5007.6     .05       0  5012.9     .07       0
  5130.8     .05       0  5391.3    .035       0  5441.7     .05       0
Bank Sta=5007.6,5012.9
XS Rating Curve= 0 ,0
Exp/Cntr=0.3,0.1

Type RM Length L Ch R = 1 ,666     ,477,477,477
BEGIN DESCRIPTION:
Mapping XS 41801259
END DESCRIPTION:
XS GIS Cut Line= 4
      2529665.54     13471176.11      2529214.14     13470887.91
      2528853.03     13470957.36      2528551.59     13471310.78
#Sta/Elev= 30
  4218.8  163.64    4350  159.57  4639.8  151.93    4762  149.92  4922.9  150.38
    4928  150.19    4947  144.16  4957.1  143.11  4979.9   142.9  4997.9  139.61
  5005.4   137.3  5005.8   136.8  5010.3   136.8  5010.7   137.3  5018.2  143.59
  5026.7  145.08    5059  146.33  5069.2  147.86  5078.7  151.01  5089.5  152.13
  5118.5  153.51  5189.8  154.48  5334.6  158.26    5360  159.72  5381.9  159.07
  5423.7  160.52  5462.5  160.66  5515.9  160.81  5579.6  163.65  5586.6  163.33
#Mann= 5 ,-1 , 0
  4218.8     .05       0  5005.4     .05       0  5010.7     .05       0
  5334.6    .035       0  5462.5     .05       0
Bank Sta=5005.4,5010.7
XS Rating Curve= 0 ,0
Exp/Cntr=0.3,0.1

Type RM Length L Ch R = 1 ,189     ,0,0,0
BEGIN DESCRIPTION:
TRIB 4 TO TURKEY CREEK 1.0
END DESCRIPTION:
XS GIS Cut Line= 4
      2529458.66     13470878.75      2529089.77     13470490.33
      2528940.03     13470525.05      2528597.45     13470980.38
#Sta/Elev= 30
  4398.3  153.18  4495.6  150.71  4700.6  148.95  4757.3  147.54  4870.5  148.31
  4884.7  148.96  4927.1  148.64  4969.7  149.47  4980.9  148.36  4990.2   143.9
  5000.5  137.65  5008.1  136.61  5008.5  136.11    5013  136.11  5013.4  136.61
  5018.5   140.6  5023.6  141.51  5026.1  143.33  5031.3  145.15  5051.8  145.97
  5061.1  145.22  5072.3   146.4  5087.7  146.68  5090.8  147.38  5126.2  149.19
  5219.9  151.49  5434.4  154.75  5455.2  155.65  5548.9  156.12  5657.5  157.97
#Mann= 3 ,-1 , 0
  4398.3     .05       0  5008.1     .05       0  5013.4     .05       0
Bank Sta=5008.1,5013.4
XS Rating Curve= 0 ,0
Exp/Cntr=0.3,0.1

Chan Stop Cuts=-1
Use User Specified Reach Order=0
Composite Channel Slope=5