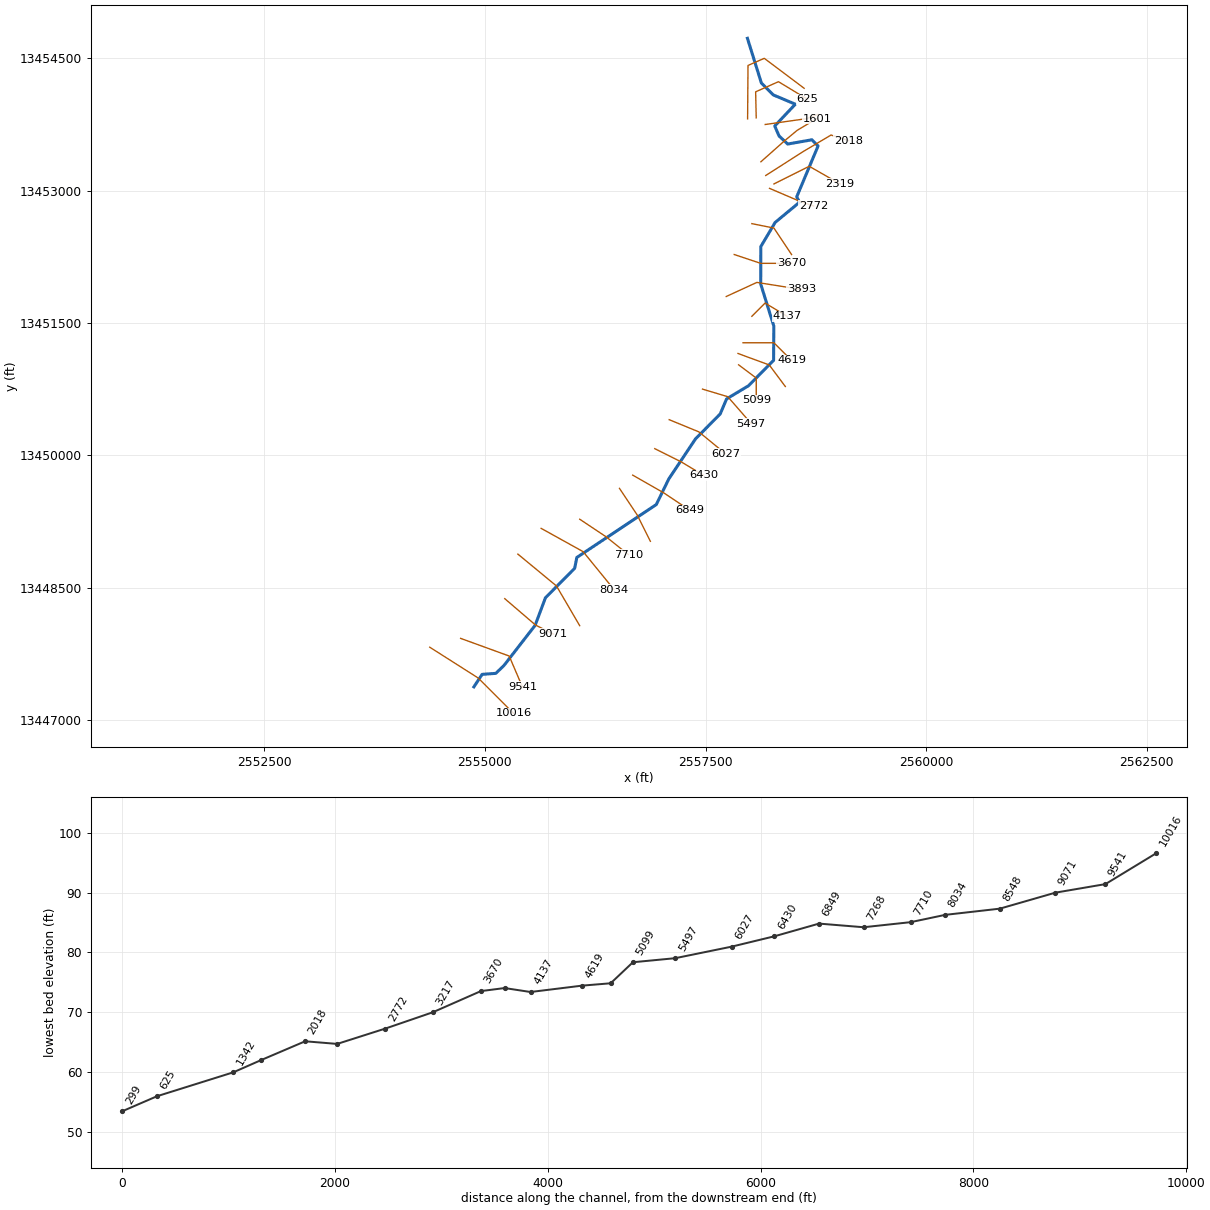
--- TRIB 4A TO COLETO CREEK.prj (project) ---

Proj Title=TRIB 4A TO COLETO CREEK Base Level Engineering
Current Plan=p01
Default Exp/Contr=0.3,0.1
English Units
Geom File=g01
Flow File=f01
Plan File=p01
Y Axis Title=Elevation
X Axis Title(PF)=Main Channel Distance
X Axis Title(XS)=Station
BEGIN DESCRIPTION:
TRIB 4A TO COLETO CREEK
END DESCRIPTION:
DSS Export Rating Curves= 0
DSS Export Rating Curve Sorted= 0
DSS Export Volume Flow Curves= 0
DXF OffsetX= 0
DXF OffsetY= 0
DXF ScaleX= 1
DXF ScaleY= 10

--- TRIB 4A TO COLETO CREEK.p01 (plan) ---

Plan Title=Multiple Run
Short Identifier=Multiple
Geom File=g01
Flow File=f01
Subcritical Flow
K Sum by GR= 0
Std Step Tol= 0.01
Critical Tol= 0.01
Num of Std Step Trials= 20
Max Error Tol= 0.3
Flow Tol Ratio= 0.001
Split Flow NTrial= 30
Split Flow Tol= 0.02
Split Flow Ratio= 0.02
Log Output Level= 0
Friction Slope Method= 1
Unsteady Friction Slope Method= 2
Unsteady Bridges Friction Slope Method= 1
Parabolic Critical Depth
Global Vel Dist=  1 , 1 , 1
Global Log Level= 0
CheckData=True
Encroach Param= -1, 0, 0, 0
BEGIN DESCRIPTION:
Multiple Run
END DESCRIPTION:

--- TRIB 4A TO COLETO CREEK.f01 (steady flow) ---

Flow Title=Multiple
Number of Profiles=7
Profile Names=10-year,25-year,50-year,1pct_min,100-year,1pct_plu,500-year
River Rch & RM= TRIB 4A TO COLET,Reach-1,10016
     521     805    1049     661    1319    2632    2061
River Rch & RM= TRIB 4A TO COLET,Reach-1,9541
     712    1124    1487     950    1896    3783    3047
River Rch & RM= TRIB 4A TO COLET,Reach-1,6027
    1076    1739    2338    1517    3027    6041    5020
Boundary for River Rch & Prof#=TRIB 4A TO COLET,Reach-1,1
Up Type=0
Dn Type=3
Dn Slope=0.005
Boundary for River Rch & Prof#=TRIB 4A TO COLET,Reach-1,2
Up Type=0
Dn Type=3
Dn Slope=0.005
Boundary for River Rch & Prof#=TRIB 4A TO COLET,Reach-1,3
Up Type=0
Dn Type=3
Dn Slope=0.005
Boundary for River Rch & Prof#=TRIB 4A TO COLET,Reach-1,4
Up Type=0
Dn Type=3
Dn Slope=0.005
Boundary for River Rch & Prof#=TRIB 4A TO COLET,Reach-1,5
Up Type=0
Dn Type=3
Dn Slope=0.005
Boundary for River Rch & Prof#=TRIB 4A TO COLET,Reach-1,6
Up Type=0
Dn Type=3
Dn Slope=0.005
Boundary for River Rch & Prof#=TRIB 4A TO COLET,Reach-1,7
Up Type=0
Dn Type=3
Dn Slope=0.005

--- TRIB 4A TO COLETO CREEK.g01 (geometry) ---

Geom Title=Existing Conditions
Program Version=4.10

River Reach=TRIB 4A TO COLET,Reach-1
Reach XY= 30
        2554875.       13447375.      2554968.52     13447517.32
      2555123.54     13447528.54      2555214.23      13447615.3
      2555569.17      13448072.7      2555685.76     13448384.68
      2556017.14     13448718.83      2556041.44     13448841.79
      2556942.08     13449441.42      2557083.14     13449731.06
      2557385.78     13450184.68      2557666.86     13450468.94
      2557738.47     13450638.57      2557988.21     13450788.63
      2558271.46     13451076.46      2558273.78      13451464.5
      2558125.52     13451940.22       2558126.2      13452364.5
      2558288.63     13452638.21      2558565.71     13452868.31
      2558533.25     13452928.23      2558775.27     13453505.06
      2558705.06     13453575.26      2558430.85     13453527.04
      2558333.11     13453618.93      2558284.37     13453731.66
      2558517.53     13453978.62      2558268.94     13454083.14
      2558132.86     13454218.83        2557975.       13454725.

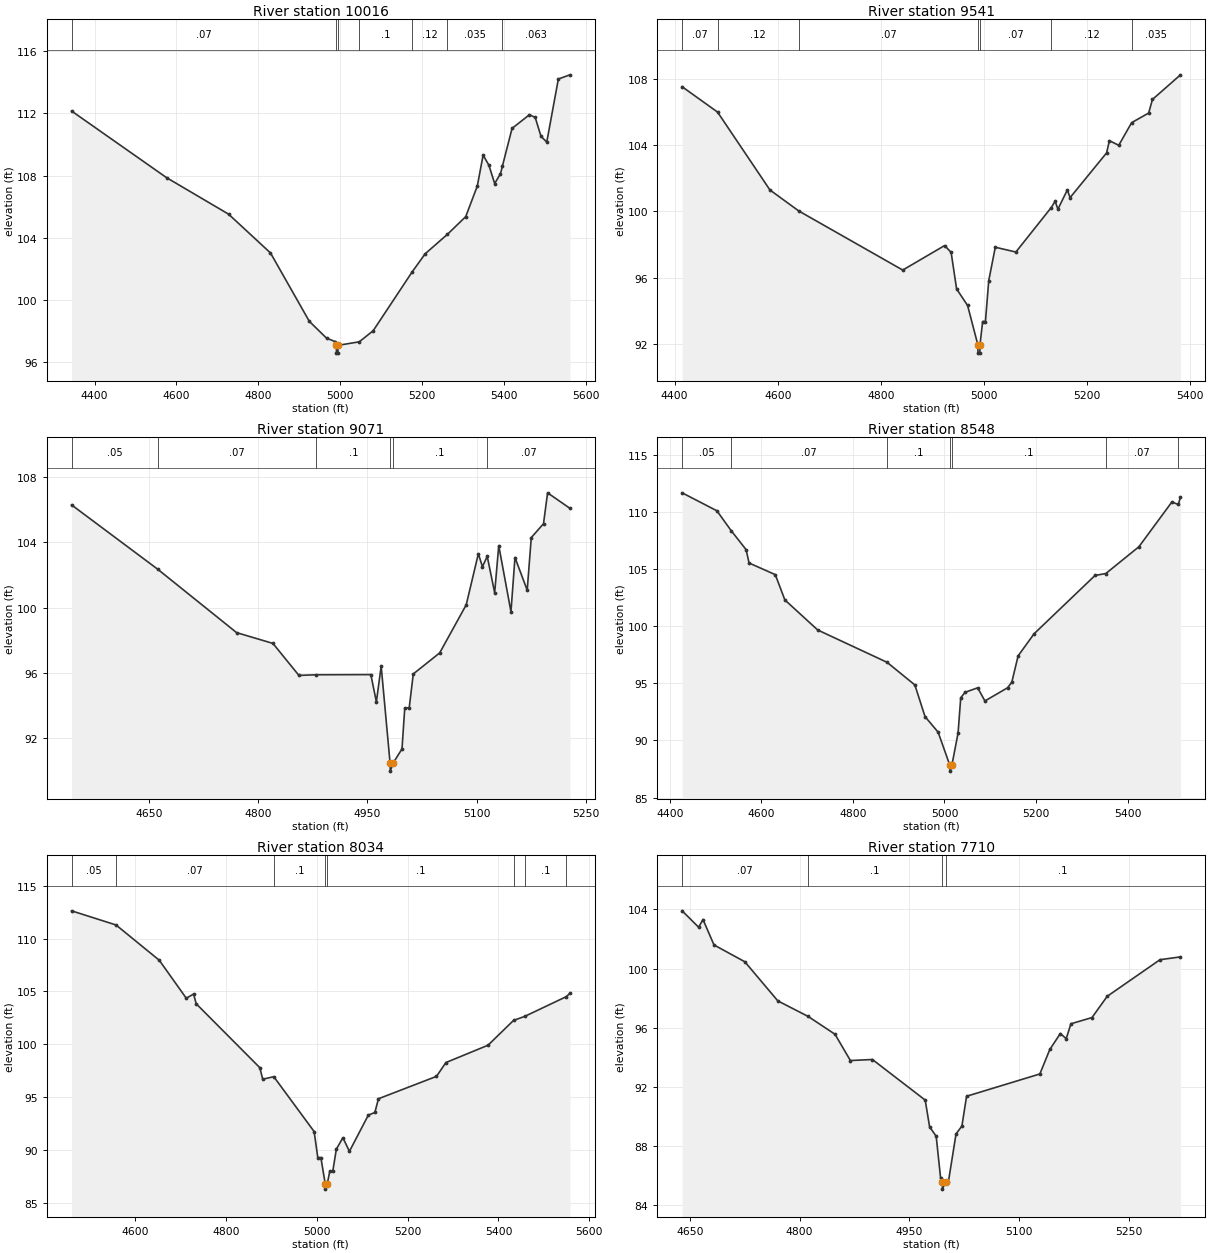
Type RM Length L Ch R = 1 ,10016   ,475,475,475
BEGIN DESCRIPTION:
TRIB 4A TO COLETO CREEK 22.0
END DESCRIPTION:
XS GIS Cut Line= 3
      2554375.01     13447824.99        2554925.       13447475.
      2555325.01     13447074.99
#Sta/Elev= 30
  4343.7  112.16  4575.7  107.87  4727.2  105.52  4829.7  103.02  4924.5   98.62
  4966.8   97.53    4988   97.31  4990.6   97.07  4990.9   96.57  4994.4   96.57
  4994.6   97.07  5046.7    97.3  5080.5   98.01  5175.8   101.8  5207.7  102.97
    5262  104.22  5306.7  105.36    5335  107.33  5349.2  109.32  5363.3  108.67
  5377.4  107.49  5391.6  108.12  5396.1  108.59  5419.9  111.04  5462.3  111.92
  5476.4  111.75  5490.6  110.53  5504.7  110.16    5533  114.22  5561.3  114.49
#Mann= 7 ,-1 , 0
  4343.7     .07       0  4990.6     .05       0  4994.6     .07       0
  5046.7      .1       0  5175.8     .12       0    5262    .035       0
  5396.1    .063       0
Bank Sta=4990.6,4994.6
XS Rating Curve= 0 ,0
Exp/Cntr=0.3,0.1

Type RM Length L Ch R = 1 ,9541    ,470,470,470
BEGIN DESCRIPTION:
TRIB 4A TO COLETO CREEK 21.0
END DESCRIPTION:
XS GIS Cut Line= 3
      2554725.03     13447924.99        2555275.       13447725.
        2555425.     13447374.99
#Sta/Elev= 30
  4414.8  107.53  4483.4     106    4585  101.29    4641  100.02  4842.4   96.45
  4923.5   97.93  4936.2   97.52  4946.8   95.31  4968.1   94.31    4988   91.93
  4988.2   91.43  4991.8   91.43  4992.1   91.93  4997.3   93.34  5002.7   93.34
  5009.1   95.81  5021.8   97.83  5061.7   97.54  5130.3  100.23  5137.8  100.61
  5143.2  100.13  5161.4  101.29  5166.8  100.83  5237.5  103.53    5243  104.27
  5261.1  103.99  5286.1  105.36  5319.1  105.94  5326.4  106.76  5380.8  108.25
#Mann= 7 ,-1 , 0
  4414.8     .07       0  4483.4     .12       0    4641     .07       0
    4988     .05       0  4992.1     .07       0  5130.3     .12       0
  5286.1    .035       0
Bank Sta=4988,4992.1
XS Rating Curve= 0 ,0
Exp/Cntr=0.3,0.1

Type RM Length L Ch R = 1 ,9071    ,523,523,523
BEGIN DESCRIPTION:
TRIB 4A TO COLETO CREEK 20.0
END DESCRIPTION:
XS GIS Cut Line= 3
      2555224.98     13448375.02        2555575.       13448075.
      2555774.99       13447975.
#Sta/Elev= 30
  4543.6   106.3  4661.7  102.37  4770.3   98.48  4820.2   97.82  4855.9   95.86
    4880    95.9  4954.7   95.91  4962.3   94.24  4968.9   96.43  4981.1    90.5
  4981.4      90  4985.4    90.5  4997.5   91.36  5001.3   93.87  5007.4   93.87
    5013   95.95  5049.3   97.24  5085.7  100.18  5102.4  103.31    5108  102.52
  5114.6  103.15  5124.8  100.92  5130.4  103.81  5147.2   99.76  5152.7  103.08
  5169.5  101.08  5175.1   104.3  5191.9  105.15  5197.5  107.04  5228.2  106.09
#Mann= 6 ,-1 , 0
  4543.6     .05       0  4661.7     .07       0    4880      .1       0
  4981.1     .05       0  4985.4      .1       0  5114.6     .07       0
Bank Sta=4981.1,4985.4
XS Rating Curve= 0 ,0
Exp/Cntr=0.3,0.1

Type RM Length L Ch R = 1 ,8548    ,514,514,514
BEGIN DESCRIPTION:
Mapping XS a251fdab
END DESCRIPTION:
XS GIS Cut Line= 3
      2555373.57     13448880.02      2555811.11     13448518.88
      2556074.24     13448068.78
#Sta/Elev= 30
    4427  111.67  4502.9   110.1  4533.9  108.37  4566.7   106.7  4573.2  105.53
  4630.5  104.51  4651.4   102.3  4723.1   99.67  4874.7   96.84  4935.4   94.86
  4957.6   92.09  4986.2   90.73  5011.9   87.82  5012.2   87.32  5016.2   87.82
  5029.8   90.66  5035.6   93.74  5045.2   94.22  5072.7   94.61  5088.4   93.46
  5137.8   94.61  5147.1   95.09    5161   97.41  5195.9   99.34    5329  104.44
  5352.6  104.61  5424.8  106.95  5496.9  110.87  5510.8  110.65  5515.7  111.29
#Mann= 7 ,-1 , 0
    4427     .05       0  4533.9     .07       0  4874.7      .1       0
  5011.9     .05       0  5016.2      .1       0  5352.6     .07       0
  5510.8    .035       0
Bank Sta=5011.9,5016.2
XS Rating Curve= 0 ,0
Exp/Cntr=0.3,0.1

Type RM Length L Ch R = 1 ,8034    ,324,324,324
BEGIN DESCRIPTION:
Mapping XS 2a77724c
END DESCRIPTION:
XS GIS Cut Line= 3
      2555637.48     13449171.67      2556113.19     13448907.77
      2556462.74     13448478.62
#Sta/Elev= 30
  4459.9  112.64  4557.8   111.3    4653  107.96  4712.5  104.36  4728.6  104.76
  4734.3  103.84  4874.5   97.78  4880.8   96.69  4905.2   96.93  4994.1   91.73
  5002.1   89.27  5008.9   89.27  5018.5   86.78  5018.8   86.28    5023   86.78
  5028.7   88.01  5035.1   87.97    5043   90.07  5057.4   91.15  5071.8   89.86
  5113.4   93.29  5127.8   93.54  5135.7   94.84  5263.5   96.96  5284.3   98.27
    5377   99.91  5433.2  102.26  5458.3  102.65  5549.8  104.52  5557.4  104.84
#Mann= 8 ,-1 , 0
  4459.9     .05       0  4557.8     .07       0  4905.2      .1       0
  5018.5     .05       0    5023      .1       0  5433.2     .07       0
  5458.3      .1       0  5549.8     .07       0
Bank Sta=5018.5,5023
XS Rating Curve= 0 ,0
Exp/Cntr=0.3,0.1

Type RM Length L Ch R = 1 ,7710    ,442,442,442
BEGIN DESCRIPTION:
TRIB 4A TO COLETO CREEK 17.0
END DESCRIPTION:
XS GIS Cut Line= 3
      2556075.02     13449274.98        2556375.       13449075.
      2556625.01     13448874.99
#Sta/Elev= 30
  4639.7  103.91  4662.2   102.8  4668.2  103.32  4683.2   101.6  4725.3  100.46
  4770.4   97.81  4811.7   96.76  4848.5   95.55  4869.5   93.77  4899.6   93.84
  4971.7   91.09  4977.7   89.28  4986.7   88.64  4992.7   85.82    4995   85.56
  4995.3   85.06  4999.5   85.56  5003.4   85.56  5013.8    88.8  5021.8   89.33
  5028.2   91.35  5128.3   92.86  5141.9   94.52  5156.3    95.6  5164.3   95.25
  5170.7   96.26  5199.5   96.68  5220.3   98.12  5292.4   100.6  5320.4  100.79
#Mann= 4 ,-1 , 0
  4639.7     .07       0  4811.7      .1       0    4995     .05       0
  4999.5      .1       0
Bank Sta=4995,4999.5
XS Rating Curve= 0 ,0
Exp/Cntr=0.3,0.1

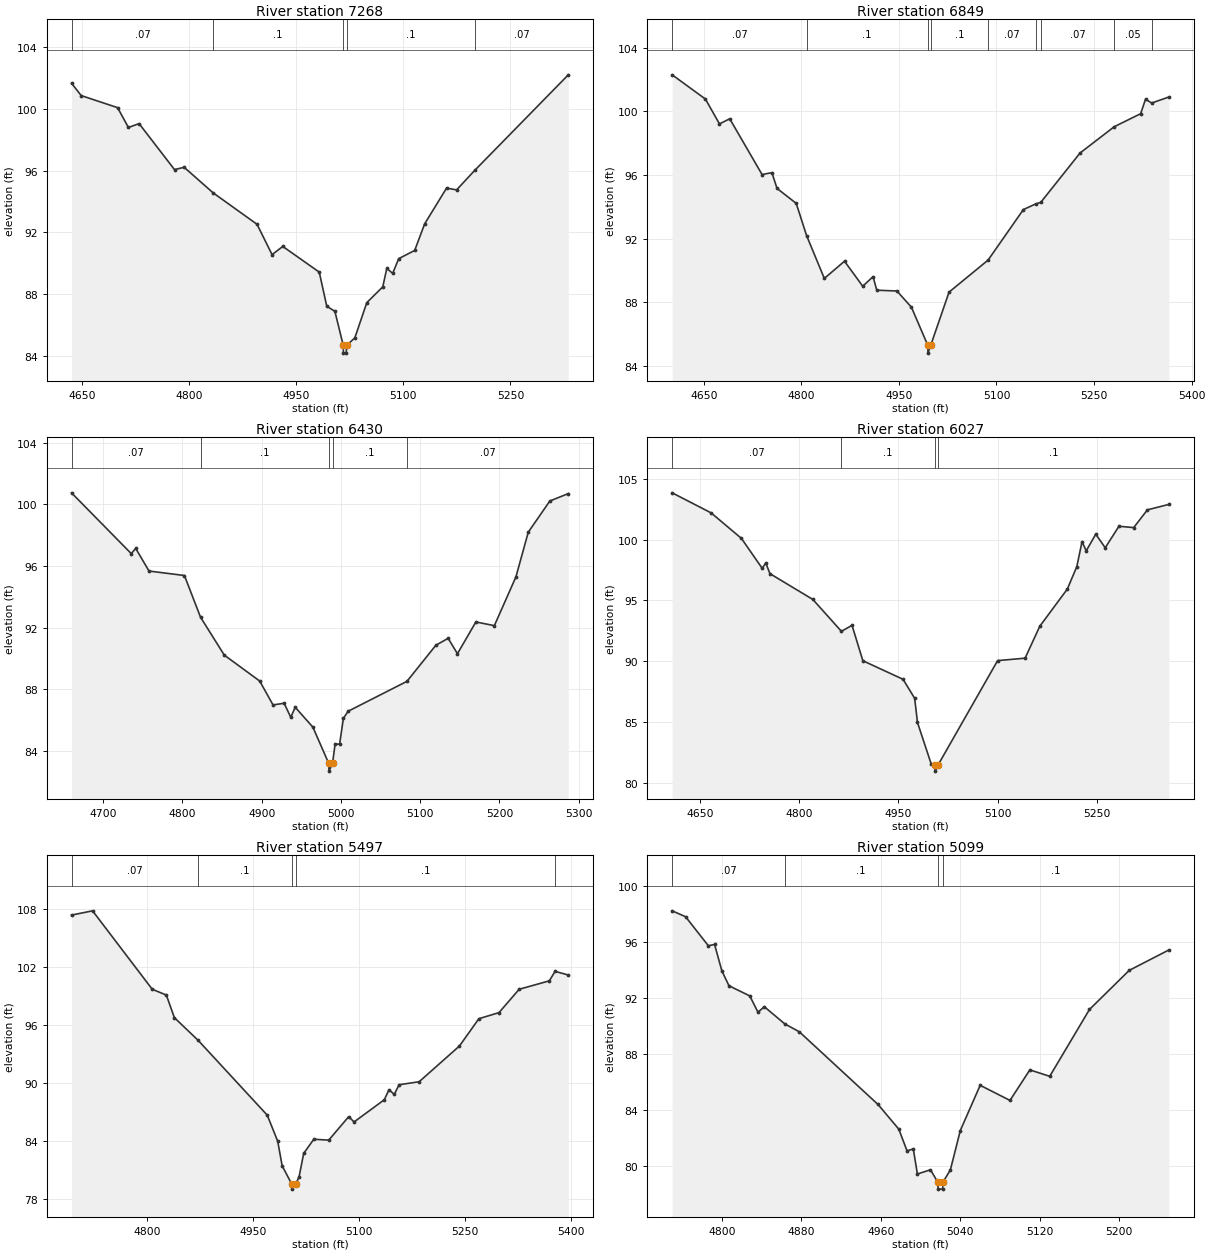
Type RM Length L Ch R = 1 ,7268    ,419,419,419
BEGIN DESCRIPTION:
TRIB 4A TO COLETO CREEK 16.0
END DESCRIPTION:
XS GIS Cut Line= 3
      2556524.98     13449625.03        2556725.       13449325.
        2556875.       13449025.
#Sta/Elev= 30
  4635.1  101.64  4648.7  100.84  4699.7  100.06  4714.8   98.78  4729.8   99.03
  4779.4   96.06  4792.9   96.21  4833.5   94.56    4895   92.53  4916.1   90.57
  4931.1    91.1  4982.2   89.44  4992.7   87.24  5004.1   86.91  5015.8   84.71
  5016.1   84.21    5020   84.21  5020.4   84.71    5032   85.19  5048.8   87.47
  5071.2   88.49  5076.8   89.68  5085.1   89.36  5093.5   90.31  5115.9   90.84
  5129.9   92.56  5160.6   94.87  5174.6   94.75    5200   96.01  5331.1  102.18
#Mann= 5 ,-1 , 0
  4635.1     .07       0  4833.5      .1       0  5015.8     .05       0
  5020.4      .1       0    5200     .07       0
Bank Sta=5015.8,5020.4
XS Rating Curve= 0 ,0
Exp/Cntr=0.3,0.1

Type RM Length L Ch R = 1 ,6849    ,419,419,419
BEGIN DESCRIPTION:
TRIB 4A TO COLETO CREEK 15.0
END DESCRIPTION:
XS GIS Cut Line= 3
      2556675.03     13449774.98        2557025.       13449575.
      2557324.97     13449375.02
#Sta/Elev= 30
  4601.5  102.29  4652.6  100.77  4674.2   99.21    4690   99.53  4739.7   96.03
  4754.8   96.15  4762.7   95.16  4792.2   94.22  4808.1    92.2  4835.4   89.51
  4866.4   90.59  4894.4   89.02  4910.3   89.62    4916   88.77    4947   88.72
  4969.3    87.7  4994.3   85.32  4994.7   84.82    4999   85.32  5027.1   88.65
  5087.1   90.66  5141.3   93.83  5160.5   94.19    5168   94.28  5228.4   97.38
  5280.9   99.03  5321.6   99.85  5329.1  100.76  5338.6  100.52  5365.1   100.9
#Mann= 9 ,-1 , 0
  4601.5     .07       0  4808.1      .1       0  4994.3     .05       0
    4999      .1       0  5087.1     .07       0  5160.5     .05       0
    5168     .07       0  5280.9     .05       0  5338.6     .07       0
Bank Sta=4994.3,4999
XS Rating Curve= 0 ,0
Exp/Cntr=0.3,0.1

Type RM Length L Ch R = 1 ,6430    ,403,403,403
BEGIN DESCRIPTION:
TRIB 4A TO COLETO CREEK 14.0
END DESCRIPTION:
XS GIS Cut Line= 3
      2556925.04     13450074.98        2557225.       13449925.
      2557474.99     13449775.01
#Sta/Elev= 30
    4660  100.74  4735.4    96.8    4741   97.14  4757.8   95.67  4802.5   95.38
  4822.8   92.68  4852.8   90.22  4897.5   88.54  4914.3   86.99  4928.3    87.1
  4936.7   86.19  4942.3   86.84  4964.6   85.55  4984.6    83.2  4984.9    82.7
  4989.4    83.2  4992.6   84.45  4998.3   84.45  5003.1   86.12    5009   86.58
  5083.3   88.52  5119.8   90.86  5135.3   91.31    5147   90.31  5170.3   92.37
  5193.6   92.13  5220.8   95.29  5236.4   98.19  5263.6  100.21  5286.9  100.69
#Mann= 5 ,-1 , 0
    4660     .07       0  4822.8      .1       0  4984.6     .05       0
  4989.4      .1       0  5083.3     .07       0
Bank Sta=4984.6,4989.4
XS Rating Curve= 0 ,0
Exp/Cntr=0.3,0.1

Type RM Length L Ch R = 1 ,6027    ,530,530,530
BEGIN DESCRIPTION:
Mapping XS 436c8b43
END DESCRIPTION:
XS GIS Cut Line= 3
      2557087.98     13450403.44      2557423.96     13450265.41
      2557724.81     13450019.02
#Sta/Elev= 30
  4607.4  103.85  4666.4   102.2  4712.3   100.1  4743.7   97.64  4749.1   98.08
  4755.5    97.2  4820.4   95.08  4863.6   92.46  4879.7   92.95  4896.1   90.04
    4957   88.51  4974.5   86.95  4978.8   84.96  4999.6   81.54  5005.1   81.46
  5005.5   80.96  5009.9   81.46  5100.1   90.05  5141.7   90.25    5164   92.88
  5205.6   95.93    5220   97.78  5227.9   99.83  5234.3   99.08  5248.7  100.45
    5263   99.33  5283.8   101.1  5306.1  100.99  5326.9  102.45  5359.5   102.9
#Mann= 4 ,-1 , 0
  4607.4     .07       0  4863.6      .1       0  5005.1     .05       0
  5009.9      .1       0
Bank Sta=5005.1,5009.9
XS Rating Curve= 0 ,0
Exp/Cntr=0.3,0.1

Type RM Length L Ch R = 1 ,5497    ,398,398,398
BEGIN DESCRIPTION:
Mapping XS 433f5414
END DESCRIPTION:
XS GIS Cut Line= 3
       2557465.6     13450749.79      2557752.08     13450663.84
      2558017.37     13450359.54
#Sta/Elev= 30
    4693  107.33  4722.8  107.77  4807.2   99.67  4827.2   99.07  4838.5   96.74
  4872.1    94.4  4969.9   86.67  4984.7   83.98    4991   81.44  5004.7   79.53
  5005.1   79.03    5010   79.53  5014.9   80.29  5021.5   82.73  5035.8   84.18
  5056.9   84.09  5085.1   86.51  5092.8   85.97  5135.5   88.26  5142.1   89.29
  5149.7   88.82  5156.4   89.81  5184.8   90.12  5241.8   93.81  5269.3   96.63
  5297.8   97.26  5326.3   99.67    5369  100.54  5377.1  101.52  5395.8  101.14
#Mann= 5 ,-1 , 0
    4693     .07       0  4872.1      .1       0  5004.7     .05       0
    5010      .1       0  5377.1     .07       0
Bank Sta=5004.7,5010
XS Rating Curve= 0 ,0
Exp/Cntr=0.3,0.1

Type RM Length L Ch R = 1 ,5099    ,209,209,209
BEGIN DESCRIPTION:
TRIB 4A TO COLETO CREEK 11.0
END DESCRIPTION:
XS GIS Cut Line= 3
      2557875.04     13451024.97        2558075.       13450875.
        2558075.     13450624.95
#Sta/Elev= 30
    4750   98.21  4763.5   97.79  4786.4   95.72  4792.7   95.81    4800   93.93
  4807.2   92.86  4828.1   92.14  4836.4   90.97  4842.7   91.37  4863.2   90.15
  4878.1   89.57  4957.2   84.39  4978.1   82.63  4986.4   81.08  4992.7   81.22
  4996.8   79.43    5010   79.73  5017.3   78.85  5017.7   78.35  5022.2   78.35
  5022.6   78.85    5030   79.72    5040   82.53    5060   85.76    5090   84.68
    5110   86.86    5130    86.4    5170   91.17    5210   93.96    5250   95.42
#Mann= 4 ,-1 , 0
    4750     .07       0  4863.2      .1       0  5017.3     .05       0
  5022.6      .1       0
Bank Sta=5017.3,5022.6
XS Rating Curve= 0 ,0
Exp/Cntr=0.3,0.1

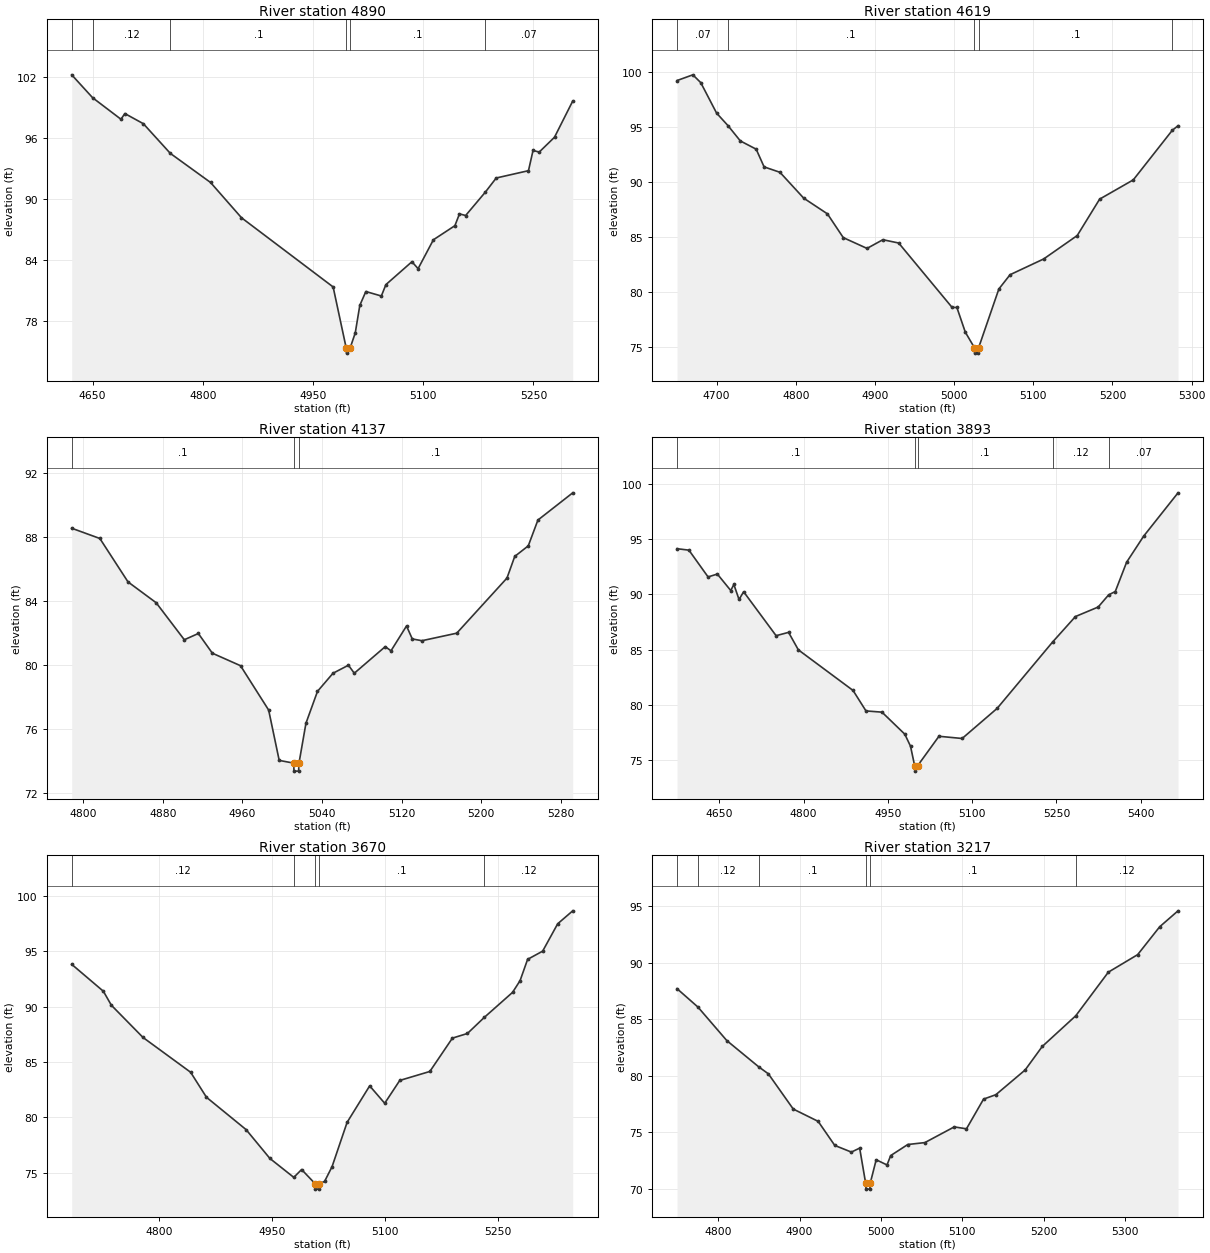
Type RM Length L Ch R = 1 ,4890    ,271,271,271
BEGIN DESCRIPTION:
Mapping XS fa23795f
END DESCRIPTION:
XS GIS Cut Line= 3
      2557868.18     13451153.52      2558222.37      13451023.3
      2558404.14     13450779.22
#Sta/Elev= 30
  4621.7  102.21  4650.1   99.96  4688.7   97.84    4694    98.4  4719.2    97.4
  4755.9   94.48  4810.6   91.62  4852.7   88.15  4977.4   81.34  4995.2   75.33
  4995.6   74.83  5000.5   75.33  5007.5   76.82  5013.7   79.53  5021.9   80.89
    5043   80.45  5049.2   81.57  5084.6   83.82    5093   83.14  5113.8   85.98
  5143.1   87.37  5149.3   88.53  5157.7   88.37  5184.4   90.66  5199.3   92.06
  5243.2   92.78  5249.4   94.77  5257.8   94.61  5278.6   96.07  5303.4   99.63
#Mann= 6 ,-1 , 0
  4621.7     .07       0  4650.1     .12       0  4755.9      .1       0
  4995.2     .05       0  5000.5      .1       0  5184.4     .07       0
Bank Sta=4995.2,5000.5
XS Rating Curve= 0 ,0
Exp/Cntr=0.3,0.1

Type RM Length L Ch R = 1 ,4619    ,482,482,482
BEGIN DESCRIPTION:
TRIB 4A TO COLETO CREEK 10.0
END DESCRIPTION:
XS GIS Cut Line= 3
      2557925.02       13451275.        2558275.       13451275.
      2558474.99     13451075.01
#Sta/Elev= 30
    4650   99.21    4670   99.73    4680   99.02    4700   96.25  4714.4   95.11
    4730   93.72    4750   92.97    4760   91.36    4780   90.87    4810   88.52
    4840   87.09    4860   84.93    4890   83.95    4910   84.74    4930   84.44
  4997.5   78.58  5003.5   78.58  5014.1   76.34  5025.6   74.93    5026   74.43
  5030.5   74.43    5031   74.93  5056.5   80.26  5070.7   81.56  5113.1   82.99
  5155.5   85.12  5183.8   88.43  5226.3   90.18  5275.6   94.69  5282.8    95.1
#Mann= 5 ,-1 , 0
    4650     .07       0  4714.4      .1       0  5025.6     .05       0
    5031      .1       0  5275.6     .07       0
Bank Sta=5025.6,5031
XS Rating Curve= 0 ,0
Exp/Cntr=0.3,0.1

Type RM Length L Ch R = 1 ,4137    ,244,244,244
BEGIN DESCRIPTION:
TRIB 4A TO COLETO CREEK 9.0
END DESCRIPTION:
XS GIS Cut Line= 3
      2558024.98     13451574.98        2558175.       13451725.
      2558424.99       13451575.
#Sta/Elev= 30
  4788.4   88.53  4816.7   87.89    4845   85.18  4873.3   83.88  4901.6   81.57
  4915.7   81.96  4929.8   80.73  4958.1   79.95  4986.4   77.18    4997   74.04
  5011.5   73.87  5011.9   73.37  5016.5   73.37  5016.9   73.87  5023.9   76.36
  5035.5   78.35  5051.1   79.48  5066.6   79.98  5072.5   79.48  5103.6   81.14
  5109.4   80.88    5125   82.43  5130.8   81.62  5140.5   81.51  5175.5   81.98
    5226   85.42  5233.8   86.77  5247.4   87.43  5257.1   89.04  5292.1   90.74
#Mann= 3 ,-1 , 0
  4788.4      .1       0  5011.5     .05       0  5016.9      .1       0
Bank Sta=5011.5,5016.9
XS Rating Curve= 0 ,0
Exp/Cntr=0.3,0.1

Type RM Length L Ch R = 1 ,3893    ,223,223,223
BEGIN DESCRIPTION:
Mapping XS 9577cdcd
END DESCRIPTION:
XS GIS Cut Line= 3
      2557734.74     13451799.27      2558081.94     13451958.98
      2558585.37     13451879.13
#Sta/Elev= 30
  4574.5   94.13  4595.7      94  4629.8   91.58  4646.3   91.84  4670.2   90.35
  4675.7    90.9  4684.9   89.54  4693.1   90.24  4750.9   86.27  4773.1   86.57
  4790.5   84.99  4887.9   81.32  4910.9   79.47  4939.4   79.36    4980   77.37
  4990.2   76.28  4997.5   74.53    4998   74.03    5003   74.53  5040.8   77.18
  5082.1   76.98  5144.4    79.7    5243   85.69  5283.8      88  5324.3   88.86
  5342.9   89.96  5354.7   90.26  5374.9   92.91  5405.3   95.27  5466.4   99.18
#Mann= 5 ,-1 , 0
  4574.5      .1       0  4997.5     .05       0    5003      .1       0
    5243     .12       0  5342.9     .07       0
Bank Sta=4997.5,5003
XS Rating Curve= 0 ,0
Exp/Cntr=0.3,0.1

Type RM Length L Ch R = 1 ,3670    ,453,453,453
BEGIN DESCRIPTION:
TRIB 4A TO COLETO CREEK 8.0
END DESCRIPTION:
XS GIS Cut Line= 3
      2557825.02     13452274.99        2558125.       13452175.
      2558474.99       13452175.
#Sta/Elev= 30
  4683.8   93.81  4725.9   91.38  4736.5   90.12  4778.6   87.21  4841.9   84.07
    4863   81.81  4915.7   78.89  4947.3   76.29  4979.1   74.58  4989.5   75.29
  5007.3   74.02  5007.7   73.52  5012.3   73.52  5012.8   74.02    5020   74.21
    5030   75.55    5050   79.55    5080   82.84    5100   81.27    5120   83.33
    5160   84.14    5190   87.15    5210   87.57  5232.4   89.02    5270   91.28
    5280   92.34    5290   94.26    5310      95    5330   97.47    5350   98.64
#Mann= 5 ,-1 , 0
  4683.8     .12       0  4979.1      .1       0  5007.3     .05       0
  5012.8      .1       0  5232.4     .12       0
Bank Sta=5007.3,5012.8
XS Rating Curve= 0 ,0
Exp/Cntr=0.3,0.1

Type RM Length L Ch R = 1 ,3217    ,445,445,445
BEGIN DESCRIPTION:
TRIB 4A TO COLETO CREEK 7.0
END DESCRIPTION:
XS GIS Cut Line= 3
        2558025.       13452625.        2558275.       13452575.
        2558475.       13452275.
#Sta/Elev= 30
  4749.5   87.72  4775.2   86.09  4810.7   83.12    4850   80.79  4861.7   80.18
  4892.3   77.06  4922.9   75.97  4943.3   73.84  4963.7   73.25  4973.9    73.6
  4981.3   70.47  4981.8   69.97  4986.4   69.97  4986.8   70.47  4994.2   72.57
  5007.5   72.11    5012   72.94    5033   73.92    5054   74.09  5090.1   75.48
  5105.1   75.31  5126.1   77.94  5141.2   78.33  5177.2   80.52  5198.2    82.6
  5239.4   85.32  5279.4   89.18  5315.4   90.73  5342.5    93.2    5365   94.61
#Mann= 6 ,-1 , 0
  4749.5     .07       0  4775.2     .12       0    4850      .1       0
  4981.3     .05       0  4986.8      .1       0  5239.4     .12       0
Bank Sta=4981.3,4986.8
XS Rating Curve= 0 ,0
Exp/Cntr=0.3,0.1

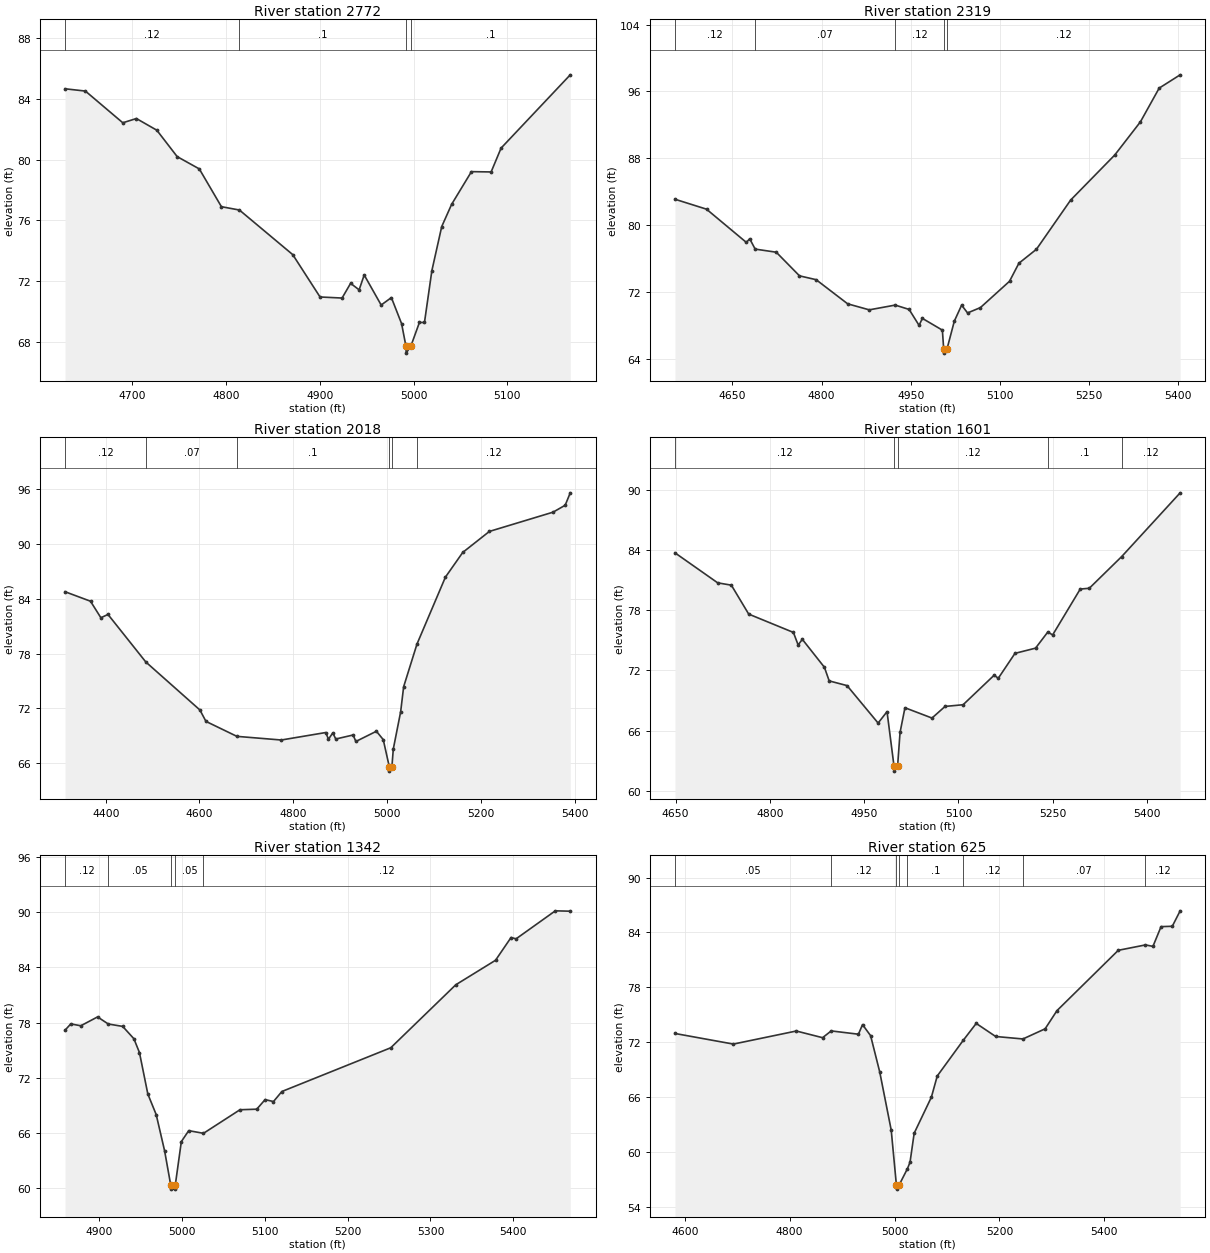
Type RM Length L Ch R = 1 ,2772    ,453,453,453
BEGIN DESCRIPTION:
TRIB 4A TO COLETO CREEK 6.0
END DESCRIPTION:
XS GIS Cut Line= 3
      2558225.03     13453024.99        2558575.       13452875.
      2558725.03     13452824.99
#Sta/Elev= 30
  4628.2   84.67  4649.9   84.52  4689.8   82.43  4704.3   82.71  4726.1   81.94
  4747.8    80.2  4771.4   79.39    4795    76.9  4814.2   76.68  4871.1   73.74
  4900.2   70.95  4923.7   70.88  4932.8   71.85  4941.9   71.42  4947.3    72.4
  4965.4   70.42  4976.3   70.91  4987.2   69.19  4991.7   67.75  4992.1   67.25
  4997.3   67.75  5006.2   69.27  5011.6   69.27  5019.5   72.69    5030   75.59
  5040.6   77.06  5061.7   79.21  5082.7   79.19  5093.3   80.76  5167.1   85.59
#Mann= 4 ,-1 , 0
  4628.2     .12       0  4814.2      .1       0  4991.7     .05       0
  4997.3      .1       0
Bank Sta=4991.7,4997.3
XS Rating Curve= 0 ,0
Exp/Cntr=0.3,0.1

Type RM Length L Ch R = 1 ,2319    ,301,301,301
BEGIN DESCRIPTION:
TRIB 4A TO COLETO CREEK 5.0
END DESCRIPTION:
XS GIS Cut Line= 3
      2558275.02     13453075.01        2558675.       13453275.
        2559025.       13453075.
#Sta/Elev= 30
  4553.2    83.1  4606.3   81.91  4673.4   77.93    4679   78.37  4688.2   77.13
  4723.7   76.76  4762.8   73.93  4790.8   73.47  4843.9   70.58  4880.2   69.86
  4923.9   70.43  4947.3   69.91  4964.1      68  4969.6   68.84  5003.3   67.43
  5005.5   65.18    5006   64.68  5011.1   65.18  5023.4   68.51  5035.7   70.42
  5045.7   69.49  5067.3   70.13  5116.3   73.28  5132.1   75.44  5161.6   77.11
  5219.2      83  5293.4   88.39  5336.6   92.36  5368.2    96.4  5403.5   97.99
#Mann= 5 ,-1 , 0
  4553.2     .12       0  4688.2     .07       0  4923.9     .12       0
  5005.5     .05       0  5011.1     .12       0
Bank Sta=5005.5,5011.1
XS Rating Curve= 0 ,0
Exp/Cntr=0.3,0.1

Type RM Length L Ch R = 1 ,2018    ,417,417,417
BEGIN DESCRIPTION:
Mapping XS 6b003b75
END DESCRIPTION:
XS GIS Cut Line= 4
       2558182.6     13453170.76      2558606.25     13453441.62
      2558922.22     13453629.12      2559120.04     13453566.65
#Sta/Elev= 30
  4313.2   84.78  4367.5   83.74  4389.6   81.93  4404.8   82.29  4485.5   77.08
  4600.9   71.82  4613.8   70.57  4679.8   68.93  4774.5   68.53  4869.3   69.35
  4875.1   68.62  4884.4   69.31  4890.7   68.64  4927.7   69.08  4933.6   68.37
  4977.4   69.49    4992   68.57  5004.8   65.62  5005.3   65.12  5010.5   65.62
  5013.4   67.54  5029.1   71.62  5035.5   74.37  5063.9   79.04  5124.6   86.38
  5161.6   89.09  5218.4   91.39  5354.2    93.5  5380.1   94.26  5390.9   95.62
#Mann= 6 ,-1 , 0
  4313.2     .12       0  4485.5     .07       0  4679.8      .1       0
  5004.8     .05       0  5010.5      .1       0  5063.9     .12       0
Bank Sta=5004.8,5010.5
XS Rating Curve= 0 ,0
Exp/Cntr=0.3,0.1

Type RM Length L Ch R = 1 ,1601    ,259,259,259
BEGIN DESCRIPTION:
Mapping XS 279ec318
END DESCRIPTION:
XS GIS Cut Line= 4
      2558127.61     13453326.27      2558390.97     13453559.68
       2558536.8      13453681.2      2558761.27     13453815.88
#Sta/Elev= 30
  4649.1   83.75  4717.1   80.75  4738.8   80.52  4766.4   77.63  4837.5    75.8
    4845   74.55  4851.7   75.11  4886.8   72.32  4894.4   70.96  4922.8   70.49
  4972.2   66.75  4986.4   67.89  4997.5   62.45    4998   61.95  5003.2   62.45
  5007.1   65.81  5014.9   68.28  5057.9   67.25  5078.7   68.41  5107.4   68.58
  5156.8   71.53  5163.3   71.22  5189.9   73.71  5222.6   74.23  5242.1   75.84
  5249.8   75.55  5293.7   80.13  5308.1   80.21  5359.7   83.38  5452.6   89.74
#Mann= 5 ,-1 , 0
  4649.1     .12       0  4997.5     .05       0  5003.2     .12       0
  5242.1      .1       0  5359.7     .12       0
Bank Sta=4997.5,5003.2
XS Rating Curve= 0 ,0
Exp/Cntr=0.3,0.1

Type RM Length L Ch R = 1 ,1342    ,717,717,717
BEGIN DESCRIPTION:
Mapping XS adb840b3
END DESCRIPTION:
XS GIS Cut Line= 3
      2558176.14     13453748.62      2558645.17     13453814.88
      2558771.82     13453862.81
#Sta/Elev= 30
  4859.4   77.18  4866.3   77.86  4878.4   77.66  4898.6   78.62  4911.5   77.85
  4928.9   77.59  4942.4   76.25  4949.1   74.75  4959.2   70.25  4969.3   68.01
  4979.4   64.09  4986.7   60.42  4987.1   59.92  4991.9   59.92  4992.4   60.42
  4999.6   65.08  5008.5   66.27  5026.3   65.98  5070.3   68.54  5090.5    68.6
  5100.6   69.64  5110.7   69.43  5120.8   70.52  5252.1   75.27  5330.5   82.11
  5378.4   84.77  5397.1   87.24  5403.2    87.1  5450.5   90.14  5468.5    90.1
#Mann= 5 ,-1 , 0
  4859.4     .12       0  4911.5     .05       0  4986.7     .05       0
  4992.4     .05       0  5026.3     .12       0
Bank Sta=4986.7,4992.4
XS Rating Curve= 0 ,0
Exp/Cntr=0.3,0.1

Type RM Length L Ch R = 1 ,625     ,326,326,326
BEGIN DESCRIPTION:
Mapping XS b07c3ba8
END DESCRIPTION:
XS GIS Cut Line= 4
      2558074.42     13453823.61      2558067.91      13454118.7
      2558326.16     13454233.72      2558655.98     13454034.09
#Sta/Elev= 30
  4581.3   72.95  4692.7   71.79  4812.7   73.22  4862.8   72.49  4879.3   73.23
  4931.2   72.87    4939   73.92  4954.4   72.71  4971.8   68.74  4993.7   62.38
  5003.5   56.42  5003.9   55.92  5009.2   56.42  5024.6   58.15  5029.6   58.87
  5037.5   62.04  5070.3   65.98  5081.5    68.3  5130.9   72.19  5155.8   74.05
  5192.9   72.62  5244.9   72.35  5287.2   73.46  5309.8   75.45  5426.7   82.05
  5478.6   82.64  5492.8   82.48  5508.3   84.64  5529.7   84.68  5544.7   86.37
#Mann= 8 ,-1 , 0
  4581.3     .05       0  4879.3     .12       0  5003.5     .05       0
  5009.2     .12       0  5024.6      .1       0  5130.9     .12       0
  5244.9     .07       0  5478.6     .12       0
Bank Sta=5003.5,5009.2
XS Rating Curve= 0 ,0
Exp/Cntr=0.3,0.1

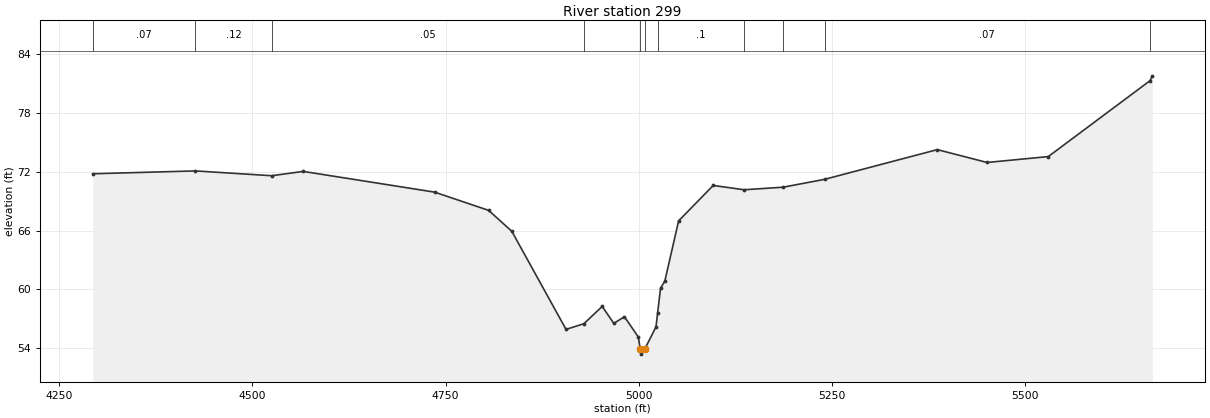
Type RM Length L Ch R = 1 ,299     ,0,0,0
BEGIN DESCRIPTION:
TRIB 4A TO COLETO CREEK 1.0
END DESCRIPTION:
XS GIS Cut Line= 4
      2557976.76      13453812.7      2557981.47     13454417.64
      2558165.57     13454498.48      2558617.61      13454158.9
#Sta/Elev= 30
  4293.5   71.79  4426.4   72.08  4525.1   71.59  4565.8   72.03  4735.8   69.92
  4805.8   68.06  4835.8   65.93    4906   55.93  4929.1   56.51  4952.8   58.27
  4967.8   56.54  4981.6   57.22  4999.5   55.16  5002.1   53.91  5002.5   53.41
  5007.8   53.91  5022.4   56.18  5024.5   57.59  5028.3   60.13  5033.8   60.84
  5051.7   66.99  5096.5    70.6  5136.3   70.16  5186.9   70.42  5240.5   71.22
  5386.5   74.25  5450.9   72.94  5530.1   73.54  5661.9   81.28  5664.9   81.77
#Mann= 11 ,-1 , 0
  4293.5     .07       0  4426.4     .12       0  4525.1     .05       0
  4929.1     .12       0  5002.1     .05       0  5007.8     .12       0
  5024.5      .1       0  5136.3     .07       0  5186.9      .1       0
  5240.5     .07       0  5661.9     .12       0
Bank Sta=5002.1,5007.8
XS Rating Curve= 0 ,0
Exp/Cntr=0.3,0.1

Chan Stop Cuts=-1
Use User Specified Reach Order=0
Composite Channel Slope=5