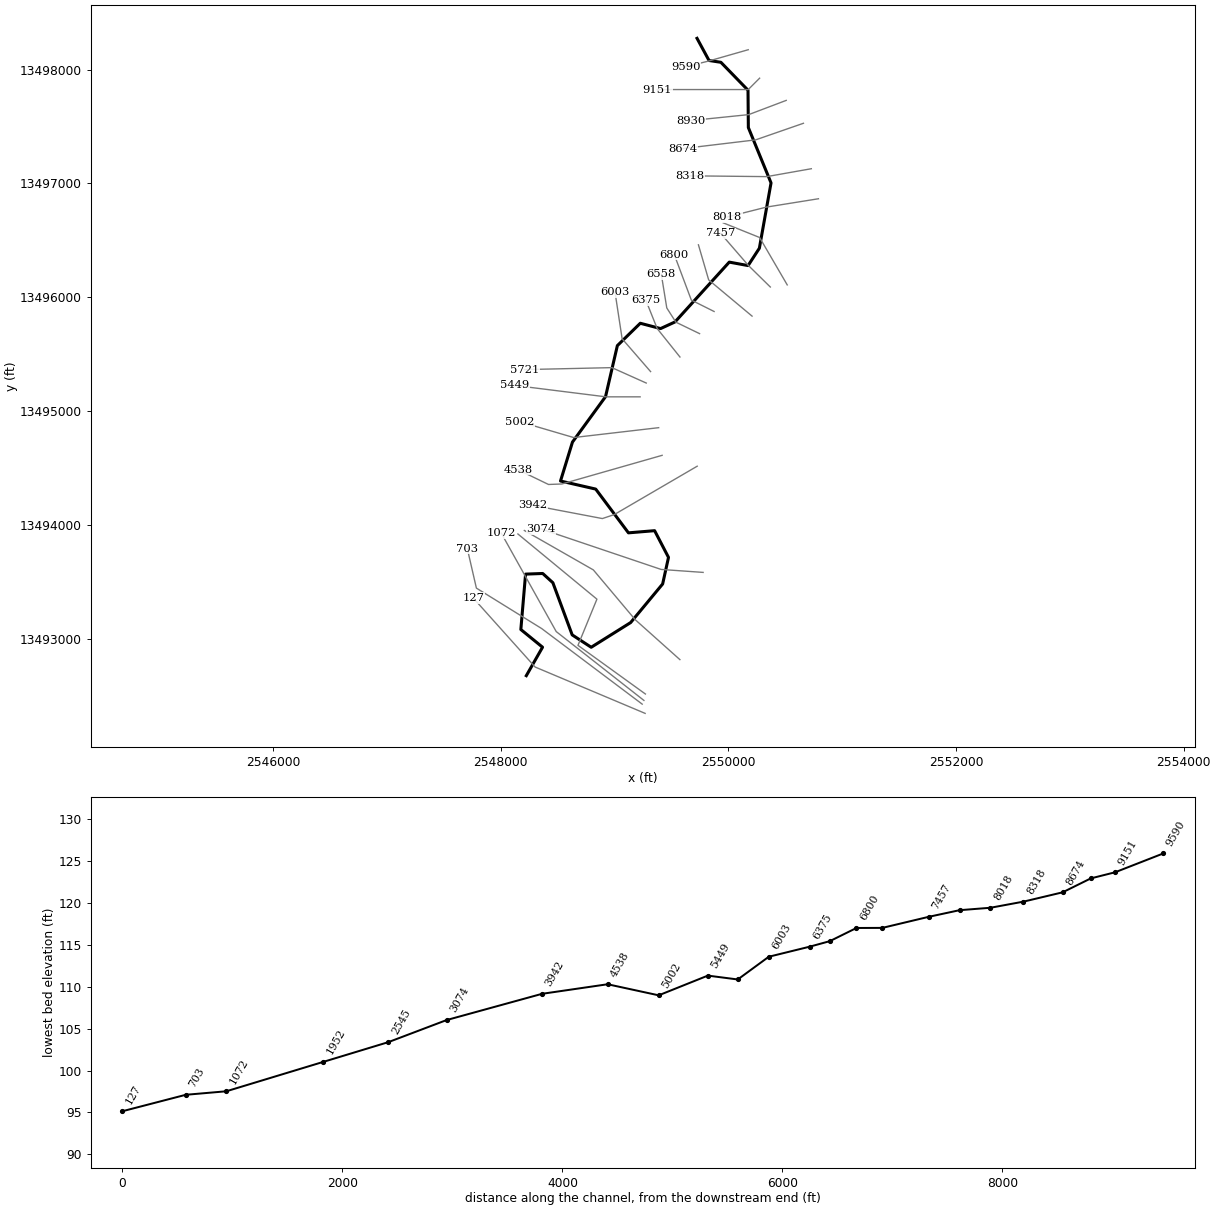
--- TRIB 4B TO COLETO CREEK.prj (project) ---

Proj Title=TRIB 4B TO COLETO CREEK Base Level Engineering
Current Plan=p01
Default Exp/Contr=0.3,0.1
English Units
Geom File=g01
Flow File=f01
Plan File=p01
Y Axis Title=Elevation
X Axis Title(PF)=Main Channel Distance
X Axis Title(XS)=Station
BEGIN DESCRIPTION:
TRIB 4B TO COLETO CREEK
END DESCRIPTION:
DSS Export Rating Curves= 0
DSS Export Rating Curve Sorted= 0
DSS Export Volume Flow Curves= 0
DXF OffsetX= 0
DXF OffsetY= 0
DXF ScaleX= 1
DXF ScaleY= 10

--- TRIB 4B TO COLETO CREEK.p01 (plan) ---

Plan Title=Multiple Run
Program Version=4.10
Short Identifier=Multiple
Geom File=g01
Flow File=f01
Subcritical Flow
K Sum by GR= 0
Std Step Tol= 0.01
Critical Tol= 0.01
Num of Std Step Trials= 20
Max Error Tol= 0.3
Flow Tol Ratio= 0.001
Split Flow NTrial= 30
Split Flow Tol= 0.02
Split Flow Ratio= 0.02
Log Output Level= 0
Friction Slope Method= 1
Unsteady Friction Slope Method= 2
Unsteady Bridges Friction Slope Method= 1
Parabolic Critical Depth
Global Vel Dist= 1 , 1 , 1
Global Log Level= 0
CheckData=True
Encroach Param=-1 ,0,0, 0
BEGIN DESCRIPTION:
Multiple Run
END DESCRIPTION:
Computation Interval=1HOUR
Output Interval=1HOUR
Run HTab= 0
Run UNet= 0
Run PostProcess= 0
Run WQNet= 0
UNET Theta= 1
UNET Theta Warmup= 1
UNET ZTol= 0.02
UNET ZSATol= 0.05
UNET MxIter= 20
UNET MaxInSteps= 0
UNET DtIC= 0
UNET DtMin= 0
UNET MaxCRTS= 20
UNET WFStab= 2
UNET SFStab= 1
UNET WFX= 1
UNET SFX= 1
UNET DSS MLevel= 4
UNET DZMax Abort= 100
UNET Convert EG Bridges= 0
UNET Use Existing IB Tables=-1
UNET Froude Reduction=False
UNET Froude Limit= 1
UNET Froude Power= 10
UNET Time Slicing=0,0, 5
UNET Junction Losses=0
Instantaneous Interval=1HOUR
Write IC File= 0
Write IC File at Sim End=0
Echo Input=False
Echo Parameters=False
Echo Output=False
Write Detailed= 0
WQ AD Non Conservative
WQ ULTIMATE=-1
WQ Max Comp Step=1HOUR
WQ Output Interval=15MIN
WQ Output Selected Increments= 0
WQ Output face flow=0
WQ Output face velocity=0
WQ Output face area=0
WQ Output face dispersion=0
WQ Output cell volume=0
WQ Output cell surface area=0
WQ Output cell continuity=0
WQ Output cumulative cell continuity=0
WQ Output face conc=0
WQ Output face dconc_dx=0
WQ Output face courant=0
WQ Output face peclet=0
WQ Output face adv mass=0
WQ Output face disp mass=0
WQ Output cell mass=0
WQ Output cell source sink temp=0
WQ Output cell source sink nsm=0
WQ Output MaxMinRange=-1
WQ Daily Max Min Mean=-1
WQ Daily Range=0
WQ Daily Time=0
WQ Create Restart=0
WQ Fixed Restart=0
WQ System Summary=0
WQ Use Fixed Temperature=0
Sorting and Armoring Iterations= 10
XS Update Threshold= 0.02
Hydraulics Update Threshold= 0.02
Energy Slope Method= 1
Volume Change Method= 0
XS Weighting Method= 0
Number of US Weighted Cross Sections= 1
Number of DS Weighted Cross Sections= 1
Upstream XS Weight=0.25
Main XS Weight=0.5
Downstream XS Weight=0.25
Number of DS XS's Weighted with US Boundary= 1
Upstream Boundary Weight= 1
Weight of XSs Associated with US Boundary= 0
Number of US XS's Weighted with DS Boundary= 1
Downstream Boundary Weight= 0.5
Weight of XSs Associated with DS Boundary= 0.5
Sediment Output Level= 4
Mass or Volume Output= 0
Output Increment Type= 1
Profile and TS Output Increment= 10
XS Output Flag= 0
XS Output Increment= 10
Disregard all LS=0
Disregard all Conn=0
Disregard all Breaches=0
Disregard all Pumps=0

--- TRIB 4B TO COLETO CREEK.f01 (steady flow) ---

Flow Title=Multiple
Number of Profiles=7
Profile Names=10-year,25-year,50-year,1pct_min,100-year,1pct_plu,500-year
River Rch & RM= TRIB 4B TO COLET,Reach-1,9590
    1060    1733    2349    1538    3069    6124    5183
River Rch & RM= TRIB 4B TO COLET,Reach-1,7737
    1566    2613    3590    2380    4748    9473    8219
River Rch & RM= TRIB 4B TO COLET,Reach-1,5721
    2177    3685    5110    3416    6816   13599   12002
Boundary for River Rch & Prof#=TRIB 4B TO COLET,Reach-1,1
Up Type=0
Dn Type=3
Dn Slope=0.005
Boundary for River Rch & Prof#=TRIB 4B TO COLET,Reach-1,2
Up Type=0
Dn Type=3
Dn Slope=0.005
Boundary for River Rch & Prof#=TRIB 4B TO COLET,Reach-1,3
Up Type=0
Dn Type=3
Dn Slope=0.005
Boundary for River Rch & Prof#=TRIB 4B TO COLET,Reach-1,4
Up Type=0
Dn Type=3
Dn Slope=0.005
Boundary for River Rch & Prof#=TRIB 4B TO COLET,Reach-1,5
Up Type=0
Dn Type=3
Dn Slope=0.005
Boundary for River Rch & Prof#=TRIB 4B TO COLET,Reach-1,6
Up Type=0
Dn Type=3
Dn Slope=0.005
Boundary for River Rch & Prof#=TRIB 4B TO COLET,Reach-1,7
Up Type=0
Dn Type=3
Dn Slope=0.005

--- TRIB 4B TO COLETO CREEK.g01 (geometry) ---

Geom Title=Existing Conditions
Program Version=4.10

River Reach=TRIB 4B TO COLET,Reach-1
Reach XY= 30
        2549725.       13498275.      2549830.44     13498080.25
      2549934.75     13498064.47      2550172.94     13497819.15
      2550175.95     13497490.96      2550375.28     13497004.82
      2550272.81     13496430.91      2550173.72     13496278.37
      2550008.29     13496308.71      2549531.34     13495783.02
      2549404.83     13495724.71       2549226.5     13495771.54
        2549025.       13495575.      2548921.17     13495126.58
      2548630.52     13494727.43      2548525.53     13494385.45
      2548834.82     13494314.53      2549122.45     13493929.99
      2549352.33     13493949.04       2549474.4     13493714.38
      2549422.93     13493480.86      2549141.67     13493141.65
      2548795.13      13492924.6      2548628.16     13493033.34
      2548458.37     13493491.71      2548369.15     13493572.96
      2548218.48     13493567.33      2548176.98     13493080.67
      2548367.69     13492925.11        2548225.       13492675.

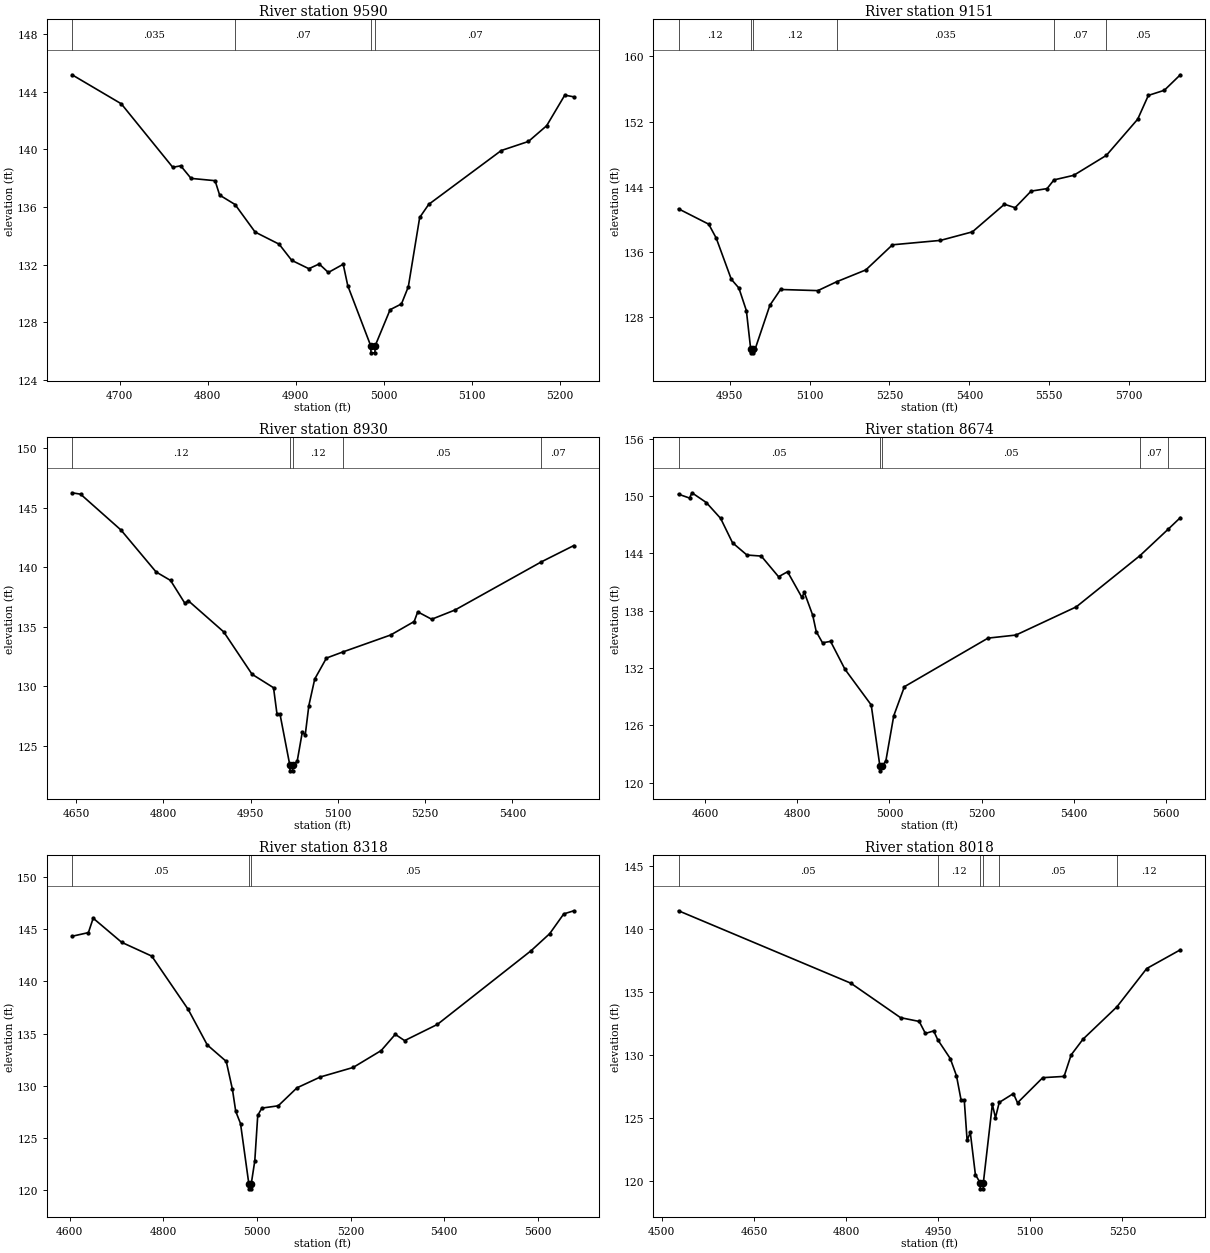
Type RM Length L Ch R = 1 ,9590    ,439,439,439
BEGIN DESCRIPTION:
TRIB 4B TO COLETO CREEK 19.0
END DESCRIPTION:
XS GIS Cut Line= 3
      2550175.02     13498175.01        2549825.       13498075.
      2549624.99       13498025.
#Sta/Elev= 30
  4645.8  145.16  4701.7  143.15  4760.2  138.75  4769.3  138.85    4781  137.98
  4808.3  137.82  4813.5  136.82    4831  136.17  4853.8  134.26  4881.1  133.42
  4895.4   132.3  4914.9  131.72  4926.6  132.05    4937  131.46  4953.9  132.03
  4959.1  130.54  4985.1  126.39  4985.5  125.89  4989.9  125.89  4990.3  126.39
  5007.2  128.88  5020.1  129.28  5027.9  130.47  5040.8  135.27  5051.1  136.18
  5133.5  139.91  5164.4  140.54  5185.1  141.63  5205.7  143.75    5216  143.63
#Mann= 4 ,-1 , 0
  4645.8    .035       0    4831     .07       0  4985.1     .05       0
  4990.3     .07       0
Bank Sta=4985.1,4990.3
XS Rating Curve= 0 ,0
Exp/Cntr=0.3,0.1

Type RM Length L Ch R = 1 ,9151    ,221,221,221
BEGIN DESCRIPTION:
TRIB 4B TO COLETO CREEK 18.0
END DESCRIPTION:
XS GIS Cut Line= 3
      2550275.02     13497925.02        2550175.       13497825.
      2549375.04       13497825.
#Sta/Elev= 30
  4854.3   141.3  4910.9  139.42    4925  137.71  4953.3  132.66  4967.5  131.59
  4981.6  128.81  4989.6  124.14    4990  123.64  4994.4  123.64  4994.8  124.14
  4998.2  124.14  5025.7  129.48  5045.7  131.41  5115.7  131.27    5151  132.36
  5205.7  133.81  5255.7  136.89  5345.7  137.43  5405.7  138.48  5465.7  141.86
  5485.7  141.44  5515.7  143.47  5545.7  143.78  5558.7  144.85  5595.7  145.41
    5657  147.86  5715.7  152.29  5735.7  155.21  5765.7  155.84  5795.7  157.74
#Mann= 6 ,-1 , 0
  4854.3     .12       0  4989.6     .05       0  4994.8     .12       0
    5151    .035       0  5558.7     .07       0    5657     .05       0
Bank Sta=4989.6,4994.8
XS Rating Curve= 0 ,0
Exp/Cntr=0.3,0.1

Type RM Length L Ch R = 1 ,8930    ,256,256,256
BEGIN DESCRIPTION:
Mapping XS c54a1801
END DESCRIPTION:
XS GIS Cut Line= 3
      2550508.74     13497729.76      2550178.92     13497604.78
      2549671.99      13497552.7
#Sta/Elev= 30
  4643.3  146.26    4658  146.14  4727.4  143.13  4787.7  139.61  4812.5   138.9
  4837.3  136.97  4842.7  137.21  4903.9  134.58  4952.6  131.02  4989.5  129.89
  4995.4   127.7  5000.5   127.7  5017.4  123.41  5017.8  122.91  5022.2  122.91
  5022.7  123.41  5030.1   123.7  5038.9  126.15    5044  125.93  5050.2  128.39
  5060.3  130.62  5080.4  132.38  5109.6  132.91  5190.9  134.32  5231.2  135.45
  5237.3  136.26  5261.3  135.64  5301.5  136.42  5449.8  140.46  5505.6  141.83
#Mann= 5 ,-1 , 0
  4643.3     .12       0  5017.4     .05       0  5022.7     .12       0
  5109.6     .05       0  5449.8     .07       0
Bank Sta=5017.4,5022.7
XS Rating Curve= 0 ,0
Exp/Cntr=0.3,0.1

Type RM Length L Ch R = 1 ,8674    ,356,356,356
BEGIN DESCRIPTION:
Mapping XS 1d155444
END DESCRIPTION:
XS GIS Cut Line= 3
      2550659.94     13497528.67      2550239.83     13497382.84
      2549600.98     13497306.46
#Sta/Elev= 30
  4542.7  150.18  4566.5  149.78  4571.8  150.33  4602.9  149.31    4634  147.65
  4659.8   145.1    4691  143.82  4722.1  143.71  4759.6  141.55  4779.1  142.07
  4810.2  139.39  4815.5  139.91  4833.7  137.52  4841.3  135.81  4854.9  134.64
  4872.4  134.79  4903.6  131.87  4960.5  128.14  4979.3  121.75  4979.7  121.25
  4984.6  121.75  4992.3   122.3  5009.4  127.01  5032.5  130.05  5213.8  135.13
  5274.3  135.45  5405.2   138.4  5543.4  143.76  5605.1  146.55  5630.8  147.73
#Mann= 5 ,-1 , 0
  4542.7     .05       0  4979.3     .05       0  4984.6     .05       0
  5543.4     .07       0  5605.1     .05       0
Bank Sta=4979.3,4984.6
XS Rating Curve= 0 ,0
Exp/Cntr=0.3,0.1

Type RM Length L Ch R = 1 ,8318    ,300,300,300
BEGIN DESCRIPTION:
Mapping XS ff207740
END DESCRIPTION:
XS GIS Cut Line= 3
      2550729.39     13497129.37      2550337.05     13497059.93
      2549663.42     13497066.87
#Sta/Elev= 30
  4604.7  144.32  4639.6  144.67  4649.8  146.05  4710.7  143.74    4775  142.42
  4852.9  137.31  4893.5  133.92  4934.1  132.34  4947.3  129.67  4954.4  127.55
  4964.6  126.39  4982.3  120.64  4982.7  120.14  4987.2  120.14  4987.6  120.64
  4995.1  122.82  5001.4  127.17  5010.2  127.87  5045.2  128.09  5085.2  129.81
  5135.2  130.85  5205.2  131.76  5265.2  133.38  5295.2  134.93  5315.2  134.33
  5385.2  135.88  5585.2  142.93  5625.2  144.57  5655.2  146.46  5676.8  146.76
#Mann= 3 ,-1 , 0
  4604.7     .05       0  4982.3     .05       0  4987.6     .05       0
Bank Sta=4982.3,4987.6
XS Rating Curve= 0 ,0
Exp/Cntr=0.3,0.1

Type RM Length L Ch R = 1 ,8018    ,281,281,281
BEGIN DESCRIPTION:
Mapping XS a5f00bc9
END DESCRIPTION:
XS GIS Cut Line= 3
      2550791.94     13496865.49      2550335.17     13496792.28
      2549991.46     13496705.48
#Sta/Elev= 30
  4527.2  141.42  4807.7  135.69  4888.7  132.96  4919.1  132.66  4929.2  131.71
  4942.7  131.91  4949.2  131.22  4969.7  129.72  4979.8  128.36  4987.4  126.41
  4992.5  126.41  4997.1  123.25  5002.3  123.87  5010.6  120.53  5018.2  119.91
  5018.7  119.41  5023.2  119.41  5023.6  119.91  5038.2  126.09  5043.3  125.04
  5049.4  126.25  5072.5  126.95  5079.2  126.22  5120.3  128.21    5155  128.31
  5166.5  130.01  5185.9  131.26  5241.1  133.82  5289.6  136.85  5344.3  138.33
#Mann= 6 ,-1 , 0
  4527.2     .05       0  4949.2     .12       0  5018.2     .05       0
  5023.6     .12       0  5049.4     .05       0  5241.1     .12       0
Bank Sta=5018.2,5023.6
XS Rating Curve= 0 ,0
Exp/Cntr=0.3,0.1

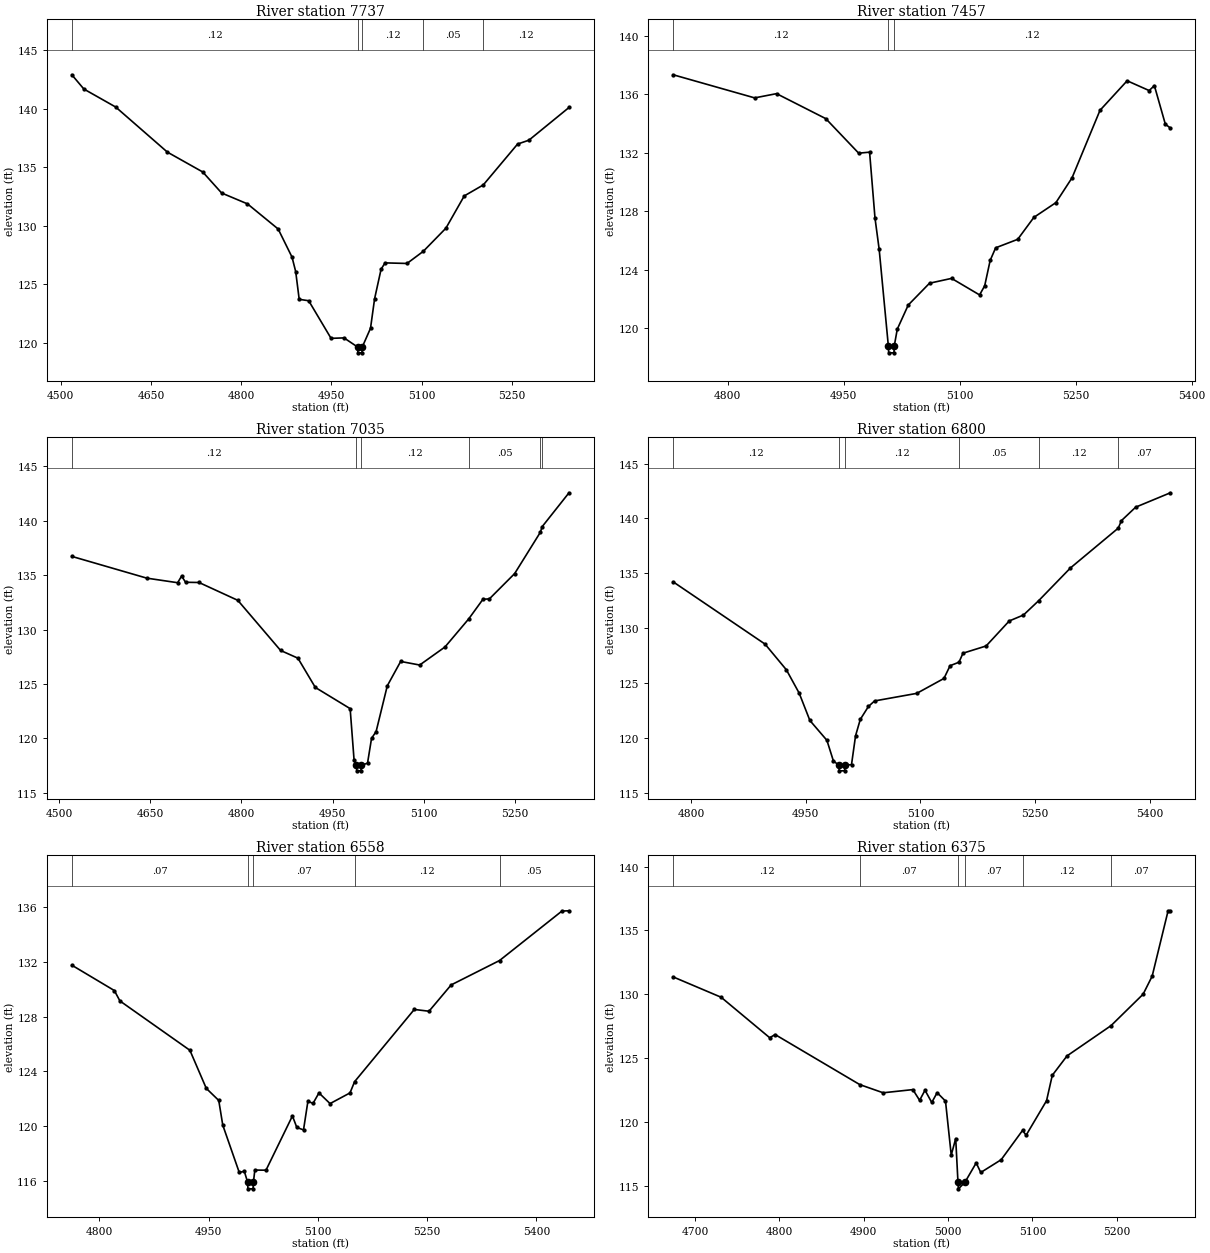
Type RM Length L Ch R = 1 ,7737    ,280,280,280
BEGIN DESCRIPTION:
TRIB 4B TO COLETO CREEK 15.0
END DESCRIPTION:
XS GIS Cut Line= 3
      2550517.59     13496108.56        2550275.       13496525.
      2549955.06     13496653.69
#Sta/Elev= 30
  4518.3  142.92  4538.3   141.7  4591.2  140.16  4677.2   136.3    4736   134.6
  4767.4   132.8  4810.4  131.87  4861.4  129.72  4884.5  127.31  4890.6  126.07
  4896.4   123.7  4912.2  123.58  4949.4  120.36  4970.9   120.4  4993.5  119.62
    4994  119.12  5000.8  119.12  5001.3  119.62    5015  121.22  5021.8  123.75
  5032.6  126.28  5039.2  126.82  5075.7  126.77  5102.8  127.81  5140.4  129.79
  5170.9  132.55  5202.5  133.49  5259.6  136.99  5278.4  137.32  5345.1  140.12
#Mann= 5 ,-1 , 0
  4518.3     .12       0  4993.5     .05       0  5001.3     .12       0
  5102.8     .05       0  5202.5     .12       0
Bank Sta=4993.5,5001.3
XS Rating Curve= 0 ,0
Exp/Cntr=0.3,0.1

Type RM Length L Ch R = 1 ,7457    ,422,422,422
BEGIN DESCRIPTION:
Mapping XS d073cd23
END DESCRIPTION:
XS GIS Cut Line= 3
      2550369.03     13496090.01      2550178.05     13496277.52
      2549932.48     13496561.13
#Sta/Elev= 30
  4729.6  137.34  4834.9  135.76  4863.2  136.05  4926.9  134.34  4969.4  131.98
  4983.5  132.05  4990.5  127.54  4995.9   125.4  5007.7  118.83  5008.2  118.33
    5015  118.33  5015.5  118.83  5019.3  119.95  5033.5   121.6    5061  123.09
  5089.5  123.42  5125.7  122.29  5132.3  122.91  5139.4  124.65  5146.5  125.51
    5175  126.09  5195.9  127.59  5224.4   128.6  5245.3   130.3  5281.4  134.91
  5316.5  136.93    5345  136.26  5351.7   136.6  5365.9  133.96  5372.4   133.7
#Mann= 3 ,-1 , 0
  4729.6     .12       0  5007.7     .05       0  5015.5     .12       0
Bank Sta=5007.7,5015.5
XS Rating Curve= 0 ,0
Exp/Cntr=0.3,0.1

Type RM Length L Ch R = 1 ,7035    ,235,235,235
BEGIN DESCRIPTION:
Mapping XS 5179baf5
END DESCRIPTION:
XS GIS Cut Line= 3
      2550208.59     13495834.22      2549827.35     13496152.52
       2549737.3     13496460.79
#Sta/Elev= 30
  4521.2  136.73  4644.5  134.73  4695.2  134.31  4701.8  134.92  4708.3  134.35
  4730.4  134.33  4794.2  132.69  4864.6  128.08  4893.1  127.37  4921.7  124.68
    4979  122.73  4985.5  117.97  4989.4  117.51  4989.9  117.01  4996.8  117.01
  4997.3  117.51  5007.6  117.72  5014.2     120  5021.7  120.62  5040.1  124.83
  5062.1  127.07  5093.4  126.74    5135   128.4    5174  130.98  5197.5  132.79
    5208  132.82  5249.6  135.15    5292  138.96  5294.8  139.46    5339  142.58
#Mann= 6 ,-1 , 0
  4521.2     .12       0  4989.4     .05       0  4997.3     .12       0
    5174     .05       0    5292     .12       0  5294.8     .05       0
Bank Sta=4989.4,4997.3
XS Rating Curve= 0 ,0
Exp/Cntr=0.3,0.1

Type RM Length L Ch R = 1 ,6800    ,242,242,242
BEGIN DESCRIPTION:
TRIB 4B TO COLETO CREEK 13.0
END DESCRIPTION:
XS GIS Cut Line= 3
      2549874.98     13495875.01        2549675.       13495975.
      2549524.99     13496375.02
#Sta/Elev= 30
  4776.4  134.22  4896.6  128.55  4924.5  126.21  4941.3  124.08  4955.3  121.59
  4977.6  119.78    4986  117.92  4993.2   117.5  4993.7     117  5000.7     117
  5001.2   117.5  5009.8  117.57  5015.1   120.2  5021.3  121.69    5032  122.87
    5040  123.37  5095.2  124.06  5130.8  125.42  5138.8  126.58  5150.5   126.9
  5155.7  127.72    5186  128.38  5216.3  130.66  5234.9   131.2  5254.7   132.5
  5296.4  135.49    5359  139.12  5363.1   139.8  5381.8  141.03  5427.2  142.34
#Mann= 6 ,-1 , 0
  4776.4     .12       0  4993.2     .05       0  5001.2     .12       0
  5150.5     .05       0  5254.7     .12       0    5359     .07       0
Bank Sta=4993.2,5001.2
XS Rating Curve= 0 ,0
Exp/Cntr=0.3,0.1

Type RM Length L Ch R = 1 ,6558    ,183,183,183
BEGIN DESCRIPTION:
Mapping XS ab49da53
END DESCRIPTION:
XS GIS Cut Line= 4
      2549747.45     13495680.32      2549539.16     13495780.99
       2549459.3     13495905.99      2549410.69     13496204.58
#Sta/Elev= 30
  4762.4  131.75  4820.7   129.9  4828.4  129.14  4924.4  125.54  4946.9  122.76
    4964  121.88  4969.5  120.08  4992.1  116.63  4999.1  116.71  5003.5  115.93
    5004  115.43  5011.1  115.43  5011.6  115.93  5013.5   116.8  5028.8  116.79
  5065.1  120.75  5071.1  119.91  5080.3  119.73  5086.3  121.81  5093.4  121.67
  5101.5  122.43  5116.7  121.65  5144.1  122.43  5150.4  123.25  5232.3  128.52
  5252.5  128.39  5282.9  130.31  5349.3  132.09  5434.9   135.7  5444.6  135.72
#Mann= 5 ,-1 , 0
  4762.4     .07       0  5003.5     .05       0  5011.6     .07       0
  5150.4     .12       0  5349.3     .05       0
Bank Sta=5003.5,5011.6
XS Rating Curve= 0 ,0
Exp/Cntr=0.3,0.1

Type RM Length L Ch R = 1 ,6375    ,372,372,372
BEGIN DESCRIPTION:
TRIB 4B TO COLETO CREEK 12.0
END DESCRIPTION:
XS GIS Cut Line= 3
      2549574.98     13495475.02        2549375.       13495725.
        2549275.     13495975.01
#Sta/Elev= 30
  4674.1  131.36  4730.9  129.77  4788.5   126.6  4794.9  126.85  4895.3  122.93
    4923  122.29  4958.2  122.54  4966.2   121.7  4972.6  122.49  4980.6  121.53
    4987   122.3  4996.9  121.64  5003.7  117.41    5009  118.71  5011.7  115.27
  5012.2  114.77  5019.8  115.27  5033.3   116.8  5038.7  116.05  5062.9  117.05
  5088.2  119.34  5092.5  118.97  5116.7  121.67  5123.5  123.66    5141  125.18
  5193.2  127.55  5231.2  130.01  5241.9  131.42  5260.8  136.54  5263.5  136.54
#Mann= 6 ,-1 , 0
  4674.1     .12       0  4895.3     .07       0  5011.7     .05       0
  5019.8     .07       0  5088.2     .12       0  5193.2     .07       0
Bank Sta=5011.7,5019.8
XS Rating Curve= 0 ,0
Exp/Cntr=0.3,0.1

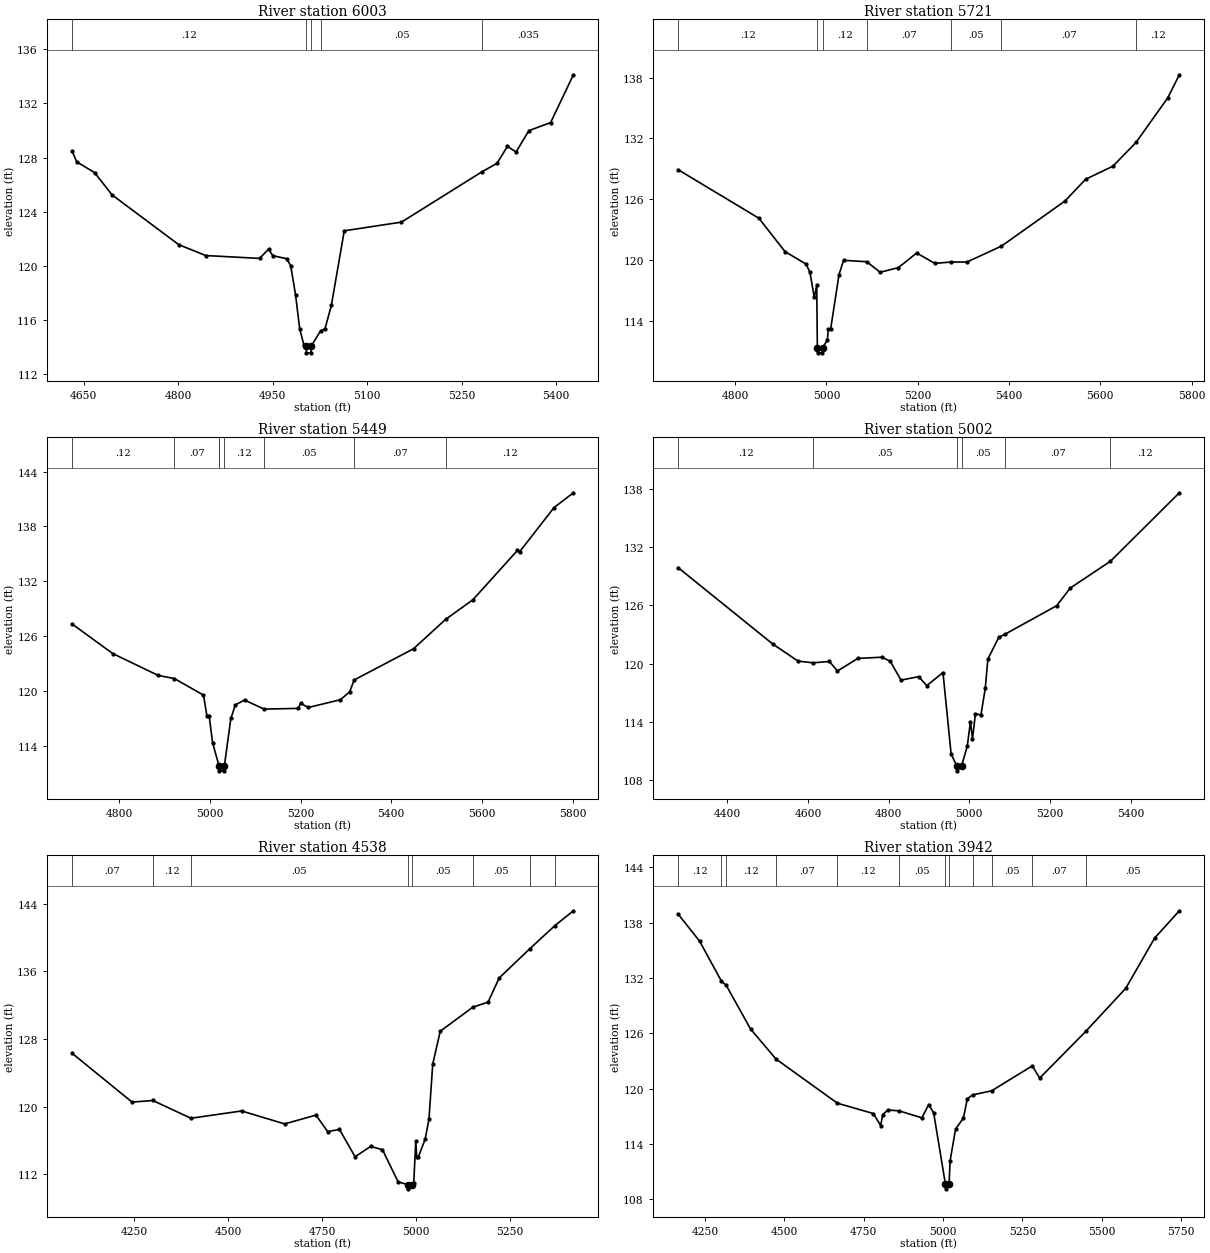
Type RM Length L Ch R = 1 ,6003    ,282,282,282
BEGIN DESCRIPTION:
Mapping XS 86c5134b
END DESCRIPTION:
XS GIS Cut Line= 3
      2549316.92     13495346.98      2549066.94     13495635.16
      2549004.43     13496044.92
#Sta/Elev= 30
  4631.4  128.49  4638.7  127.69  4667.2  126.89    4695  125.24    4801  121.56
  4843.8  120.76  4929.3  120.55  4943.5  121.24  4950.1  120.75    4972  120.53
  4978.6  120.01  4986.2  117.88  4992.9  115.33  4999.5  114.15  5003.1  114.07
  5003.6  113.57  5010.7  113.57  5011.2  114.07  5025.9  115.19    5033  115.35
  5043.1  117.07  5063.6  122.59  5154.4  123.23  5282.9  126.97  5306.1  127.57
  5322.7  128.83  5336.4  128.41  5356.7  129.99  5391.3  130.59  5427.4  134.12
#Mann= 5 ,-1 , 0
  4631.4     .12       0  5003.1     .05       0  5011.2     .12       0
  5025.9     .05       0  5282.9    .035       0
Bank Sta=5003.1,5011.2
XS Rating Curve= 0 ,0
Exp/Cntr=0.3,0.1

Type RM Length L Ch R = 1 ,5721    ,272,272,272
BEGIN DESCRIPTION:
Mapping XS cdd9876c
END DESCRIPTION:
XS GIS Cut Line= 3
      2549278.71     13495246.28      2548976.66     13495381.69
      2548209.67     13495364.33
#Sta/Elev= 30
  4674.9  128.92    4852  124.13  4909.3  120.84  4955.7   119.6  4963.9  118.78
  4973.4  116.32  4978.8  117.51  4980.1  111.36  4980.6  110.86  4991.1  110.86
  4991.6  111.36    5002  112.12  5004.1  113.19  5009.2  113.19  5027.6  118.58
  5037.6  119.98  5088.6  119.84  5117.6   118.8  5157.6  119.26  5197.6   120.7
  5237.6  119.68  5272.9  119.81  5307.7  119.81  5383.4  121.38  5522.7  125.83
  5567.7  127.97  5627.7  129.26  5678.3  131.61  5747.8     136  5773.1  138.27
#Mann= 7 ,-1 , 0
  4674.9     .12       0  4980.1     .05       0  4991.6     .12       0
  5088.6     .07       0  5272.9     .05       0  5383.4     .07       0
  5678.3     .12       0
Bank Sta=4980.1,4991.6
XS Rating Curve= 0 ,0
Exp/Cntr=0.3,0.1

Type RM Length L Ch R = 1 ,5449    ,447,447,447
BEGIN DESCRIPTION:
TRIB 4B TO COLETO CREEK 10.0
END DESCRIPTION:
XS GIS Cut Line= 3
      2549225.02       13495125.        2548925.       13495125.
      2548125.05     13495224.99
#Sta/Elev= 30
  4695.6  127.36  4785.6  124.12  4885.6  121.74  4921.2   121.4  4985.6  119.59
  4993.1  117.35  4998.1  117.35  5005.7  114.38  5019.8  111.89  5020.1  111.82
  5020.6  111.32  5031.1  111.32  5031.6  111.82    5046  117.04  5056.1  118.53
  5076.2  119.05  5119.2  118.06  5194.7  118.14  5199.7  118.69  5217.3  118.24
  5287.9  119.09    5308  119.94  5318.1  121.24  5449.1  124.65  5519.7  127.85
  5580.1     130  5678.4  135.39  5683.4  135.25    5759  140.06  5801.8  141.68
#Mann= 8 ,-1 , 0
  4695.6     .12       0  4921.2     .07       0  5019.8     .12       0
  5020.1     .05       0  5031.6     .12       0  5119.2     .05       0
  5318.1     .07       0  5519.7     .12       0
Bank Sta=5020.1,5031.6
XS Rating Curve= 0 ,0
Exp/Cntr=0.3,0.1

Type RM Length L Ch R = 1 ,5002    ,464,464,464
BEGIN DESCRIPTION:
Mapping XS 3bdcf56d
END DESCRIPTION:
XS GIS Cut Line= 3
      2549387.94      13494854.1      2548641.46      13494767.3
       2548169.2     13494905.94
#Sta/Elev= 30
  4277.4  129.88  4511.9  122.03    4575  120.26  4612.1  120.08  4652.9  120.22
    4673  119.24  4723.3  120.53  4783.7  120.66  4803.9  120.23  4830.7   118.3
  4874.3  118.66  4894.5  117.73  4934.7  119.08  4954.9   110.7  4969.2  109.47
  4969.7  108.97  4980.8  109.47  4995.1  111.53  5002.9  114.04  5007.9  112.27
  5015.3  114.85  5028.9  114.71  5039.7  117.48  5046.1  120.47  5073.1   122.7
  5087.7     123    5217  125.96  5250.4  127.77    5350  130.52  5521.1  137.57
#Mann= 6 ,-1 , 0
  4277.4     .12       0  4612.1     .05       0  4969.2     .05       0
  4980.8     .05       0  5087.7     .07       0    5350     .12       0
Bank Sta=4969.2,4980.8
XS Rating Curve= 0 ,0
Exp/Cntr=0.3,0.1

Type RM Length L Ch R = 1 ,4538    ,596,596,596
BEGIN DESCRIPTION:
Mapping XS e211ac82
END DESCRIPTION:
XS GIS Cut Line= 4
      2549418.38     13494611.05      2548537.29     13494359.31
      2548420.11     13494354.97      2548150.97      13494485.2
#Sta/Elev= 30
  4085.7  126.33  4245.2  120.55  4300.3  120.74  4401.7  118.64  4536.4   119.5
  4650.8  117.97    4734  119.01  4765.2  117.06  4796.4  117.32    4838  114.09
  4879.6  115.31  4910.8  114.92  4952.4  111.12  4977.8  110.79  4978.3  110.29
  4989.4  110.79    4994  111.02  4999.4  115.92    5002     114  5005.7     114
  5024.3  116.17  5034.4  118.51  5044.4  125.04  5064.4  128.93  5151.1  131.78
  5191.6  132.38    5221  135.23  5301.8  138.66  5368.7  141.41  5418.3  143.18
#Mann= 8 ,-1 , 0
  4085.7     .07       0  4300.3     .12       0  4401.7     .05       0
  4977.8     .05       0  4989.4     .05       0  5151.1     .05       0
  5301.8    .035       0  5368.7     .05       0
Bank Sta=4977.8,4989.4
XS Rating Curve= 0 ,0
Exp/Cntr=0.3,0.1

Type RM Length L Ch R = 1 ,3942    ,868,868,868
BEGIN DESCRIPTION:
Mapping XS b9b36b48
END DESCRIPTION:
XS GIS Cut Line= 4
      2549726.51     13494515.55      2548997.36     13494090.22
       2548893.2     13494055.49      2548278.45     13494172.38
#Sta/Elev= 30
    4165  138.94    4233  135.99    4302  131.64  4316.9   131.2  4393.4  126.48
  4473.5  123.22  4667.2  118.43  4780.3  117.31  4803.5  116.01  4810.2  117.19
  4825.9  117.69  4861.9   117.6  4933.4  116.84  4954.9  118.28  4970.6  117.37
  5007.6  109.65  5008.1  109.15  5019.2  109.65  5022.2  112.16  5039.7  115.64
  5064.3  116.82  5076.6  118.91  5093.1  119.33  5153.1  119.77  5281.5  122.48
  5304.5  121.14  5450.6  126.24  5575.8  130.88  5666.8  136.32  5744.7  139.28
#Mann= 12 ,-1 , 0
    4165     .12       0    4302     .07       0  4316.9     .12       0
  4473.5     .07       0  4667.2     .12       0  4861.9     .05       0
  5007.6     .05       0  5019.2     .05       0  5093.1     .07       0
  5153.1     .05       0  5281.5     .07       0  5450.6     .05       0
Bank Sta=5007.6,5019.2
XS Rating Curve= 0 ,0
Exp/Cntr=0.3,0.1

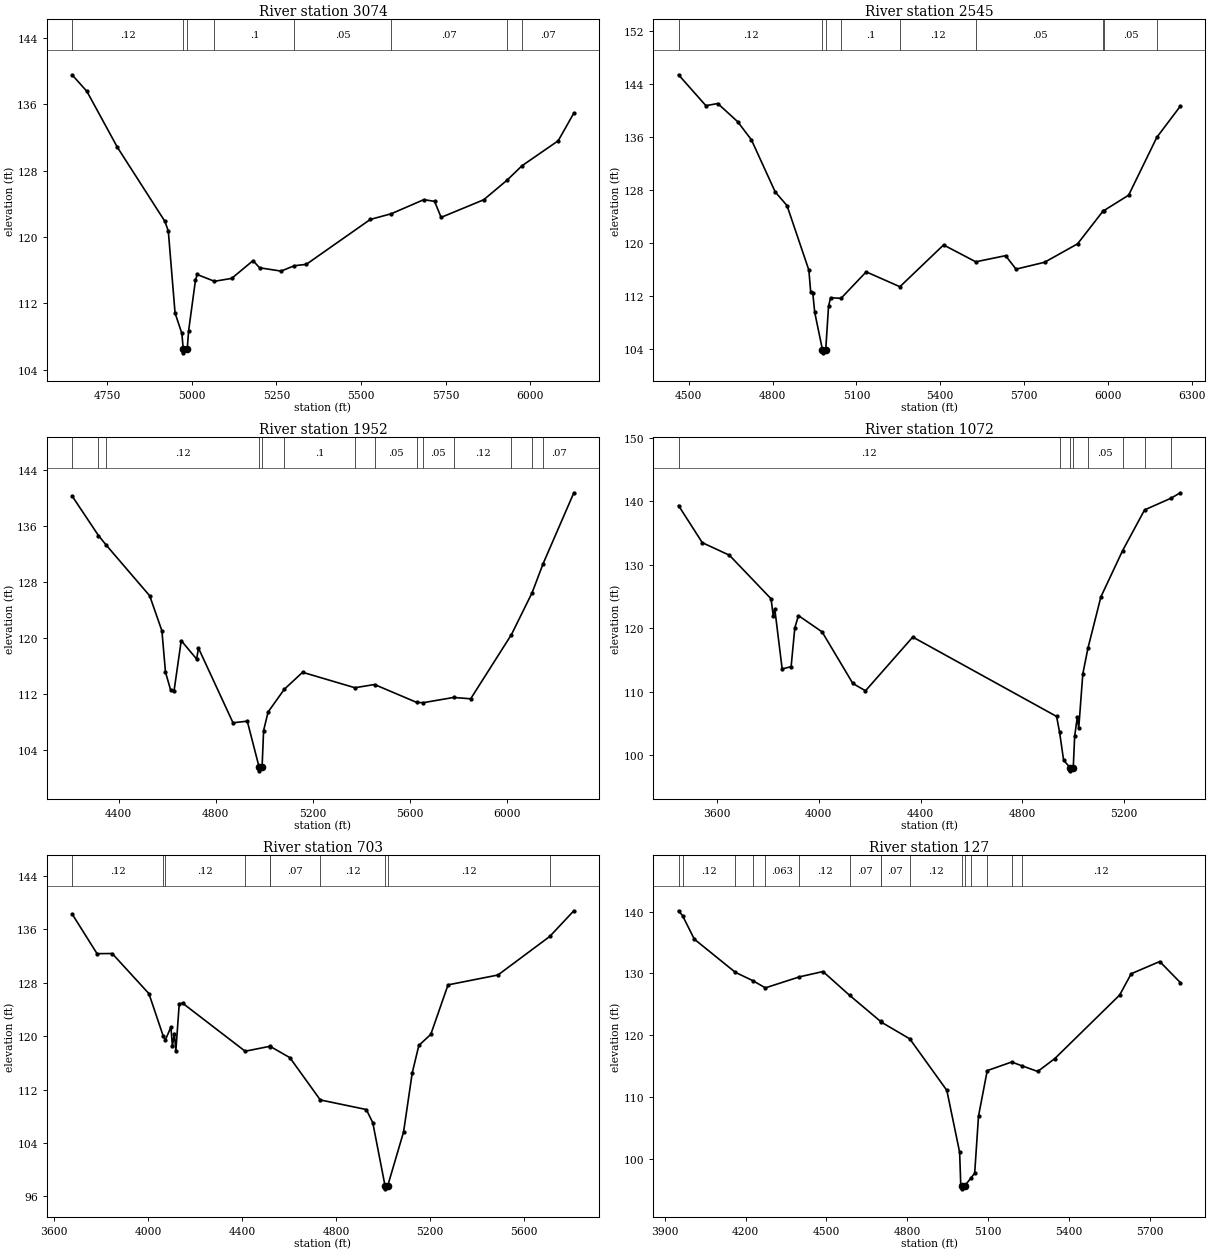
Type RM Length L Ch R = 1 ,3074    ,529,529,529
BEGIN DESCRIPTION:
Mapping XS 60bca6d9
END DESCRIPTION:
XS GIS Cut Line= 3
      2549778.65      13493582.4      2549409.69     13493608.45
        2548355.     13493964.35
#Sta/Elev= 30
  4645.8  139.56  4689.6  137.56  4779.8  130.81  4920.1  121.88  4930.2  120.72
  4950.2  110.82  4970.3  108.36  4974.3  106.52  4974.8  106.02  4986.2  106.52
  4990.3  108.69  5010.4  114.75  5015.5  115.47  5066.6  114.65  5117.6     115
  5180.6  117.14    5200  116.28  5263.4  115.88  5302.9  116.53  5337.9  116.69
  5527.2  122.11  5589.4   122.8  5685.5   124.5  5717.2  124.29  5736.5  122.36
  5862.3  124.48  5931.3  126.84  5975.4  128.58  6082.6   131.6  6128.8  134.94
#Mann= 8 ,-1 , 0
  4645.8     .12       0  4974.3     .05       0  4986.2     .12       0
  5066.6      .1       0  5302.9     .05       0  5589.4     .07       0
  5931.3     .12       0  5975.4     .07       0
Bank Sta=4974.3,4986.2
XS Rating Curve= 0 ,0
Exp/Cntr=0.3,0.1

Type RM Length L Ch R = 1 ,2545    ,593,593,593
BEGIN DESCRIPTION:
Mapping XS 6840c3fe
END DESCRIPTION:
XS GIS Cut Line= 4
      2549574.55     13492816.02      2549182.21      13493166.7
      2548814.16      13493604.2      2548207.73     13493950.73
#Sta/Elev= 30
    4463  145.45    4561  140.78  4603.6   141.1  4674.7  138.36    4724  135.61
  4809.3  127.72  4851.4  125.67  4929.6  115.91  4936.3  112.57  4943.8   112.4
  4950.6  109.52  4978.2  103.89  4978.7  103.39  4990.1  103.89  5000.1  110.42
  5007.4  111.73  5044.7  111.63  5134.9  115.64  5255.6  113.39  5411.9  119.71
  5527.2  117.16    5634  118.09  5671.4  116.05  5773.6  117.09  5891.7  119.88
  5984.1   124.9  5986.1  124.91  6074.5  127.24  6175.6     136  6259.4  140.69
#Mann= 9 ,-1 , 0
    4463     .12       0  4978.2     .05       0  4990.1     .12       0
  5044.7      .1       0  5255.6     .12       0  5527.2     .05       0
  5984.1     .12       0  5986.1     .05       0  6175.6     .07       0
Bank Sta=4978.2,4990.1
XS Rating Curve= 0 ,0
Exp/Cntr=0.3,0.1

Type RM Length L Ch R = 1 ,1952    ,880,880,880
BEGIN DESCRIPTION:
Mapping XS a270d662
END DESCRIPTION:
XS GIS Cut Line= 4
      2549271.46     13492513.93      2548679.03     13492941.44
      2548845.41     13493347.25      2548151.07     13493920.08
#Sta/Elev= 30
  4208.3  140.33  4317.3  134.66  4349.9  133.27  4528.5  126.05  4578.8  121.04
  4593.5  115.15  4614.4  112.63  4629.1  112.51  4658.5  119.65  4721.9  117.01
  4729.7  118.57    4872   107.9  4930.9  108.13  4979.9  101.53  4980.4  101.03
  4991.9  101.53  4998.2  106.79  5016.7  109.44  5083.3  112.68  5158.9  115.12
  5374.7  112.91  5455.6  113.37    5629  110.82    5656  110.77  5781.5  111.52
  5852.2  111.33  6020.3  120.51  6105.6   126.5  6150.8  130.64  6277.6  140.78
#Mann= 14 ,-1 , 0
  4208.3     .12       0  4317.3     .05       0  4349.9     .12       0
  4979.9     .05       0  4991.9     .12       0  5083.3      .1       0
  5374.7     .12       0  5455.6     .05       0    5629     .12       0
    5656     .05       0  5781.5     .12       0  6020.3     .07       0
  6105.6     .05       0  6150.8     .07       0
Bank Sta=4979.9,4991.9
XS Rating Curve= 0 ,0
Exp/Cntr=0.3,0.1

Type RM Length L Ch R = 1 ,1072    ,369,369,369
BEGIN DESCRIPTION:
Mapping XS 8694cf95
END DESCRIPTION:
XS GIS Cut Line= 3
      2549258.43     13492457.52      2548487.77     13493062.53
      2548005.11     13493927.16
#Sta/Elev= 30
  3449.9  139.33  3543.3  133.48  3649.8   131.5  3813.4  124.63  3821.5     122
  3827.9  123.01  3856.8  113.59    3892  113.94  3906.5  120.07  3920.9  121.99
  4013.7  119.42  4134.3   111.3    4184  110.14  4369.6  118.61  4934.3   106.1
  4946.1  103.59  4961.8    99.2  4987.7   98.03  4988.2   97.53  4999.7   98.03
  5005.2  102.98  5015.5  105.97  5021.2  104.26  5037.2   112.8  5057.3  116.85
  5108.2  124.94  5193.1   132.2  5279.7  138.64  5382.7  140.47  5419.9  141.34
#Mann= 8 ,-1 , 0
  3449.9     .12       0  4946.1     .07       0  4987.7     .05       0
  4999.7     .07       0  5057.3     .05       0  5193.1     .12       0
  5279.7     .07       0  5382.7     .05       0
Bank Sta=4987.7,4999.7
XS Rating Curve= 0 ,0
Exp/Cntr=0.3,0.1

Type RM Length L Ch R = 1 ,703     ,576,576,576
BEGIN DESCRIPTION:
Mapping XS eb0c3d71
END DESCRIPTION:
XS GIS Cut Line= 4
       2549243.3     13492424.92      2548360.02     13493089.01
      2547786.38     13493444.47      2547706.72     13493790.81
#Sta/Elev= 30
  3677.2  138.33  3783.5  132.37    3848  132.39  4004.2  126.38  4065.1  120.02
  4074.2  119.44  4097.9  121.36  4104.2  118.56  4112.5  120.39  4118.8  117.78
  4133.3  124.87  4147.9  124.94  4413.9  117.74  4518.9  118.48  4521.2  118.45
    4604  116.78  4733.5  110.44  4929.4     109  4956.9  107.02  5008.8   97.61
  5009.3   97.11  5020.8   97.61    5088  105.65  5124.7  114.48  5152.9  118.61
  5203.8  120.27  5277.1  127.69  5489.6  129.17    5710  134.95  5812.5   138.8
#Mann= 10 ,-1 , 0
  3677.2     .12       0  4065.1    .063       0  4074.2     .12       0
  4413.9     .07       0  4518.9     .12       0  4521.2     .07       0
  4733.5     .12       0  5008.8     .05       0  5020.8     .12       0
    5710     .07       0
Bank Sta=5008.8,5020.8
XS Rating Curve= 0 ,0
Exp/Cntr=0.3,0.1

Type RM Length L Ch R = 1 ,127     ,0,0,0
BEGIN DESCRIPTION:
TRIB 4B TO COLETO CREEK 1.0
END DESCRIPTION:
XS GIS Cut Line= 3
      2549269.04     13492343.77      2548302.24      13492751.1
      2547759.29      13493356.9
#Sta/Elev= 30
  3950.9  140.14  3965.8  139.36  4009.5  135.55  4161.6  130.19  4226.3  128.84
  4273.3  127.67    4400  129.45  4487.2  130.31  4585.7  126.47  4701.2  122.23
  4702.5  122.15  4809.3  119.42  4946.9  111.08  4994.4  101.08  4998.6   95.74
  5001.7   95.65  5002.2   95.15  5013.7   95.65  5035.4   96.85  5050.3   97.68
  5064.5  106.92  5096.9  114.28  5187.5  115.67  5226.1  115.05  5284.3  114.14
  5347.8  116.23  5588.5  126.51  5631.2  129.95  5737.3  131.93  5813.5  128.53
#Mann= 16 ,-1 , 0
  3950.9     .05       0  3965.8     .12       0  4161.6    .063       0
  4226.3     .12       0  4273.3    .063       0    4400     .12       0
  4585.7     .07       0  4701.2     .12       0  4702.5     .07       0
  4809.3     .12       0  5001.7     .05       0  5013.7     .12       0
  5035.4     .07       0  5096.9     .12       0  5187.5     .07       0
  5226.1     .12       0
Bank Sta=5001.7,5013.7
XS Rating Curve= 0 ,0
Exp/Cntr=0.3,0.1

Chan Stop Cuts=-1
Use User Specified Reach Order=0
Composite Channel Slope=5