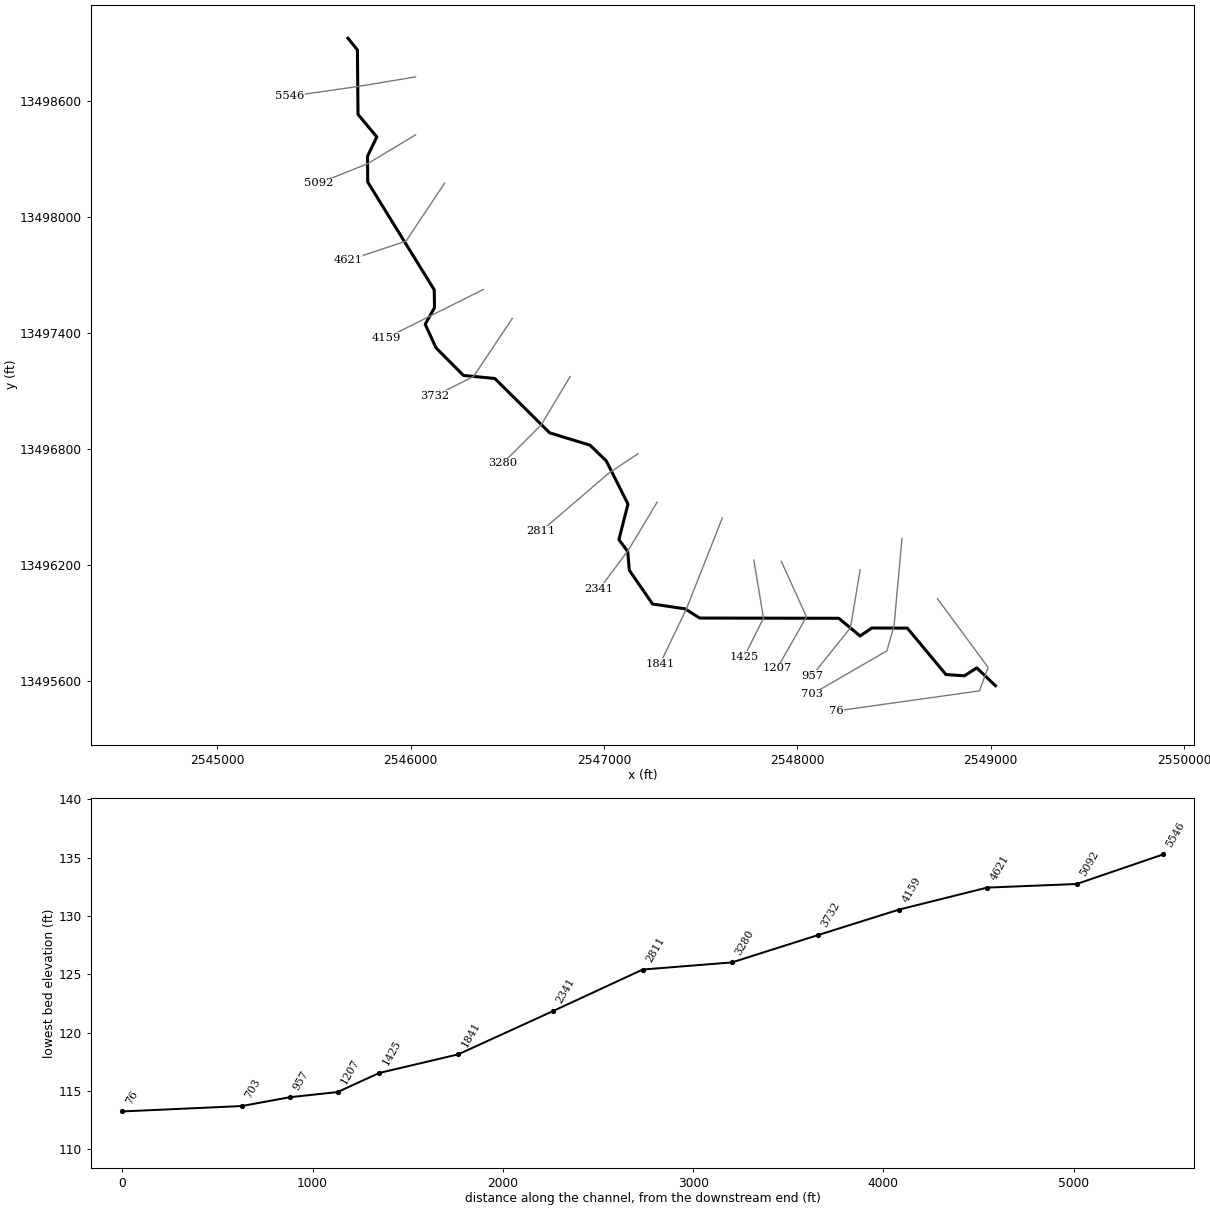
--- TRIB 4B_1 TO COLETO CREEK.prj (project) ---

Proj Title=TRIB 4B_1 TO COLETO CREEK Base Level Engineering
Current Plan=p01
Default Exp/Contr=0.3,0.1
English Units
Geom File=g01
Flow File=f01
Plan File=p01
Y Axis Title=Elevation
X Axis Title(PF)=Main Channel Distance
X Axis Title(XS)=Station
BEGIN DESCRIPTION:
TRIB 4B_1 TO COLETO CREEK
END DESCRIPTION:
DSS Export Rating Curves= 0
DSS Export Rating Curve Sorted= 0
DSS Export Volume Flow Curves= 0
DXF OffsetX= 0
DXF OffsetY= 0
DXF ScaleX= 1
DXF ScaleY= 10

--- TRIB 4B_1 TO COLETO CREEK.p01 (plan) ---

Plan Title=Multiple Run
Short Identifier=Multiple
Geom File=g01
Flow File=f01
Subcritical Flow
K Sum by GR= 0
Std Step Tol= 0.01
Critical Tol= 0.01
Num of Std Step Trials= 20
Max Error Tol= 0.3
Flow Tol Ratio= 0.001
Split Flow NTrial= 30
Split Flow Tol= 0.02
Split Flow Ratio= 0.02
Log Output Level= 0
Friction Slope Method= 1
Unsteady Friction Slope Method= 2
Unsteady Bridges Friction Slope Method= 1
Parabolic Critical Depth
Global Vel Dist=  1 , 1 , 1
Global Log Level= 0
CheckData=True
Encroach Param= -1, 0, 0, 0
BEGIN DESCRIPTION:
Multiple Run
END DESCRIPTION:

--- TRIB 4B_1 TO COLETO CREEK.f01 (steady flow) ---

Flow Title=Multiple
Number of Profiles=7
Profile Names=10-year,25-year,50-year,1pct_min,100-year,1pct_plu,500-year
River Rch & RM= TRIB 4B_1 TO COL,Reach-1,5546
     754    1210    1620    1050    2095    4180    3461
River Rch & RM= TRIB 4B_1 TO COL,Reach-1,5092
     932    1512    2039    1329    2651    5290    4433
Boundary for River Rch & Prof#=TRIB 4B_1 TO COL,Reach-1,1
Up Type=0
Dn Type=3
Dn Slope=0.005
Boundary for River Rch & Prof#=TRIB 4B_1 TO COL,Reach-1,2
Up Type=0
Dn Type=3
Dn Slope=0.005
Boundary for River Rch & Prof#=TRIB 4B_1 TO COL,Reach-1,3
Up Type=0
Dn Type=3
Dn Slope=0.005
Boundary for River Rch & Prof#=TRIB 4B_1 TO COL,Reach-1,4
Up Type=0
Dn Type=3
Dn Slope=0.005
Boundary for River Rch & Prof#=TRIB 4B_1 TO COL,Reach-1,5
Up Type=0
Dn Type=3
Dn Slope=0.005
Boundary for River Rch & Prof#=TRIB 4B_1 TO COL,Reach-1,6
Up Type=0
Dn Type=3
Dn Slope=0.005
Boundary for River Rch & Prof#=TRIB 4B_1 TO COL,Reach-1,7
Up Type=0
Dn Type=3
Dn Slope=0.005

--- TRIB 4B_1 TO COLETO CREEK.g01 (geometry) ---

Geom Title=Existing Conditions
Program Version=4.10

River Reach=TRIB 4B_1 TO COL,Reach-1
Reach XY= 30
        2545675.       13498925.      2545724.04      13498864.6
      2545727.07     13498530.86       2545824.4     13498414.38
      2545776.23      13498314.5      2545777.23     13498180.93
      2546121.33     13497623.42      2546122.81     13497530.97
      2546074.71     13497445.17      2546130.83      13497322.7
      2546272.55     13497180.47       2546434.8     13497164.52
      2546718.94     13496883.14      2546927.44     13496819.48
      2547011.39     13496738.24      2547123.91     13496514.46
      2547076.82     13496331.12      2547122.62     13496269.03
      2547130.54     13496172.58       2547251.1     13495997.71
      2547419.06     13495972.73      2547495.03     13495925.07
      2548214.57     13495923.94       2548324.9     13495832.33
      2548385.43     13495873.61      2548569.16     13495872.95
      2548768.81     13495632.75      2548864.52     13495626.27
      2548928.42     13495667.32        2549025.       13495575.

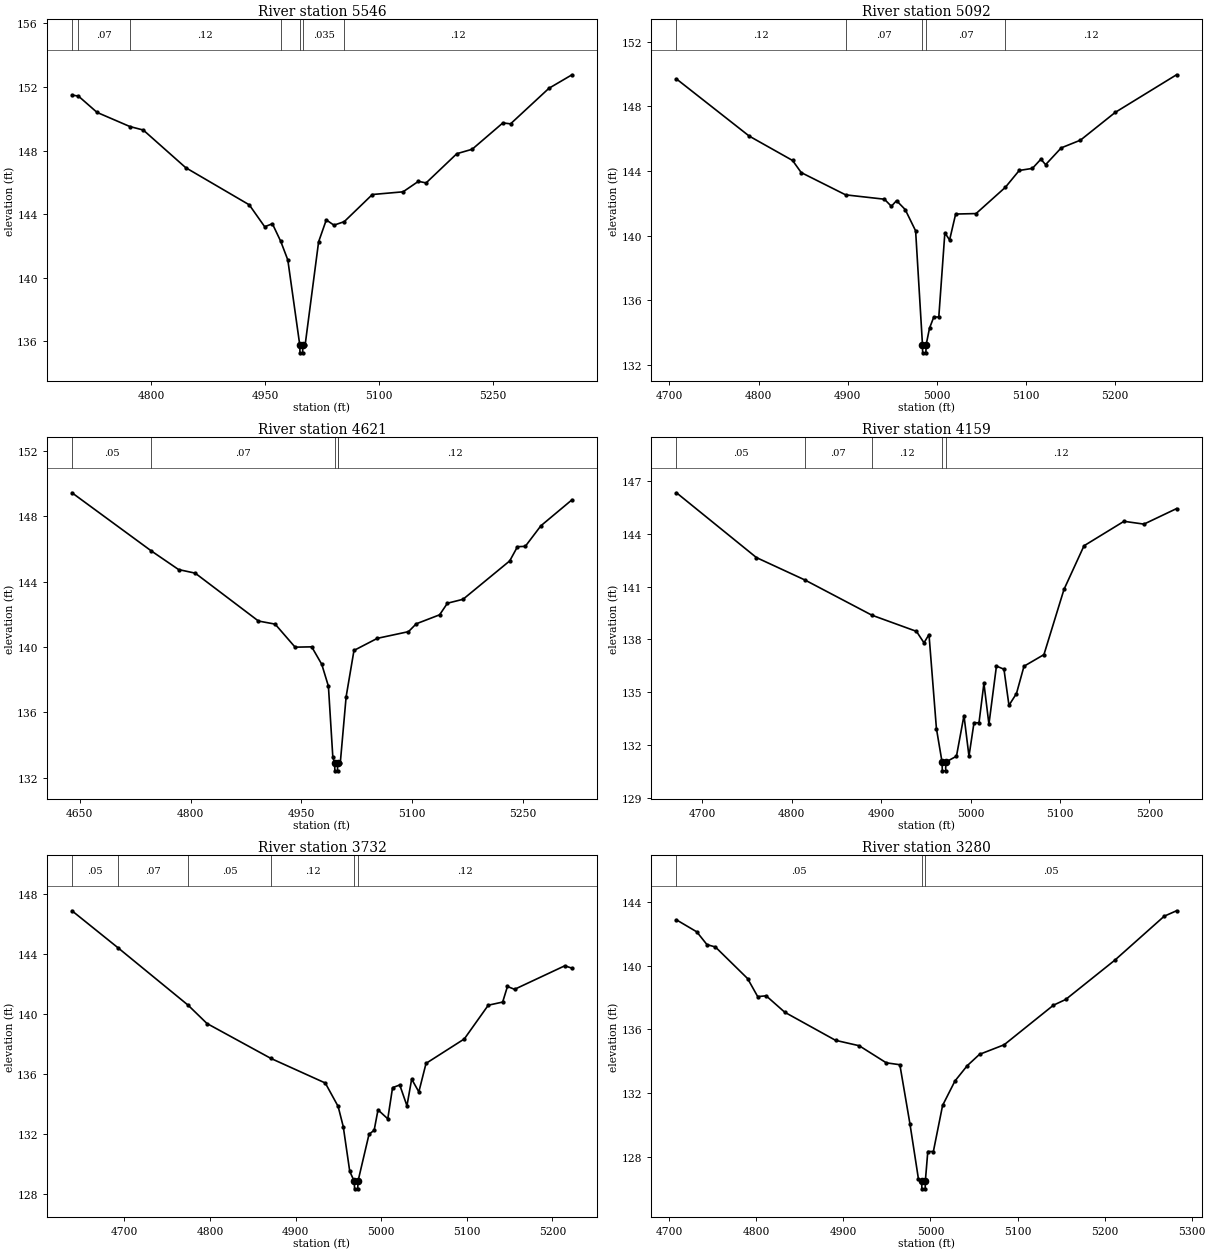
Type RM Length L Ch R = 1 ,5546    ,454,454,454
BEGIN DESCRIPTION:
TRIB 4B-1 TO COLETO CREEK 12.0
END DESCRIPTION:
XS GIS Cut Line= 3
      2546025.03       13498725.        2545725.       13498675.
      2545375.02       13498625.
#Sta/Elev= 30
  4695.8  151.49  4704.2  151.43  4728.8   150.4    4772  149.51  4789.6  149.29
  4845.4  146.92    4929  144.58  4949.3   143.2  4959.4  143.39  4970.4  142.28
  4979.7  141.11  4995.4  135.76  4995.7  135.26  4999.2  135.26  4999.5  135.76
  5002.5  135.76  5020.2  142.25  5030.3  143.63  5040.4   143.3  5053.9  143.52
  5090.9  145.23  5131.3   145.4  5151.5  146.06  5161.6  145.96    5202   147.8
  5222.2  148.08  5262.6  149.74  5272.7  149.68  5323.2  151.92  5353.5  152.77
#Mann= 7 ,-1 , 0
  4695.8     .12       0  4704.2     .07       0    4772     .12       0
  4970.4    .035       0  4995.4    .035       0  4999.5    .035       0
  5053.9     .12       0
Bank Sta=4995.4,4999.5
XS Rating Curve= 0 ,0
Exp/Cntr=0.3,0.1

Type RM Length L Ch R = 1 ,5092    ,471,471,471
BEGIN DESCRIPTION:
TRIB 4B-1 TO COLETO CREEK 11.0
END DESCRIPTION:
XS GIS Cut Line= 3
      2546024.98     13498424.99        2545775.       13498275.
      2545524.99     13498174.99
#Sta/Elev= 30
    4708   149.7  4789.6  146.16  4838.2  144.65  4847.9   143.9  4897.7  142.52
  4941.2  142.25    4949  141.81  4954.8  142.16  4964.5  141.61  4976.2  140.29
  4983.9  133.23  4984.1  132.73  4987.7  132.73    4988  133.23  4991.8  134.26
  4996.6  134.95  5002.2  134.95    5009  140.17  5014.3  139.72  5021.1  141.33
    5044  141.36  5076.9  142.99  5092.4  144.03  5107.2  144.16  5116.7  144.73
    5122  144.39  5139.5  145.43  5161.1  145.91  5200.1  147.63  5268.8  149.96
#Mann= 5 ,-1 , 0
    4708     .12       0  4897.7     .07       0  4983.9     .05       0
    4988     .07       0  5076.9     .12       0
Bank Sta=4983.9,4988
XS Rating Curve= 0 ,0
Exp/Cntr=0.3,0.1

Type RM Length L Ch R = 1 ,4621    ,462,462,462
BEGIN DESCRIPTION:
TRIB 4B-1 TO COLETO CREEK 10.0
END DESCRIPTION:
XS GIS Cut Line= 3
      2546175.03     13498175.04        2545975.       13497875.
      2545675.03     13497775.01
#Sta/Elev= 30
  4639.4  149.44  4746.8  145.88  4783.7  144.74  4806.2  144.52  4891.8  141.59
  4914.4   141.4  4941.4  139.99  4963.9  140.01  4977.5  138.94  4986.5   137.6
  4992.5  133.24  4994.9  132.92  4995.2  132.42  4998.8  132.42    4999  132.92
  4999.1  132.92  5002.6  132.92  5010.5  136.96  5021.1  139.79  5052.7  140.53
  5094.9  140.94  5105.4  141.42    5137  141.97  5147.6  142.68  5168.7  142.92
  5231.9  145.27  5242.4  146.14    5253  146.16  5274.1  147.42  5316.2  149.01
#Mann= 5 ,-1 , 0
  4639.4     .05       0  4746.8     .07       0  4994.9     .05       0
    4999     .07       0  4999.1     .12       0
Bank Sta=4994.9,4999
XS Rating Curve= 0 ,0
Exp/Cntr=0.3,0.1

Type RM Length L Ch R = 1 ,4159    ,427,427,427
BEGIN DESCRIPTION:
TRIB 4B-1 TO COLETO CREEK 9.0
END DESCRIPTION:
XS GIS Cut Line= 3
      2546374.96     13497624.98        2546075.       13497475.
      2545874.97     13497374.99
#Sta/Elev= 30
  4671.2  146.33  4760.6  142.65  4814.7  141.38  4889.6  139.38  4939.5  138.46
  4947.9  137.81  4953.5  138.28  4961.8  132.94  4968.1  131.04  4968.4  130.54
  4972.1  130.54  4972.3  131.04  4984.2  131.37  4992.6  133.68  4998.2  131.37
  5003.8  133.27  5009.4  133.27  5014.9  135.51  5020.5  133.19  5028.9  136.49
  5037.3  136.31  5042.9  134.26  5051.3  134.93  5059.7  136.48    5082  137.14
  5104.4  140.84  5126.8  143.32  5171.5  144.71  5193.8  144.55  5230.2  145.43
#Mann= 5 ,-1 , 0
  4671.2     .05       0  4814.7     .07       0  4889.6     .12       0
  4968.1     .05       0  4972.3     .12       0
Bank Sta=4968.1,4972.3
XS Rating Curve= 0 ,0
Exp/Cntr=0.3,0.1

Type RM Length L Ch R = 1 ,3732    ,452,452,452
BEGIN DESCRIPTION:
TRIB 4B-1 TO COLETO CREEK 8.0
END DESCRIPTION:
XS GIS Cut Line= 3
      2546524.98     13497474.96        2546325.       13497175.
      2546125.02     13497075.01
#Sta/Elev= 30
  4638.7   146.9  4692.5  144.43  4774.2  140.61  4796.4  139.38  4871.1  137.05
  4934.6  135.41  4949.6  133.85  4955.6   132.5  4963.2  129.51  4968.5  128.85
  4968.8  128.35  4972.5  128.35  4972.8  128.85  4985.7  131.99  4991.7  132.26
  4996.2  133.62  5007.6  133.02  5013.2   135.1  5021.6  135.28    5030  133.89
  5035.5  135.67  5043.9  134.82  5052.3  136.72    5097  138.35    5125   140.6
  5141.8  140.81  5147.4  141.85  5155.7  141.66  5214.4  143.23  5222.8  143.07
#Mann= 6 ,-1 , 0
  4638.7     .05       0  4692.5     .07       0  4774.2     .05       0
  4871.1     .12       0  4968.5     .05       0  4972.8     .12       0
Bank Sta=4968.5,4972.8
XS Rating Curve= 0 ,0
Exp/Cntr=0.3,0.1

Type RM Length L Ch R = 1 ,3280    ,469,469,469
BEGIN DESCRIPTION:
TRIB 4B-1 TO COLETO CREEK 7.0
END DESCRIPTION:
XS GIS Cut Line= 3
      2546825.01     13497175.02        2546675.       13496925.
      2546475.01     13496725.01
#Sta/Elev= 30
  4708.2  142.87  4731.5  142.12  4743.2  141.32  4752.9  141.17  4789.9  139.19
  4801.5  138.06  4811.2  138.11  4832.6  137.08  4890.9  135.32  4918.1  134.98
  4949.2  133.91  4964.8  133.79  4976.4  130.08  4986.2  126.61  4989.8  126.51
  4990.1  126.01  4993.9  126.01  4994.1  126.51  4996.9  128.35  5003.3  128.35
  5013.9  131.24  5028.1  132.77  5042.2  133.73  5056.3  134.44  5084.6  135.04
  5141.2  137.52  5155.3  137.88  5211.9  140.35  5268.5   143.1  5282.6  143.44
#Mann= 3 ,-1 , 0
  4708.2     .05       0  4989.8     .05       0  4994.1     .05       0
Bank Sta=4989.8,4994.1
XS Rating Curve= 0 ,0
Exp/Cntr=0.3,0.1

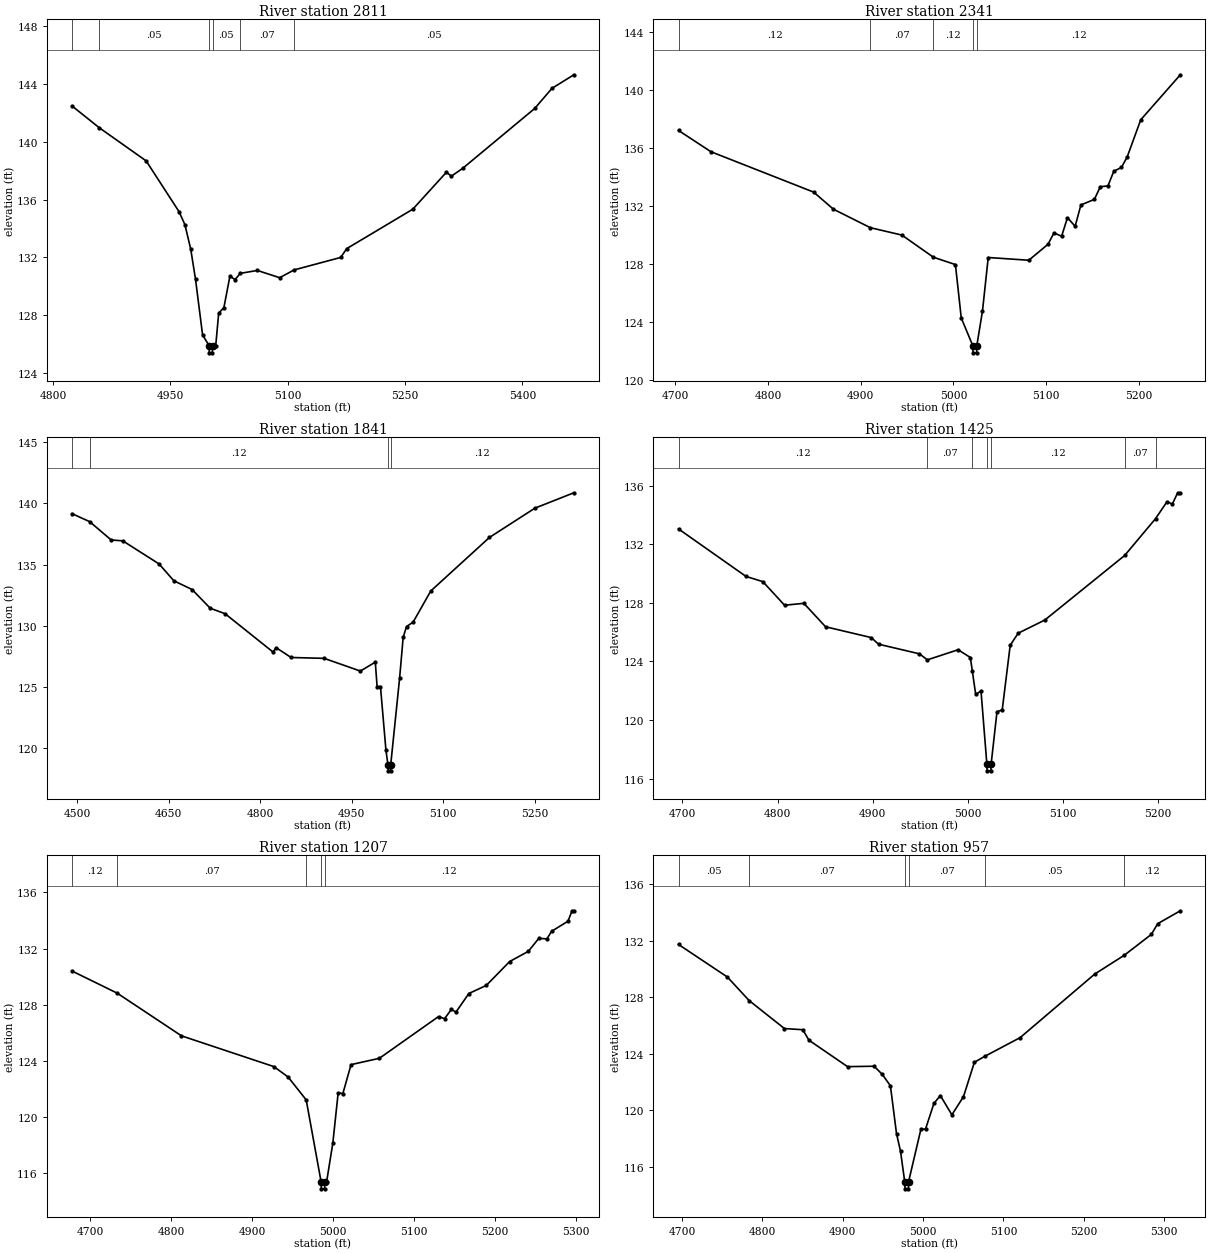
Type RM Length L Ch R = 1 ,2811    ,470,470,470
BEGIN DESCRIPTION:
TRIB 4B-1 TO COLETO CREEK 6.0
END DESCRIPTION:
XS GIS Cut Line= 3
      2547175.01     13496775.01        2547025.       13496675.
      2546674.97     13496374.98
#Sta/Elev= 30
  4824.4  142.48  4858.8  140.99  4919.1  138.68  4961.1  135.17  4968.6  134.27
  4976.1  132.56  4982.2  130.48  4991.2  126.64  4999.5   125.9  4999.8   125.4
  5003.6   125.4  5003.9   125.9    5008   125.9  5011.8  128.15  5018.4  128.52
  5026.1   130.7  5032.7  130.47  5039.3   130.9  5061.2   131.1  5089.7   130.6
  5108.3  131.14  5167.7     132  5175.4  132.61  5259.9  135.34  5302.7  137.89
  5309.3  137.63  5323.5  138.16  5415.7  142.31  5437.7   143.7  5465.7  144.64
#Mann= 6 ,-1 , 0
  4824.4     .07       0  4858.8     .05       0  4999.5     .05       0
  5003.9     .05       0  5039.3     .07       0  5108.3     .05       0
Bank Sta=4999.5,5003.9
XS Rating Curve= 0 ,0
Exp/Cntr=0.3,0.1

Type RM Length L Ch R = 1 ,2341    ,500,500,500
BEGIN DESCRIPTION:
TRIB 4B-1 TO COLETO CREEK 5.0
END DESCRIPTION:
XS GIS Cut Line= 3
      2547274.99     13496524.99        2547125.       13496275.
      2546975.02     13496075.03
#Sta/Elev= 30
  4703.4  137.22  4738.4  135.75  4849.2  132.96  4870.5  131.78  4910.4   130.5
  4944.4  129.99  4978.4  128.46  5002.2  127.95  5008.5  124.26  5020.9  122.35
  5021.2  121.85    5025  121.85  5025.3  122.35  5031.4  124.74  5037.6  128.44
  5081.4  128.25  5102.2  129.36  5108.5  130.14  5116.8  129.91  5123.1  131.19
  5131.4   130.6  5137.6  132.07  5152.2  132.46  5158.5  133.33  5166.8  133.39
  5173.1   134.4  5181.4  134.67  5187.6   135.4  5202.2  137.96  5244.9  141.07
#Mann= 5 ,-1 , 0
  4703.4     .12       0  4910.4     .07       0  4978.4     .12       0
  5020.9     .05       0  5025.3     .12       0
Bank Sta=5020.9,5025.3
XS Rating Curve= 0 ,0
Exp/Cntr=0.3,0.1

Type RM Length L Ch R = 1 ,1841    ,416,416,416
BEGIN DESCRIPTION:
Mapping XS 39630d4d
END DESCRIPTION:
XS GIS Cut Line= 3
      2547612.04     13496443.38      2547427.79     13495976.63
      2547289.28     13495687.38
#Sta/Elev= 30
  4491.4  139.16  4520.2  138.51  4555.5  137.01  4574.5  136.94    4634  135.05
  4658.3  133.67  4688.1  132.96  4717.8  131.43  4742.2  130.98  4820.7  127.85
    4826   128.2  4850.4   127.4  4904.5  127.33    4964  126.29  4988.4  127.02
  4991.4  125.02  4996.9  125.02  5005.9   119.8  5009.2  118.63  5009.5  118.13
  5013.4  118.13  5013.7  118.63  5028.3  125.72  5034.1  129.04  5039.6  129.93
  5050.4  130.29  5079.4  132.84  5175.6  137.22    5250  139.61  5313.9  140.87
#Mann= 4 ,-1 , 0
  4491.4     .07       0  4520.2     .12       0  5009.2     .05       0
  5013.7     .12       0
Bank Sta=5009.2,5013.7
XS Rating Curve= 0 ,0
Exp/Cntr=0.3,0.1

Type RM Length L Ch R = 1 ,1425    ,218,218,218
BEGIN DESCRIPTION:
TRIB 4B-1 TO COLETO CREEK 3.0
END DESCRIPTION:
XS GIS Cut Line= 3
      2547775.01     13496224.97        2547825.       13495925.
      2547725.01     13495725.01
#Sta/Elev= 30
  4695.9  133.05  4766.8  129.81  4784.6  129.45  4807.4  127.84  4827.7  127.97
  4850.5  126.37  4898.6  125.63  4906.2  125.18  4949.3  124.52  4957.6  124.11
  4989.9   124.8  5002.8  124.27  5004.9  123.33  5008.4  121.75    5014  121.98
  5020.1  117.03  5020.4  116.53  5024.3  116.53  5024.7  117.03  5030.8  120.57
  5036.3  120.69  5044.7  125.11  5053.1  125.93  5081.1  126.83  5165.1  131.24
  5197.5  133.75  5209.6  134.91  5215.2  134.75  5220.8  135.52  5223.6  135.52
#Mann= 7 ,-1 , 0
  4695.9     .12       0  4957.6     .07       0  5004.9     .12       0
  5020.1     .05       0  5024.7     .12       0  5165.1     .07       0
  5197.5     .12       0
Bank Sta=5020.1,5024.7
XS Rating Curve= 0 ,0
Exp/Cntr=0.3,0.1

Type RM Length L Ch R = 1 ,1207    ,250,250,250
BEGIN DESCRIPTION:
Mapping XS 893e388b
END DESCRIPTION:
XS GIS Cut Line= 3
       2547917.3     13496218.12      2548047.49     13495931.69
      2547896.45     13495666.07
#Sta/Elev= 30
  4677.7   130.4  4733.4  128.83  4812.9  125.79  4927.1   123.6  4944.7  122.86
  4967.1  121.23  4985.5   115.4  4985.8   114.9  4989.7   114.9  4990.1   115.4
  4992.3   115.4    5000  118.16  5006.6  121.74  5012.4  121.68  5022.5  123.74
  5057.5  124.19  5130.6  127.16  5138.1  127.01  5146.5  127.67  5152.2  127.48
  5168.1   128.8  5189.7  129.38  5218.6  131.08  5241.6   131.8  5254.6  132.73
  5264.6  132.69  5270.4  133.23  5290.7  133.95  5295.6  134.69  5297.9  134.69
#Mann= 5 ,-1 , 0
  4677.7     .12       0  4733.4     .07       0  4967.1     .12       0
  4985.5     .05       0  4990.1     .12       0
Bank Sta=4985.5,4990.1
XS Rating Curve= 0 ,0
Exp/Cntr=0.3,0.1

Type RM Length L Ch R = 1 ,957     ,254,254,254
BEGIN DESCRIPTION:
TRIB 4B-1 TO COLETO CREEK 2.0
END DESCRIPTION:
XS GIS Cut Line= 3
      2548324.99     13496174.97        2548275.       13495875.
      2548074.98     13495624.97
#Sta/Elev= 30
  4695.8  131.72  4756.6  129.42  4783.6  127.76  4827.6  125.78  4850.4   125.7
    4858  124.96  4906.1  123.09  4939.1  123.12  4949.2  122.55  4959.4  121.74
    4967  118.36    4972  117.11  4977.2  114.96  4977.6  114.46  4981.7  114.46
    4982  114.96  4997.4  118.68  5003.1  118.68  5013.5  120.49  5021.5  121.05
  5035.9  119.69  5050.3  120.97  5063.9   123.4  5076.8  123.82  5120.8  125.14
  5213.6  129.63  5250.4  130.96    5284  132.43    5292  133.19  5320.1   134.1
#Mann= 6 ,-1 , 0
  4695.8     .05       0  4783.6     .07       0  4977.2     .05       0
    4982     .07       0  5076.8     .05       0  5250.4     .12       0
Bank Sta=4977.2,4982
XS Rating Curve= 0 ,0
Exp/Cntr=0.3,0.1

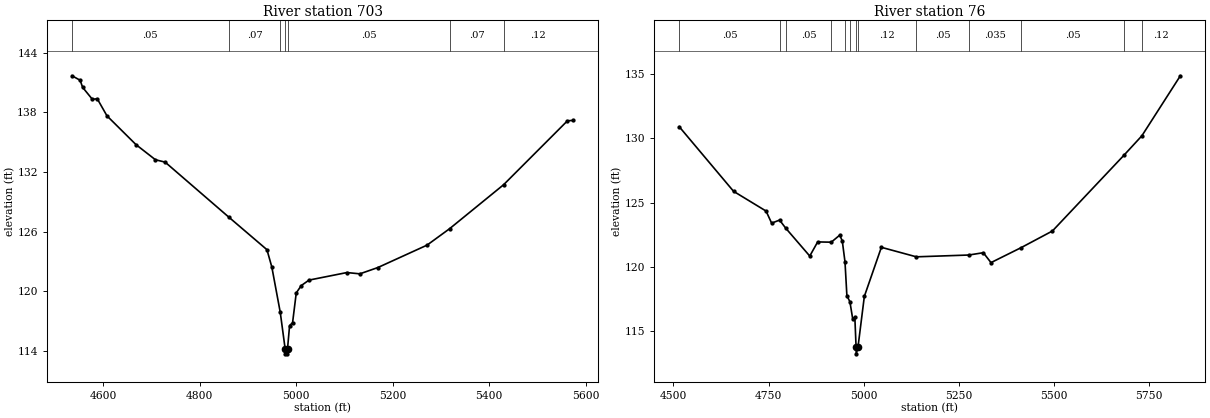
Type RM Length L Ch R = 1 ,703     ,627,627,627
BEGIN DESCRIPTION:
Mapping XS bf9adc38
END DESCRIPTION:
XS GIS Cut Line= 4
      2548541.49     13496336.96      2548500.54     13495886.55
      2548463.69     13495755.53      2548074.74     13495530.35
#Sta/Elev= 30
    4536  141.68  4552.7  141.23    4558  140.51  4578.1  139.31  4588.2  139.37
  4608.3  137.65  4668.5  134.75  4708.7  133.23  4728.8  132.99  4860.3  127.47
  4939.6  124.18  4949.7  122.44  4967.2  117.87  4977.3   114.2  4977.7   113.7
  4981.8   113.7  4982.2   114.2  4986.5  116.54  4992.7  116.84  5000.3  119.83
  5010.7  120.57  5026.7  121.12  5105.2  121.88    5132  121.75  5169.1  122.38
  5271.2  124.64  5317.8  126.29  5429.5  130.71  5561.9  137.15  5573.8  137.19
#Mann= 7 ,-1 , 0
    4536     .05       0  4860.3     .07       0  4967.2     .05       0
  4977.3     .05       0  4982.2     .05       0  5317.8     .07       0
  5429.5     .12       0
Bank Sta=4977.3,4982.2
XS Rating Curve= 0 ,0
Exp/Cntr=0.3,0.1

Type RM Length L Ch R = 1 ,76      ,0,0,0
BEGIN DESCRIPTION:
TRIB 4B-1 TO COLETO CREEK 1.0
END DESCRIPTION:
XS GIS Cut Line= 4
      2548725.03     13496024.97      2548987.08     13495669.88
      2548941.94     13495548.35      2548201.66     13495444.35
#Sta/Elev= 30
    4515  130.92    4658  125.89  4743.6  124.35  4758.2  123.41  4779.1  123.65
    4795  123.03  4858.5  120.85  4879.3  121.95  4915.1  121.93  4937.5  122.48
  4944.1  122.02  4951.2   120.4  4956.2  117.76  4964.1   117.3  4971.7  115.92
  4977.1  116.11  4980.4  113.74  4980.8  113.24  4985.3  113.74  5002.1  117.71
  5046.9  121.53  5138.9  120.79  5276.7  120.93  5315.1  121.11  5335.3  120.34
  5414.3   121.5  5496.9   122.8  5684.6  128.68  5732.3  130.21  5833.5  134.88
#Mann= 13 ,-1 , 0
    4515     .05       0  4779.1    .035       0    4795     .05       0
  4915.1     .12       0  4951.2     .05       0  4964.1     .12       0
  4980.4     .05       0  4985.3     .12       0  5138.9     .05       0
  5276.7    .035       0  5414.3     .05       0  5684.6     .07       0
  5732.3     .12       0
Bank Sta=4980.4,4985.3
XS Rating Curve= 0 ,0
Exp/Cntr=0.3,0.1

Chan Stop Cuts=-1
Use User Specified Reach Order=0
Composite Channel Slope=5